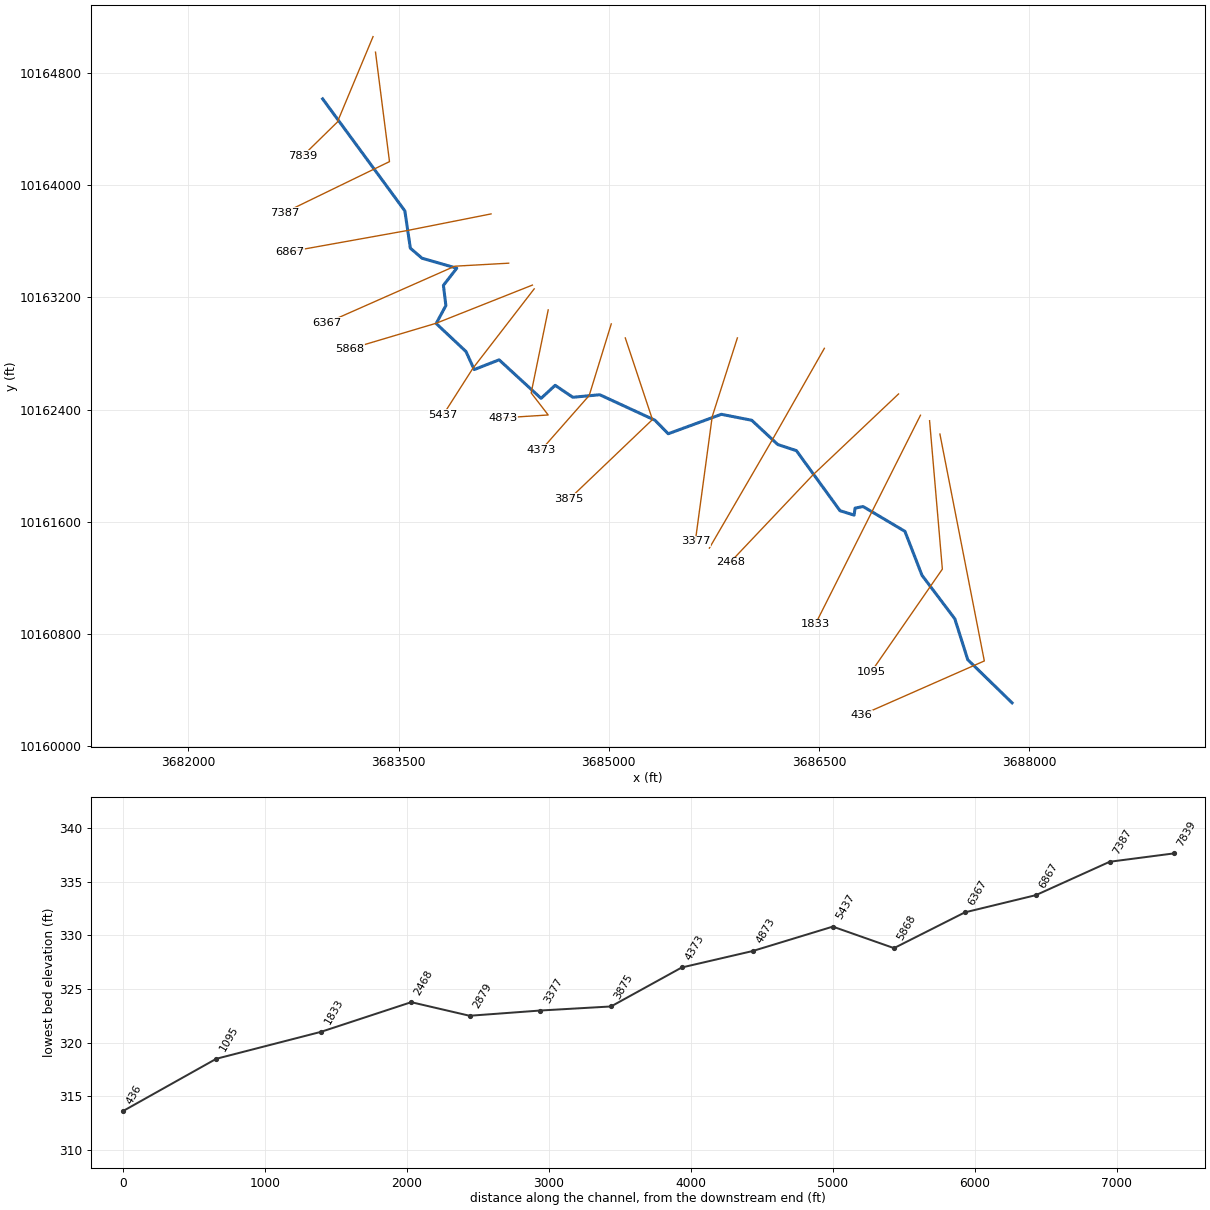
--- BUMS CREEK.prj (project) ---

Proj Title=BUMS CREEK Base Level Engineering
Current Plan=p01
Default Exp/Contr=0.3,0.1
English Units
Geom File=g01
Flow File=f01
Flow File=f02
Plan File=p01
Y Axis Title=Elevation
X Axis Title(PF)=Main Channel Distance
X Axis Title(XS)=Station
BEGIN DESCRIPTION:
BUMS CREEK
END DESCRIPTION:
DSS Export Rating Curves= 0
DSS Export Rating Curve Sorted= 0
DSS Export Volume Flow Curves= 0
DXF OffsetX= 0
DXF OffsetY= 0
DXF ScaleX= 1
DXF ScaleY= 10

--- BUMS CREEK.p01 (plan) ---

Plan Title=Multiple Run
Program Version=4.10
Short Identifier=Multiple
Geom File=g01
Flow File=f01
Subcritical Flow
K Sum by GR= 0
Std Step Tol= 0.01
Critical Tol= 0.01
Num of Std Step Trials= 20
Max Error Tol= 0.3
Flow Tol Ratio= 0.001
Split Flow NTrial= 30
Split Flow Tol= 0.02
Split Flow Ratio= 0.02
Log Output Level= 0
Friction Slope Method= 1
Unsteady Friction Slope Method= 2
Unsteady Bridges Friction Slope Method= 1
Parabolic Critical Depth
Global Vel Dist= 1 , 1 , 1
Global Log Level= 0
CheckData=True
Encroach Param=-1 ,0,0, 0
BEGIN DESCRIPTION:
Multiple Run
END DESCRIPTION:
Computation Interval=1HOUR
Output Interval=1HOUR
Run HTab= 0
Run UNet= 0
Run PostProcess= 0
Run WQNet= 0
UNET Theta= 1
UNET Theta Warmup= 1
UNET ZTol= 0.02
UNET ZSATol= 0.05
UNET MxIter= 20
UNET MaxInSteps= 0
UNET DtIC= 0
UNET DtMin= 0
UNET MaxCRTS= 20
UNET WFStab= 2
UNET SFStab= 1
UNET WFX= 1
UNET SFX= 1
UNET DSS MLevel= 4
UNET DZMax Abort= 100
UNET Convert EG Bridges= 0
UNET Use Existing IB Tables=-1
UNET Froude Reduction=False
UNET Froude Limit= 1
UNET Froude Power= 10
UNET Time Slicing=0,0, 5
UNET Junction Losses=0
Instantaneous Interval=1HOUR
Write IC File= 0
Write IC File at Sim End=0
Echo Input=False
Echo Parameters=False
Echo Output=False
Write Detailed= 0
WQ AD Non Conservative
WQ ULTIMATE=-1
WQ Max Comp Step=1HOUR
WQ Output Interval=15MIN
WQ Output Selected Increments= 0
WQ Output face flow=0
WQ Output face velocity=0
WQ Output face area=0
WQ Output face dispersion=0
WQ Output cell volume=0
WQ Output cell surface area=0
WQ Output cell continuity=0
WQ Output cumulative cell continuity=0
WQ Output face conc=0
WQ Output face dconc_dx=0
WQ Output face courant=0
WQ Output face peclet=0
WQ Output face adv mass=0
WQ Output face disp mass=0
WQ Output cell mass=0
WQ Output cell source sink temp=0
WQ Output cell source sink nsm=0
WQ Output MaxMinRange=-1
WQ Daily Max Min Mean=-1
WQ Daily Range=0
WQ Daily Time=0
WQ Create Restart=0
WQ Fixed Restart=0
WQ System Summary=0
WQ Use Fixed Temperature=0
Sorting and Armoring Iterations= 10
XS Update Threshold= 0.02
Hydraulics Update Threshold= 0.02
Energy Slope Method= 1
Volume Change Method= 0
XS Weighting Method= 0
Number of US Weighted Cross Sections= 1
Number of DS Weighted Cross Sections= 1
Upstream XS Weight=0.25
Main XS Weight=0.5
Downstream XS Weight=0.25
Number of DS XS's Weighted with US Boundary= 1
Upstream Boundary Weight= 1
Weight of XSs Associated with US Boundary= 0
Number of US XS's Weighted with DS Boundary= 1
Downstream Boundary Weight= 0.5
Weight of XSs Associated with DS Boundary= 0.5
Sediment Output Level= 4
Mass or Volume Output= 0
Output Increment Type= 1
Profile and TS Output Increment= 10
XS Output Flag= 0
XS Output Increment= 10
Disregard all LS=0
Disregard all Conn=0
Disregard all Breaches=0
Disregard all Pumps=0

--- BUMS CREEK.f01 (steady flow) ---

Flow Title=Multiple
Program Version=4.10
Number of Profiles= 7
Profile Names=10-year,25-year,50-year,1pct_min,100-year,1pct_plu,500-year
River Rch & RM=BUMS CREEK,Reach-1         ,7839
     574     784    1066     477    1442    4355    2728
River Rch & RM=BUMS CREEK,Reach-1         ,6867
    1065    1481    2036     918    2772    8371    5322
Boundary for River Rch & Prof#=BUMS CREEK,Reach-1         , 1
Up Type= 0
Dn Type= 3
Dn Slope=0.0075
Boundary for River Rch & Prof#=BUMS CREEK,Reach-1         , 2
Up Type= 0
Dn Type= 3
Dn Slope=0.0075
Boundary for River Rch & Prof#=BUMS CREEK,Reach-1         , 3
Up Type= 0
Dn Type= 3
Dn Slope=0.0075
Boundary for River Rch & Prof#=BUMS CREEK,Reach-1         , 4
Up Type= 0
Dn Type= 3
Dn Slope=0.0075
Boundary for River Rch & Prof#=BUMS CREEK,Reach-1         , 5
Up Type= 0
Dn Type= 3
Dn Slope=0.0075
Boundary for River Rch & Prof#=BUMS CREEK,Reach-1         , 6
Up Type= 0
Dn Type= 3
Dn Slope=0.0075
Boundary for River Rch & Prof#=BUMS CREEK,Reach-1         , 7
Up Type= 0
Dn Type= 3
Dn Slope=0.0075
DSS Import GetInterval= 0
DSS Import GetPeak= 0
DSS Import FillOption= 0

--- BUMS CREEK.f02 (steady flow) ---

Flow Title=Orig_BLE_Flows
Program Version=4.10
Number of Profiles= 7
Profile Names=10-year,25-year,50-year,1pct_min,100-year,1pct_plu,500-year
River Rch & RM=BUMS CREEK,Reach-1         ,7839
     574     769     927     367    1109    3349    1586
River Rch & RM=BUMS CREEK,Reach-1         ,6867
    1065    1452    1770     706    2132    6439    3094
Boundary for River Rch & Prof#=BUMS CREEK,Reach-1         , 1
Up Type= 0
Dn Type= 3
Dn Slope=0.0075
Boundary for River Rch & Prof#=BUMS CREEK,Reach-1         , 2
Up Type= 0
Dn Type= 3
Dn Slope=0.0075
Boundary for River Rch & Prof#=BUMS CREEK,Reach-1         , 3
Up Type= 0
Dn Type= 3
Dn Slope=0.0075
Boundary for River Rch & Prof#=BUMS CREEK,Reach-1         , 4
Up Type= 0
Dn Type= 3
Dn Slope=0.0075
Boundary for River Rch & Prof#=BUMS CREEK,Reach-1         , 5
Up Type= 0
Dn Type= 3
Dn Slope=0.0075
Boundary for River Rch & Prof#=BUMS CREEK,Reach-1         , 6
Up Type= 0
Dn Type= 3
Dn Slope=0.0075
Boundary for River Rch & Prof#=BUMS CREEK,Reach-1         , 7
Up Type= 0
Dn Type= 3
Dn Slope=0.0075
DSS Import GetInterval= 0
DSS Import GetPeak= 0
DSS Import FillOption= 0

--- BUMS CREEK.g01 (geometry) ---

Geom Title=Existing Conditions
Program Version=4.10

River Reach=BUMS CREEK      ,Reach-1
Reach XY= 30
      3682958.23     10164616.84      3683544.82     10163817.58
      3683584.08      10163551.4       3683667.5     10163479.74
      3683915.35     10163408.48      3683820.05     10163286.18
      3683837.58     10163141.93      3683768.49     10163013.77
      3683981.21     10162813.82      3684039.73       10162685.
      3684217.43     10162754.71      3684516.79     10162479.64
      3684617.59     10162572.78      3684743.31     10162487.43
      3684935.79     10162505.51      3685329.79     10162323.61
      3685424.35     10162227.14      3685803.44     10162365.96
      3686020.46     10162323.16      3686206.63      10162149.9
      3686338.78     10162106.73      3686650.06     10161678.12
      3686750.68     10161646.44       3686757.7     10161696.35
      3686814.99     10161707.63      3687113.61     10161530.55
      3687235.13     10161217.18      3687469.51     10160906.42
      3687561.92     10160614.61      3687878.23     10160306.84

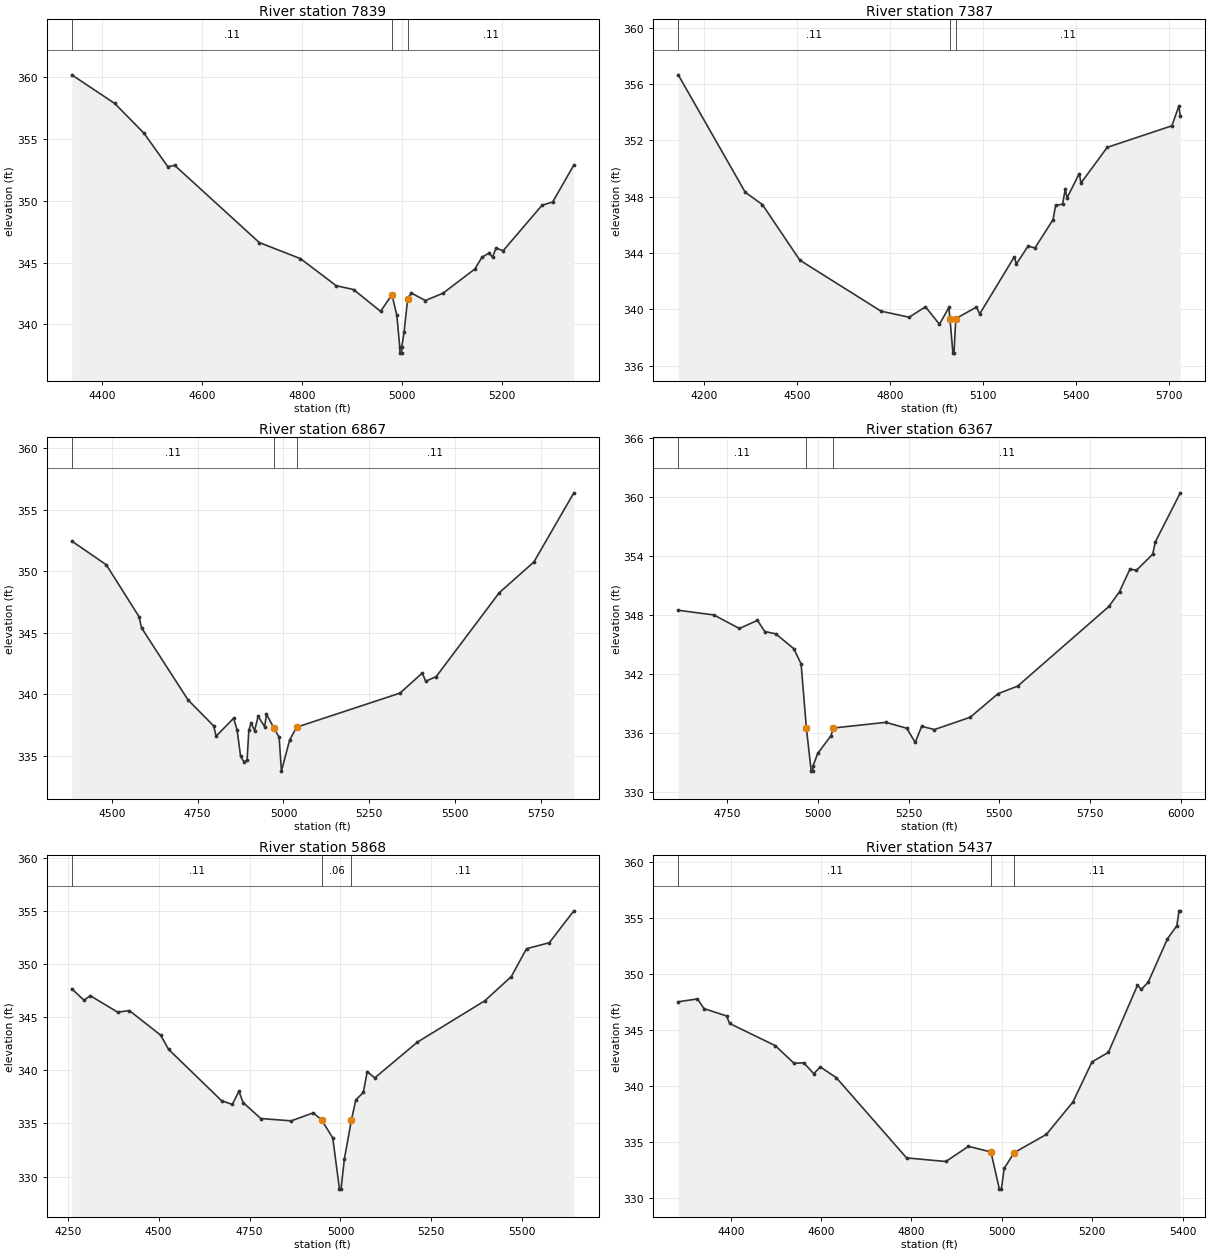
Type RM Length L Ch R = 1 ,7839    ,452,452,452
BEGIN DESCRIPTION:
BUMS CREEK 12.0
END DESCRIPTION:
XS GIS Cut Line= 3
      3683317.84     10165061.05      3683063.37     10164451.53
      3682817.82     10164211.04
#Sta/Elev= 30
  4339.5   360.2  4425.5  357.88    4484  355.47  4531.6  352.77  4545.4  352.87
  4714.6  346.62  4796.9  345.32  4868.3  343.13    4903  342.82  4957.2  341.05
  4979.8   342.4  4989.7  340.72  4995.5  338.17  4995.8  337.67  4999.3  337.67
  4999.5  338.17  5004.3   339.4  5011.3  342.07  5018.4  342.54  5046.7  341.93
    5082  342.52  5145.7  344.48  5159.9  345.43    5174  345.77    5181  345.44
  5188.1  346.18  5202.3  345.96    5280  349.64  5301.3   349.9  5343.7   352.9
#Mann= 3 , 0 , 0
  4339.5     .11       0  4979.8     .06       0  5011.3     .11       0
Bank Sta=4979.8,5011.3
XS Rating Curve= 0 ,0
Exp/Cntr=0.3,0.1

Type RM Length L Ch R = 1 ,7387    ,520,520,520
BEGIN DESCRIPTION:
Mapping XS 634347e9
END DESCRIPTION:
XS GIS Cut Line= 3
      3683335.41     10164950.43      3683435.24     10164169.19
       3682685.9     10163805.35
#Sta/Elev= 30
  4115.9  356.65  4332.2  348.31  4387.5  347.44  4508.4  343.49  4770.5  339.87
  4861.3  339.44  4913.9  340.18  4959.1  338.94  4989.5  340.13    4993339.3377
  5002.5  336.89    5006  336.89  5011.8  339.34  5078.5  340.16  5088.9  339.67
  5200.7  343.73  5207.3  343.22  5245.2  344.49  5267.4  344.36  5325.7  346.37
  5334.1  347.38  5356.4  347.47  5365.2  348.53  5370.8  347.91  5410.4  349.64
  5415.9  348.97  5500.6   351.5  5709.2  353.03  5731.8  354.43  5736.5  353.74
#Mann= 3 , 0 , 0
  4115.9     .11       0    4993     .06       0  5011.8     .11       0
Bank Sta=4993,5011.8
XS Rating Curve= 0 ,0
Exp/Cntr=0.3,0.1

Type RM Length L Ch R = 1 ,6867    ,500,500,500
BEGIN DESCRIPTION:
BUMS CREEK 11.0
END DESCRIPTION:
XS GIS Cut Line= 3
      3684160.05     10163795.92      3683555.49     10163676.18
      3682723.39     10163526.82
#Sta/Elev= 30
  4383.7  352.47  4484.3  350.54  4579.6  346.32  4586.8  345.42  4722.4  339.55
  4796.7  337.45  4803.9  336.61  4854.9  338.07  4865.1  337.11  4875.3  334.96
  4885.5   334.5  4894.1  334.68  4899.2  337.09  4905.8  337.68    4916  337.07
  4926.2  338.23  4945.3  337.38  4950.4  338.39 4971.89337.2921  4987.4  336.53
  4994.1  333.77  5017.9  336.29  5038.2  337.34  5339.1  340.11    5404  341.74
  5414.2  341.08  5444.6  341.45  5627.9  348.26  5729.1  350.77  5845.4  356.39
#Mann= 3 , 0 , 0
  4383.7     .11       0 4971.89     .06       0  5038.2     .11       0
Bank Sta=4971.89,5038.2
XS Rating Curve= 0 ,0
Exp/Cntr=0.3,0.1

Type RM Length L Ch R = 1 ,6367    ,499,499,499
BEGIN DESCRIPTION:
BUMS CREEK 10.0
END DESCRIPTION:
XS GIS Cut Line= 3
      3684285.95     10163444.36      3683901.55     10163422.84
      3682988.15     10163018.99
#Sta/Elev= 30
    4615  348.48  4713.3     348  4783.4  346.63  4833.4  347.45  4853.5  346.32
  4883.5  346.09  4933.6  344.58  4953.6  343.03 4968.17336.5305  4981.5  332.16
  4985.8  332.16  4986.2  332.66  4999.3  333.95  5036.4  335.77  5041.9  336.53
  5187.1  337.11  5244.7  336.51    5268  335.07  5285.8   336.7  5321.1  336.38
  5419.5  337.62  5496.1  340.01  5550.7  340.79  5802.2  348.87  5831.2  350.37
    5860  352.66  5877.8  352.53  5922.5  354.16  5929.8  355.41  5998.7  360.39
#Mann= 3 , 0 , 0
    4615     .11       0 4968.17     .06       0  5041.9     .11       0
Bank Sta=4968.17,5041.9
XS Rating Curve= 0 ,0
Exp/Cntr=0.3,0.1

Type RM Length L Ch R = 1 ,5868    ,431,431,431
BEGIN DESCRIPTION:
BUMS CREEK 9.0
END DESCRIPTION:
XS GIS Cut Line= 3
      3684455.19     10163288.11      3683768.25     10163015.67
      3683153.07     10162832.37
#Sta/Elev= 30
    4261  347.66  4294.7  346.58  4311.9  347.01  4387.2  345.46  4419.5  345.61
  4505.4   343.3  4527.1  341.97  4672.9  337.14  4702.6  336.78  4720.7  338.03
  4732.3  336.96  4780.9  335.46  4864.6  335.24  4925.1  335.99  4948.3  335.32
  4978.9  333.63  4997.3  328.82  5001.6  328.82  5010.8  331.67    5030  335.29
  5042.2  337.21    5063  337.92  5073.6  339.88  5094.3  339.28  5211.5  342.64
  5396.9  346.53    5470  348.81  5511.7  351.43  5574.3  351.99  5641.9  354.99
#Mann= 3 , 0 , 0
    4261     .11       0  4948.3     .06       0    5030     .11       0
Bank Sta=4948.3,5030
XS Rating Curve= 0 ,0
Exp/Cntr=0.3,0.1

Type RM Length L Ch R = 1 ,5437    ,564,564,564
BEGIN DESCRIPTION:
BUMS CREEK 8.0
END DESCRIPTION:
XS GIS Cut Line= 3
      3684467.88      10163261.1      3684029.86     10162693.49
      3683817.87      10162361.1
#Sta/Elev= 30
  4283.9  347.51  4326.5  347.77    4341   346.9  4390.8  346.25  4397.6  345.58
  4498.6  343.61  4540.3  342.03  4561.8  342.08  4583.8  341.11  4598.3  341.71
  4633.6  340.76  4789.3  333.61  4876.3  333.29  4926.2  334.64    4976  334.14
  4994.6  330.83    4999  330.83  5005.3  332.67    5027  334.07  5098.6   335.7
  5157.3  338.58  5199.7  342.16    5236  343.01  5300.3  348.98  5308.8  348.62
    5324  349.25  5366.4   353.1  5387.5  354.29  5392.2  355.61  5395.1  355.61
#Mann= 3 , 0 , 0
  4283.9     .11       0    4976     .06       0    5027     .11       0
Bank Sta=4976,5027
XS Rating Curve= 0 ,0
Exp/Cntr=0.3,0.1

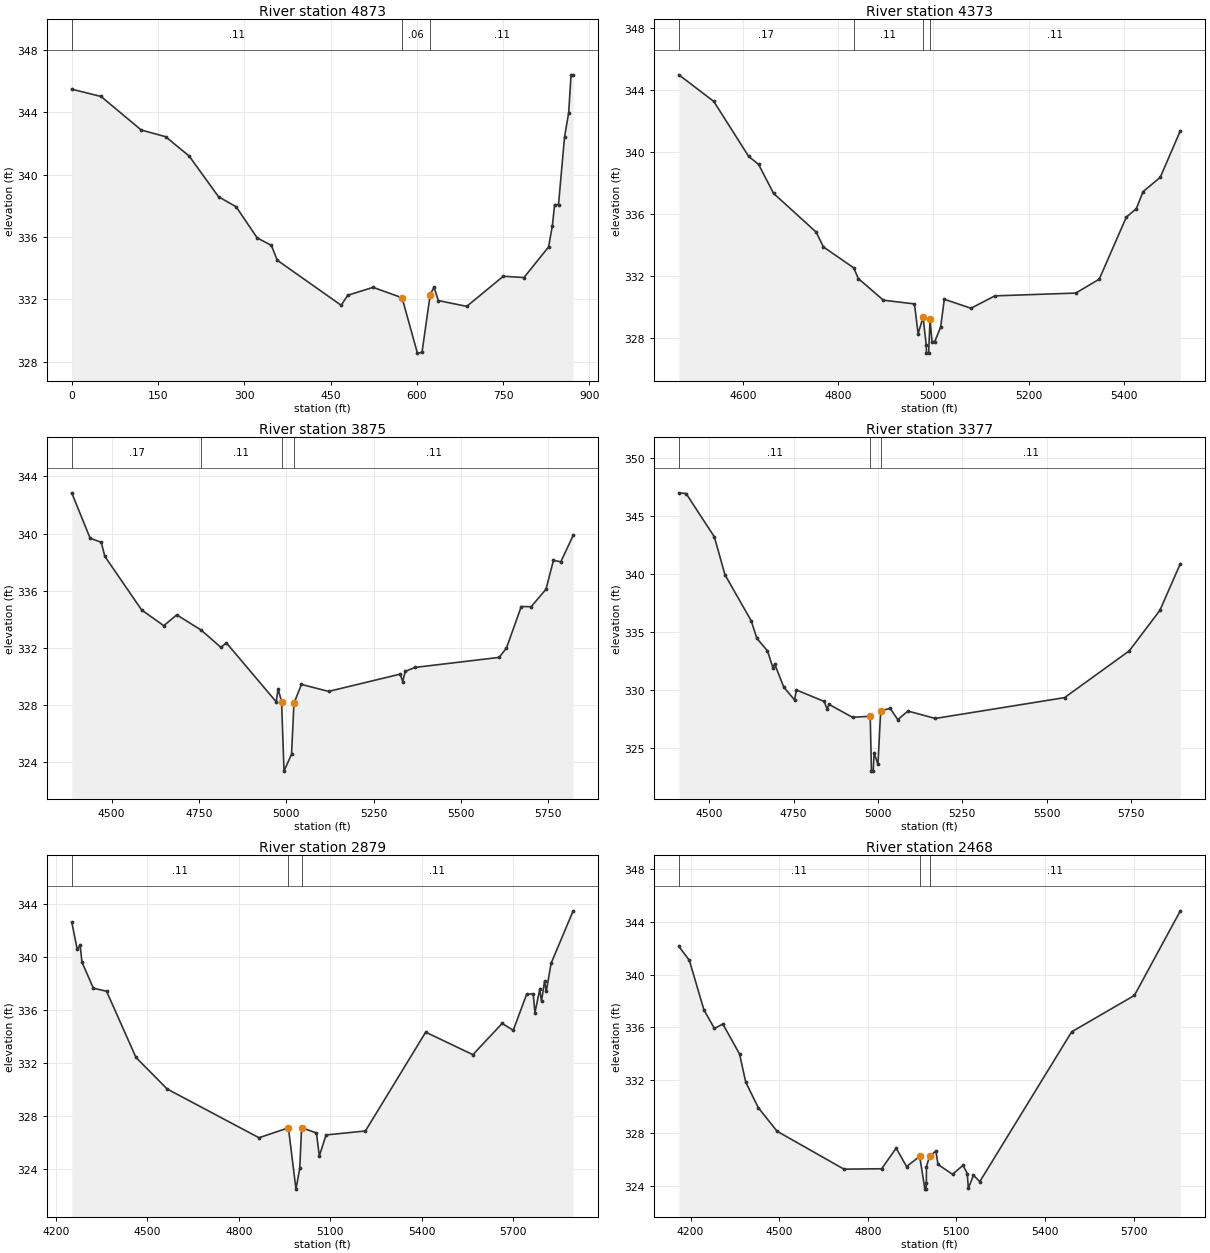
Type RM Length L Ch R = 1 ,4873    ,500,500,500
BEGIN DESCRIPTION:
BUMS CREEK 7.0
END DESCRIPTION:
XS GIS Cut Line= 4
      3684567.85     10163111.07      3684446.19     10162518.54
      3684567.85     10162361.07      3684247.06     10162340.92
#Sta/Elev= 30
       0  345.48      51  345.01   120.9  342.86   163.3  342.43   204.2  341.19
   255.2  338.58   285.8  337.94   322.4  335.94   347.1  335.46   357.3  334.51
   468.4  331.62   479.8  332.26   523.9  332.77   574.3   332.1     601  328.55
     609   328.6   623.2   332.3   629.9  332.78   637.4  331.92   686.8  331.55
   750.3  333.48   786.3   333.4     829  335.36   835.7  336.73   839.5  338.07
   846.3  338.07   856.8  342.41     864  343.97   868.1   346.4   871.8   346.4
#Mann= 3 ,-1 , 0
       0     .11       0   574.3     .06       0   623.2     .11       0
Bank Sta=574.3,623.2
XS Rating Curve= 0 ,0
Exp/Cntr=0.3,0.1

Type RM Length L Ch R = 1 ,4373    ,498,498,498
BEGIN DESCRIPTION:
BUMS CREEK 6.0
END DESCRIPTION:
XS GIS Cut Line= 3
      3685017.85     10163011.08      3684860.48     10162500.37
      3684517.85     10162111.07
#Sta/Elev= 30
  4465.6  344.99  4538.9  343.27  4612.1  339.72    4633   339.2  4664.4  337.33
  4753.8  334.83  4769.1  333.87  4832.7  332.52  4842.3  331.83    4895  330.43
  4960.3  330.19  4967.9  328.26  4978.3  329.33  4985.1  327.51  4985.5  327.01
    4990  327.01    4993  329.23    4997  327.76  5002.9  327.76  5015.3   328.7
  5022.9  330.49    5079  329.91  5129.1  330.71    5299  330.89  5348.3  331.79
  5405.2   335.8  5426.1  336.34  5440.3  337.44  5476.4  338.37  5518.6  341.38
#Mann= 4 ,-1 , 0
  4465.6     .17       0  4832.7     .11       0  4978.3     .06       0
    4993     .11       0
Bank Sta=4978.3,4993
XS Rating Curve= 0 ,0
Exp/Cntr=0.3,0.1

Type RM Length L Ch R = 1 ,3875    ,498,498,498
BEGIN DESCRIPTION:
BUMS CREEK 5.0
END DESCRIPTION:
XS GIS Cut Line= 3
      3685117.85     10162911.06      3685311.76     10162328.38
      3684717.86     10161761.08
#Sta/Elev= 30
  4385.9  342.85  4438.6  339.67  4470.3  339.39  4480.7   338.4  4586.1  334.65
  4649.4  333.55  4686.5  334.31  4756.5  333.24  4813.1  332.03  4828.5  332.35
  4971.3  328.22  4976.6  329.13  4986.6  328.23  4993.6  323.37  5015.1  324.56
    5022  328.12  5043.4  329.44  5121.1  328.95  5326.1  330.16  5333.4  329.63
  5340.3  330.35  5368.6  330.63  5609.2  331.33  5630.2  331.98  5672.7  334.89
    5701  334.88  5743.5   336.1  5764.9  338.13  5785.9  338.02  5821.3  339.87
#Mann= 4 ,-1 , 0
  4385.9     .17       0  4756.5     .11       0  4986.6     .06       0
    5022     .11       0
Bank Sta=4986.6,5022
XS Rating Curve= 0 ,0
Exp/Cntr=0.3,0.1

Type RM Length L Ch R = 1 ,3377    ,498,498,498
BEGIN DESCRIPTION:
BUMS CREEK 4.0
END DESCRIPTION:
XS GIS Cut Line= 3
      3685917.86     10162911.08      3685738.12     10162349.23
      3685617.85     10161461.04
#Sta/Elev= 30
  4410.1  347.03  4431.4  346.97  4515.1  343.23  4546.6  339.95  4624.4  335.98
  4641.1  334.46  4672.6  333.38  4688.7  331.92    4694  332.24  4720.9  330.25
    4753  329.13  4758.3     330  4840.6  329.01  4849.5  328.34  4854.8  328.76
  4924.6  327.64  4977.1  327.73  4980.8  322.99    4986  322.99  4988.6  324.58
    5000  323.57  5008.2  328.21  5036.4  328.41  5058.7  327.44    5089  328.18
  5169.7  327.54  5553.2  329.34  5744.9  333.38  5835.7  336.88  5896.3  340.91
#Mann= 3 , 0 , 0
  4410.1     .11       0  4977.1     .06       0  5008.2     .11       0
Bank Sta=4977.1,5008.2
XS Rating Curve= 0 ,0
Exp/Cntr=0.3,0.1

Type RM Length L Ch R = 1 ,2879    ,411,411,411
BEGIN DESCRIPTION:
BUMS CREEK 3.0
END DESCRIPTION:
XS GIS Cut Line= 3
      3686538.52      10162836.7      3686168.57     10162186.48
      3685717.85     10161411.06
#Sta/Elev= 30
  4251.9  342.67  4269.9  340.61  4279.6  340.91  4285.4  339.64  4322.8  337.67
  4366.1  337.44  4462.7  332.44    4565  330.06  4866.2  326.38 4962.74327.1276
  4987.5   322.5    5000  324.08  5005.9  327.14  5054.7  326.74  5064.1     325
  5086.2  326.59  5215.3  326.89  5413.1  334.35  5567.9  332.65  5663.9  335.01
  5700.3  334.49  5744.2  337.21  5765.7  337.25  5771.5  335.82  5787.2  337.58
    5793  336.68    5803  338.21  5808.7  337.43  5824.5  339.55  5896.9  343.51
#Mann= 3 , 0 , 0
  4251.9     .11       0 4962.74     .06       0  5005.9     .11       0
Bank Sta=4962.74,5005.9
XS Rating Curve= 0 ,0
Exp/Cntr=0.3,0.1

Type RM Length L Ch R = 1 ,2468    ,635,635,635
BEGIN DESCRIPTION:
BUMS CREEK 2.0
END DESCRIPTION:
XS GIS Cut Line= 3
      3687067.84     10162511.06      3686458.04     10161934.38
      3685867.85     10161311.07
#Sta/Elev= 30
  4160.7  342.13  4196.1  341.07  4245.4  337.33    4281  335.92  4309.4  336.26
    4366  333.99    4387  331.86  4429.5  329.93    4493  328.15  4719.6  325.28
    4847  325.31  4896.3  326.87  4931.5  325.48 4975.91326.2465  4993.5  323.77
  4997.5  323.77  4998.5  324.27  4998.8  325.48  5009.5  326.27  5030.9  326.65
  5037.8  325.64  5087.2  324.89  5122.8  325.58  5136.9  324.95  5140.7  323.84
    5158  324.82  5179.4  324.34  5490.5  335.67  5702.8  338.42  5858.4  344.82
#Mann= 3 , 0 , 0
  4160.7     .11       0 4975.91     .09       0  5009.5     .11       0
Bank Sta=4975.91,5009.5
XS Rating Curve= 0 ,0
Exp/Cntr=0.3,0.1

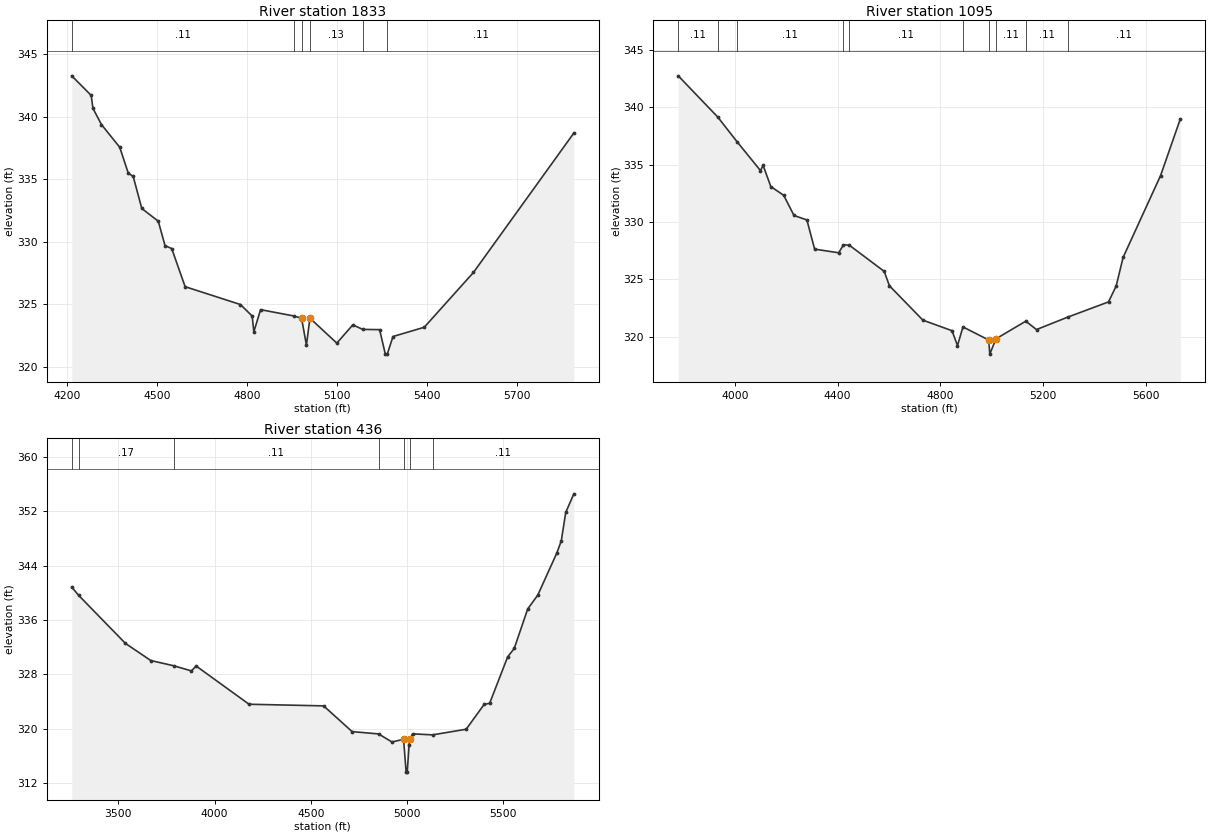
Type RM Length L Ch R = 1 ,1833    ,738,738,738
BEGIN DESCRIPTION:
Mapping XS 5102a17e
END DESCRIPTION:
XS GIS Cut Line= 2
      3687224.32     10162359.32      3686473.42     10160866.21
#Sta/Elev= 30
  4216.8  343.28  4281.6  341.71  4287.2  340.68  4315.6  339.38  4376.5  337.56
  4405.1  335.47  4421.1  335.24  4449.9  332.66  4504.8  331.64  4527.2  329.69
  4549.5  329.45  4594.1   326.4  4778.3  324.97  4817.3  324.05  4822.9  322.79
  4845.3  324.56  4954.9  324.06  4981.8323.8735  4997.9  321.72  5009.6  323.88
  5099.1  321.88  5152.2  323.34  5185.5  322.98  5241.5  322.96  5260.6     321
    5267     321  5286.1  322.41  5390.1  323.15    5554  327.54  5888.1   338.7
#Mann= 6 ,-1 , 0
  4216.8     .11       0  4954.9     .13       0  4981.8     .08       0
  5009.6     .13       0  5185.5     .11       0    5267     .11       0
Bank Sta=4981.8,5009.6
XS Rating Curve= 0 ,0
Exp/Cntr=0.3,0.1

Type RM Length L Ch R = 1 ,1095    ,659,659,659
BEGIN DESCRIPTION:
Mapping XS f5102b1b
END DESCRIPTION:
XS GIS Cut Line= 3
       3687289.4     10162320.22      3687380.55      10161261.2
      3686872.78     10160527.75
#Sta/Elev= 30
  3779.5  342.73  3933.3  339.14  4008.1     337  4099.8  334.47  4109.9  334.93
    4140  333.08  4190.2  332.32  4230.3  330.56  4280.5  330.17  4310.6  327.63
  4404.4  327.31    4423  328.01  4445.8  327.97  4581.6  325.69  4601.7  324.44
  4732.2  321.44  4845.6  320.52  4866.9  319.22  4888.1  320.85  4988.5  319.71
  4992.7  318.48  5016.5  319.81  5132.7  321.35  5174.6  320.62  5296.9  321.71
    5455  323.03  5484.8  324.42  5511.8  326.91  5657.5  334.03  5734.5  338.97
#Mann= 10 ,-1 , 0
  3779.5     .11       0  3933.3     .17       0  4008.1     .11       0
    4423     .17       0  4445.8     .11       0  4888.1     .11       0
  4988.5     .06       0  5016.5     .11       0  5132.7     .11       0
  5296.9     .11       0
Bank Sta=4988.5,5016.5
XS Rating Curve= 0 ,0
Exp/Cntr=0.3,0.1

Type RM Length L Ch R = 1 ,436     ,0,0,0
BEGIN DESCRIPTION:
BUMS CREEK 1.0
END DESCRIPTION:
XS GIS Cut Line= 3
      3687363.18     10162224.78      3687680.03     10160605.82
      3686803.32     10160219.55
#Sta/Elev= 30
  3258.6  340.84  3294.8  339.61  3537.5  332.54  3669.1  330.02  3787.9  329.25
  3880.3  328.49  3904.3  329.22  4179.4  323.58  4566.7  323.34  4714.6  319.55
    4852  319.21  4921.6  318.02  4981.9  318.42  4995.2  313.58  5000.9  313.58
  5010.7  317.64 5015.84318.3998  5028.5  319.22  5132.8  319.07    5307   319.9
  5400.3  323.55  5429.1  323.73  5522.4  330.55  5556.7   331.8  5626.7  337.62
  5678.8  339.65  5777.6  345.84  5800.9  347.63  5824.2  351.84  5866.3  354.58
#Mann= 7 ,-1 , 0
  3258.6     .11       0  3294.8     .17       0  3787.9     .11       0
    4852     .11       0  4981.9     .06       0 5015.84     .11       0
  5132.8     .11       0
Bank Sta=4981.9,5015.84
XS Rating Curve= 0 ,0
Exp/Cntr=0.3,0.1

Chan Stop Cuts=-1
Use User Specified Reach Order=0
Composite Channel Slope=5