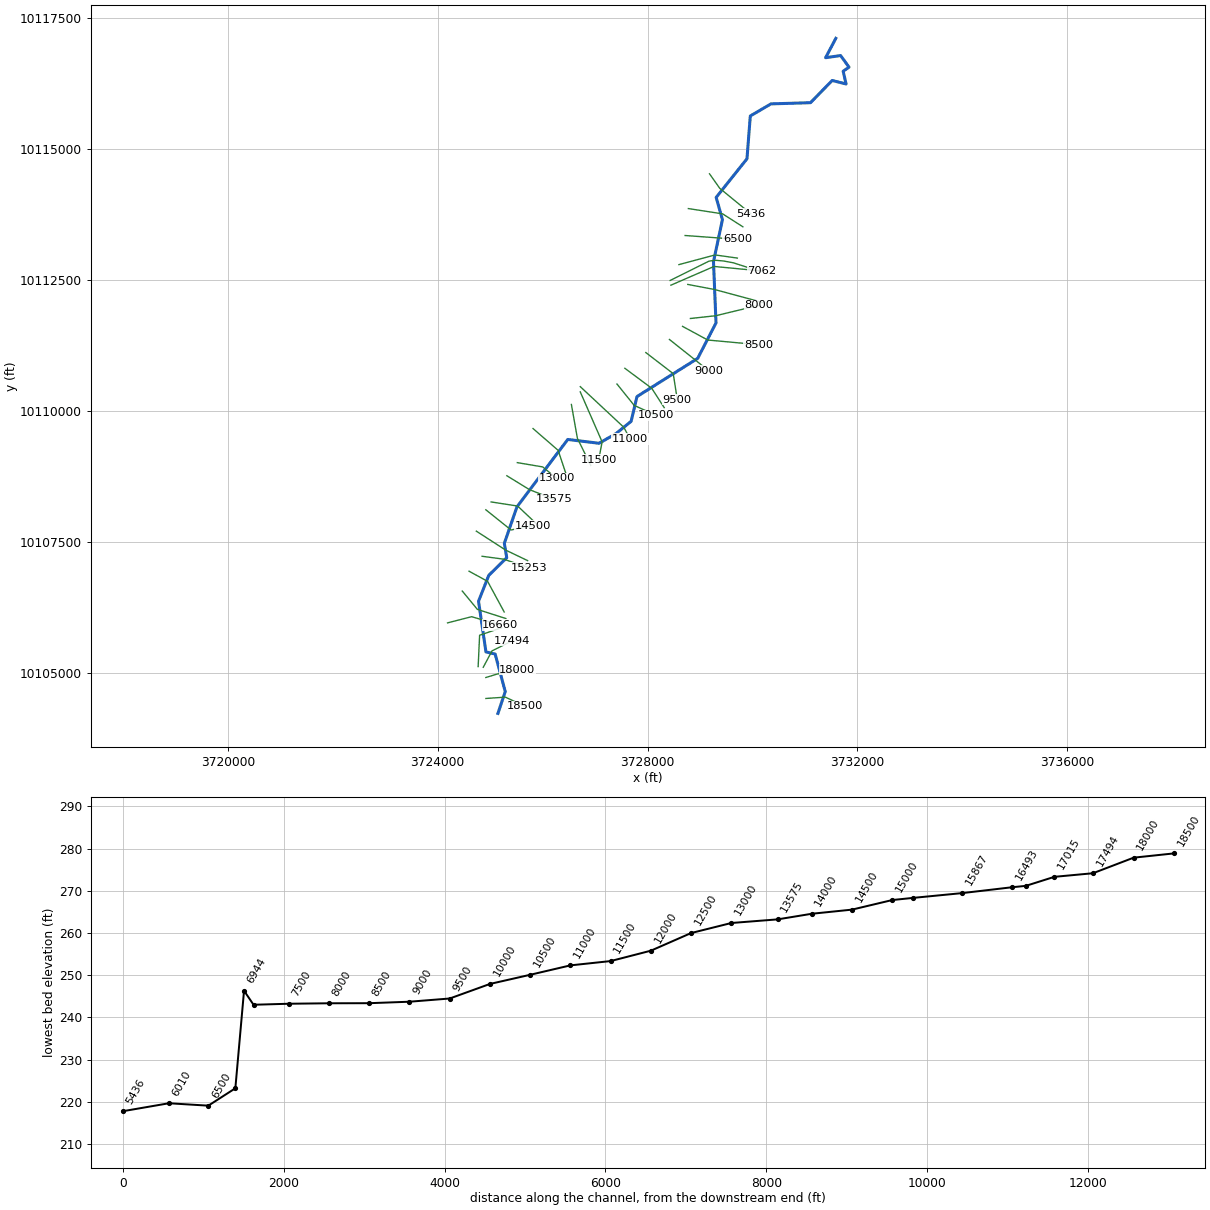
--- CANEY CREEK TRIBUTARY NO 2.prj (project) ---

Proj Title=CANEY CREEK TRIBUTARY NO 2 Base Level Engineering
Current Plan=p01
Default Exp/Contr=0.3,0.1
English Units
Geom File=g01
Flow File=f01
Flow File=f02
Plan File=p01
Y Axis Title=Elevation
X Axis Title(PF)=Main Channel Distance
X Axis Title(XS)=Station
BEGIN DESCRIPTION:
CANEY CREEK TRIBUTARY NO 2
END DESCRIPTION:
DSS Export Rating Curves= 0
DSS Export Rating Curve Sorted= 0
DSS Export Volume Flow Curves= 0
DXF OffsetX= 0
DXF OffsetY= 0
DXF ScaleX= 1
DXF ScaleY= 10

--- CANEY CREEK TRIBUTARY NO 2.p01 (plan) ---

Plan Title=Multiple Run
Short Identifier=Multiple
Geom File=g01
Flow File=f01
Subcritical Flow
K Sum by GR= 0
Std Step Tol= 0.01
Critical Tol= 0.01
Num of Std Step Trials= 20
Max Error Tol= 0.3
Flow Tol Ratio= 0.001
Split Flow NTrial= 30
Split Flow Tol= 0.02
Split Flow Ratio= 0.02
Log Output Level= 0
Friction Slope Method= 1
Unsteady Friction Slope Method= 2
Unsteady Bridges Friction Slope Method= 1
Parabolic Critical Depth
Global Vel Dist=  1 , 1 , 1
Global Log Level= 0
CheckData=True
Encroach Param= -1, 0, 0, 0
BEGIN DESCRIPTION:
Multiple Run
END DESCRIPTION:

--- CANEY CREEK TRIBUTARY NO 2.f01 (steady flow) ---

Flow Title=Multiple
Program Version=4.10
Number of Profiles= 7
Profile Names=10-year,25-year,50-year,1pct_min,100-year,1pct_plu,500-year
River Rch & RM=CANEY CREEK TRIB,Reach-1         ,18500
     501     665     888     390    1178    3558    2140
River Rch & RM=CANEY CREEK TRIB,Reach-1         ,15867
     923    1272    1739     780    2357    7118    4482
River Rch & RM=CANEY CREEK TRIB,Reach-1         ,10500
    1325    1860    2575    1169    3531   10663    6871
River Rch & RM=CANEY CREEK TRIB,Reach-1         ,6836
    1473    2081    2893    1320    3985   12035    7819
River Rch & RM=CANEY CREEK TRIB,Reach-1         ,1684
    1392    1952    2700    1225    3699   11171    7181
Boundary for River Rch & Prof#=CANEY CREEK TRIB,Reach-1         , 1
Up Type= 0
Dn Type= 3
Dn Slope=0.005
Boundary for River Rch & Prof#=CANEY CREEK TRIB,Reach-1         , 2
Up Type= 0
Dn Type= 3
Dn Slope=0.005
Boundary for River Rch & Prof#=CANEY CREEK TRIB,Reach-1         , 3
Up Type= 0
Dn Type= 3
Dn Slope=0.005
Boundary for River Rch & Prof#=CANEY CREEK TRIB,Reach-1         , 4
Up Type= 0
Dn Type= 3
Dn Slope=0.005
Boundary for River Rch & Prof#=CANEY CREEK TRIB,Reach-1         , 5
Up Type= 0
Dn Type= 3
Dn Slope=0.005
Boundary for River Rch & Prof#=CANEY CREEK TRIB,Reach-1         , 6
Up Type= 0
Dn Type= 3
Dn Slope=0.005
Boundary for River Rch & Prof#=CANEY CREEK TRIB,Reach-1         , 7
Up Type= 0
Dn Type= 3
Dn Slope=0.005
DSS Import GetInterval= 0
DSS Import GetPeak= 0
DSS Import FillOption= 0

--- CANEY CREEK TRIBUTARY NO 2.f02 (steady flow) ---

Flow Title=Orig_BLE_Flows
Program Version=4.10
Number of Profiles= 7
Profile Names=10-year,25-year,50-year,1pct_min,100-year,1pct_plu,500-year
River Rch & RM=CANEY CREEK TRIB,Reach-1         ,18500
     501     652     772     300     906    2735    1244
River Rch & RM=CANEY CREEK TRIB,Reach-1         ,15867
     923    1247    1512     600    1813    5476    2606
River Rch & RM=CANEY CREEK TRIB,Reach-1         ,10500
    1325    1824    2239     899    2716    8202    3995
River Rch & RM=CANEY CREEK TRIB,Reach-1         ,6836
    1473    2040    2516    1015    3065    9255    4546
River Rch & RM=CANEY CREEK TRIB,Reach-1         ,1684
    1392    1914    2348     942    2845    8591    4175
Boundary for River Rch & Prof#=CANEY CREEK TRIB,Reach-1         , 1
Up Type= 0
Dn Type= 3
Dn Slope=0.005
Boundary for River Rch & Prof#=CANEY CREEK TRIB,Reach-1         , 2
Up Type= 0
Dn Type= 3
Dn Slope=0.005
Boundary for River Rch & Prof#=CANEY CREEK TRIB,Reach-1         , 3
Up Type= 0
Dn Type= 3
Dn Slope=0.005
Boundary for River Rch & Prof#=CANEY CREEK TRIB,Reach-1         , 4
Up Type= 0
Dn Type= 3
Dn Slope=0.005
Boundary for River Rch & Prof#=CANEY CREEK TRIB,Reach-1         , 5
Up Type= 0
Dn Type= 3
Dn Slope=0.005
Boundary for River Rch & Prof#=CANEY CREEK TRIB,Reach-1         , 6
Up Type= 0
Dn Type= 3
Dn Slope=0.005
Boundary for River Rch & Prof#=CANEY CREEK TRIB,Reach-1         , 7
Up Type= 0
Dn Type= 3
Dn Slope=0.005
DSS Import GetInterval= 0
DSS Import GetPeak= 0
DSS Import FillOption= 0

--- CANEY CREEK TRIBUTARY NO 2.g01 (geometry) ---

Geom Title=Existing Conditions
Program Version=4.10

River Reach=CANEY CREEK TRIB,Reach-1
Reach XY= 30
      3725148.23     10104226.84      3725287.64     10104641.93
      3725095.33     10105358.57      3724919.51     10105399.35
      3724778.12     10106366.46      3724973.64     10106860.43
      3725315.81      10107196.8      3725270.17      10107471.2
      3725510.49     10108166.87      3726479.21     10109453.11
      3727076.43      10109380.2      3727397.61     10109564.22
      3727687.55      10109798.6       3727799.3     10110271.74
      3728956.64     10110999.99      3729305.93     10111676.85
      3729257.95     10112844.81      3729428.45     10113646.87
      3729308.88     10114071.61      3729896.08     10114807.72
      3729959.83     10115625.27      3730353.49     10115856.05
      3731107.42     10115878.76       3731521.1     10116302.51
      3731785.68     10116235.85      3731730.12      10116479.6
      3731841.93     10116556.68      3731681.51     10116778.21
       3731395.4     10116737.24      3731590.49     10117106.66

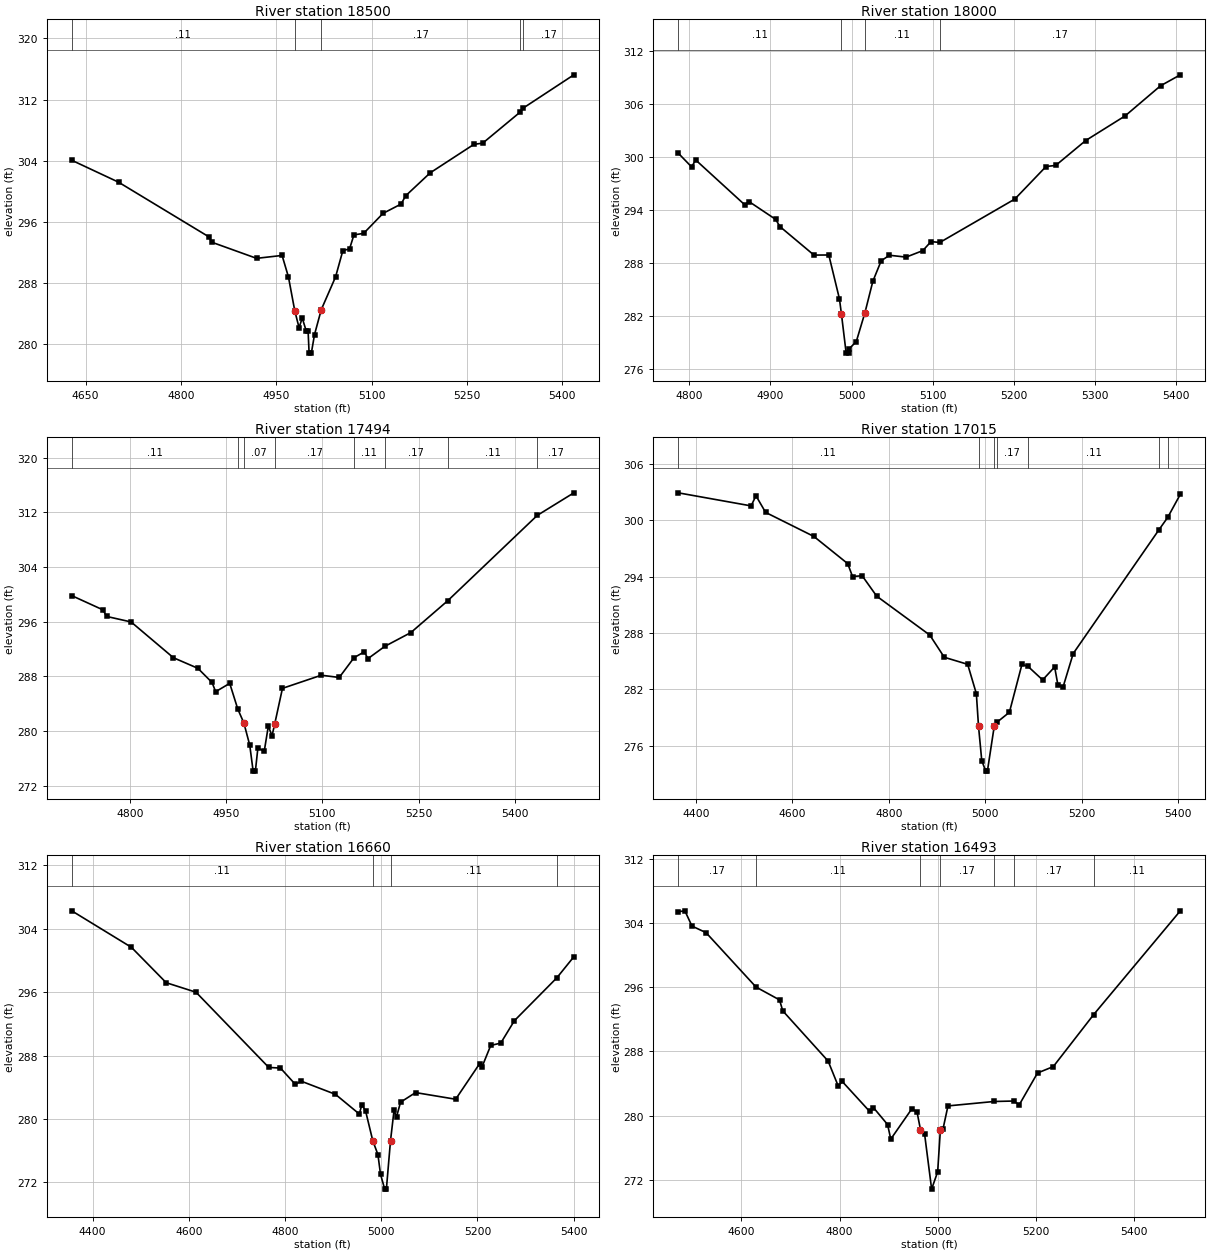
Type RM Length L Ch R = 1 ,18500   ,500,500,500
BEGIN DESCRIPTION:
CANEY CREEK TRIBUTARY NO. 2 37.0
END DESCRIPTION:
XS GIS Cut Line= 3
       3724917.9     10104511.07       3725288.7     10104536.95
      3725667.89     10104361.06
#Sta/Elev= 30
  4628.3  304.06  4701.8   301.2  4843.8  294.06  4848.8  293.34    4919  291.24
  4959.1  291.62  4969.1  288.81  4979.1  284.36  4985.8  282.18  4990.8  283.45
  4997.1  281.73    5000  281.73  5001.6  278.85  5005.1  278.85  5010.1  281.27
  5020.7  284.53  5043.2  288.81  5054.7  292.26  5065.2  292.47  5072.1  294.31
  5087.3   294.5  5117.9  297.12  5146.3  298.34  5153.4  299.41  5192.1  302.42
  5260.8  306.14  5274.7   306.3  5333.6  310.36  5338.5  310.89    5418  315.23
#Mann= 5 ,-1 , 0
  4628.3     .11       0  4979.1     .07       0  5020.7     .17       0
  5333.6     .11       0  5338.5     .17       0
Bank Sta=4979.1,5020.7
XS Rating Curve= 0 ,0
Exp/Cntr=0.3,0.1

Type RM Length L Ch R = 1 ,18000   ,506,506,506
BEGIN DESCRIPTION:
CANEY CREEK TRIBUTARY NO. 2 36.0
END DESCRIPTION:
XS GIS Cut Line= 3
      3724917.85     10104911.07      3725122.23      10104973.5
      3725517.85     10105061.07
#Sta/Elev= 30
  4786.3  300.44  4802.7  298.89  4807.9  299.66  4868.3   294.6  4873.5  294.97
  4906.3  292.96  4911.8  292.13  4953.6  288.92  4971.9  288.93    4985  283.98
 4987.49282.2461  4993.3  277.84  4996.8  277.84  4997.1  278.34  5005.8  279.15
  5016.5  282.43  5026.2  285.96  5036.5  288.28  5046.7   288.9  5067.2  288.69
  5087.7  289.42  5097.9  290.44  5108.8  290.35  5201.2  295.25  5239.7  298.93
  5251.6  299.05  5288.5  301.86  5337.2  304.65  5380.8  308.05  5405.2  309.29
#Mann= 4 ,-1 , 0
  4786.3     .11       0 4987.49     .05       0  5016.5     .11       0
  5108.8     .17       0
Bank Sta=4987.49,5016.5
XS Rating Curve= 0 ,0
Exp/Cntr=0.3,0.1

Type RM Length L Ch R = 1 ,17494   ,479,479,479
BEGIN DESCRIPTION:
CANEY CREEK TRIBUTARY NO. 2 35.0
END DESCRIPTION:
XS GIS Cut Line= 3
       3724868.3     10105106.33      3725034.97     10105418.82
      3725417.85     10105611.07
#Sta/Elev= 30
  4709.3  299.82  4757.9  297.74  4763.6  296.78  4801.8  295.97  4867.7  290.74
  4905.9  289.19  4927.9  287.12  4933.6  285.77  4955.5  286.99  4968.1  283.22
  4977.5  281.21  4986.7  277.96    4992  274.15  4995.5  274.15  4999.4  277.53
  5009.3  277.05  5015.7  280.75  5021.4  279.31 5025.72 281.087  5037.7  286.26
  5098.3  288.18  5126.2  287.85  5149.3  290.75  5165.3   291.6  5170.9   290.6
  5197.2   292.4  5237.9  294.42  5295.5  299.09  5434.9  311.56  5491.9  314.86
#Mann= 8 ,-1 , 0
  4709.3     .11       0  4968.1     .17       0  4977.5     .07       0
 5025.72     .17       0  5149.3     .11       0  5197.2     .17       0
  5295.5     .11       0  5434.9     .17       0
Bank Sta=4977.5,5025.72
XS Rating Curve= 0 ,0
Exp/Cntr=0.3,0.1

Type RM Length L Ch R = 1 ,17015   ,355,355,355
BEGIN DESCRIPTION:
CANEY CREEK TRIBUTARY NO. 2 34.0
END DESCRIPTION:
XS GIS Cut Line= 3
      3724771.08     10105120.16      3724798.86     10105717.43
      3725217.81     10105861.06
#Sta/Elev= 30
  4363.6   302.9  4514.7  301.51  4524.7  302.59  4544.7  300.82  4644.8  298.26
  4714.9  295.37  4724.9     294  4744.9  294.08    4775  291.91  4885.1  287.77
  4915.1  285.41  4963.6  284.66  4981.6  281.54 4986.05278.0858  4992.8  274.42
    5001   273.3  5004.5   273.3  5018.8  278.12  5023.9  278.48  5050.1  279.56
  5076.1  284.65  5088.4  284.45    5119     283  5143.9  284.38  5150.7  282.45
  5161.3  282.24  5182.4  285.81  5360.4  298.99  5378.2  300.28  5404.4  302.74
#Mann= 7 ,-1 , 0
  4363.6     .11       0 4986.05     .05       0  5018.8     .11       0
  5023.9     .17       0  5088.4     .11       0  5360.4     .17       0
  5378.2     .11       0
Bank Sta=4986.05,5018.8
XS Rating Curve= 0 ,0
Exp/Cntr=0.3,0.1

Type RM Length L Ch R = 1 ,16660   ,167,167,167
BEGIN DESCRIPTION:
Mapping XS 475074e2
END DESCRIPTION:
XS GIS Cut Line= 3
      3724187.73     10105953.54      3724646.08      10106071.6
      3725193.73     10105912.16
#Sta/Elev= 30
  4356.6  306.24  4480.6  301.64  4552.9  297.18  4614.9  295.98  4766.1   286.5
  4790.4  286.42  4821.4  284.36  4833.4  284.77  4904.7  283.11  4954.3  280.63
  4959.5  281.78  4967.2  281.06 4982.28277.2683    4993  275.52  4998.4  273.04
  5007.1  271.16  5010.6  271.16  5019.2  277.27  5026.5  281.08  5031.7  280.28
  5040.1  282.12  5071.3  283.33  5154.6  282.49  5204.5  286.98  5209.7  286.61
  5227.5  289.27  5248.4  289.57  5276.7  292.39    5365   297.8  5400.3  300.45
#Mann= 4 ,-1 , 0
  4356.6     .11       0 4982.28     .05       0  5019.2     .11       0
    5365     .17       0
Bank Sta=4982.28,5019.2
XS Rating Curve= 0 ,0
Exp/Cntr=0.3,0.1

Type RM Length L Ch R = 1 ,16493   ,626,626,626
BEGIN DESCRIPTION:
CANEY CREEK TRIBUTARY NO. 2 33.0
END DESCRIPTION:
XS GIS Cut Line= 3
      3724467.85     10106561.07      3724757.19     10106210.49
      3725298.89     10106036.87
#Sta/Elev= 30
  4471.2  305.42  4484.8  305.51  4499.2  303.62  4527.9   302.8  4629.8  296.02
  4677.7  294.42  4684.2  293.06  4776.7   286.8  4797.5  283.66  4805.4  284.26
  4861.4  280.52  4869.2  280.99  4897.9  278.89  4904.4  277.07  4947.5  280.86
    4958  280.43 4964.95278.2624  4973.4  277.69  4987.7  270.84    5000     273
  5005.5   278.2  5010.7  278.28    5021  281.21  5114.8  281.76  5155.5  281.82
  5166.2  281.34  5203.5  285.31  5235.7  286.11  5318.1   292.6  5494.6  305.52
#Mann= 7 ,-1 , 0
  4471.2     .17       0  4629.8     .11       0 4964.95     .05       0
  5005.5     .17       0  5114.8     .11       0  5155.5     .17       0
  5318.1     .11       0
Bank Sta=4964.95,5005.5
XS Rating Curve= 0 ,0
Exp/Cntr=0.3,0.1

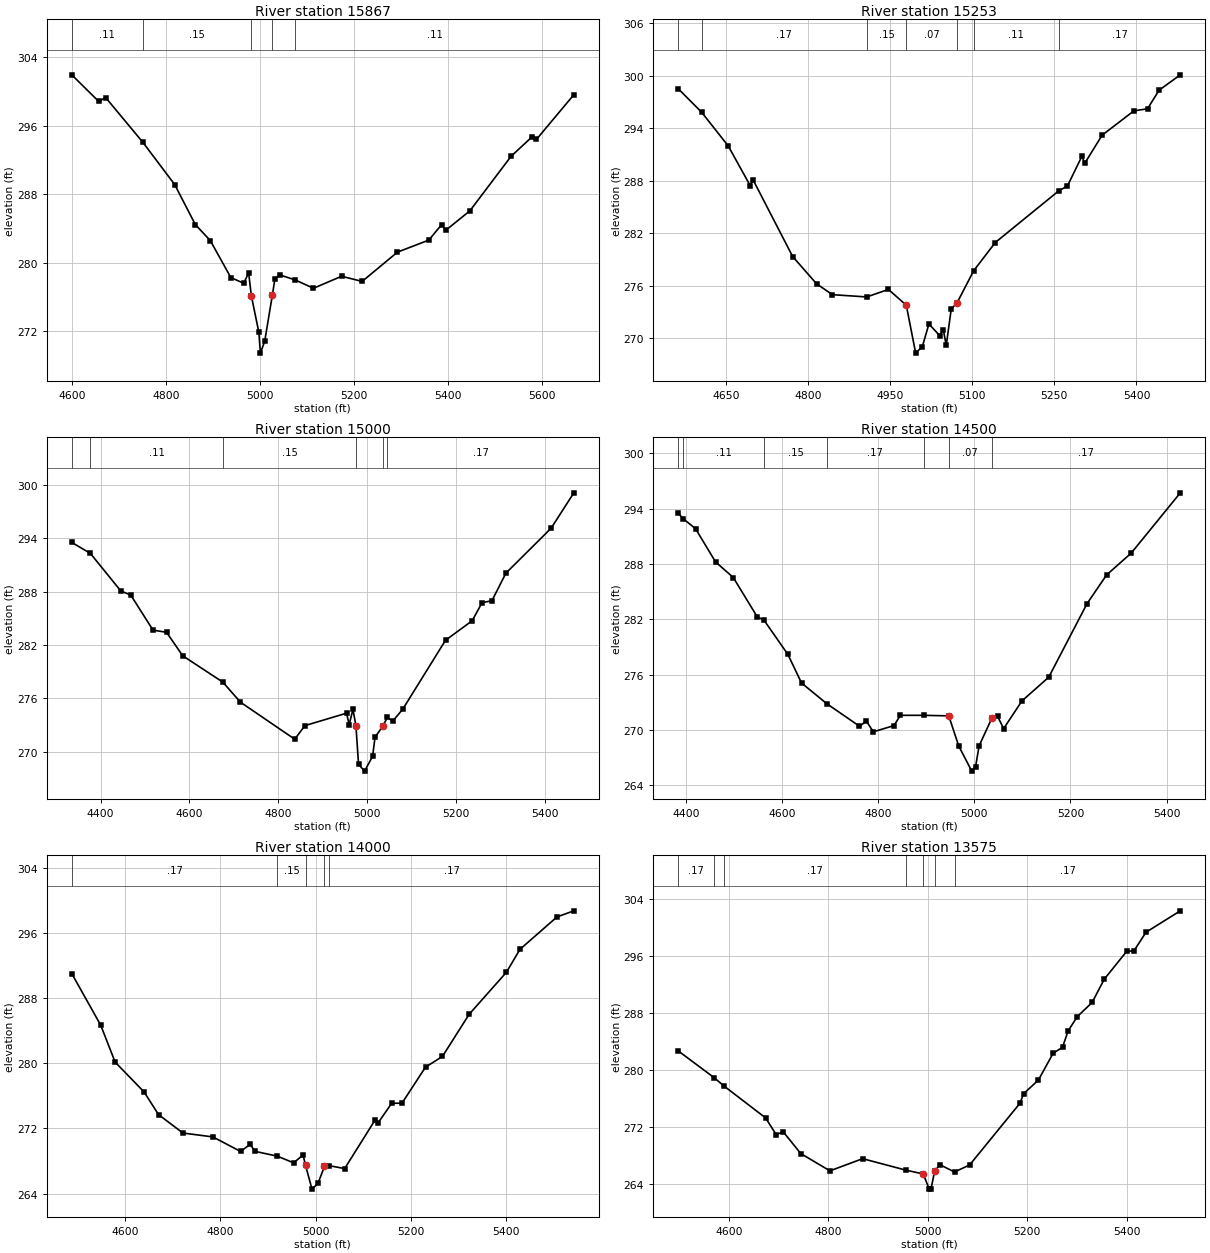
Type RM Length L Ch R = 1 ,15867   ,614,614,614
BEGIN DESCRIPTION:
CANEY CREEK TRIBUTARY NO. 2 32.0
END DESCRIPTION:
XS GIS Cut Line= 3
      3724597.51     10106939.64      3724951.64     10106745.21
      3725267.84      10106161.1
#Sta/Elev= 30
  4599.6  301.92    4657  298.81  4671.7  299.27  4750.9  294.04  4818.6  289.11
  4862.4  284.45  4894.4  282.57    4938  278.26  4965.5  277.59  4975.9  278.82
  4981.6  276.15  4997.7  271.85  5000.9  269.44  5010.1  270.83  5026.3  276.19
  5031.9  278.14  5042.4  278.56  5074.6  277.99  5113.8  277.01  5173.7  278.41
  5217.4  277.81  5292.6  281.23  5359.2  282.63  5386.7  284.45  5394.9  283.76
  5446.7  286.05  5534.2  292.41  5577.9  294.63  5588.2  294.38  5667.8   299.6
#Mann= 5 ,-1 , 0
  4599.6     .11       0  4750.9     .15       0  4981.6     .07       0
  5026.3     .15       0  5074.6     .11       0
Bank Sta=4981.6,5026.3
XS Rating Curve= 0 ,0
Exp/Cntr=0.3,0.1

Type RM Length L Ch R = 1 ,15253   ,253,253,253
BEGIN DESCRIPTION:
CANEY CREEK TRIBUTARY NO. 2 31.0
END DESCRIPTION:
XS GIS Cut Line= 3
      3724847.51     10107224.37      3725257.19     10107168.82
      3725734.64     10107009.68
#Sta/Elev= 30
  4563.3  298.51  4606.1  295.82  4654.5  291.98  4694.6  287.45  4699.7  288.13
  4772.2  279.34  4815.9  276.22  4844.8  274.98  4907.4  274.72  4947.1  275.58
  4979.7  273.77  4996.8   268.3    5009  269.05    5021  271.63  5040.7   270.3
  5047.3  270.97  5052.6  269.18  5061.8  273.36  5072.3  274.04  5102.7  277.71
  5142.2  280.94  5257.6  286.82  5273.9   287.4  5300.3  290.79  5305.6     290
  5337.2   293.2  5395.2  295.98  5420.1  296.22  5441.2  298.34    5480   300.1
#Mann= 7 ,-1 , 0
  4563.3     .11       0  4606.1     .17       0  4907.4     .15       0
  4979.7     .07       0  5072.3     .15       0  5102.7     .11       0
  5257.6     .17       0
Bank Sta=4979.7,5072.3
XS Rating Curve= 0 ,0
Exp/Cntr=0.3,0.1

Type RM Length L Ch R = 1 ,15000   ,500,500,500
BEGIN DESCRIPTION:
CANEY CREEK TRIBUTARY NO. 2 30.0
END DESCRIPTION:
XS GIS Cut Line= 3
      3724736.38     10107703.53      3725294.84     10107342.69
      3725714.16      10107141.7
#Sta/Elev= 30
  4335.1  293.53  4376.9   292.3  4445.5  288.07  4467.8  287.61    4518  283.66
  4548.4  283.42  4584.7  280.78  4675.1  277.81  4714.6  275.56  4836.9  271.39
  4859.8  272.92  4953.5  274.32  4959.4  273.03  4967.9  274.75  4974.6  272.88
  4980.5  268.56    4994   267.8  5012.1  269.46  5017.6  271.62  5034.8  272.83
  5045.2  273.84  5057.4  273.42  5080.1  274.78  5176.2  282.52  5236.2  284.72
  5258.4  286.75  5280.6  286.97  5312.2  290.08  5413.9  295.13    5465  299.11
#Mann= 6 ,-1 , 0
  4335.1     .17       0  4376.9     .11       0  4675.1     .15       0
  4974.6     .07       0  5034.8     .15       0  5045.2     .17       0
Bank Sta=4974.6,5034.8
XS Rating Curve= 0 ,0
Exp/Cntr=0.3,0.1

Type RM Length L Ch R = 1 ,14500   ,500,500,500
BEGIN DESCRIPTION:
CANEY CREEK TRIBUTARY NO. 2 29.0
END DESCRIPTION:
XS GIS Cut Line= 3
      3724917.87     10108111.05        3725398.     10107725.94
      3725817.86     10107811.07
#Sta/Elev= 30
  4384.5   293.5  4394.3  292.91  4420.5  291.81  4462.1  288.21  4498.9  286.52
  4548.5  282.28  4562.9  281.89  4612.5  278.18  4640.9  275.08  4693.4  272.84
  4761.3   270.4  4775.7  270.95  4790.1  269.79  4833.2  270.47  4846.2  271.58
  4894.7  271.58    4947  271.52  4967.8  268.24  4994.8  265.53  5002.8  266.03
    5010  268.26  5036.4  271.26  5048.4  271.47  5061.1  270.14  5099.1  273.14
  5154.8  275.71  5234.5  283.69  5275.3  286.81  5326.4  289.17  5428.4   295.7
#Mann= 7 ,-1 , 0
  4384.5     .17       0  4394.3     .11       0  4562.9     .15       0
  4693.4     .17       0  4894.7     .15       0    4947     .07       0
  5036.4     .17       0
Bank Sta=4947,5036.4
XS Rating Curve= 0 ,0
Exp/Cntr=0.3,0.1

Type RM Length L Ch R = 1 ,14000   ,425,425,425
BEGIN DESCRIPTION:
CANEY CREEK TRIBUTARY NO. 2 28.0
END DESCRIPTION:
XS GIS Cut Line= 3
      3725017.88     10108261.07      3725523.65     10108182.76
      3725917.85     10107811.07
#Sta/Elev= 30
  4488.2  291.02  4548.9  284.69  4579.2  280.15    4640  276.48  4670.3   273.7
  4721.5  271.44  4784.5  270.96  4842.3  269.18  4862.6  270.05  4872.7  269.19
  4919.5   268.6  4953.7  267.78  4973.6  268.74  4978.7  267.48  4992.3  264.55
  5004.9  265.26  5018.5  267.33    5028  267.44  5060.8  267.07  5124.5  273.02
  5131.4  272.72  5159.7   275.1  5181.1   275.1  5230.5  279.53  5266.1  280.85
  5322.3  286.04  5400.4  291.19  5428.7     294  5506.4  297.98  5541.8  298.73
#Mann= 5 ,-1 , 0
  4488.2     .17       0  4919.5     .15       0  4978.7     .07       0
  5018.5     .15       0    5028     .17       0
Bank Sta=4978.7,5018.5
XS Rating Curve= 0 ,0
Exp/Cntr=0.3,0.1

Type RM Length L Ch R = 1 ,13575   ,575,575,575
BEGIN DESCRIPTION:
CANEY CREEK TRIBUTARY NO. 2 27.0
END DESCRIPTION:
XS GIS Cut Line= 3
      3725317.88     10108761.05      3725750.25     10108495.21
      3726217.85     10108311.07
#Sta/Elev= 30
  4497.7  282.65  4569.7   278.9    4590   277.7  4673.5  273.23  4694.7  270.89
    4709  271.27  4744.2  268.22  4802.9  265.79  4868.7   267.5  4955.6  265.89
  4990.7  265.35  5002.6  263.22  5006.3  263.22  5013.4  265.74  5024.2  266.65
  5053.5  265.63    5084  266.62  5185.4  275.31  5192.4  276.63  5222.1  278.53
  5251.9  282.31  5270.9  283.17  5282.1  285.47  5300.7  287.48  5330.4  289.46
  5354.8  292.73  5400.3  296.68  5414.4   296.7  5438.8  299.33  5507.8  302.34
#Mann= 7 ,-1 , 0
  4497.7     .17       0  4569.7     .15       0    4590     .17       0
  4955.6     .15       0  4990.7     .07       0  5013.4     .15       0
  5053.5     .17       0
Bank Sta=4990.7,5013.4
XS Rating Curve= 0 ,0
Exp/Cntr=0.3,0.1

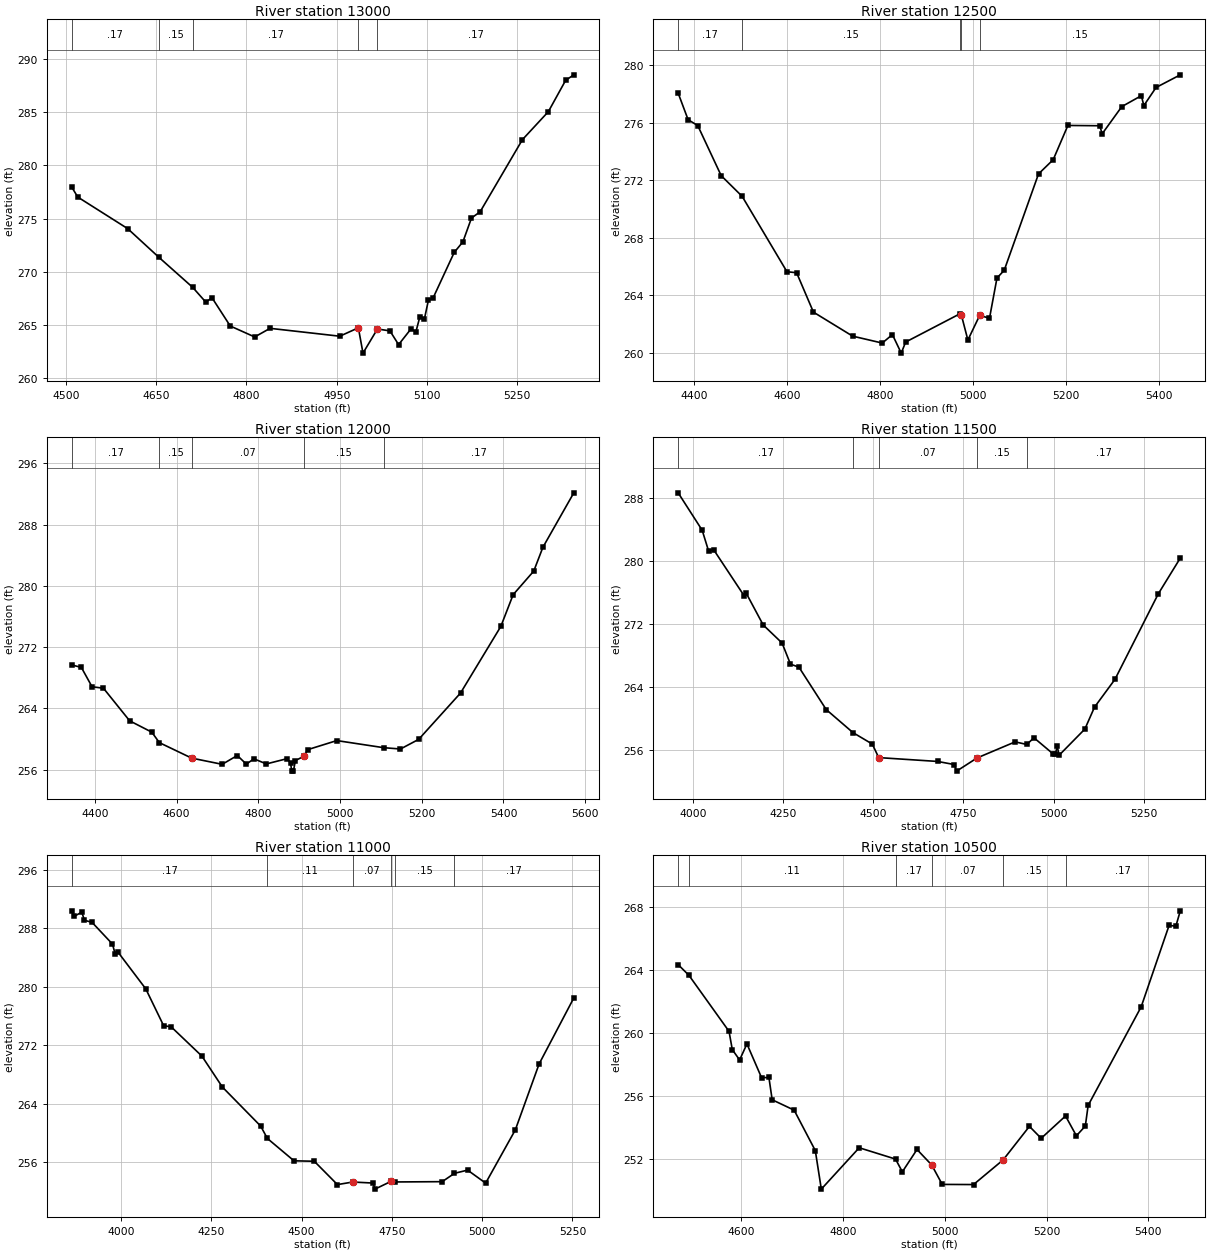
Type RM Length L Ch R = 1 ,13000   ,500,500,500
BEGIN DESCRIPTION:
CANEY CREEK TRIBUTARY NO. 2 26.0
END DESCRIPTION:
XS GIS Cut Line= 3
      3725517.84     10109011.07      3726001.69     10108929.36
      3726267.83     10108711.09
#Sta/Elev= 30
  4509.3  277.98  4519.5  277.03  4602.5  274.06  4653.9  271.39  4710.6  268.54
  4732.4  267.15  4742.6  267.57    4773  264.91  4813.6  263.88  4839.2  264.69
  4955.1  263.95    4986  264.74  4993.7  262.36  5017.7  264.63  5038.5  264.45
  5052.9  263.16  5073.7  264.65  5081.6  264.35    5088  265.72  5095.9  265.59
  5102.4  267.32  5110.3  267.55  5145.4  271.83  5159.8  272.82  5174.1  275.06
  5188.5  275.65  5258.8  282.43  5301.9  285.06  5330.6     288  5344.2  288.52
#Mann= 5 ,-1 , 0
  4509.3     .17       0  4653.9     .15       0  4710.6     .17       0
    4986     .07       0  5017.7     .17       0
Bank Sta=4986,5017.7
XS Rating Curve= 0 ,0
Exp/Cntr=0.3,0.1

Type RM Length L Ch R = 1 ,12500   ,500,500,500
BEGIN DESCRIPTION:
CANEY CREEK TRIBUTARY NO. 2 25.0
END DESCRIPTION:
XS GIS Cut Line= 3
      3725817.85     10109661.07      3726296.27     10109245.36
      3726437.73     10108821.65
#Sta/Elev= 30
  4366.2  278.06  4387.6  276.21  4408.4   275.8  4458.8  272.32  4503.9  270.88
  4600.3  265.64  4621.1  265.57  4657.3  262.83  4741.7  261.16  4805.4  260.68
  4827.2  261.27  4846.2  259.98  4855.7  260.75  4972.2  262.71  4975.6  262.63
  4989.6  260.89  5015.1  262.61  5036.1   262.4  5052.2   265.2  5067.8  265.74
  5141.6  272.44  5173.2  273.43  5204.8  275.81  5273.4  275.79  5278.6  275.23
  5320.8  277.12  5362.9  277.88  5368.2  277.19  5394.5  278.45  5446.7  279.33
#Mann= 5 ,-1 , 0
  4366.2     .17       0  4503.9     .15       0  4972.2     .17       0
  4975.6     .07       0  5015.1     .15       0
Bank Sta=4975.6,5015.1
XS Rating Curve= 0 ,0
Exp/Cntr=0.3,0.1

Type RM Length L Ch R = 1 ,12000   ,500,500,500
BEGIN DESCRIPTION:
CANEY CREEK TRIBUTARY NO. 2 24.0
END DESCRIPTION:
XS GIS Cut Line= 3
      3726548.85     10110120.25      3726663.38     10109473.51
      3726917.83     10108961.11
#Sta/Elev= 30
  4343.2  269.67  4366.9  269.35  4393.1  266.82    4421  266.63  4485.2  262.37
  4539.3  260.89  4557.9  259.52  4636.9   257.5  4711.6  256.69  4748.6  257.84
  4770.8  256.71  4789.2  257.41  4819.7  256.74  4870.5  257.43  4878.9  256.84
    4882   255.8  4885.9   255.8  4890.8  257.18  4911.1  257.73  4921.2  258.61
  4992.1  259.79    5107  258.86  5147.9  258.69  5192.5  259.95  5294.9     266
  5393.5   274.7  5423.7  278.85  5474.1  281.93  5496.5  285.04  5572.1  292.15
#Mann= 5 ,-1 , 0
  4343.2     .17       0  4557.9     .15       0  4636.9     .07       0
  4911.1     .15       0    5107     .17       0
Bank Sta=4636.9,4911.1
XS Rating Curve= 0 ,0
Exp/Cntr=0.3,0.1

Type RM Length L Ch R = 1 ,11500   ,500,500,500
BEGIN DESCRIPTION:
CANEY CREEK TRIBUTARY NO. 2 23.0
END DESCRIPTION:
XS GIS Cut Line= 3
      3726717.86     10110361.05      3727134.65     10109406.37
      3727067.85     10109061.07
#Sta/Elev= 30
  3958.3  288.72    4025  283.96  4042.9   281.3  4056.5  281.51    4142  275.59
  4147.5  275.93  4194.3  271.92  4246.6  269.63    4270  266.94  4293.4  266.56
  4369.1  261.17  4443.3  258.24    4497  256.78  4514.8  255.06  4678.4  254.57
  4724.1  254.18    4731  253.34  4787.5  255.01  4893.4  257.06  4925.7  256.73
  4945.6  257.58  4997.7  255.57  5004.9  255.48    5010   256.5  5015.6  255.37
  5086.9  258.69  5113.6  261.47  5170.4  265.01  5290.6  275.88  5351.7  280.43
#Mann= 5 ,-1 , 0
  3958.3     .17       0  4443.3     .15       0  4514.8     .07       0
  4787.5     .15       0  4925.7     .17       0
Bank Sta=4514.8,4787.5
XS Rating Curve= 0 ,0
Exp/Cntr=0.3,0.1

Type RM Length L Ch R = 1 ,11000   ,500,500,500
BEGIN DESCRIPTION:
CANEY CREEK TRIBUTARY NO. 2 22.0
END DESCRIPTION:
XS GIS Cut Line= 3
      3726717.87     10110461.05      3727548.51     10109684.94
      3727667.86     10109461.06
#Sta/Elev= 30
  3863.2  290.36  3870.3  289.61  3891.3  290.18  3898.6  289.07  3919.6  288.79
  3976.3  285.81  3983.6  284.47  3990.4  284.79  4068.5  279.69  4117.9  274.66
  4138.9   274.5  4223.9   270.5  4280.6  266.27  4386.6  260.94  4405.1  259.25
  4478.9  256.19  4535.1  256.13  4599.1  252.94  4641.6  253.29    4698  253.15
  4703.1  252.32  4747.6  253.38  4757.8   253.3  4889.3  253.34  4923.3  254.48
  4959.6  254.92  5009.6  253.14  5091.8  260.42  5157.7  269.44  5253.7  278.45
#Mann= 6 ,-1 , 0
  3863.2     .17       0  4405.1     .11       0  4641.6     .07       0
  4747.6     .11       0  4757.8     .15       0  4923.3     .17       0
Bank Sta=4641.6,4747.6
XS Rating Curve= 0 ,0
Exp/Cntr=0.3,0.1

Type RM Length L Ch R = 1 ,10500   ,500,500,500
BEGIN DESCRIPTION:
CANEY CREEK TRIBUTARY NO. 2 21.0
END DESCRIPTION:
XS GIS Cut Line= 3
      3727417.85     10110511.07      3727746.37     10110102.71
      3728167.85     10109911.07
#Sta/Elev= 30
  4475.9  264.36  4497.1  263.68  4575.9  260.12  4582.3  258.96  4596.7   258.3
  4611.1  259.32  4639.9  257.17  4654.3  257.19  4660.7  255.77  4703.9  255.11
  4745.5  252.54  4757.3  250.09  4831.8  252.72  4903.2     252  4916.6  251.19
  4945.4  252.61  4974.2  251.63    4995  250.39  5056.5  250.38  5114.8  251.95
  5166.4  254.08  5189.5  253.32  5237.4  254.74  5258.7  253.48  5276.3   254.1
  5281.8  255.41  5386.1  261.68    5441  266.86  5454.2   266.8    5463  267.78
#Mann= 6 ,-1 , 0
  4475.9     .17       0  4497.1     .11       0  4903.2     .17       0
  4974.2     .07       0  5114.8     .15       0  5237.4     .17       0
Bank Sta=4974.2,5114.8
XS Rating Curve= 0 ,0
Exp/Cntr=0.3,0.1

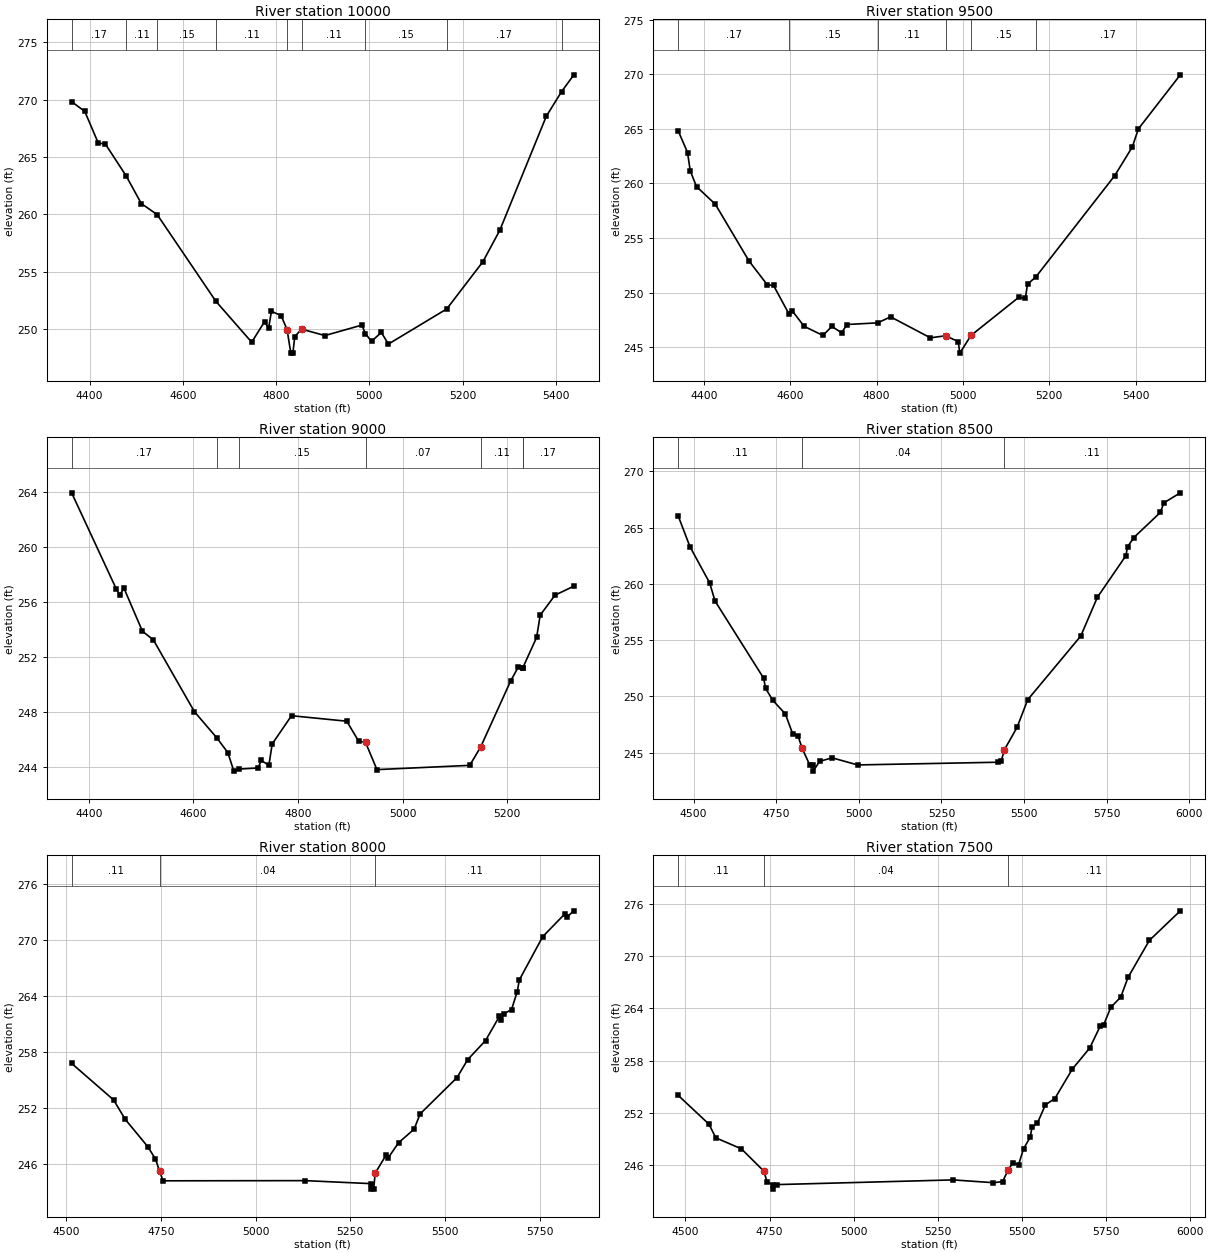
Type RM Length L Ch R = 1 ,10000   ,500,500,500
BEGIN DESCRIPTION:
CANEY CREEK TRIBUTARY NO. 2 20.0
END DESCRIPTION:
XS GIS Cut Line= 3
      3727567.88     10110811.05      3728080.32     10110429.98
      3728317.87     10110061.05
#Sta/Elev= 30
  4361.4  269.81  4389.5  268.97  4418.7  266.19  4433.3  266.15  4478.2  263.36
  4510.9  260.94  4544.9  259.98  4670.9  252.43  4747.7  248.87  4775.4  250.67
  4783.8  250.07    4790  251.56  4810.8  251.19  4823.6249.9606  4831.6  247.92
    4836  247.92  4840.1  249.36  4854.7  250.01  4904.7  249.45    4984  250.36
  4991.8   249.6  5004.7  248.95  5025.8  249.72    5041  248.71  5166.2  251.77
  5243.7  255.88    5280  258.62  5379.7  268.54  5412.5  270.69  5438.8  272.15
#Mann= 9 ,-1 , 0
  4361.4     .17       0  4478.2     .11       0  4544.9     .15       0
  4670.9     .11       0  4823.6     .07       0  4854.7     .11       0
  4991.8     .15       0  5166.2     .17       0  5412.5     .11       0
Bank Sta=4823.6,4854.7
XS Rating Curve= 0 ,0
Exp/Cntr=0.3,0.1

Type RM Length L Ch R = 1 ,9500    ,500,500,500
BEGIN DESCRIPTION:
CANEY CREEK TRIBUTARY NO. 2 19.0
END DESCRIPTION:
XS GIS Cut Line= 3
      3727967.84     10111111.08       3728490.6     10110708.68
      3728567.86     10110211.04
#Sta/Elev= 30
  4340.3  264.83  4362.1  262.83  4368.4  261.15  4382.9  259.71  4426.4   258.1
  4504.4  252.91  4546.9  250.72  4561.4  250.66    4597  248.06  4604.9  248.33
    4632  246.93  4675.6  246.09  4696.4  246.91  4718.9  246.34  4731.7  247.09
  4802.6  247.24  4832.5  247.79  4924.7  245.87    4960  246.06  4989.1  245.53
  4992.9  244.47  5018.8  246.09  5129.1  249.57  5144.7   249.5  5149.7  250.78
  5169.1  251.45  5351.8  260.72  5392.3  263.33  5406.6     265  5503.6  269.94
#Mann= 6 ,-1 , 0
  4340.3     .17       0    4597     .15       0  4802.6     .11       0
    4960     .04       0  5018.8     .15       0  5169.1     .17       0
Bank Sta=4960,5018.8
XS Rating Curve= 0 ,0
Exp/Cntr=0.3,0.1

Type RM Length L Ch R = 1 ,9000    ,500,500,500
BEGIN DESCRIPTION:
CANEY CREEK TRIBUTARY NO. 2 18.0
END DESCRIPTION:
XS GIS Cut Line= 3
      3728417.86     10111361.07      3728913.24     10110967.17
      3729167.87     10110761.05
#Sta/Elev= 30
  4367.1  263.95  4452.8  256.93  4459.2  256.52  4467.2  257.01  4502.5  253.88
  4523.3  253.26  4601.8  248.04  4644.5  246.14  4665.8  245.06  4677.3  243.71
  4687.2  243.86  4723.5  243.94  4729.9  244.49  4744.3  244.13  4750.7  245.69
  4787.6  247.74  4893.3  247.34  4915.8   245.9  4929.2   245.8    4951  243.82
  5128.5  244.13  5149.3  245.46  5206.9  250.28  5221.2  251.27  5229.8  251.21
    5230  251.23  5256.4  253.43  5263.2  255.05  5291.6  256.51  5327.6  257.16
#Mann= 7 ,-1 , 0
  4367.1     .17       0  4644.5     .11       0  4687.2     .15       0
  4929.2     .07       0  5149.3     .11       0  5229.8     .15       0
    5230     .17       0
Bank Sta=4929.2,5149.3
XS Rating Curve= 0 ,0
Exp/Cntr=0.3,0.1

Type RM Length L Ch R = 1 ,8500    ,500,500,500
BEGIN DESCRIPTION:
CANEY CREEK TRIBUTARY NO. 2 17.0
END DESCRIPTION:
XS GIS Cut Line= 3
      3728667.88     10111611.06      3729148.79      10111350.2
       3730117.9     10111261.07
#Sta/Elev= 30
  4452.9  266.05  4488.5  263.31  4548.4  260.08  4564.6  258.47  4711.9  251.61
  4717.6  250.72  4739.5  249.65  4777.5  248.44  4799.4   246.7  4815.6  246.51
  4828.3  245.39    4851  243.93  4861.4  243.86  4861.9  243.36  4881.2  244.23
  4919.2  244.54  4996.6  243.91  5420.8  244.15  5430.9  244.25  5440.9  245.27
    5479  247.25  5511.2   249.7  5671.9  255.36  5722.1   258.8  5808.4  262.49
  5813.4  263.28  5832.6  264.11  5912.9  266.34  5923.3  267.19  5973.2  268.08
#Mann= 3 , 0 , 0
  4452.9     .11       0  4828.3     .04       0  5440.9     .11       0
Bank Sta=4828.3,5440.9
XS Rating Curve= 0 ,0
Exp/Cntr=0.3,0.1

Type RM Length L Ch R = 1 ,8000    ,500,500,500
BEGIN DESCRIPTION:
CANEY CREEK TRIBUTARY NO. 2 16.0
END DESCRIPTION:
XS GIS Cut Line= 3
      3728817.87     10111761.07      3729300.65     10111814.27
      3730117.88     10112011.08
#Sta/Elev= 30
  4514.3   256.8  4624.9   252.9  4655.7  250.82  4715.5  247.88  4735.6  246.57
  4746.6  245.25  4755.7  244.23  5130.8  244.25  5303.6  243.93  5305.7  243.34
  5311.9  243.34    5316  245.05  5345.5  247.04  5350.7  246.71  5377.7  248.31
  5418.8  249.76  5434.5  251.39    5532  255.28  5560.3  257.21  5607.4  259.25
  5644.2  261.85  5649.3  261.47  5655.4  262.11    5676  262.56  5691.2   264.5
  5696.6  265.74  5758.3  270.37    5817  272.82  5822.2  272.47  5840.6  273.14
#Mann= 3 , 0 , 0
  4514.3     .11       0  4746.6     .04       0    5316     .11       0
Bank Sta=4746.6,5316
XS Rating Curve= 0 ,0
Exp/Cntr=0.3,0.1

Type RM Length L Ch R = 1 ,7500    ,438,438,438
BEGIN DESCRIPTION:
CANEY CREEK TRIBUTARY NO. 2 15.0
END DESCRIPTION:
XS GIS Cut Line= 3
      3728767.85     10112411.07      3729280.41     10112313.86
      3730217.83     10112061.08
#Sta/Elev= 30
  4478.3  254.02  4569.9   250.7  4590.3  249.13  4666.4  247.86  4732.8  245.31
  4742.9  244.04  4759.6  243.73  4760.1  243.23  4770.9  243.75  5295.7  244.29
  5415.4  243.97  5442.7  244.09 5458.87245.4131  5473.8  246.28  5490.1  246.03
  5504.9  247.86  5524.8   249.2    5530  250.32  5546.3  250.83  5569.9  252.92
  5598.1  253.65  5649.9  257.03  5701.6  259.45  5732.7  261.96  5743.1  262.12
  5764.3  264.13  5793.9  265.31  5815.6  267.58  5878.9  271.83  5970.9  275.23
#Mann= 3 , 0 , 0
  4478.3     .11       0  4732.8     .04       0 5458.87     .11       0
Bank Sta=4732.8,5458.87
XS Rating Curve= 0 ,0
Exp/Cntr=0.3,0.1

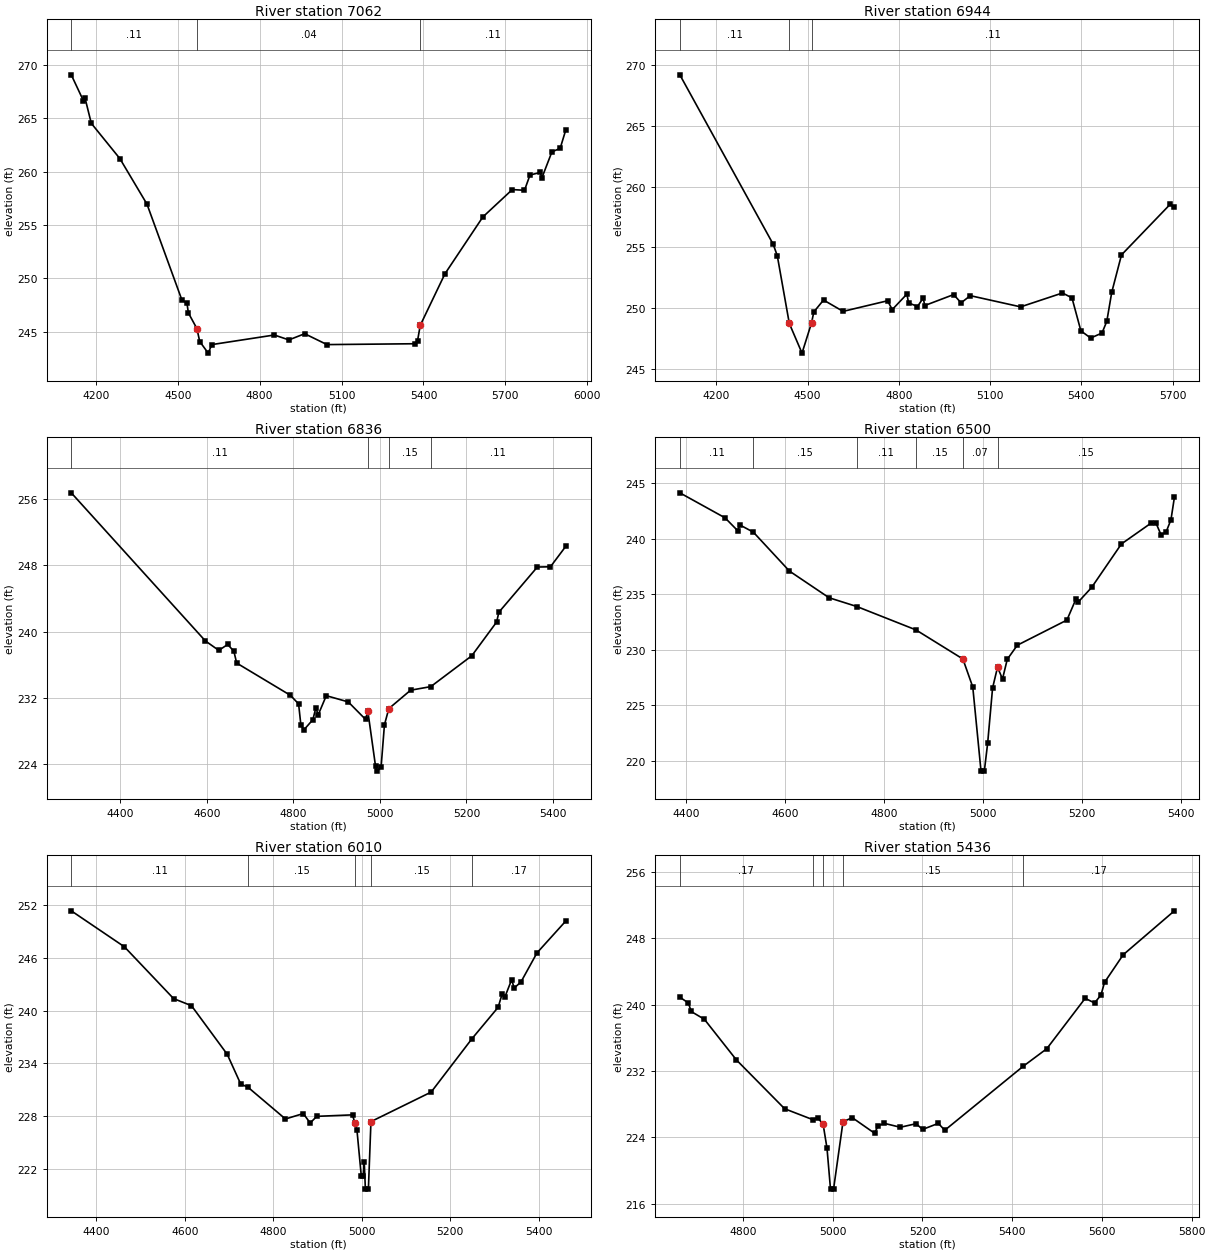
Type RM Length L Ch R = 1 ,7062    ,118,118,118
BEGIN DESCRIPTION:
CANEY CREEK TRIBUTARY NO. 2 10.0
END DESCRIPTION:
XS GIS Cut Line= 3
      3728445.84     10112396.69      3729268.73     10112754.32
      3730178.46     10112667.51
#Sta/Elev= 30
  4110.2  269.09  4154.7  266.66  4160.1  266.96  4183.6  264.54  4288.3  261.23
  4387.5  256.96  4515.8  247.94  4533.7   247.7  4539.1  246.76  4570.3  245.29
  4580.6  244.08  4611.7  242.99  4624.9  243.79  4853.8  244.69  4907.2  244.23
    4965  244.81  5046.7  243.79  5368.2  243.87  5378.2  244.14  5388.3   245.6
  5478.7  250.43  5617.5  255.76  5725.4  258.33    5770  258.26  5790.1  259.69
  5828.2  259.94  5833.3   259.4  5870.5  261.87  5900.6  262.19  5921.3  263.93
#Mann= 3 , 0 , 0
  4110.2     .11       0  4570.3     .04       0  5388.3     .11       0
Bank Sta=4570.3,5388.3
XS Rating Curve= 0 ,0
Exp/Cntr=0.3,0.1

Type RM Length L Ch R = 1 ,6944    ,108,108,108
BEGIN DESCRIPTION:
Mapping XS c528166a
END DESCRIPTION:
XS GIS Cut Line= 6
      3728431.95     10112486.97      3729171.51     10112855.01
      3729286.09     10112872.38      3729449.29     10112858.49
      3729636.79     10112823.76      3729949.33     10112723.06
#Sta/Elev= 30
  4079.7  269.18  4386.7  255.26  4400.1  254.32  4439.6  248.76  4481.4  246.32
  4512.7   248.8  4520.3  249.71  4552.2  250.68  4616.5  249.75  4762.6  250.62
  4778.2   249.9  4826.3  251.17  4831.7  250.45  4861.1  250.15  4879.7  250.84
  4885.1  250.23    4980  251.13  5004.4  250.45  5034.7  251.04  5200.2  250.12
  5337.7  251.26    5369  250.86  5398.3  248.15  5430.4  247.56  5467.7  247.97
  5483.5  248.93  5499.8  251.32  5531.8  254.39  5692.1  258.55  5705.7  258.32
#Mann= 3 , 0 , 0
  4079.7     .11       0  4439.6     .06       0  4512.7     .11       0
Bank Sta=4439.6,4512.7
XS Rating Curve= 0 ,0
Exp/Cntr=0.3,0.1

Type RM Length L Ch R = 1 ,6836    ,336,336,336
BEGIN DESCRIPTION:
CANEY CREEK TRIBUTARY NO. 2 9.0
END DESCRIPTION:
XS GIS Cut Line= 3
      3728598.58     10112789.04       3729287.6     10112973.94
        3729713.     10112914.07
#Sta/Elev= 30
  4286.6  256.73  4596.5  238.89  4627.5  237.75  4648.2  238.46  4662.4  237.64
  4668.9  236.22  4793.2  232.33    4812   231.3  4817.2   228.8  4824.2  228.17
    4845   229.4    4852  230.84  4857.2  229.97    4876  232.29  4926.8  231.54
  4966.8  229.43    4972  230.44  4989.9  223.77  4994.3   223.2  5002.7   223.7
  5010.4  228.77  5020.5  230.73  5070.9  232.95  5117.5  233.38  5212.3   237.1
  5269.8  241.17  5274.8  242.34  5363.8  247.79  5394.1  247.82  5429.6  250.29
#Mann= 4 ,-1 , 0
  4286.6     .11       0    4972     .07       0  5020.5     .15       0
  5117.5     .11       0
Bank Sta=4972,5020.5
XS Rating Curve= 0 ,0
Exp/Cntr=0.3,0.1

Type RM Length L Ch R = 1 ,6500    ,490,490,490
BEGIN DESCRIPTION:
CANEY CREEK TRIBUTARY NO. 2 8.0
END DESCRIPTION:
XS GIS Cut Line= 2
      3728716.61      10113344.6      3729714.76     10113271.82
#Sta/Elev= 30
  4386.8  244.12  4478.3  241.87  4503.7  240.72  4508.7  241.22  4535.6  240.58
  4608.6  237.08  4688.8  234.68    4745  233.89  4864.5  231.79  4959.6  229.17
  4979.6  226.65  4996.3  219.08    5003  219.08  5009.7  221.58  5019.7  226.56
  5029.7  228.43  5039.8  227.37  5049.4  229.14  5069.8  230.41  5170.1  232.67
  5188.4  234.56  5193.4  234.31  5220.2  235.61  5280.4  239.52  5340.6   241.4
  5350.6  241.38  5360.6  240.34  5370.6  240.57  5380.7   241.7  5387.6   243.7
#Mann= 6 ,-1 , 0
  4386.8     .11       0  4535.6     .15       0    4745     .11       0
  4864.5     .15       0  4959.6     .07       0  5029.7     .15       0
Bank Sta=4959.6,5029.7
XS Rating Curve= 0 ,0
Exp/Cntr=0.3,0.1

Type RM Length L Ch R = 1 ,6010    ,574,574,574
BEGIN DESCRIPTION:
CANEY CREEK TRIBUTARY NO. 2 7.0
END DESCRIPTION:
XS GIS Cut Line= 3
      3728779.16     10113858.48      3729431.93     10113757.79
      3729817.82     10113511.09
#Sta/Elev= 30
  4343.1  251.39  4463.2  247.29  4574.5  241.38    4615  240.57  4695.9  235.02
  4726.3  231.64  4742.8  231.27  4827.5  227.65  4867.9  228.27  4883.4  227.19
  4898.3  227.95  4979.2  228.12 4984.66227.1631  4989.3  226.35    4999  221.17
  5003.6  221.17  5005.7  222.76  5008.3  219.65  5015.1  219.65  5020.9  227.35
  5157.1  230.72  5249.6  236.82  5308.6  240.39  5317.8  241.95  5323.8  241.56
    5339  243.52  5344.9  242.59  5360.1  243.27  5396.5   246.6  5461.6  250.23
#Mann= 5 ,-1 , 0
  4343.1     .11       0  4742.8     .15       0 4984.66     .07       0
  5020.9     .15       0  5249.6     .17       0
Bank Sta=4984.66,5020.9
XS Rating Curve= 0 ,0
Exp/Cntr=0.3,0.1

Type RM Length L Ch R = 1 ,5436    ,497,497,497
BEGIN DESCRIPTION:
CANEY CREEK TRIBUTARY NO. 2 6.0
END DESCRIPTION:
XS GIS Cut Line= 3
       3729181.9     10114521.72      3729378.75     10114243.64
      3729967.84     10113761.08
#Sta/Elev= 30
  4659.3  240.91  4678.4   240.2  4684.6  239.18    4714  238.24  4785.4  233.34
  4892.9  227.45  4955.1  226.15  4966.4  226.36  4978.6   225.6  4987.3  222.69
  4995.1  217.76  5001.9  217.76    5023   225.9  5043.8  226.37  5093.3   224.5
  5101.2   225.4  5115.2  225.69  5150.7  225.22  5185.9  225.65  5200.3  224.96
  5235.4  225.69  5249.8  224.86    5424  232.55  5477.1  234.69  5562.7  240.77
  5583.5  240.21  5597.9  241.16  5605.8  242.69  5647.4  246.02  5761.5  251.32
#Mann= 5 ,-1 , 0
  4659.3     .17       0  4955.1     .15       0  4978.6     .07       0
    5023     .15       0    5424     .17       0
Bank Sta=4978.6,5023
XS Rating Curve= 0 ,0
Exp/Cntr=0.3,0.1