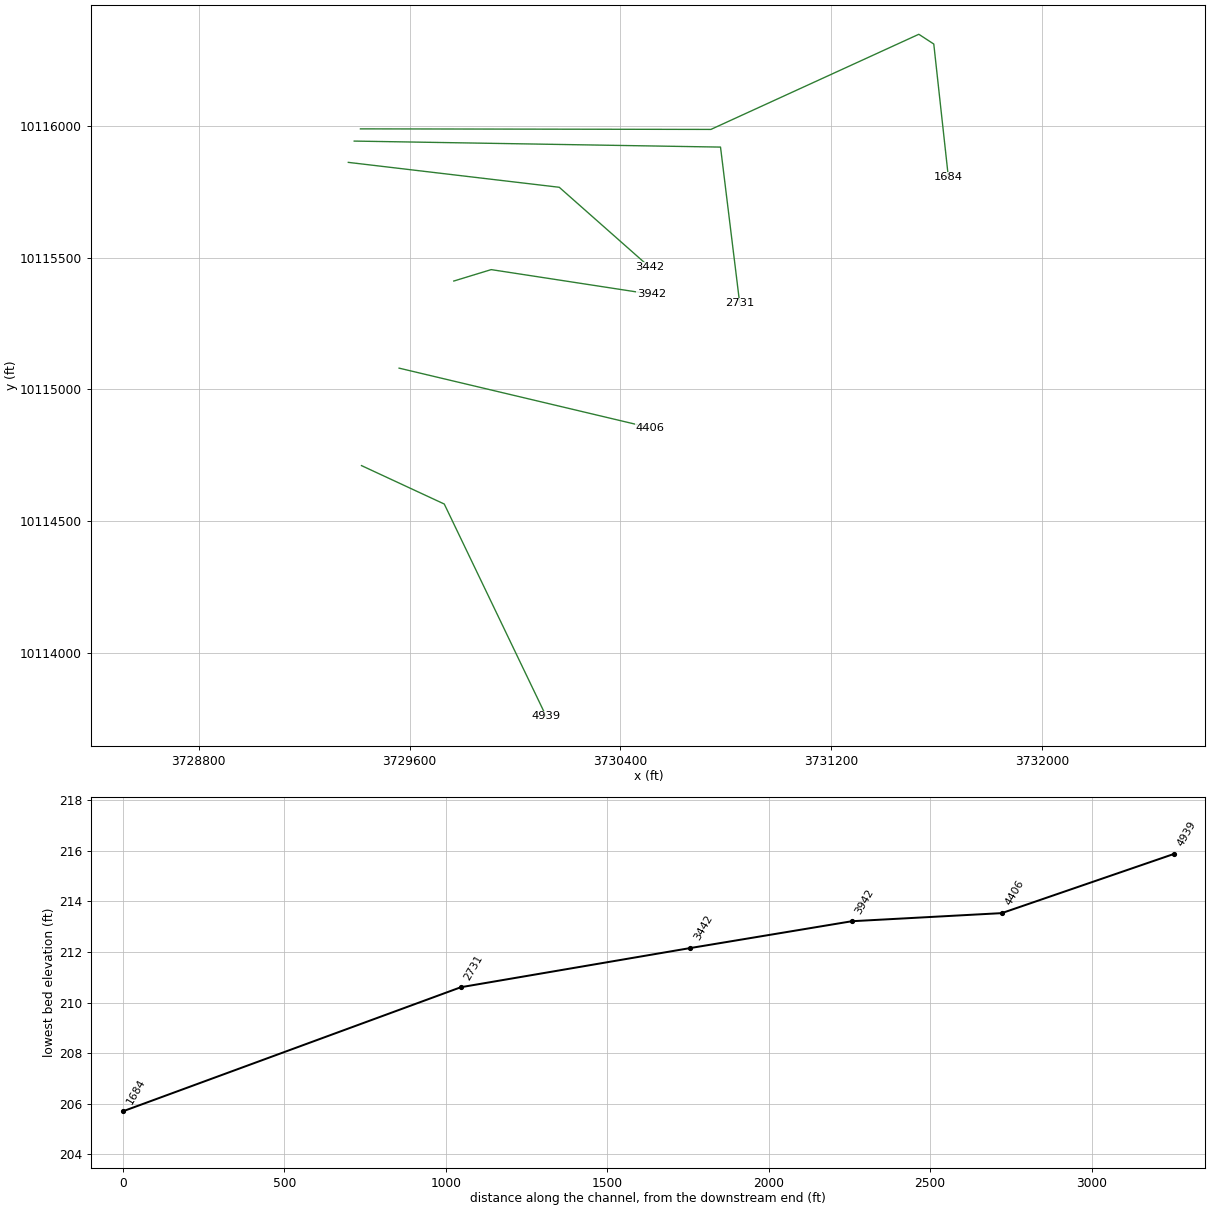
HEC-RAS study CANEY CREEK TRIBUTARY NO 2.prj: CANEY CREEK TRIBUTARY NO 2 Base Level Engineering

--- CANEY CREEK TRIBUTARY NO 2.g01 (geometry) --- (continued)

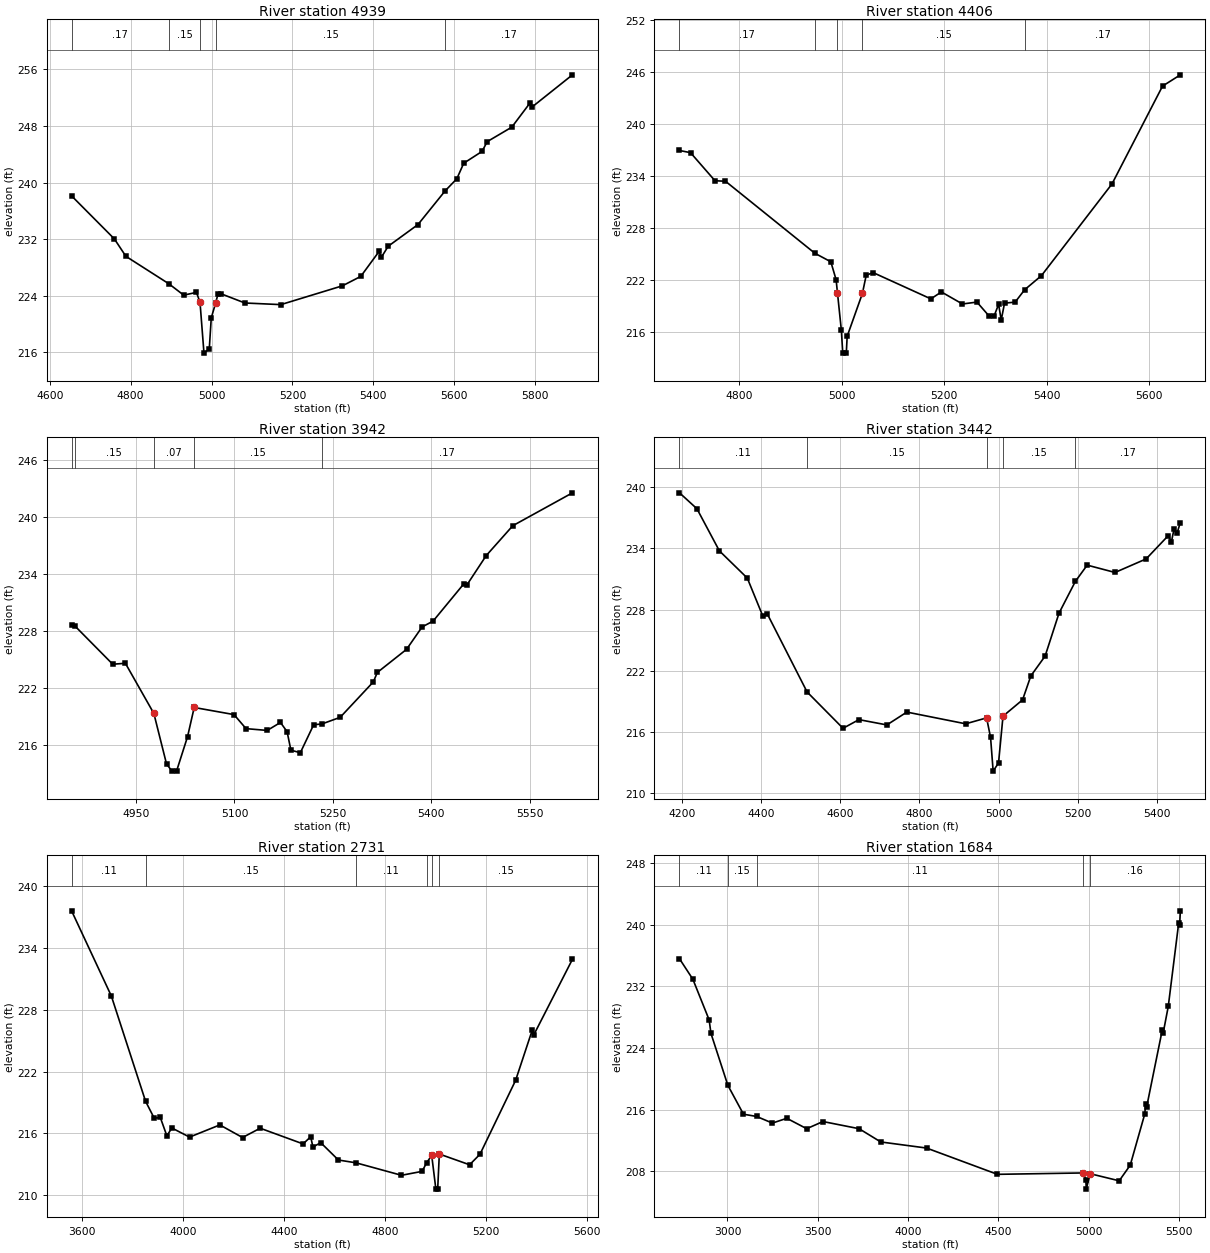
Type RM Length L Ch R = 1 ,4939    ,533,533,533
BEGIN DESCRIPTION:
CANEY CREEK TRIBUTARY NO. 2 5.0
END DESCRIPTION:
XS GIS Cut Line= 3
      3729417.82     10114711.09      3729731.74     10114565.37
      3730117.86     10113761.05
#Sta/Elev= 30
  4653.9  238.12  4759.7  232.03  4788.2  229.57  4894.6  225.68  4931.1  224.08
  4962.6  224.47  4971.4  223.07  4981.2  215.88  4994.3  216.49  4999.2  220.85
 5009.98 222.975  5015.9  224.24  5023.5  224.27  5082.4  222.97  5171.2  222.74
  5323.5   225.4  5368.8  226.73  5414.1  230.26  5419.6  229.42  5436.7     231
  5510.2  234.06  5577.6  238.84  5606.3  240.54  5623.4  242.74  5668.7  244.41
  5681.4  245.79  5742.2  247.84  5787.5  251.28    5793  250.72  5892.2  255.24
#Mann= 5 ,-1 , 0
  4653.9     .17       0  4894.6     .15       0  4971.4     .07       0
 5009.98     .15       0  5577.6     .17       0
Bank Sta=4971.4,5009.98
XS Rating Curve= 0 ,0
Exp/Cntr=0.3,0.1

Type RM Length L Ch R = 1 ,4406    ,464,464,464
BEGIN DESCRIPTION:
CANEY CREEK TRIBUTARY NO. 2 4.0
END DESCRIPTION:
XS GIS Cut Line= 2
      3729560.44      10115080.7      3730511.74     10114855.03
#Sta/Elev= 30
  4683.4  236.92  4704.9  236.67  4752.7  233.43  4773.2  233.37  4947.7  225.06
  4978.8  224.08  4989.1  222.01 4991.79220.4804  4999.3  216.21  5002.1  213.54
    5009  213.54  5010.7  215.48  5040.4  220.42  5047.8  222.51    5061  222.84
  5174.1   219.8  5194.6   220.6  5235.7  219.21    5264  219.43  5287.1  217.86
  5297.4  217.81  5306.3  219.17  5311.4  217.36  5317.9  219.31  5338.5  219.42
  5357.1  220.85  5389.9  222.48  5527.6  233.06  5626.3  244.35  5661.1  245.65
#Mann= 5 ,-1 , 0
  4683.4     .17       0  4947.7     .15       0 4991.79     .07       0
  5040.4     .15       0  5357.1     .17       0
Bank Sta=4991.79,5040.4
XS Rating Curve= 0 ,0
Exp/Cntr=0.3,0.1

Type RM Length L Ch R = 1 ,3942    ,500,500,500
BEGIN DESCRIPTION:
CANEY CREEK TRIBUTARY NO. 2 3.0
END DESCRIPTION:
XS GIS Cut Line= 3
      3729767.88     10115411.08      3729909.72     10115454.38
      3730517.81     10115361.08
#Sta/Elev= 30
  4851.7  228.64  4856.5  228.54  4914.4  224.49  4933.7  224.59  4977.1   219.3
  4996.4  213.98  5004.7  213.22  5011.7  213.22  5028.5  216.86  5038.6  219.93
  5099.3  219.18  5117.6   217.7  5149.9  217.51  5170.1  218.35  5180.2  217.38
    5186  215.43  5200.4  215.16  5220.7  218.11  5233.1  218.19  5261.1  218.89
  5311.7  222.63  5317.7  223.62  5362.3  226.06    5386  228.42  5402.8  229.04
  5449.4  232.95  5454.4  232.86  5483.7  235.94  5524.2  239.09  5615.2  242.56
#Mann= 5 ,-1 , 0
  4851.7     .17       0  4856.5     .15       0  4977.1     .07       0
  5038.6     .15       0  5233.1     .17       0
Bank Sta=4977.1,5038.6
XS Rating Curve= 0 ,0
Exp/Cntr=0.3,0.1

Type RM Length L Ch R = 1 ,3442    ,711,711,711
BEGIN DESCRIPTION:
CANEY CREEK TRIBUTARY NO. 2 2.0
END DESCRIPTION:
XS GIS Cut Line= 3
      3729367.85     10115861.07      3730167.79     10115766.63
      3730511.82     10115462.63
#Sta/Elev= 30
  4194.5  239.45  4238.5  237.89  4295.2  233.76  4365.7  231.09  4404.3  227.42
    4416  227.59  4516.7  219.92  4607.4  216.36  4647.6  217.21  4718.1  216.69
  4768.5  217.95    4917   216.8  4969.9  217.38  4979.9  215.46  4986.4  212.16
    5000  212.96  5011.3  217.55  5060.7  219.15  5081.6   221.5  5117.6  223.44
  5152.7  227.65  5194.1  230.77  5223.8  232.36  5294.1  231.64  5372.7  232.97
  5428.7  235.26  5436.3  234.62    5443  235.87  5450.5  235.48  5459.1  236.54
#Mann= 5 ,-1 , 0
  4194.5     .11       0  4516.7     .15       0  4969.9     .07       0
  5011.3     .15       0  5194.1     .17       0
Bank Sta=4969.9,5011.3
XS Rating Curve= 0 ,0
Exp/Cntr=0.3,0.1

Type RM Length L Ch R = 1 ,2731    ,1047,1047,1047
BEGIN DESCRIPTION:
Mapping XS 6d0d32d1
END DESCRIPTION:
XS GIS Cut Line= 3
      3729390.25     10115941.82      3730779.39     10115919.05
      3730852.07     10115327.22
#Sta/Elev= 30
  3558.3  237.57  3715.9  229.32  3851.6  219.12  3885.9  217.48    3910  217.55
  3935.9  215.78    3956  216.53    4026  215.65    4146  216.83    4236  215.61
    4306  216.51    4476  214.99    4506  215.68  4515.2  214.69    4546  215.11
    4616  213.43  4685.6  213.16  4866.1  211.95  4947.6  212.33  4966.1  213.17
  4985.9  213.88  5002.4  210.61  5009.6  210.61  5016.1  214.01  5136.1  212.97
  5177.3  213.99  5318.4  221.14  5385.1  226.06  5390.1  225.53  5543.9  232.88
#Mann= 6 ,-1 , 0
  3558.3     .11       0  3851.6     .15       0  4685.6     .11       0
  4966.1     .15       0  4985.9     .07       0  5016.1     .15       0
Bank Sta=4985.9,5016.1
XS Rating Curve= 0 ,0
Exp/Cntr=0.3,0.1

Type RM Length L Ch R = 1 ,1684    ,0,0,0
BEGIN DESCRIPTION:
CANEY CREEK TRIBUTARY NO. 2 1.0
END DESCRIPTION:
XS GIS Cut Line= 5
      3729413.79     10115988.17      3730742.85     10115986.07
      3731531.44     10116346.88      3731588.18     10116309.88
      3731643.56     10115804.51
#Sta/Elev= 30
  2734.3  235.59  2808.4  232.93  2898.4  227.66  2908.4  225.91    3002  219.17
  3088.4  215.42  3160.9  215.13  3248.4  214.27  3328.4  214.89  3438.4  213.54
  3528.4  214.47  3728.4  213.54  3848.4  211.82  4101.9  211.03  4494.1  207.62
  4968.4   207.8  4983.5  206.94  4985.8   205.7  5007.2   207.7  5168.1  206.78
  5229.2  208.81    5309   215.4  5315.3  216.77  5320.3  216.39  5406.5  226.35
  5411.5  225.95  5439.7  229.41  5497.6  240.27  5502.7  239.99  5506.7  241.81
#Mann= 5 ,-1 , 0
  2734.3     .11       0    3002     .15       0  3160.9     .11       0
  4968.4     .04       0  5007.2     .16       0
Bank Sta=4968.4,5007.2
XS Rating Curve= 0 ,0
Exp/Cntr=0.3,0.1

Chan Stop Cuts=-1
Use User Specified Reach Order=0
Composite Channel Slope=5