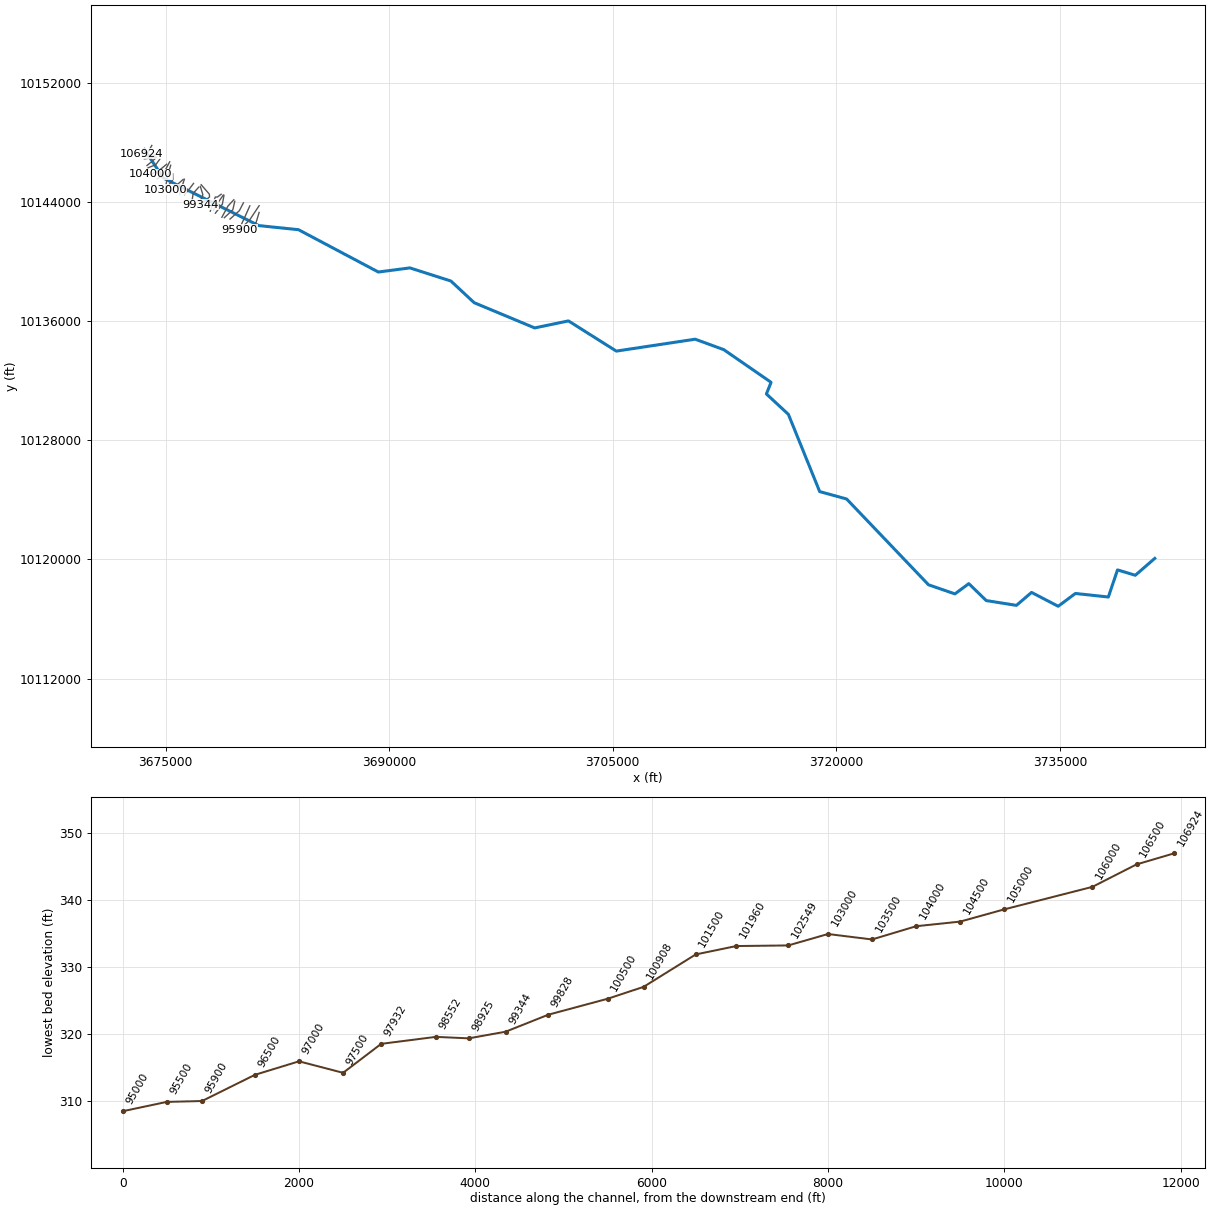
--- CANEY CREEK.prj (project) ---

Proj Title=CANEY CREEK Base Level Engineering
Current Plan=p01
Default Exp/Contr=0.3,0.1
English Units
Geom File=g01
Flow File=f01
Flow File=f02
Plan File=p01
Y Axis Title=Elevation
X Axis Title(PF)=Main Channel Distance
X Axis Title(XS)=Station
BEGIN DESCRIPTION:
CANEY CREEK
END DESCRIPTION:
DSS Export Rating Curves= 0
DSS Export Rating Curve Sorted= 0
DSS Export Volume Flow Curves= 0
DXF OffsetX= 0
DXF OffsetY= 0
DXF ScaleX= 1
DXF ScaleY= 10

--- CANEY CREEK.p01 (plan) ---

Plan Title=Multiple Run
Short Identifier=Multiple
Geom File=g01
Flow File=f01
Subcritical Flow
K Sum by GR= 0
Std Step Tol= 0.01
Critical Tol= 0.01
Num of Std Step Trials= 20
Max Error Tol= 0.3
Flow Tol Ratio= 0.001
Split Flow NTrial= 30
Split Flow Tol= 0.02
Split Flow Ratio= 0.02
Log Output Level= 0
Friction Slope Method= 1
Unsteady Friction Slope Method= 2
Unsteady Bridges Friction Slope Method= 1
Parabolic Critical Depth
Global Vel Dist=  1 , 1 , 1
Global Log Level= 0
CheckData=True
Encroach Param= -1, 0, 0, 0
BEGIN DESCRIPTION:
Multiple Run
END DESCRIPTION:

--- CANEY CREEK.f01 (steady flow) ---

Flow Title=Multiple
Program Version=4.10
Number of Profiles= 7
Profile Names=10-year,25-year,50-year,1pct_min,100-year,1pct_plu,500-year
River Rch & RM=CANEY CREEK,Reach-1         ,106924
     628     852    1151     512    1547    4672    2886
River Rch & RM=CANEY CREEK,Reach-1         ,101960
     705     961    1303     580    1752    5291    3287
River Rch & RM=CANEY CREEK,Reach-1         ,98925
    1235    1733    2397    1087    3283    9915    6378
River Rch & RM=CANEY CREEK,Reach-1         ,93543
    1323    1863    2583    1174    3545   10706    6918
River Rch & RM=CANEY CREEK,Reach-1         ,91518
    2235    3209    4507    2072    6256   18893   12487
River Rch & RM=CANEY CREEK,Reach-1         ,87785
    2654    3841    5422    2504    7561   22834   15236
River Rch & RM=CANEY CREEK,Reach-1         ,82455
    2881    4159    5860    2700    8155   24628   16357
River Rch & RM=CANEY CREEK,Reach-1         ,80160
    3584    5223    7412    3436   10378   31341   21082
River Rch & RM=CANEY CREEK,Reach-1         ,78044
    3725    5434    7713    3578   10806   32634   21966
River Rch & RM=CANEY CREEK,Reach-1         ,74967
    3664    5314    7514    3471   10483   31658   21132
River Rch & RM=CANEY CREEK,Reach-1         ,71114
    4144    6045    8580    3978   12013   36279   24390
River Rch & RM=CANEY CREEK,Reach-1         ,66498
    4173    6074    8609    3985   12034   36342   24353
River Rch & RM=CANEY CREEK,Reach-1         ,61591
    4537    6600    9352    4325   13062   39447   26392
River Rch & RM=CANEY CREEK,Reach-1         ,54351
    5152    7534   10712    4971   15012   45336   30537
River Rch & RM=CANEY CREEK,Reach-1         ,50986
    5296    7751   11027    5121   15464   46701   31486
River Rch & RM=CANEY CREEK,Reach-1         ,49417
    5699    8320   11816    5475   16535   49935   33521
River Rch & RM=CANEY CREEK,Reach-1         ,46124
    5888    8578   12167    5630   17003   51348   34366
River Rch & RM=CANEY CREEK,Reach-1         ,42510
    6393    9327   13243    6134   18524   55942   37505
River Rch & RM=CANEY CREEK,Reach-1         ,38750
    6755    9893   14084    6541   19752   59650   40202
River Rch & RM=CANEY CREEK,Reach-1         ,35924
    6638    9689   13762    6376   19254   58146   39001
River Rch & RM=CANEY CREEK,Reach-1         ,32041
    6925   10140   14433    6701   20237   61115   41172
River Rch & RM=CANEY CREEK,Reach-1         ,30832
    6408    9297   13151    6066   18318   55319   36780
River Rch & RM=CANEY CREEK,Reach-1         ,23606
    7856   11535   16453    7653   23111   69794   47181
River Rch & RM=CANEY CREEK,Reach-1         ,21558
    7538   10973   15558    7191   21717   65584   43777
River Rch & RM=CANEY CREEK,Reach-1         ,18829
    7468   10852   15367    7093   21421   64690   43069
River Rch & RM=CANEY CREEK,Reach-1         ,15557
    8225   12029   17110    7934   23959   72355   48604
River Rch & RM=CANEY CREEK,Reach-1         ,11692
    8225   12017   17081    7915   23902   72183   48420
River Rch & RM=CANEY CREEK,Reach-1         ,7124
    7766   11271   15946    7353   22205   67058   44546
Boundary for River Rch & Prof#=CANEY CREEK,Reach-1         , 1
Up Type= 0
Dn Type= 3
Dn Slope=0.0005
Boundary for River Rch & Prof#=CANEY CREEK,Reach-1         , 2
Up Type= 0
Dn Type= 3
Dn Slope=0.0005
Boundary for River Rch & Prof#=CANEY CREEK,Reach-1         , 3
Up Type= 0
Dn Type= 3
Dn Slope=0.0005
Boundary for River Rch & Prof#=CANEY CREEK,Reach-1         , 4
Up Type= 0
Dn Type= 3
Dn Slope=0.0005
Boundary for River Rch & Prof#=CANEY CREEK,Reach-1         , 5
Up Type= 0
Dn Type= 3
Dn Slope=0.0005
Boundary for River Rch & Prof#=CANEY CREEK,Reach-1         , 6
Up Type= 0
Dn Type= 3
Dn Slope=0.0005
Boundary for River Rch & Prof#=CANEY CREEK,Reach-1         , 7
Up Type= 0
Dn Type= 3
Dn Slope=0.0005
DSS Import GetInterval= 0
DSS Import GetPeak= 0
DSS Import FillOption= 0

--- CANEY CREEK.f02 (steady flow) ---

Flow Title=Orig_BLE_Flows
Program Version=4.10
Number of Profiles= 7
Profile Names=10-year,25-year,50-year,1pct_min,100-year,1pct_plu,500-year
River Rch & RM=CANEY CREEK,Reach-1         ,106924
     628     835    1001     394    1190    3593    1678
River Rch & RM=CANEY CREEK,Reach-1         ,101960
     705     942    1133     446    1348    4072    1911
River Rch & RM=CANEY CREEK,Reach-1         ,98925
    1235    1699    2084     836    2525    7625    3708
River Rch & RM=CANEY CREEK,Reach-1         ,93543
    1323    1826    2246     903    2727    8234    4022
River Rch & RM=CANEY CREEK,Reach-1         ,91518
    2235    3146    3919    1593    4812   14532    7260
River Rch & RM=CANEY CREEK,Reach-1         ,87785
    2654    3766    4715    1926    5816   17565    8858
River Rch & RM=CANEY CREEK,Reach-1         ,82455
    2881    4077    5096    2077    6273   18943    9510
River Rch & RM=CANEY CREEK,Reach-1         ,80160
    3584    5121    6445    2644    7983   24109   12257
River Rch & RM=CANEY CREEK,Reach-1         ,78044
    3725    5327    6707    2752    8312   25100   12771
River Rch & RM=CANEY CREEK,Reach-1         ,74967
    3664    5210    6534    2670    8064   24352   12286
River Rch & RM=CANEY CREEK,Reach-1         ,71114
    4144    5926    7461    3060    9241   27906   14180
River Rch & RM=CANEY CREEK,Reach-1         ,66498
    4173    5955    7486    3065    9257   27955   14159
River Rch & RM=CANEY CREEK,Reach-1         ,61591
    4537    6471    8132    3327   10048   30343   15344
River Rch & RM=CANEY CREEK,Reach-1         ,54351
    5152    7386    9315    3824   11548   34875   17754
River Rch & RM=CANEY CREEK,Reach-1         ,50986
    5296    7599    9589    3939   11895   35922   18306
River Rch & RM=CANEY CREEK,Reach-1         ,49417
    5699    8157   10275    4212   12719   38410   19489
River Rch & RM=CANEY CREEK,Reach-1         ,46124
    5888    8410   10580    4331   13079   39497   19980
River Rch & RM=CANEY CREEK,Reach-1         ,42510
    6393    9144   11516    4718   14249   43031   21805
River Rch & RM=CANEY CREEK,Reach-1         ,38750
    6755    9699   12247    5031   15194   45884   23373
River Rch & RM=CANEY CREEK,Reach-1         ,35924
    6638    9499   11967    4904   14811   44728   22675
River Rch & RM=CANEY CREEK,Reach-1         ,32041
    6925    9941   12550    5155   15567   47011   23937
River Rch & RM=CANEY CREEK,Reach-1         ,30832
    6408    9115   11436    4666   14091   42554   21384
River Rch & RM=CANEY CREEK,Reach-1         ,23606
    7856   11309   14307    5887   17778   53689   27431
River Rch & RM=CANEY CREEK,Reach-1         ,21558
    7538   10758   13529    5532   16705   50449   25452
River Rch & RM=CANEY CREEK,Reach-1         ,18829
    7468   10639   13363    5457   16478   49764   25040
River Rch & RM=CANEY CREEK,Reach-1         ,15557
    8225   11793   14878    6103   18430   55658   28258
River Rch & RM=CANEY CREEK,Reach-1         ,11692
    8225   11781   14853    6088   18386   55526   28151
River Rch & RM=CANEY CREEK,Reach-1         ,7124
    7766   11050   13866    5656   17081   51584   25899
Boundary for River Rch & Prof#=CANEY CREEK,Reach-1         , 1
Up Type= 0
Dn Type= 3
Dn Slope=0.0005
Boundary for River Rch & Prof#=CANEY CREEK,Reach-1         , 2
Up Type= 0
Dn Type= 3
Dn Slope=0.0005
Boundary for River Rch & Prof#=CANEY CREEK,Reach-1         , 3
Up Type= 0
Dn Type= 3
Dn Slope=0.0005
Boundary for River Rch & Prof#=CANEY CREEK,Reach-1         , 4
Up Type= 0
Dn Type= 3
Dn Slope=0.0005
Boundary for River Rch & Prof#=CANEY CREEK,Reach-1         , 5
Up Type= 0
Dn Type= 3
Dn Slope=0.0005
Boundary for River Rch & Prof#=CANEY CREEK,Reach-1         , 6
Up Type= 0
Dn Type= 3
Dn Slope=0.0005
Boundary for River Rch & Prof#=CANEY CREEK,Reach-1         , 7
Up Type= 0
Dn Type= 3
Dn Slope=0.0005
DSS Import GetInterval= 0
DSS Import GetPeak= 0
DSS Import FillOption= 0

--- CANEY CREEK.g01 (geometry) ---

Geom Title=Existing Conditions
Program Version=4.10

River Reach=CANEY CREEK     ,Reach-1
Reach XY= 30
      3673568.23     10147541.84      3674848.23     10145616.84
      3681248.23     10142426.84      3683911.26      10142151.5
      3689269.84     10139308.62      3691385.02     10139585.33
       3694137.4     10138704.85      3695698.21       10137249.
      3699760.22     10135553.47      3702025.78     10136025.53
      3705237.07     10133996.85      3710529.91     10134795.83
      3712449.81     10134093.74      3715624.31     10131899.93
      3715309.63     10131118.51      3716785.69     10129747.59
      3718885.39     10124559.65      3720693.66     10124061.84
      3726188.25     10118299.07      3727959.77     10117687.02
      3728893.17     10118376.32      3730062.95     10117238.24
      3732088.31     10116917.07      3733102.11     10117786.33
      3734890.21     10116856.89      3736044.34     10117716.45
        3738256.     10117477.68      3738871.94      10119300.7
      3740064.95     10118937.89      3741371.03     10120072.64

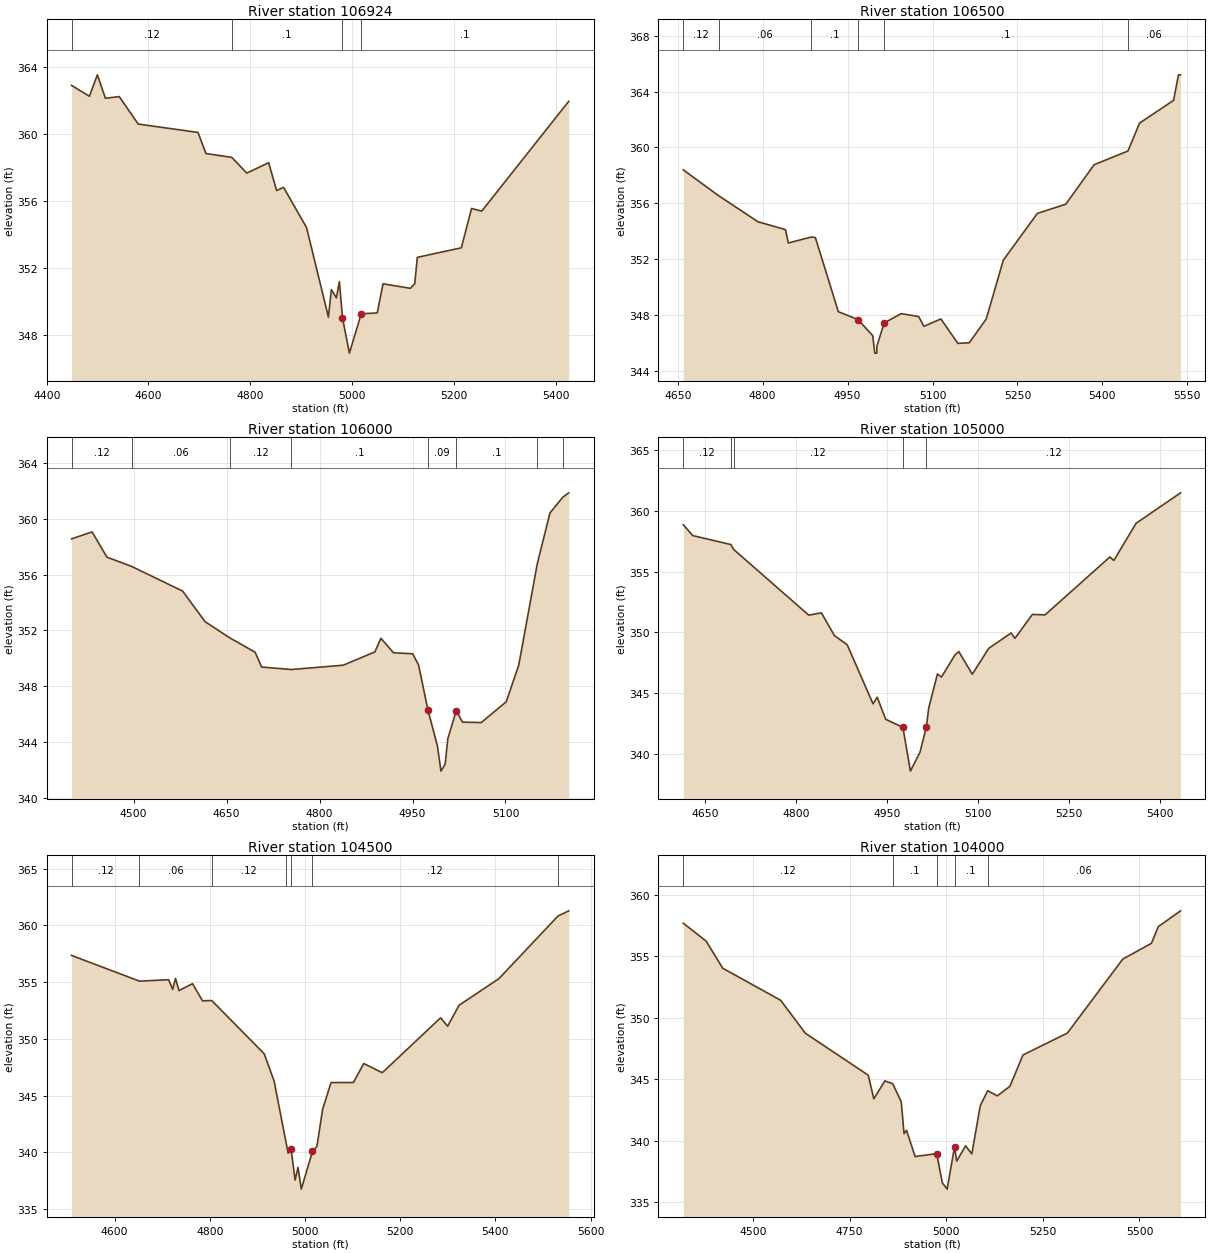
Type RM Length L Ch R = 1 ,106924  ,424,424,424
BEGIN DESCRIPTION:
CANEY CREEK 210.0
END DESCRIPTION:
XS GIS Cut Line= 3
      3674067.84     10147811.05      3673757.17     10147278.29
      3673396.94     10147265.27
#Sta/Elev= 30
  4448.8  362.89  4483.9  362.24  4499.6  363.52  4515.4  362.12  4542.6  362.22
  4579.9  360.58  4697.3  360.08    4713  358.82  4763.8  358.59  4793.2  357.65
  4836.2  358.27  4851.9  356.61  4865.5   356.8  4910.7   354.4  4953.7  349.05
  4959.5  350.69  4969.4   350.2  4975.2  351.17  4981.3  349.02  4994.9   346.9
  5018.2  349.25  5049.6   349.3    5061  351.04  5114.9  350.77  5123.4  351.05
  5128.4  352.62  5214.9  353.19    5235  355.54    5255  355.38    5426  361.94
#Mann= 4 ,-1 , 0
  4448.8     .12       0  4763.8      .1       0  4981.3     .09       0
  5018.2      .1       0
Bank Sta=4981.3,5018.2
XS Rating Curve= 0 ,0
Exp/Cntr=0.3,0.1

Type RM Length L Ch R = 1 ,106500  ,500,500,500
BEGIN DESCRIPTION:
CANEY CREEK 209.0
END DESCRIPTION:
XS GIS Cut Line= 3
      3674278.03     10147165.44      3673942.32     10147110.94
      3673405.57     10147074.29
#Sta/Elev= 30
  4659.9  358.39  4722.2  356.54  4791.8  354.67  4840.3  354.11  4845.3  353.15
    4886  353.58  4893.1  353.54  4933.6  348.23  4968.5  347.66  4994.4  346.51
    4998  345.26  5001.5  345.26  5001.7  345.76  5014.5  347.42  5044.6  348.09
  5075.5  347.88  5084.7  347.18  5114.7  347.71  5144.8  345.96  5164.9     346
  5194.9  347.71    5225  351.92  5285.1  355.27  5335.3  355.93  5385.4  358.76
  5445.1  359.74  5465.6  361.74  5525.7  363.37  5534.3   365.2    5538   365.2
#Mann= 6 ,-1 , 0
  4659.9     .12       0  4722.2     .06       0    4886      .1       0
  4968.5     .09       0  5014.5      .1       0  5445.1     .06       0
Bank Sta=4968.5,5014.5
XS Rating Curve= 0 ,0
Exp/Cntr=0.3,0.1

Type RM Length L Ch R = 1 ,106000  ,1000,1000,1000
BEGIN DESCRIPTION:
CANEY CREEK 208.0
END DESCRIPTION:
XS GIS Cut Line= 3
      3674360.47     10147035.23      3673768.23     10146937.19
      3673567.83     10146911.07
#Sta/Elev= 30
  4399.7  358.56  4432.8  359.06  4456.9  357.25  4496.6  356.59    4579  354.82
  4615.2  352.63    4655  351.47    4696  350.44  4706.4  349.38  4754.4   349.2
  4838.2  349.51  4889.2  350.46    4899  351.44  4919.3   350.4  4950.2  350.33
  4959.8  349.52 4974.81346.3109  4990.2  343.72  4995.9  341.92  5002.7  342.42
    5007  344.25  5020.6  346.25  5030.6  345.43  5060.9   345.4  5101.2  346.89
  5121.4  349.51  5151.4  356.79  5171.8  360.42  5192.6  361.55  5202.1  361.86
#Mann= 8 ,-1 , 0
  4399.7     .12       0  4496.6     .06       0    4655     .12       0
  4754.4      .1       0 4974.81     .09       0  5020.6      .1       0
  5151.4     .06       0  5192.6     .12       0
Bank Sta=4974.81,5020.6
XS Rating Curve= 0 ,0
Exp/Cntr=0.3,0.1

Type RM Length L Ch R = 1 ,105000  ,500,500,500
BEGIN DESCRIPTION:
CANEY CREEK 207.0
END DESCRIPTION:
XS GIS Cut Line= 3
      3674364.83     10146996.19      3674078.55     10146736.53
       3673741.3     10146463.52
#Sta/Elev= 30
  4613.5  358.85  4629.1  357.96  4692.1  357.22  4696.3  356.83  4820.4  351.41
  4841.3   351.6  4862.9  349.72  4883.9  348.97  4926.5  344.11  4933.4  344.65
  4947.4  342.84  4975.8  342.17  4988.2  338.57    5004  340.13 5014.38342.1808
  5018.4  343.77  5032.8  346.57  5039.5  346.32  5061.5  348.12    5068  348.41
  5090.3  346.55  5117.5  348.68  5154.3  349.94  5160.7   349.5  5189.4  351.47
  5210.3  351.43  5317.3   356.2  5323.8  355.91  5360.5  358.97  5433.9  361.48
#Mann= 5 ,-1 , 0
  4613.5     .12       0  4692.1     .06       0  4696.3     .12       0
  4975.8     .09       0 5014.38     .12       0
Bank Sta=4975.8,5014.38
XS Rating Curve= 0 ,0
Exp/Cntr=0.3,0.1

Type RM Length L Ch R = 1 ,104500  ,500,500,500
BEGIN DESCRIPTION:
CANEY CREEK 206.0
END DESCRIPTION:
XS GIS Cut Line= 3
      3674620.87     10146913.68      3674332.41     10146516.84
      3673817.83     10146311.06
#Sta/Elev= 30
  4509.4  357.35  4652.2  355.08  4713.4  355.21  4721.9  354.36    4728  355.32
  4735.2  354.25  4763.6  354.86  4784.6  353.35  4804.1  353.37  4914.3  348.68
  4935.2  346.26  4959.8  340.94  4964.5  339.92  4970.7  340.31  4979.2  337.55
  4985.4  338.66  4992.2  336.75  5015.7  340.07    5025  340.52  5037.2  343.81
  5054.7  346.14  5101.8  346.15  5123.4  347.82  5162.4  347.01  5284.9  351.85
  5299.7  351.11  5323.9  352.96  5407.4   355.3  5531.6  360.82  5554.2  361.28
#Mann= 7 ,-1 , 0
  4509.4     .12       0  4652.2     .06       0  4804.1     .12       0
  4959.8     .06       0  4970.7     .07       0  5015.7     .12       0
  5531.6     .06       0
Bank Sta=4970.7,5015.7
XS Rating Curve= 0 ,0
Exp/Cntr=0.3,0.1

Type RM Length L Ch R = 1 ,104000  ,500,500,500
BEGIN DESCRIPTION:
CANEY CREEK 205.0
END DESCRIPTION:
XS GIS Cut Line= 3
      3675063.61     10146549.13      3674537.96     10146117.11
      3673987.21     10145863.36
#Sta/Elev= 30
  4319.6   357.7  4378.8  356.24  4421.5  354.04  4571.5  351.43  4635.3  348.75
  4798.2  345.33  4812.6  343.41  4841.2  344.87  4861.4  344.64  4883.6  343.17
  4890.8  340.57  4897.2  340.85  4919.5  338.71  4975.4  338.95  4989.8  336.58
  5002.3  336.06  5021.5  339.51    5027  338.34    5050  339.58  5066.2  338.93
  5088.2  342.86  5107.3  344.07  5132.2  343.65  5164.8  344.43  5198.7  346.98
  5313.5  348.76  5456.8  354.78  5531.2  356.07  5548.6  357.42  5606.4  358.71
#Mann= 5 ,-1 , 0
  4319.6     .12       0  4861.4      .1       0  4975.4     .09       0
  5021.5      .1       0  5107.3     .06       0
Bank Sta=4975.4,5021.5
XS Rating Curve= 0 ,0
Exp/Cntr=0.3,0.1

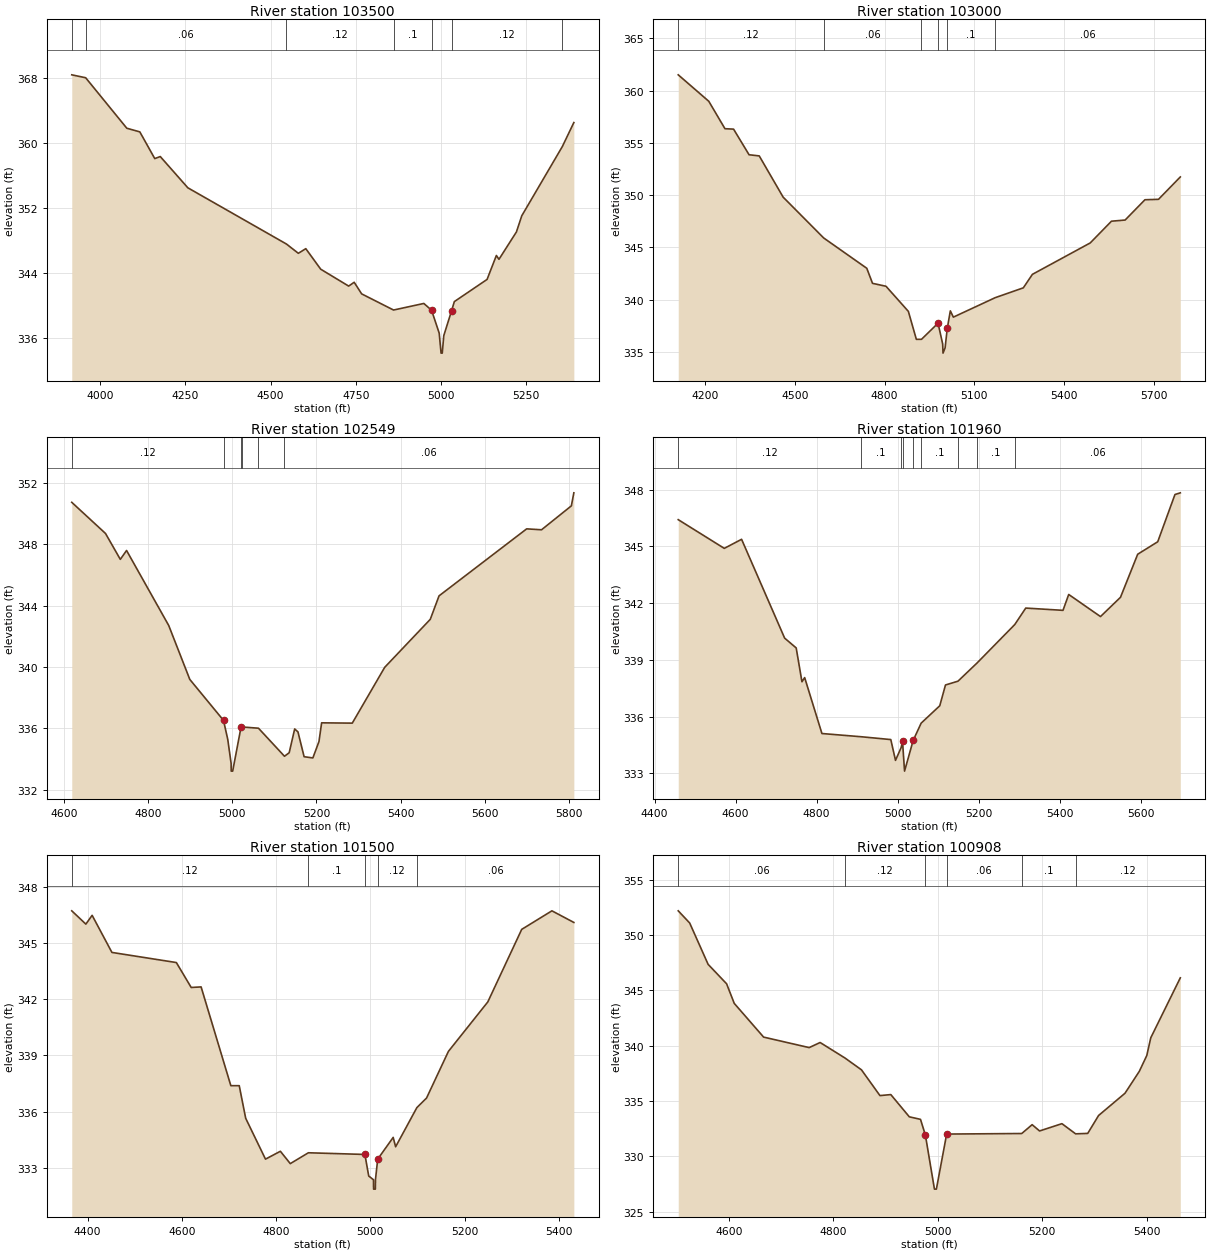
Type RM Length L Ch R = 1 ,103500  ,500,500,500
BEGIN DESCRIPTION:
CANEY CREEK 204.0
END DESCRIPTION:
XS GIS Cut Line= 3
      3675267.85     10146711.06      3674755.01     10145756.84
      3674417.83     10145561.06
#Sta/Elev= 30
  3916.7  368.38  3957.5  368.02  4078.2   361.8  4116.4  361.35  4160.2  358.06
  4176.4  358.31  4257.3  354.46  4546.7  347.53  4581.5  346.39  4603.4  346.96
  4647.2  344.43  4729.2  342.35  4745.4  342.82  4767.3  341.39  4860.9   339.4
  4949.8  340.21  4972.5  339.37  4994.8  336.55  5000.3  334.09  5003.8  334.09
  5008.3  336.25  5031.4  339.34  5039.3  340.44  5135.3  343.17  5162.6  346.12
  5170.2  345.65  5221.4  349.02  5237.1  351.01  5356.1  359.54  5389.9   362.5
#Mann= 7 ,-1 , 0
  3916.7     .12       0  3957.5     .06       0  4546.7     .12       0
  4860.9      .1       0  4972.5     .09       0  5031.4     .12       0
  5356.1     .06       0
Bank Sta=4972.5,5031.4
XS Rating Curve= 0 ,0
Exp/Cntr=0.3,0.1

Type RM Length L Ch R = 1 ,103000  ,451,451,451
BEGIN DESCRIPTION:
CANEY CREEK 203.0
END DESCRIPTION:
XS GIS Cut Line= 3
       3675332.7     10146479.72      3675101.31     10145620.53
      3674959.68     10144844.76
#Sta/Elev= 30
  4110.2   361.5  4212.4  358.97  4266.4  356.35  4295.2  356.31    4347  353.86
    4381  353.75  4460.9  349.81  4596.3  345.91  4740.5  343.01  4759.7  341.57
  4804.8  341.29  4879.5  338.89  4906.2  336.22  4923.4  336.22  4978.7  337.76
  4994.2  335.78  4995.4   334.9  5002.3   335.4  5009.6  337.27  5019.8  338.94
  5029.9  338.34  5169.8   340.2  5263.8  341.14  5294.2  342.43  5487.4  345.43
  5558.5  347.51  5604.1  347.62  5670.4  349.56  5715.7   349.6  5788.6  351.74
#Mann= 6 ,-1 , 0
  4110.2     .12       0  4596.3     .06       0  4923.4      .1       0
  4978.7     .09       0  5009.6      .1       0  5169.8     .06       0
Bank Sta=4978.7,5009.6
XS Rating Curve= 0 ,0
Exp/Cntr=0.3,0.1

Type RM Length L Ch R = 1 ,102549  ,589,589,589
BEGIN DESCRIPTION:
CANEY CREEK 202.0
END DESCRIPTION:
XS GIS Cut Line= 3
      3675467.85     10145911.08       3675484.6     10145524.81
      3674998.48     10144882.44
#Sta/Elev= 30
  4619.1  350.73  4699.2   348.7  4734.4  347.01  4749.2  347.59  4849.3   342.7
  4899.4  339.18  4979.4  336.51  4989.5  335.27  4997.5   333.7  4997.7   333.2
  5001.2   333.2  5020.9  336.05  5022.3  336.08  5062.4     336  5124.2  334.17
  5135.4   334.4  5148.4  335.95  5156.2  335.76  5170.8  334.14  5191.6  334.06
  5206.1  335.13  5212.4  336.35  5285.2  336.33  5362.2  339.97  5470.4   343.1
  5491.2  344.63  5699.3     349  5734.6  348.94  5805.4   350.5  5811.3  351.35
#Mann= 6 ,-1 , 0
  4619.1     .12       0  4979.4     .09       0  5020.9     .12       0
  5022.3     .06       0  5062.4      .1       0  5124.2     .06       0
Bank Sta=4979.4,5020.9
XS Rating Curve= 0 ,0
Exp/Cntr=0.3,0.1

Type RM Length L Ch R = 1 ,101960  ,460,460,460
BEGIN DESCRIPTION:
CANEY CREEK 201.0
END DESCRIPTION:
XS GIS Cut Line= 3
      3676170.37     10145529.16      3675766.72     10145173.25
       3675293.6     10144656.73
#Sta/Elev= 30
  4458.5  346.42  4572.1   344.9  4614.8  345.38    4721  340.15  4749.5  339.63
  4763.7  337.84  4770.4  338.06    4813   335.1  4909.9  334.93  4982.9  334.78
  4994.5  333.68  5008.5  334.36  5011.8  334.69  5016.8  333.11 5038.11334.7368
  5057.8  335.65  5103.7  336.57  5117.8  337.67  5148.6  337.87    5196  338.84
  5288.8  340.87  5315.8  341.74  5407.7  341.62  5421.8  342.46  5500.2  341.29
  5549.5  342.31    5592  344.59  5641.4  345.25  5683.9  347.75  5697.1  347.84
#Mann= 9 ,-1 , 0
  4458.5     .12       0  4909.9      .1       0  5008.5     .06       0
  5011.8     .07       0 5038.11     .06       0  5057.8      .1       0
  5148.6     .12       0    5196      .1       0  5288.8     .06       0
Bank Sta=5011.8,5038.11
XS Rating Curve= 0 ,0
Exp/Cntr=0.3,0.1

Type RM Length L Ch R = 1 ,101500  ,592,592,592
BEGIN DESCRIPTION:
CANEY CREEK 200.0
END DESCRIPTION:
XS GIS Cut Line= 3
      3676252.83     10145542.17      3676057.87     10144939.42
      3675931.66     10144526.58
#Sta/Elev= 30
  4366.5  346.71  4396.4     346  4409.7  346.47  4451.7  344.49  4588.4  343.95
  4619.9  342.62  4640.9  342.65    4704  337.38  4721.8  337.38  4735.5  335.64
  4777.5  333.46  4809.1  333.88  4830.1  333.22  4868.5   333.8  4988.4  333.71
  4996.5  332.56  5006.6  332.36  5006.9  331.86  5010.6  331.86  5010.8  332.36
  5015.6  333.46  5048.4  334.62  5053.6  334.12  5098.7  336.21  5119.2  336.72
  5165.6  339.21  5249.2  341.85  5321.1  345.72  5385.2  346.71  5431.7  346.09
#Mann= 5 ,-1 , 0
  4366.5     .12       0  4868.5      .1       0  4988.4     .09       0
  5015.6     .12       0  5098.7     .06       0
Bank Sta=4988.4,5015.6
XS Rating Curve= 0 ,0
Exp/Cntr=0.3,0.1

Type RM Length L Ch R = 1 ,100908  ,408,408,408
BEGIN DESCRIPTION:
CANEY CREEK 199.0
END DESCRIPTION:
XS GIS Cut Line= 3
      3676867.86     10145261.08      3676539.29     10144826.03
      3676267.83     10144511.05
#Sta/Elev= 30
  4503.1   352.2    4525   351.1  4560.3  347.36  4595.7   345.6  4610.3  343.83
  4666.5  340.78  4753.7  339.83  4774.7  340.29  4822.2  338.89  4853.8  337.82
  4889.2  335.49    4910  335.58  4945.4  333.57  4966.8  333.34 4976.14331.9247
  4993.5  327.03  4997.2  327.03  5016.9  332.01  5160.6  332.06  5180.5  332.86
  5194.7  332.29  5237.5  332.95  5263.7  332.03  5286.9  332.07  5307.7  333.69
  5358.2   335.7  5385.6  337.68  5399.9  339.11  5407.6  340.72  5464.1  346.14
#Mann= 6 ,-1 , 0
  4503.1     .06       0  4822.2     .12       0 4976.14     .09       0
  5016.9     .06       0  5160.6      .1       0  5263.7     .12       0
Bank Sta=4976.14,5016.9
XS Rating Curve= 0 ,0
Exp/Cntr=0.3,0.1

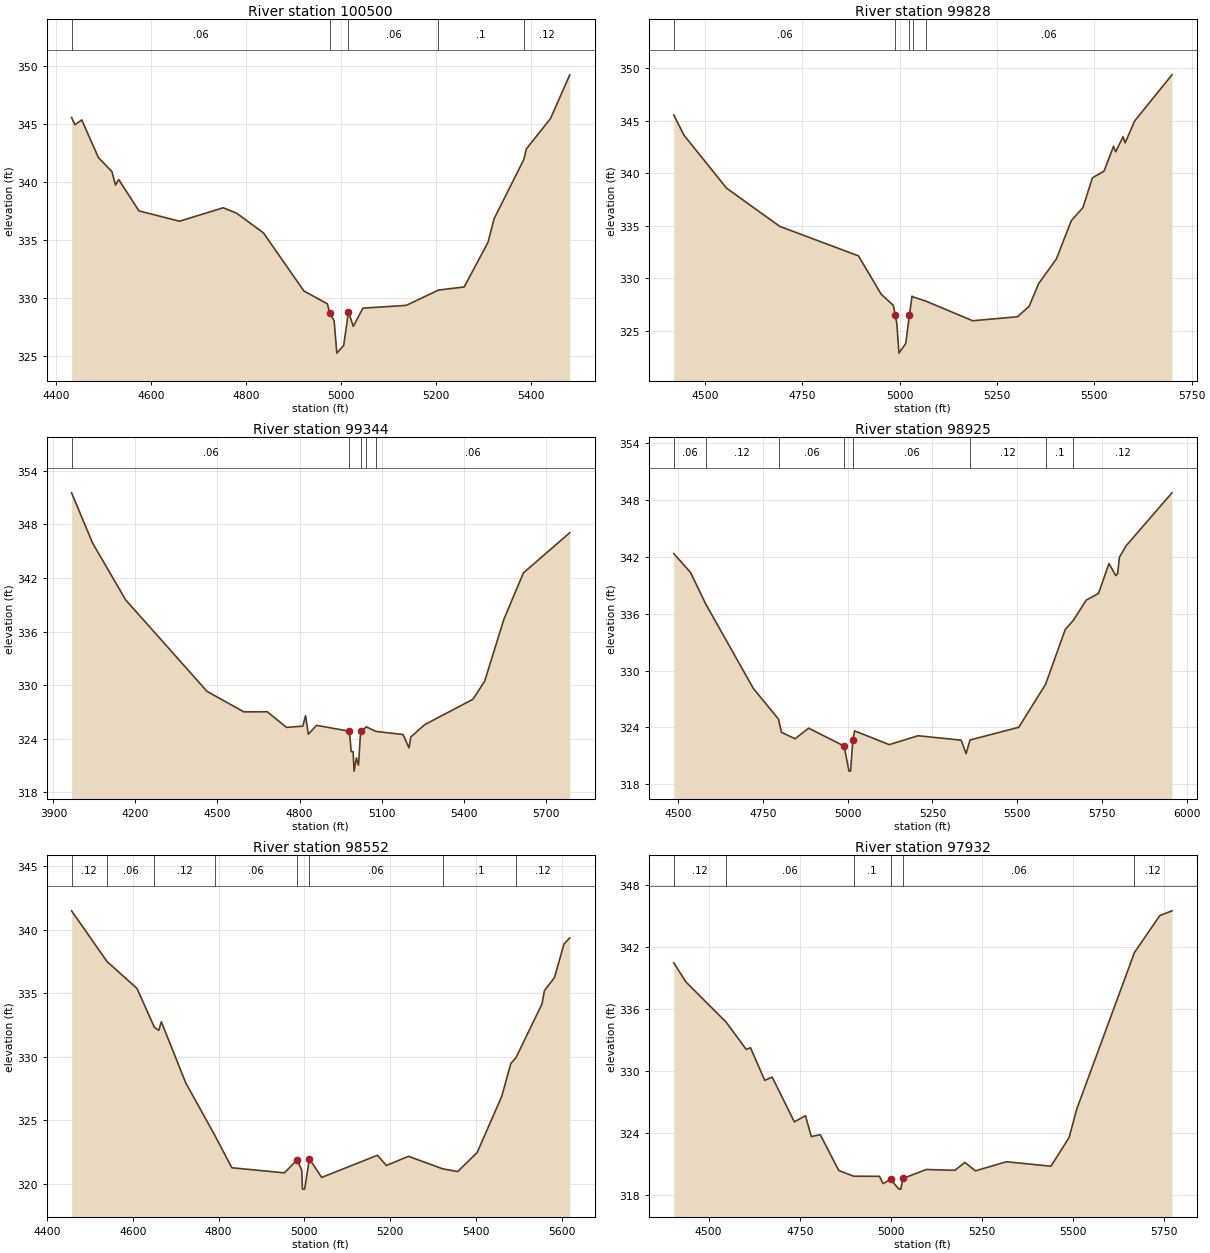
Type RM Length L Ch R = 1 ,100500  ,672,672,672
BEGIN DESCRIPTION:
CANEY CREEK 198.0
END DESCRIPTION:
XS GIS Cut Line= 3
      3677217.87     10145011.09      3676842.27     10144586.88
      3676767.85     10144111.06
#Sta/Elev= 30
  4433.4  345.59  4440.5  344.96  4454.8  345.38  4489.9  342.13  4518.3  340.92
  4525.9  339.76  4532.5  340.24  4575.2  337.53  4660.5  336.64  4752.5   337.8
  4780.7  337.33    4837  335.64  4922.3  330.62  4971.7  329.51  4976.1 328.765
  4985.9  328.04  4991.5  325.26  5005.9  325.92    5016  328.83  5026.1  327.57
  5046.4  329.14  5137.5  329.38  5205.4   330.7  5259.5  330.97  5309.5  334.81
  5322.3  336.85  5384.8  341.95  5390.5  342.89  5441.1   345.5  5481.6  349.27
#Mann= 5 ,-1 , 0
  4433.4     .06       0  4976.1     .06       0    5016     .06       0
  5205.4      .1       0  5384.8     .12       0
Bank Sta=4976.1,5016
XS Rating Curve= 0 ,0
Exp/Cntr=0.3,0.1

Type RM Length L Ch R = 1 ,99828   ,484,484,484
BEGIN DESCRIPTION:
CANEY CREEK 197.0
END DESCRIPTION:
XS GIS Cut Line= 3
      3677324.88      10145060.4      3677494.15     10144504.85
      3677238.53     10143854.98
#Sta/Elev= 30
  4420.3  345.54  4446.7  343.61  4555.6  338.59  4692.2  334.95  4894.5  332.14
  4952.7   328.5  4984.1  327.43 4988.62326.5615    4993  325.72  4998.5  322.89
  5015.9  323.81 5025.53326.5549    5032  328.31  5034.7  328.24  5067.2  327.84
  5187.8  325.97  5302.9  326.35  5332.7  327.34  5357.1   329.5  5402.7  331.85
    5441  335.49  5470.8  336.73  5495.2  339.56    5525   340.2  5549.4  342.56
  5554.8  342.04  5573.8  343.47  5579.2  342.89  5603.6  344.97  5699.4  349.36
#Mann= 5 ,-1 , 0
  4420.3     .06       0 4988.62     .06       0 5025.53     .06       0
  5034.7      .1       0  5067.2     .06       0
Bank Sta=4988.62,5025.53
XS Rating Curve= 0 ,0
Exp/Cntr=0.3,0.1

Type RM Length L Ch R = 1 ,99344   ,419,419,419
BEGIN DESCRIPTION:
CANEY CREEK 196.0
END DESCRIPTION:
XS GIS Cut Line= 4
      3677381.32     10145173.24      3677928.18     10144539.57
       3677941.2     10144352.94      3677333.55     10143836.44
#Sta/Elev= 30
  3966.6  351.54  4043.8  345.89  4164.5  339.54  4461.8   329.3  4596.7     327
  4682.2  327.01  4752.5  325.26  4812.1   325.4  4822.2  326.58  4832.2   324.5
  4862.3  325.49  4982.5  324.83  4989.1  322.54    4996  322.54  4999.6  320.36
  5008.2  321.84  5015.8  321.03  5022.3  324.24 5026.27324.8381  5044.7  325.32
  5079.2  324.81  5178.8  324.46  5200.3  322.96  5206.8  324.18  5257.4  325.56
  5434.2  328.41    5477  330.43  5547.3  337.37  5618.7  342.57  5788.2  347.07
#Mann= 5 ,-1 , 0
  3966.6     .06       0  4982.5     .06       0 5026.27     .06       0
  5044.7      .1       0  5079.2     .06       0
Bank Sta=4982.5,5026.27
XS Rating Curve= 0 ,0
Exp/Cntr=0.3,0.1

Type RM Length L Ch R = 1 ,98925   ,373,373,373
BEGIN DESCRIPTION:
CANEY CREEK 195.0
END DESCRIPTION:
XS GIS Cut Line= 4
      3678722.44     10144535.22      3678466.37     10144344.26
      3678327.48      10144348.6      3677989.34     10143394.86
#Sta/Elev= 30
  4486.7  342.35  4535.8  340.38  4580.6  337.06  4721.3  328.12  4795.9  324.86
  4804.6  323.47  4844.7  322.79  4884.7  323.91  4989.5  322.02  5003.8  319.37
  5008.5  319.37  5015.1  322.64  5020.4  323.62  5122.8  322.17  5207.7  323.11
    5335  322.64  5349.5  321.22    5361  322.66  5504.8     324  5583.9  328.53
  5642.3  334.35  5665.9  335.29  5704.1  337.44  5740.3  338.14  5771.1   341.3
  5791.3  340.02  5796.7  340.26    5802  341.97  5822.3   343.2    5957  348.77
#Mann= 8 ,-1 , 0
  4486.7     .06       0  4580.6     .12       0  4795.9     .06       0
  4989.5     .06       0  5015.1     .06       0    5361     .12       0
  5583.9      .1       0  5665.9     .12       0
Bank Sta=4989.5,5015.1
XS Rating Curve= 0 ,0
Exp/Cntr=0.3,0.1

Type RM Length L Ch R = 1 ,98552   ,620,620,620
BEGIN DESCRIPTION:
CANEY CREEK 194.0
END DESCRIPTION:
XS GIS Cut Line= 3
      3678861.33      10144478.8      3678557.52      10144036.1
      3678217.88     10143511.11
#Sta/Elev= 30
  4456.9  341.47  4539.7  337.48  4609.5  335.37    4650  332.32  4660.3  332.07
  4666.3  332.75  4723.2  327.95  4790.9  323.83  4830.8  321.27  4953.3  320.87
  4983.1  321.89  4993.8  321.08  4995.6  319.59  5000.6  319.59  5011.7  321.97
  5040.4  320.51  5170.3  322.25  5191.4  321.45  5242.9  322.17  5322.3  321.19
  5357.6  320.97  5403.1  322.47  5460.5  326.89  5481.6  329.47  5493.6  329.92
  5554.2  334.14  5560.1   335.2  5583.4  336.22  5605.6  338.86  5619.1  339.34
#Mann= 8 ,-1 , 0
  4456.9     .12       0  4539.7     .06       0    4650     .12       0
  4790.9     .06       0  4983.1     .06       0  5011.7     .06       0
  5322.3      .1       0  5493.6     .12       0
Bank Sta=4983.1,5011.7
XS Rating Curve= 0 ,0
Exp/Cntr=0.3,0.1

Type RM Length L Ch R = 1 ,97932   ,432,432,432
BEGIN DESCRIPTION:
CANEY CREEK 193.0
END DESCRIPTION:
XS GIS Cut Line= 3
      3678909.07     10144457.06      3678804.91     10143871.17
      3678332.31     10143259.82
#Sta/Elev= 30
  4404.2  340.46  4437.7   338.6  4547.9  334.72  4603.3  332.07  4614.8  332.24
    4654  329.08  4674.4   329.4  4735.3  325.06  4765.8  325.66  4781.8  323.64
  4806.4  323.82  4857.2  320.35  4898.2   319.8  4968.9  319.79  4979.1  319.08
  4999.3   319.5  5022.5  318.55  5027.6  318.55  5033.2  319.58  5097.5  320.45
  5176.3  320.37  5203.4  321.14  5232.4  320.32  5317.5   321.2  5439.8  320.77
  5489.6  323.54  5510.4  326.28  5668.9  341.44  5738.6  345.03    5772  345.49
#Mann= 6 ,-1 , 0
  4404.2     .12       0  4547.9     .06       0  4898.2      .1       0
  4999.3     .07       0  5033.2     .06       0  5668.9     .12       0
Bank Sta=4999.3,5033.2
XS Rating Curve= 0 ,0
Exp/Cntr=0.3,0.1

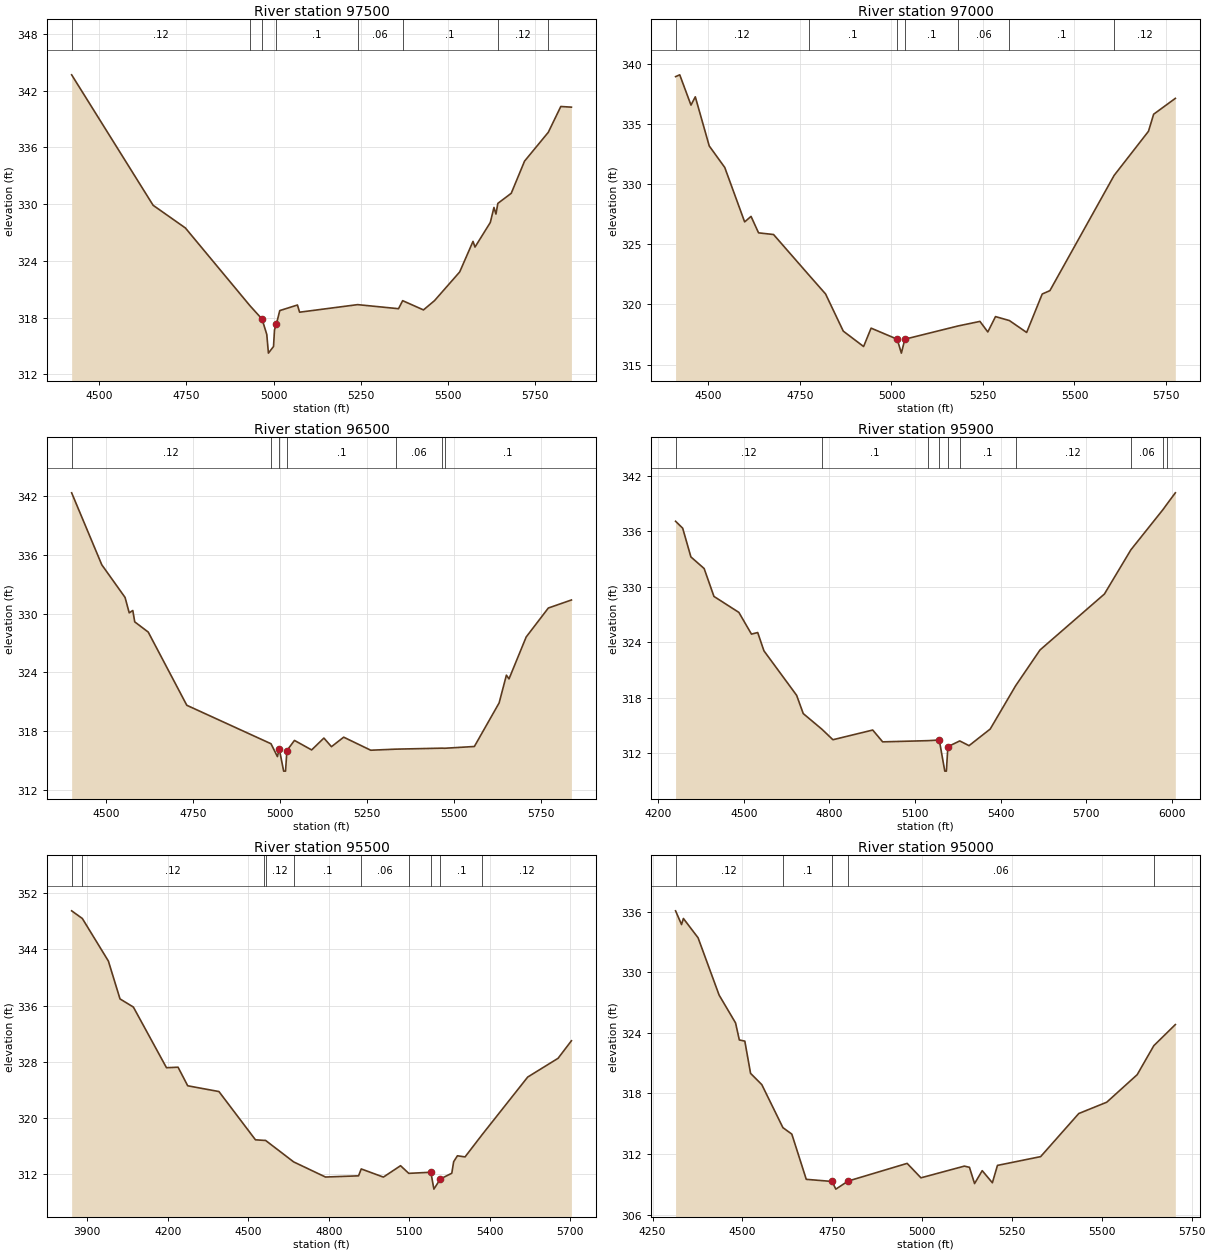
Type RM Length L Ch R = 1 ,97500   ,500,500,500
BEGIN DESCRIPTION:
CANEY CREEK 192.0
END DESCRIPTION:
XS GIS Cut Line= 3
      3679567.85     10144161.07      3679175.13     10143736.84
      3678770.29     10142985.93
#Sta/Elev= 30
  4421.9  343.68  4655.2  329.88  4747.6  327.48  4932.9  319.24    4967  317.85
  4980.7  316.22  4985.4  314.24    5000  314.94  5002.8  316.69  5008.5  317.36
  5017.9  318.74  5068.5  319.33  5074.7  318.57  5240.8  319.37    5358  318.94
  5369.8  319.79  5429.4  318.81    5461  319.79  5533.2  322.83  5571.3  326.06
    5577  325.46  5620.8  328.06  5631.3  329.65    5637  328.95  5642.4  330.08
  5680.8  331.15  5718.9  334.55  5786.9   337.6  5822.7  340.33  5853.1  340.26
#Mann= 8 ,-1 , 0
  4421.9     .12       0  4932.9      .1       0    4967     .09       0
  5008.5      .1       0  5240.8     .06       0  5369.8      .1       0
  5642.4     .12       0  5786.9     .06       0
Bank Sta=4967,5008.5
XS Rating Curve= 0 ,0
Exp/Cntr=0.3,0.1

Type RM Length L Ch R = 1 ,97000   ,500,500,500
BEGIN DESCRIPTION:
CANEY CREEK 191.0
END DESCRIPTION:
XS GIS Cut Line= 3
      3679633.91     10144062.17      3679504.07     10143486.84
      3678935.13     10142959.72
#Sta/Elev= 30
  4410.2  338.96  4421.6  339.11  4452.3  336.59  4464.1  337.28  4502.2  333.19
  4544.6   331.4  4598.9  326.87  4616.4  327.33  4636.9  325.96  4677.9  325.82
  4773.9  322.47  4820.1  320.87  4868.4  317.78  4923.9   316.5  4944.4  318.03
  5015.6  317.11  5027.1  315.95  5036.6  317.11    5182  318.21  5241.8  318.59
  5263.3  317.71  5284.3  318.99  5322.3  318.66  5369.4  317.67  5411.9  320.87
  5432.9  321.15  5608.4  330.74  5702.2  334.41  5716.3  335.83  5775.6  337.15
#Mann= 7 ,-1 , 0
  4410.2     .12       0  4773.9      .1       0  5015.6     .09       0
  5036.6      .1       0    5182     .06       0  5322.3      .1       0
  5608.4     .12       0
Bank Sta=5015.6,5036.6
XS Rating Curve= 0 ,0
Exp/Cntr=0.3,0.1

Type RM Length L Ch R = 1 ,96500   ,600,600,600
BEGIN DESCRIPTION:
CANEY CREEK 190.0
END DESCRIPTION:
XS GIS Cut Line= 3
      3680215.49     10143957.94      3679941.32     10143426.61
      3679317.08     10142868.58
#Sta/Elev= 30
  4402.1   342.3  4488.6  334.97  4555.5  331.64  4567.4  330.07  4577.7  330.31
  4583.3  329.15    4622  328.11  4732.8  320.65  4974.6  316.73    4993  315.42
  4998.3  316.22  5010.9  313.94  5016.3  313.94  5020.3  316.04    5042  317.07
  5091.3   316.1  5126.5  317.31  5148.2  316.43  5183.3   317.4    5261  316.07
  5333.2  316.18  5466.1  316.28  5473.2  316.27  5558.6  316.45  5629.7  320.89
  5650.6  323.72  5658.1  323.34  5707.4  327.61    5771  330.56  5837.3  331.38
#Mann= 7 ,-1 , 0
  4402.1     .12       0  4974.6      .1       0  4998.3     .09       0
  5020.3      .1       0  5333.2     .06       0  5466.1     .12       0
  5473.2      .1       0
Bank Sta=4998.3,5020.3
XS Rating Curve= 0 ,0
Exp/Cntr=0.3,0.1

Type RM Length L Ch R = 1 ,95900   ,400,400,400
BEGIN DESCRIPTION:
CANEY CREEK 189.0
END DESCRIPTION:
XS GIS Cut Line= 3
      3680645.18     10143753.96      3680345.71     10143081.24
      3679917.87     10142161.11
#Sta/Elev= 30
  4260.8   337.1  4285.7  336.35  4314.5  333.24  4360.9  331.98  4395.3  328.96
  4482.6  327.23  4526.7  324.88  4548.6  325.05  4570.4  323.07    4685  318.25
  4708.2  316.27  4773.9  314.57  4812.1  313.44  4951.6  314.49  4986.4  313.21
  5146.1  313.34  5184.8  313.41  5204.1  310.04  5209.7  310.04  5214.9  312.69
  5256.5  313.31  5289.1   312.8  5363.3   314.6  5452.4  319.29  5537.7  323.16
  5763.4  329.22  5856.2  334.01    5969  338.38  5981.9  338.93  6011.9  340.18
#Mann= 10 ,-1 , 0
  4260.8     .12       0  4773.9      .1       0  5146.1     .06       0
  5184.8     .09       0  5214.9     .06       0  5256.5      .1       0
  5452.4     .12       0  5856.2     .06       0    5969     .12       0
  5981.9     .06       0
Bank Sta=5184.8,5214.9
XS Rating Curve= 0 ,0
Exp/Cntr=0.3,0.1

Type RM Length L Ch R = 1 ,95500   ,500,500,500
BEGIN DESCRIPTION:
CANEY CREEK 188.0
END DESCRIPTION:
XS GIS Cut Line= 3
      3681267.84     10143761.06      3680626.79     10142797.28
      3680117.83     10142311.05
#Sta/Elev= 30
  3842.5  349.47  3882.3  348.38  3979.3  342.33  4022.6  336.95  4072.4  335.79
  4195.7  327.17  4238.8  327.24  4274.8   324.6  4391.1  323.78  4527.1  316.92
  4558.7  316.84  4564.6  316.84  4669.4  313.78  4787.9  311.63  4911.1   311.8
  4921.1  312.78  5003.6  311.62  5067.5  313.24  5098.1  312.15  5180.4  312.31
  5191.7  309.91  5215.9  311.36  5258.4  312.17  5265.3  313.81  5279.4  314.65
  5307.7  314.49  5371.7  317.67  5541.1  325.84  5654.3  328.51  5703.9     331
#Mann= 10 ,-1 , 0
  3842.5     .06       0  3882.3     .12       0  4558.7      .1       0
  4564.6     .12       0  4669.4      .1       0  4921.1     .06       0
  5098.1      .1       0  5180.4     .06       0  5215.9      .1       0
  5371.7     .12       0
Bank Sta=5180.4,5215.9
XS Rating Curve= 0 ,0
Exp/Cntr=0.3,0.1

Type RM Length L Ch R = 1 ,95000   ,500,500,500
BEGIN DESCRIPTION:
CANEY CREEK 187.0
END DESCRIPTION:
XS GIS Cut Line= 3
      3681267.86     10143311.09      3681071.69     10142653.64
      3680567.86     10142161.08
#Sta/Elev= 30
  4313.9  336.09  4330.5  334.73  4335.7  335.33  4376.5  333.42  4435.1  327.74
  4480.9  324.98  4491.3   323.3  4506.6  323.18  4522.6  319.99  4553.9  318.87
  4612.6  314.61  4637.4  313.97  4677.6  309.49  4749.1  309.28  4759.9  308.52
    4794  309.32  4958.3  311.07  4996.7  309.64  5117.6   310.8  5131.7  310.68
  5145.9  309.07  5167.2  310.35  5195.5  309.15  5209.6  310.87  5329.8  311.74
  5435.9  316.01  5513.7  317.13  5598.5  319.86  5644.7  322.73  5704.6  324.82
#Mann= 5 ,-1 , 0
  4313.9     .12       0  4612.6      .1       0  4749.1     .06       0
    4794     .06       0  5644.7      .1       0
Bank Sta=4749.1,4794
XS Rating Curve= 0 ,0
Exp/Cntr=0.3,0.1