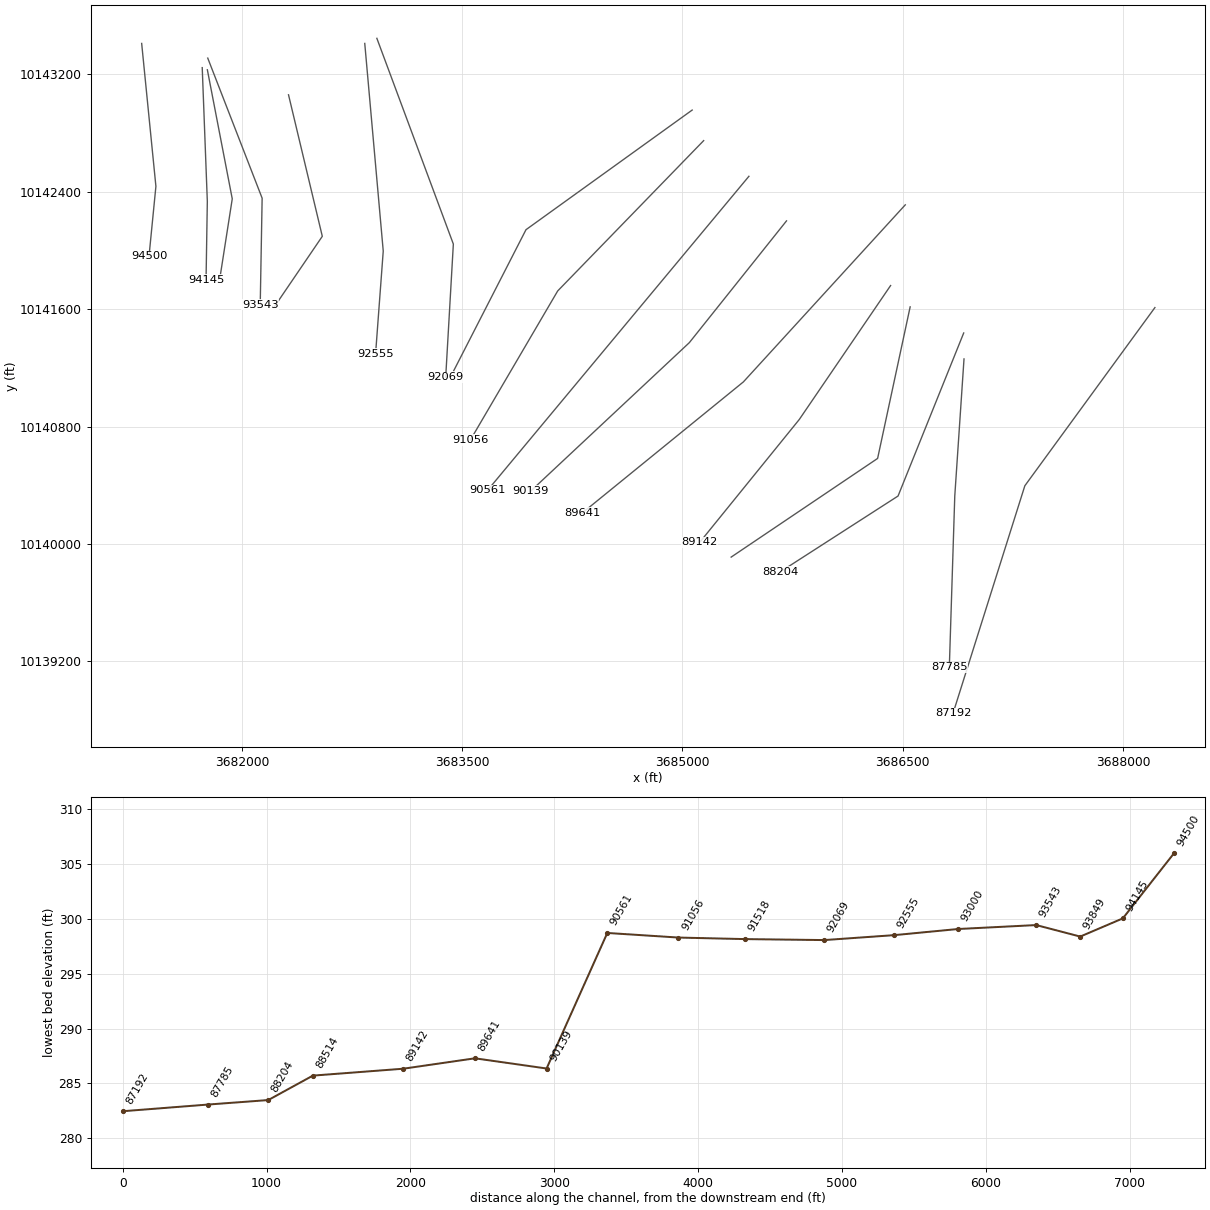
HEC-RAS study CANEY CREEK.prj: CANEY CREEK Base Level Engineering

--- CANEY CREEK.g01 (geometry) --- (continued)

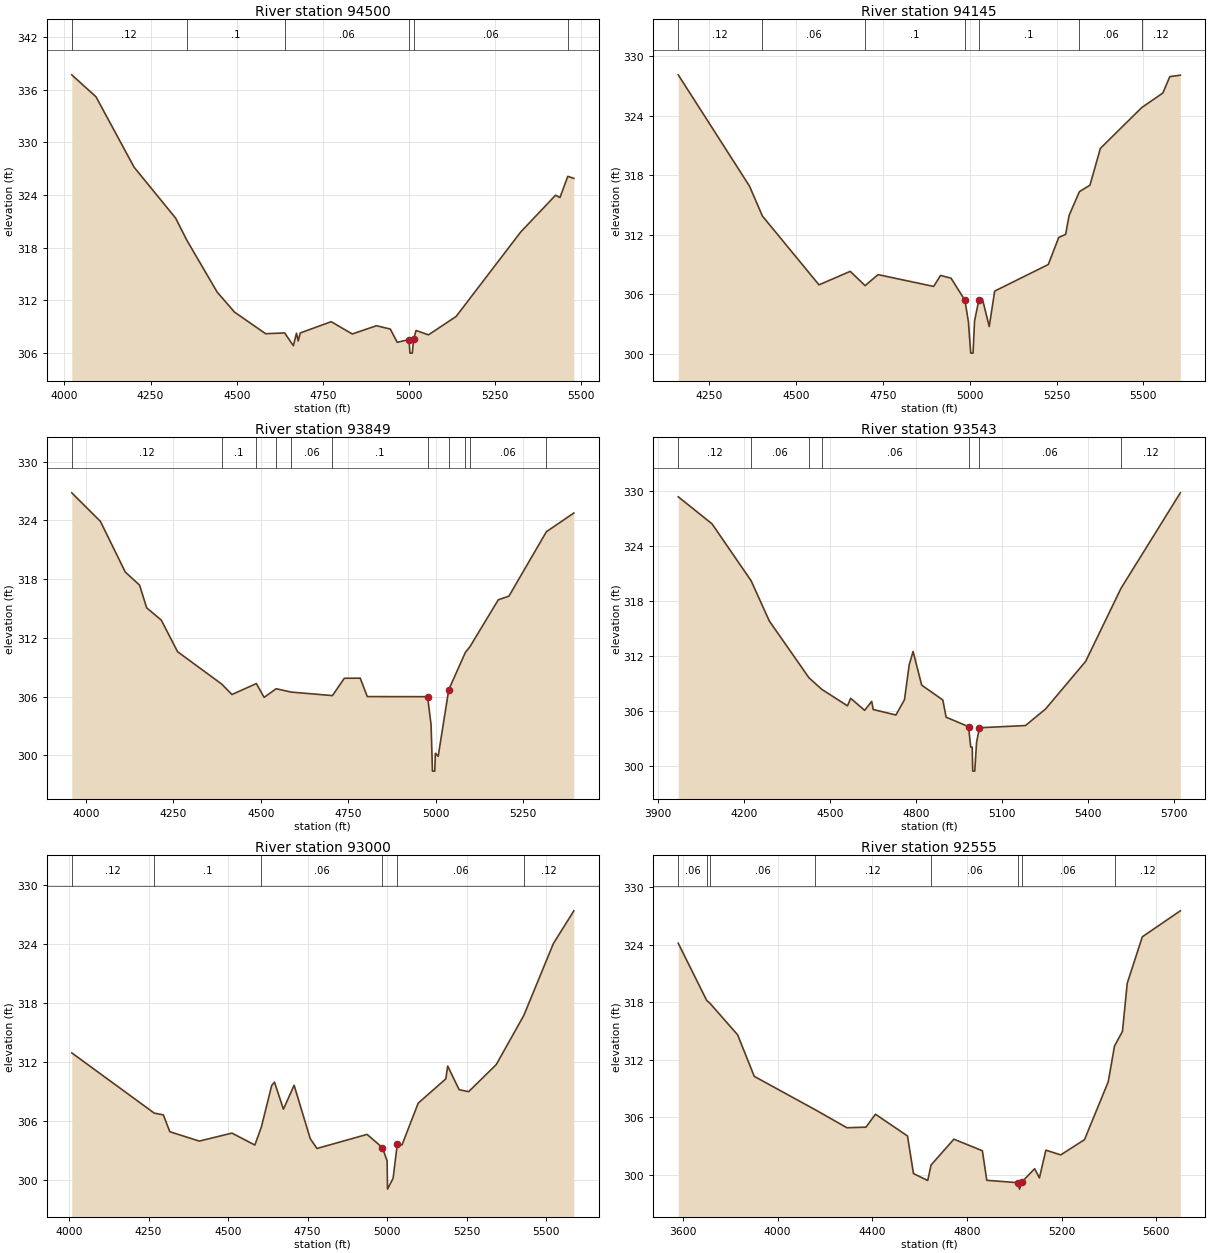
Type RM Length L Ch R = 1 ,94500   ,355,355,355
BEGIN DESCRIPTION:
CANEY CREEK 186.0
END DESCRIPTION:
XS GIS Cut Line= 3
      3681317.85     10143411.04       3681414.8     10142437.16
      3681367.85     10141961.07
#Sta/Elev= 30
  4021.3  337.68  4091.6  335.18  4202.2  327.16  4322.8  321.36  4355.5  318.83
  4443.3  312.94  4493.6  310.66    4584   308.2  4639.2  308.29  4664.4  306.83
  4673.5  308.26  4678.5  307.38  4684.5  308.29  4774.2  309.57  4835.3  308.17
  4905.6  309.11  4945.8  308.73  4965.9  307.22    5000  307.54  5002.8  305.99
  5009.5  305.99 5013.44 307.572  5020.5  308.57  5056.4  308.07  5136.7  310.16
  5324.1  319.78  5425.3  323.97  5438.2  323.71  5460.8  326.12  5478.4  325.89
#Mann= 6 ,-1 , 0
  4021.3     .12       0  4355.5      .1       0  4639.2     .06       0
    5000     .06       0 5013.44     .06       0  5460.8     .12       0
Bank Sta=5000,5013.44
XS Rating Curve= 0 ,0
Exp/Cntr=0.3,0.1

Type RM Length L Ch R = 1 ,94145   ,296,296,296
BEGIN DESCRIPTION:
CANEY CREEK 185.0
END DESCRIPTION:
XS GIS Cut Line= 3
      3681730.26     10143246.16      3681764.98     10142334.71
       3681756.3     10141800.89
#Sta/Elev= 30
  4160.3   328.1  4365.5  316.89  4402.8  313.87  4565.7  306.94  4655.7   308.3
  4698.5  306.86  4735.8  307.97  4895.9  306.78  4915.9  307.89    4946  307.61
    4986  305.39    4996  303.23  5002.7  300.06  5009.4  300.06  5013.7  303.31
    5026  305.37    5036  305.57    5056  302.74  5071.7  306.31  5226.1  308.99
  5256.1  311.71  5276.1  312.03  5286.1  313.94  5315.7  316.33  5346.1  316.98
  5376.1  320.69  5495.2   324.8  5556.1  326.27  5576.1  327.92  5606.3  328.06
#Mann= 7 ,-1 , 0
  4160.3     .12       0  4402.8     .06       0  4698.5      .1       0
    4986     .09       0    5026      .1       0  5315.7     .06       0
  5495.2     .12       0
Bank Sta=4986,5026
XS Rating Curve= 0 ,0
Exp/Cntr=0.3,0.1

Type RM Length L Ch R = 1 ,93849   ,306,306,306
BEGIN DESCRIPTION:
Mapping XS 299aeaa2
END DESCRIPTION:
XS GIS Cut Line= 3
      3681765.14     10143231.52      3681934.72     10142352.02
      3681851.38     10141817.47
#Sta/Elev= 30
  3958.9  326.81  4040.8   323.9  4112.1  318.72  4152.9  317.39  4173.2  315.07
    4215  313.82  4261.7  310.59  4387.8  307.29  4417.4  306.22  4487.2  307.34
  4509.3  305.93  4543.9  306.81  4586.6  306.47  4704.8  306.11  4738.8  307.88
  4784.3  307.89  4804.6  306.01    4977     306  4987.1  303.12    4991   298.4
  4997.7   298.4  4999.4  300.22  5007.4  299.92  5037.7  306.72  5085.1  310.51
  5098.6  311.12  5179.4  315.89  5209.8  316.26  5317.1  322.84  5395.6  324.75
#Mann= 11 ,-1 , 0
  3958.9     .12       0  4387.8      .1       0  4487.2     .06       0
  4543.9      .1       0  4586.6     .06       0  4704.8      .1       0
    4977     .09       0  5037.7      .1       0  5085.1     .12       0
  5098.6     .06       0  5317.1     .12       0
Bank Sta=4977,5037.7
XS Rating Curve= 0 ,0
Exp/Cntr=0.3,0.1

Type RM Length L Ch R = 1 ,93543   ,543,543,543
BEGIN DESCRIPTION:
CANEY CREEK 184.0
END DESCRIPTION:
XS GIS Cut Line= 3
      3681767.85     10143311.07      3682138.25     10142356.41
      3682125.23     10141631.62
#Sta/Elev= 30
  3972.2  329.37  4090.2  326.41  4226.1  320.21  4289.4  315.83  4427.6  309.63
  4471.7  308.38  4561.7  306.57  4572.9  307.39  4621.5  306.08  4646.1  307.06
  4651.4  306.17  4730.4  305.57  4760.3  307.24  4776.7  311.04  4790.3   312.5
  4820.2  308.83  4893.8  307.21  4905.4  305.33  4983.6   304.3    4991  302.07
  4996.2  302.07    4998  299.45  5005.1  299.45  5011.5  302.62  5021.5  304.18
  5181.6  304.42  5251.6  306.22  5391.6  311.43  5514.4  319.38  5721.1   329.8
#Mann= 7 ,-1 , 0
  3972.2     .12       0  4226.1     .06       0  4427.6      .1       0
  4471.7     .06       0  4983.6     .06       0  5021.5     .06       0
  5514.4     .12       0
Bank Sta=4983.6,5021.5
XS Rating Curve= 0 ,0
Exp/Cntr=0.3,0.1

Type RM Length L Ch R = 1 ,93000   ,445,445,445
BEGIN DESCRIPTION:
CANEY CREEK 183.0
END DESCRIPTION:
XS GIS Cut Line= 3
      3682317.85     10143061.07      3682547.93     10142096.63
      3682217.87      10141611.1
#Sta/Elev= 30
  4008.5  312.93  4267.9  306.81  4296.4  306.63  4316.9  304.92  4409.4  303.97
  4512.2  304.78  4584.2  303.57  4604.8  305.42  4637.1  309.62  4645.9  309.96
    4674  307.21  4707.6  309.64  4758.3  304.22  4779.5  303.22    4937  304.65
  4985.2  303.31    5000  301.95  5001.3  299.09  5018.8  300.19  5031.9  303.64
  5046.8  303.58  5097.7  307.82  5184.5  310.29  5190.5  311.59  5226.5  309.19
  5256.3  308.99  5343.1  311.74  5429.9  316.74  5522.7  324.03  5587.1  327.36
#Mann= 6 ,-1 , 0
  4008.5     .12       0  4267.9      .1       0  4604.8     .06       0
  4985.2     .06       0  5031.9     .06       0  5429.9     .12       0
Bank Sta=4985.2,5031.9
XS Rating Curve= 0 ,0
Exp/Cntr=0.3,0.1

Type RM Length L Ch R = 1 ,92555   ,486,486,486
BEGIN DESCRIPTION:
Mapping XS 28ca21cd
END DESCRIPTION:
XS GIS Cut Line= 3
      3682837.04     10143411.06       3682962.9     10141996.17
      3682910.82     10141297.38
#Sta/Elev= 30
  3580.2  324.17  3700.8  318.19  3712.8  317.95  3831.2  314.62  3901.4  310.29
  4158.9  306.81    4293  304.93  4373.3  304.99  4413.5  306.34  4548.8  304.07
  4574.1  300.15  4634.3  299.43  4648.3  301.04  4744.8  303.74  4865.2  302.53
  4883.8  299.45  5015.8   299.2  5022.2  298.53 5032.42299.2884    5086  300.66
  5106.1   299.7  5133.5  302.59  5196.3   302.1  5296.6  303.69  5396.9  309.72
  5423.4  313.45    5457  314.98  5477.1  319.99  5540.9  324.84  5701.4  327.55
#Mann= 8 ,-1 , 0
  3580.2     .06       0  3700.8     .12       0  3712.8     .06       0
  4158.9     .12       0  4648.3     .06       0  5015.8     .06       0
 5032.42     .06       0  5423.4     .12       0
Bank Sta=5015.8,5032.42
XS Rating Curve= 0 ,0
Exp/Cntr=0.3,0.1

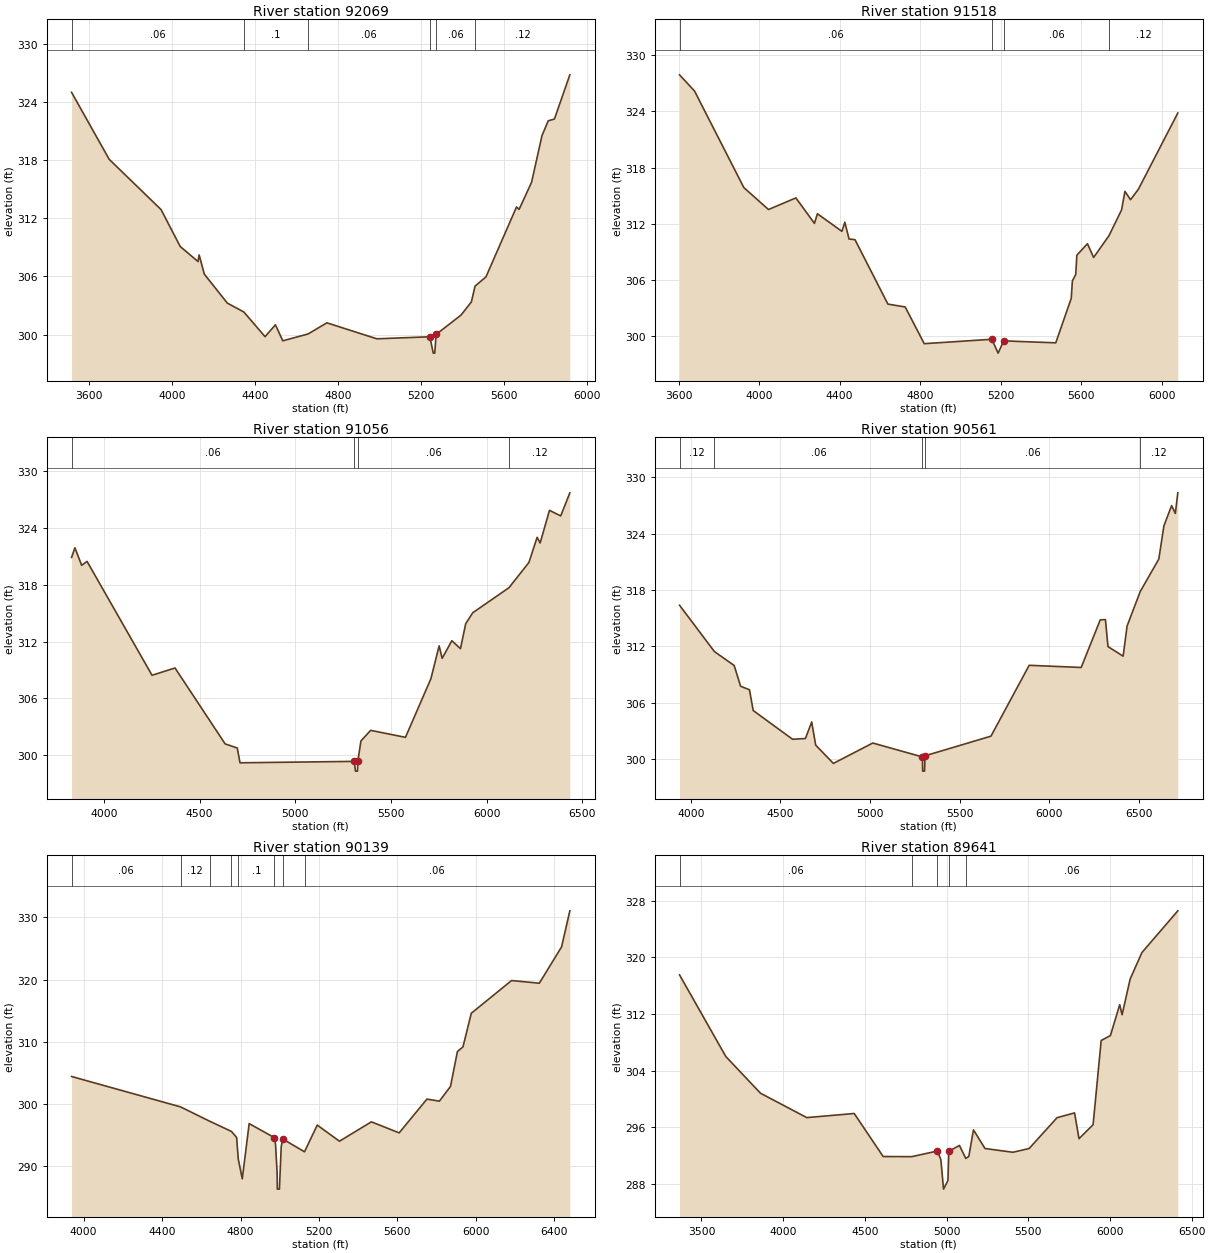
Type RM Length L Ch R = 1 ,92069   ,551,551,551
BEGIN DESCRIPTION:
CANEY CREEK 182.0
END DESCRIPTION:
XS GIS Cut Line= 3
      3682919.51     10143445.79      3683440.33     10142043.91
      3683388.25      10141136.8
#Sta/Elev= 30
  3514.7  325.02  3696.2   318.1  3946.4  312.91  4039.1  309.09  4124.9  307.54
  4130.2  308.22  4155.2  306.24    4266  303.25  4345.8  302.33  4448.2  299.78
  4498.2  301.01  4533.9  299.35  4655.9  300.06  4746.5  301.21  4987.6  299.56
  5243.4  299.77  5259.8  298.08  5267.1  298.08  5273.5  300.01  5393.7  302.01
  5443.8  303.37  5461.5  305.01  5513.9  305.95  5661.6  313.18  5674.1  312.93
  5734.2  315.73  5784.3  320.54  5814.4  322.08  5844.4  322.26  5918.8  326.83
#Mann= 6 ,-1 , 0
  3514.7     .06       0  4345.8      .1       0  4655.9     .06       0
  5243.4     .06       0  5273.5     .06       0  5461.5     .12       0
Bank Sta=5243.4,5273.5
XS Rating Curve= 0 ,0
Exp/Cntr=0.3,0.1

Type RM Length L Ch R = 1 ,91518   ,462,462,462
BEGIN DESCRIPTION:
CANEY CREEK 143.0
END DESCRIPTION:
XS GIS Cut Line= 3
      3685066.72     10142957.04      3683934.99     10142141.77
      3683443.49     10141181.89
#Sta/Elev= 30
  3605.2   327.9  3679.6  326.17  3924.2  315.86  4046.5  313.51  4182.7  314.75
  4274.8  312.03  4289.5  313.06    4411  311.18  4425.7  312.15  4446.6  310.36
    4476  310.29  4639.3  303.41  4725.3   303.1  4819.7  299.18  5155.4  299.65
  5186.5  298.17  5214.2  299.48  5472.6  299.27  5549.4  304.02  5555.1  305.89
  5571.6  306.56  5577.3  308.63  5629.9  309.86  5660.5  308.39  5737.1  310.73
  5799.3  313.47  5815.9  315.45  5843.7  314.56  5882.5  315.67  6078.4  323.82
#Mann= 4 ,-1 , 0
  3605.2     .06       0  5155.4     .06       0  5214.2     .06       0
  5737.1     .12       0
Bank Sta=5155.4,5214.2
XS Rating Curve= 0 ,0
Exp/Cntr=0.3,0.1

Type RM Length L Ch R = 1 ,91056   ,495,495,495
BEGIN DESCRIPTION:
Mapping XS 0251adf6
END DESCRIPTION:
XS GIS Cut Line= 3
      3685144.87     10142748.72      3684150.95     10141724.42
      3683556.36     10140708.84
#Sta/Elev= 30
    3831  320.89  3848.4  321.91  3883.7  320.06    3912  320.47  4251.5  308.44
  4371.7  309.21  4633.5  301.19  4697.1  300.75  4711.2  299.19  5308.3  299.34
  5314.8  298.31  5325.3  298.31 5327.59 299.432  5343.3   301.5  5394.2  302.62
    5576  301.88    5709  308.08    5752  311.55  5767.7  310.23  5818.4  312.09
  5863.5  311.25  5890.8  313.89  5927.9  315.05  6116.7  317.69  6221.2  320.36
  6264.2  323.02  6279.9  322.42  6328.7  325.87  6387.3  325.28  6435.1  327.72
#Mann= 4 ,-1 , 0
    3831     .06       0  5308.3     .06       0 5327.59     .06       0
  6116.7     .12       0
Bank Sta=5308.3,5327.59
XS Rating Curve= 0 ,0
Exp/Cntr=0.3,0.1

Type RM Length L Ch R = 1 ,90561   ,422,422,422
BEGIN DESCRIPTION:
Mapping XS b43c5bc1
END DESCRIPTION:
XS GIS Cut Line= 2
      3685453.05     10142505.68      3683673.61     10140366.02
#Sta/Elev= 30
  3936.4  316.38  4131.2  311.45  4241.5  309.97  4277.4  307.76  4326.9  307.39
  4347.7  305.18  4567.7  302.12  4639.4   302.2  4674.5  303.96  4696.6   301.5
  4795.6  299.55  5015.6  301.72  5292.9  300.24  5294.2  298.73  5304.7  298.73
  5307.3  300.36  5675.7  302.45  5889.2  309.99  6179.6  309.76  6286.3  314.83
    6315  314.85  6329.3  311.98  6413.9  310.96    6436  314.17  6509.5  317.84
  6613.1  321.29  6641.7  324.83  6684.7  326.98  6705.5  326.15  6719.3  328.34
#Mann= 5 ,-1 , 0
  3936.4     .12       0  4131.2     .06       0  5292.9     .06       0
  5307.3     .06       0  6509.5     .12       0
Bank Sta=5292.9,5307.3
XS Rating Curve= 0 ,0
Exp/Cntr=0.3,0.1

Type RM Length L Ch R = 1 ,90139   ,498,498,498
BEGIN DESCRIPTION:
CANEY CREEK 142.0
END DESCRIPTION:
XS GIS Cut Line= 3
      3685709.09     10142201.83      3685047.38     10141372.07
      3683967.87     10140361.09
#Sta/Elev= 30
  3938.7  304.44  4494.4  299.56  4642.7  297.26  4753.9  295.62  4780.1  294.66
  4788.5  291.21  4808.9  288.01  4844.1  296.88  4972.2  294.63  4978.6  293.56
  4986.7   288.9  4987.8  286.36  4998.3  286.36  5007.5  293.14  5014.3  294.43
  5126.2  292.35  5191.2  296.64  5304.5  294.05  5467.2  297.16  5608.8  295.39
  5750.5  300.81    5814  300.48  5870.6  302.85  5905.8  308.44  5934.1  309.19
  5976.6  314.59  6181.8  319.84  6323.4  319.41  6436.8  325.24    6479  331.03
#Mann= 8 ,-1 , 0
  3938.7     .06       0  4494.4     .12       0  4642.7     .06       0
  4753.9     .12       0  4788.5      .1       0  4972.2     .09       0
  5014.3      .1       0  5126.2     .06       0
Bank Sta=4972.2,5014.3
XS Rating Curve= 0 ,0
Exp/Cntr=0.3,0.1

Type RM Length L Ch R = 1 ,89641   ,499,499,499
BEGIN DESCRIPTION:
CANEY CREEK 141.0
END DESCRIPTION:
XS GIS Cut Line= 3
      3686517.84     10142311.06       3685415.6     10141104.68
      3684317.84     10140211.06
#Sta/Elev= 30
  3365.9  317.51  3649.3  305.99  3861.4  300.82  4144.5  297.38    4435  297.96
    4612  291.89  4787.5  291.87  4944.4  292.67  4965.3  291.44  4981.7  287.29
  5008.6  288.52 5014.03292.6347    5079  293.45  5117.9  291.62  5136.4   291.9
  5164.7  295.65  5235.5  293.02  5406.5  292.49  5505.6  293.02  5676.5  297.37
  5783.5  298.04  5810.8  294.41    5897  296.38  5946.5  308.26  6002.9  308.95
    6060  313.31  6074.4  311.89  6123.9  316.93  6195.7  320.66  6415.5  326.55
#Mann= 5 ,-1 , 0
  3365.9     .06       0  4787.5      .1       0  4944.4     .09       0
 5014.03      .1       0  5117.9     .06       0
Bank Sta=4944.4,5014.03
XS Rating Curve= 0 ,0
Exp/Cntr=0.3,0.1

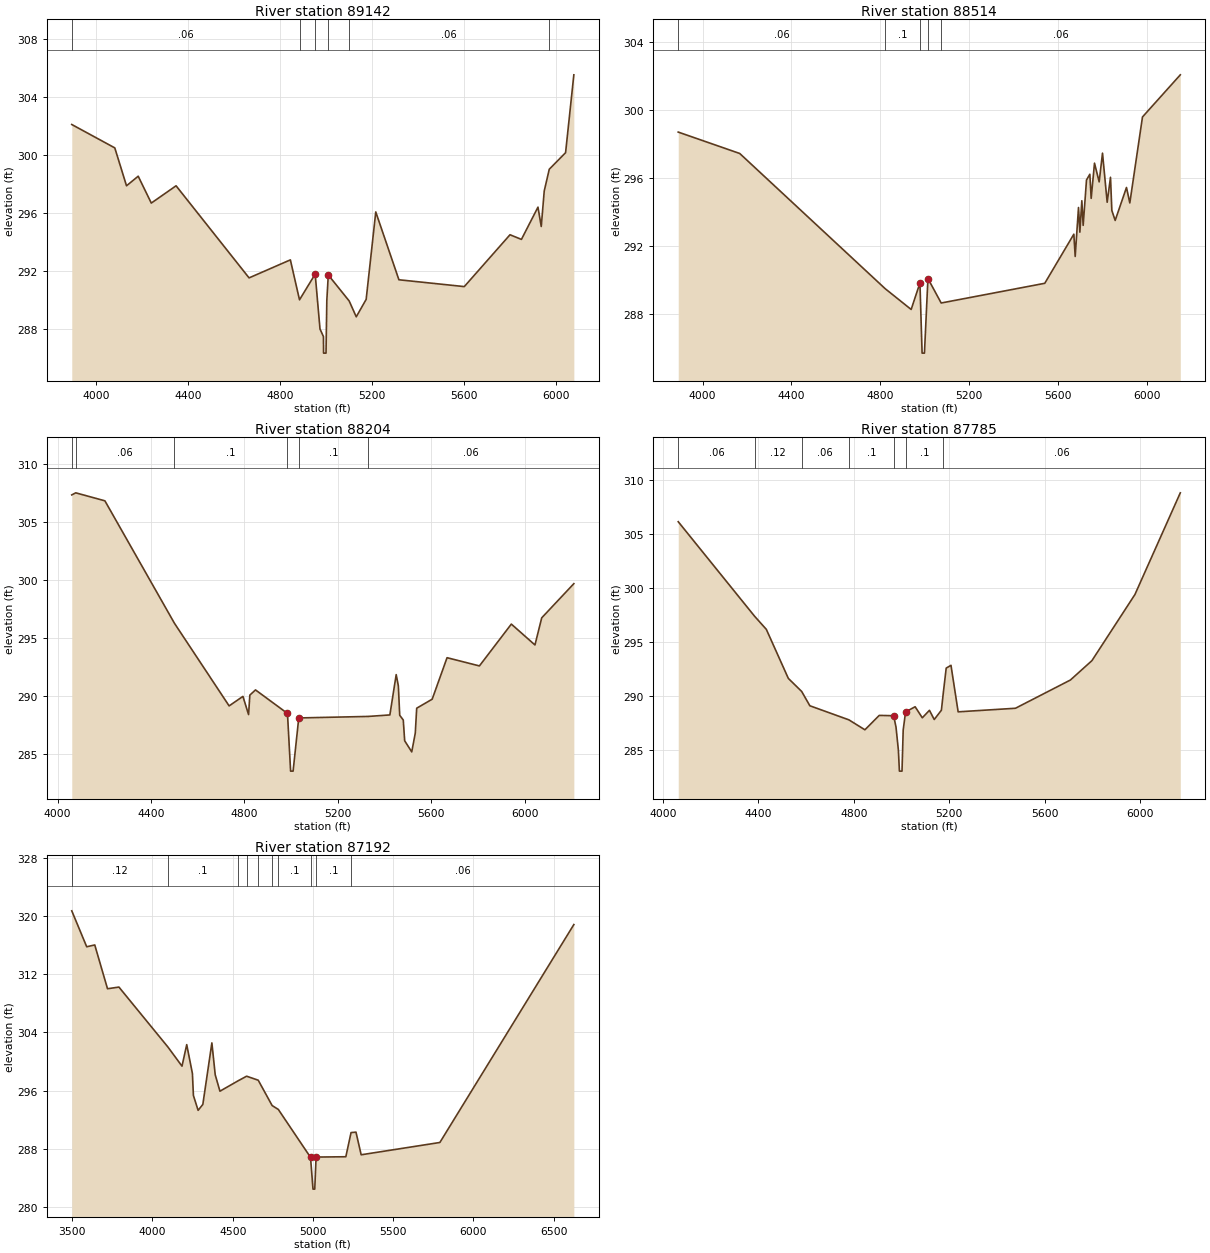
Type RM Length L Ch R = 1 ,89142   ,628,628,628
BEGIN DESCRIPTION:
CANEY CREEK 140.0
END DESCRIPTION:
XS GIS Cut Line= 3
      3686417.86     10141761.08       3685796.2     10140848.62
      3685117.85     10140011.07
#Sta/Elev= 30
  3895.9  302.08  4082.9  300.47  4133.8  297.86  4184.6  298.52  4241.5  296.67
  4349.2  297.86  4666.4  291.52  4845.9  292.76  4885.6  290.01  4953.7  291.78
  4974.7     288  4989.6  287.48  4990.2  286.34  5000.8  286.34  5004.3  289.97
  5010.7  291.72  5101.5  289.93  5132.2  288.84  5175.3  290.04    5217  296.06
  5317.6  291.39  5601.7  290.92  5800.4  294.49    5850  294.17  5921.9  296.39
  5936.2  295.06  5949.1   297.5    5971     299  6041.9  300.14  6077.8   305.5
#Mann= 6 ,-1 , 0
  3895.9     .06       0  4885.6      .1       0  4953.7     .09       0
  5010.7      .1       0  5101.5     .06       0    5971      .1       0
Bank Sta=4953.7,5010.7
XS Rating Curve= 0 ,0
Exp/Cntr=0.3,0.1

Type RM Length L Ch R = 1 ,88514   ,310,310,310
BEGIN DESCRIPTION:
CANEY CREEK 139.0
END DESCRIPTION:
XS GIS Cut Line= 3
      3686551.12     10141615.87      3686329.46     10140582.98
      3685332.15     10139910.62
#Sta/Elev= 30
  3890.4  298.72  4167.2  297.46    4821  289.51  4938.5  288.28    4978  289.84
  4987.7  285.71  4998.3  285.71    5014   290.1  5073.6  288.66  5539.7  289.82
  5670.5  292.71  5676.6   291.4  5691.5  294.28  5697.6  292.83  5706.5  294.68
  5712.5  293.23  5727.5   295.9  5742.5  296.24  5748.5  294.82  5763.5  296.89
  5784.5  295.79  5799.5  297.48  5820.5  294.59  5835.5  296.06  5841.5  294.11
  5856.5  293.52  5907.4  295.46  5922.4  294.55  5979.4  299.61  6149.6  302.09
#Mann= 5 ,-1 , 0
  3890.4     .06       0    4821      .1       0    4978     .09       0
    5014      .1       0  5073.6     .06       0
Bank Sta=4978,5014
XS Rating Curve= 0 ,0
Exp/Cntr=0.3,0.1

Type RM Length L Ch R = 1 ,88204   ,419,419,419
BEGIN DESCRIPTION:
CANEY CREEK 138.0
END DESCRIPTION:
XS GIS Cut Line= 3
      3686915.71     10141437.97      3686468.66     10140326.85
      3685667.86     10139811.08
#Sta/Elev= 30
  4060.7  307.32  4077.7   307.5  4202.6  306.81  4500.5  296.24  4734.6  289.11
  4793.7  289.93  4817.9  288.36  4823.3  290.04  4847.5  290.49  4984.5  288.46
  4997.9  283.48  5008.6  283.48  5032.8  288.07  5329.8   288.2    5423  288.33
  5450.1  291.81  5459.3  290.84  5465.2   288.3  5480.4  287.89  5486.4   286.1
  5516.7  285.14  5531.9  286.77  5537.9  288.91  5604.3  289.69  5667.9  293.27
  5806.5  292.56  5943.2  296.17  6044.4  294.37  6073.3  296.71  6210.9  299.66
#Mann= 6 ,-1 , 0
  4060.7      .1       0  4077.7     .06       0  4500.5      .1       0
  4984.5     .09       0  5032.8      .1       0  5329.8     .06       0
Bank Sta=4984.5,5032.8
XS Rating Curve= 0 ,0
Exp/Cntr=0.3,0.1

Type RM Length L Ch R = 1 ,87785   ,593,593,593
BEGIN DESCRIPTION:
CANEY CREEK 137.0
END DESCRIPTION:
XS GIS Cut Line= 3
      3686917.85     10141261.12      3686854.95     10140326.85
      3686817.85     10139161.02
#Sta/Elev= 30
  4064.9  306.12  4384.5  297.39  4433.9  296.17    4526  291.64    4582  290.43
  4616.2  289.11  4779.6  287.81  4846.7  286.89  4906.8  288.22    4967  288.19
    4977  287.14    4987  284.99  4991.2  283.07  5002.1  283.07  5007.1  286.88
  5017.1  288.54  5057.1  289.02  5087.1     288  5117.1  288.69  5137.1  287.84
  5167.1   288.7  5174.2  290.13  5187.2  292.59  5207.2  292.85  5237.2  288.55
  5477.3  288.88  5707.4  291.49  5797.5  293.28  5977.6  299.39  6167.7  308.79
#Mann= 7 ,-1 , 0
  4064.9     .06       0  4384.5     .12       0    4582     .06       0
  4779.6      .1       0    4967     .09       0  5017.1      .1       0
  5174.2     .06       0
Bank Sta=4967,5017.1
XS Rating Curve= 0 ,0
Exp/Cntr=0.3,0.1

Type RM Length L Ch R = 1 ,87192   ,499,499,499
BEGIN DESCRIPTION:
CANEY CREEK 136.0
END DESCRIPTION:
XS GIS Cut Line= 3
      3688217.86     10141611.08      3687332.08      10140396.7
      3686842.94      10138845.7
#Sta/Elev= 30
  3496.9  320.71    3590  315.77  3640.2  316.02  3719.7     310  3790.8  310.23
    4097  301.97    4184  299.36  4213.4  302.32  4248.9  298.35  4255.1  295.33
  4284.4  293.29  4313.8   294.1  4370.2  302.56    4391  298.18  4420.4  295.92
  4533.9  297.35  4586.7  297.98  4659.1  297.43  4745.7  293.95  4784.4  293.41
  4985.1  286.83  5000.5  282.46  5011.4  282.46 5019.72286.8658  5205.1  286.91
  5237.7  290.23  5268.4  290.29  5300.7  287.18  5791.2  288.87  6626.3  318.82
#Mann= 10 ,-1 , 0
  3496.9     .12       0    4097      .1       0  4533.9     .06       0
  4586.7     .12       0  4659.1     .06       0  4745.7     .12       0
  4784.4      .1       0  4985.1     .09       0 5019.72      .1       0
  5237.7     .06       0
Bank Sta=4985.1,5019.72
XS Rating Curve= 0 ,0
Exp/Cntr=0.3,0.1