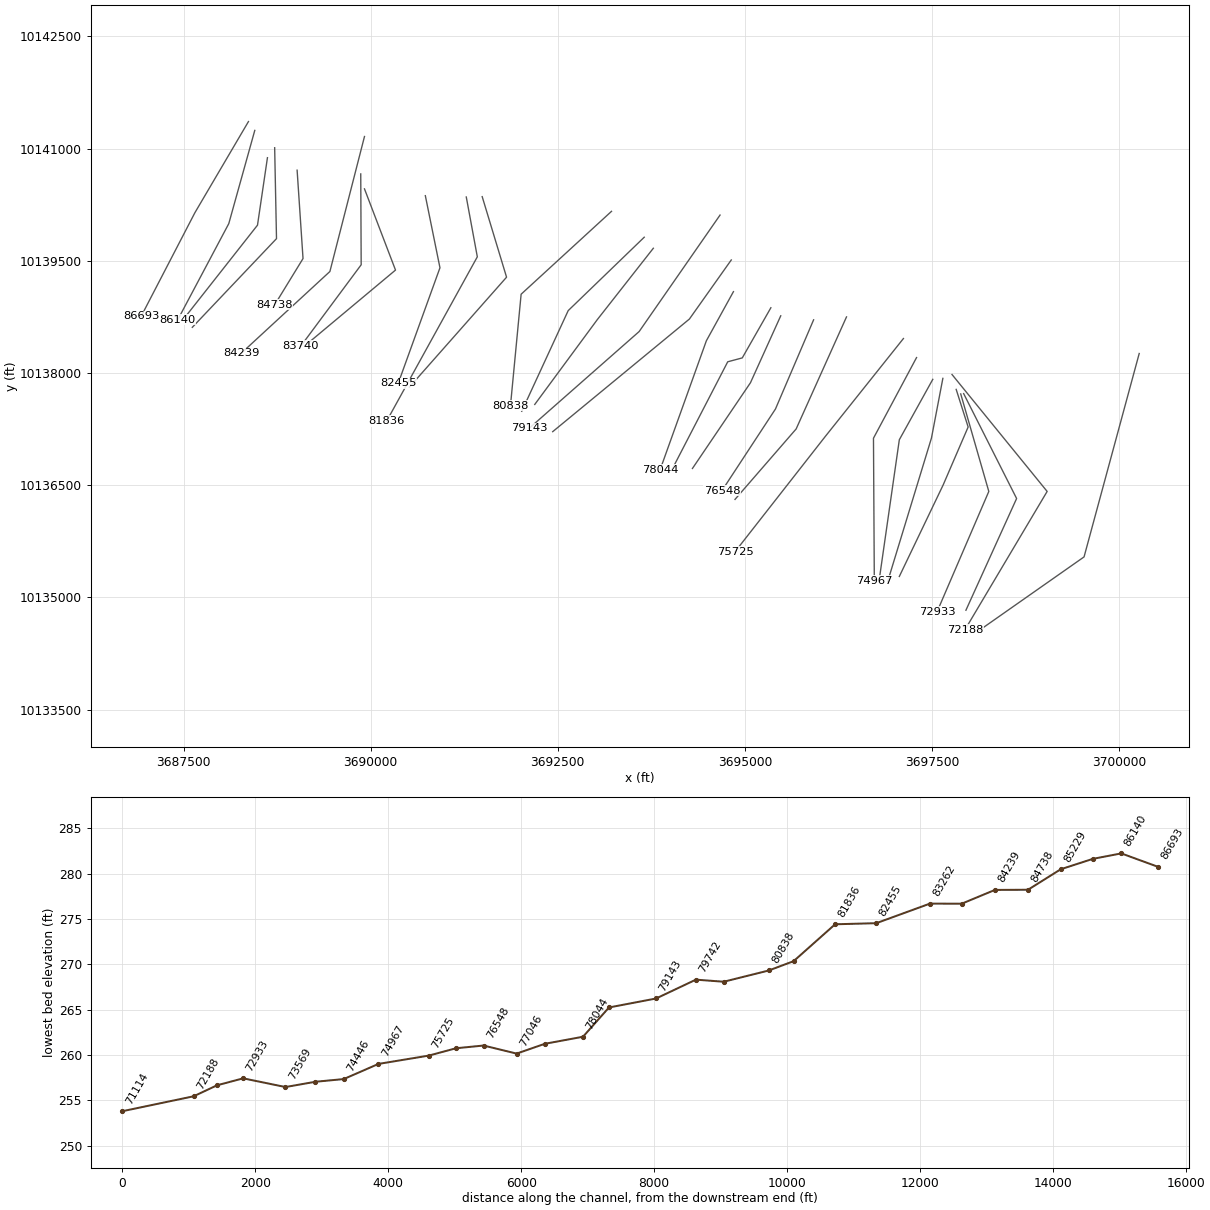
HEC-RAS study CANEY CREEK.prj: CANEY CREEK Base Level Engineering

--- CANEY CREEK.g01 (geometry) --- (continued)

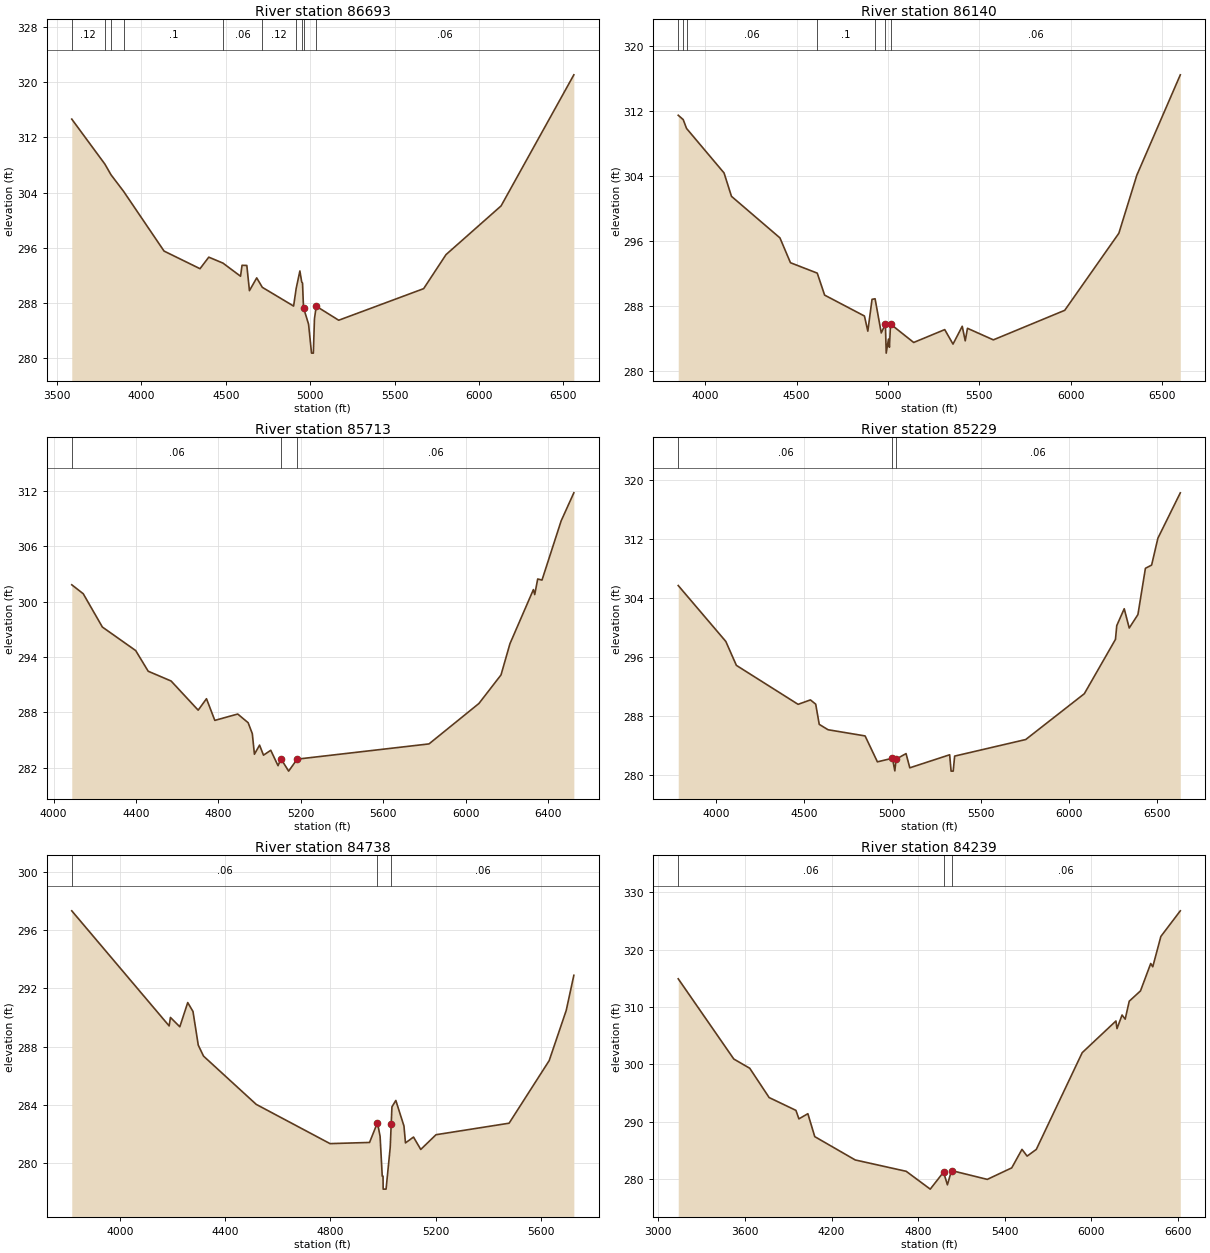
Type RM Length L Ch R = 1 ,86693   ,553,553,553
BEGIN DESCRIPTION:
CANEY CREEK 135.0
END DESCRIPTION:
XS GIS Cut Line= 3
      3688367.86     10141361.08      3687652.21     10140142.83
      3686933.16     10138755.84
#Sta/Elev= 30
  3587.1  314.63    3783  308.13  3820.3  306.55  3894.3  304.17    4134  295.53
    4347  292.98    4399  294.65    4483  293.79  4587.2  291.89  4596.1  293.47
  4624.4  293.45    4640   289.8    4683  291.65  4716.4  290.28  4901.7  287.57
  4916.8  290.11  4938.9  292.65  4949.7  291.06  4954.5   290.9  4960.3  287.35
  4990.4  284.94  5007.8  280.76  5018.7  280.76  5025.2  285.72  5035.8  287.55
  5168.9  285.52  5672.2  290.09  5804.9  295.02  6131.2  302.07  6562.3  321.04
#Mann= 10 ,-1 , 0
  3587.1     .12       0    3783     .06       0  3820.3     .12       0
  3894.3      .1       0    4483     .06       0  4716.4     .12       0
  4916.8      .1       0  4949.7     .06       0  4960.3     .06       0
  5035.8     .06       0
Bank Sta=4960.3,5035.8
XS Rating Curve= 0 ,0
Exp/Cntr=0.3,0.1

Type RM Length L Ch R = 1 ,86140   ,427,427,427
BEGIN DESCRIPTION:
CANEY CREEK 134.0
END DESCRIPTION:
XS GIS Cut Line= 3
      3688452.17     10141242.64      3688104.95     10139996.99
      3687423.52     10138712.26
#Sta/Elev= 30
  3852.2  311.47  3879.3  310.94  3897.7  309.85    4103  304.38  4143.5  301.51
  4408.8   296.4  4466.3  293.35    4613  292.07  4653.2  289.37  4871.2   286.8
  4889.6  284.94  4912.7  288.85  4929.4  288.92  4963.2  284.72 4985.82285.8155
  4990.3  282.24  5002.6  283.97  5007.8  282.96    5014285.8106  5140.6  283.55
  5310.5  285.13  5355.8  283.35  5406.3  285.54  5422.7  283.75    5435  285.29
  5576.6  283.87  5967.1   287.5  6263.3  296.97  6361.9  304.12  6599.6  316.44
#Mann= 7 ,-1 , 0
  3852.2     .06       0  3879.3     .12       0  3897.7     .06       0
    4613      .1       0  4929.4     .06       0 4985.82     .07       0
    5014     .06       0
Bank Sta=4985.82,5014
XS Rating Curve= 0 ,0
Exp/Cntr=0.3,0.1

Type RM Length L Ch R = 1 ,85713   ,484,484,484
BEGIN DESCRIPTION:
CANEY CREEK 133.0
END DESCRIPTION:
XS GIS Cut Line= 3
      3688621.44     10140878.07      3688488.52     10139976.21
      3687545.03     10138777.34
#Sta/Elev= 30
  4088.4  301.84  4144.1  300.87    4237  297.26  4398.7  294.71  4459.4  292.47
  4570.6  291.41    4702  288.25  4742.4  289.49  4782.8  287.14    4894  287.83
  4944.5  286.89  4964.8   285.7  4975.1  283.47    5000  284.46  5019.1  283.37
  5054.4   283.9  5089.6  282.23  5104.1  282.97  5141.1  281.64  5182.7  282.94
  5822.5  284.59  6064.7  288.97  6172.1  292.07  6215.4  295.45  6329.3  301.32
  6335.7  300.78  6350.2  302.47    6371  302.35    6464  308.77  6525.6  311.81
#Mann= 3 , 0 , 0
  4088.4     .06       0  5104.1     .06       0  5182.7     .06       0
Bank Sta=5104.1,5182.7
XS Rating Curve= 0 ,0
Exp/Cntr=0.3,0.1

Type RM Length L Ch R = 1 ,85229   ,491,491,491
BEGIN DESCRIPTION:
CANEY CREEK 132.0
END DESCRIPTION:
XS GIS Cut Line= 3
      3688717.85     10141011.04      3688742.42     10139796.09
      3687617.84     10138611.06
#Sta/Elev= 30
  3784.8  305.69  4054.8   298.1  4114.8  294.85  4464.9  289.56  4534.9  290.16
  4564.9  289.58  4584.9  286.84  4634.9  286.11    4845  285.27    4915  281.75
    5000  282.24  5013.9  280.52  5020.8  282.11  5077.4  282.87  5098.8  280.94
  5324.9  282.71  5333.1  280.49  5345.1  280.49  5353.2  282.53  5756.5  284.78
    6089     291  6265.8  298.38  6273.1  300.25  6315.5  302.54  6343.8  299.92
  6393.2  301.75  6435.7  308.03  6470.9  308.47  6506.5  312.12  6633.7  318.28
#Mann= 3 , 0 , 0
  3784.8     .06       0    5000     .06       0  5020.8     .06       0
Bank Sta=5000,5020.8
XS Rating Curve= 0 ,0
Exp/Cntr=0.3,0.1

Type RM Length L Ch R = 1 ,84738   ,499,499,499
BEGIN DESCRIPTION:
CANEY CREEK 131.0
END DESCRIPTION:
XS GIS Cut Line= 3
      3689017.85     10140711.06      3689096.81     10139529.99
      3688717.86     10138911.09
#Sta/Elev= 30
  3816.3  297.31  4186.6  289.42  4191.6     290  4227.2  289.36  4257.3  291.02
  4277.3  290.41  4297.4   288.1  4317.4  287.35  4517.8  284.04  4798.5  281.35
  4948.8  281.43  4978.9  282.79  4988.9  281.84    4997  279.12    5000  279.12
  5000.6  278.23  5011.6  278.23  5027.4   281.1  5031.2282.7195  5033.9  283.87
  5048.7  284.31  5079.6  282.56  5085.4   281.4    5116   281.8  5143.5  280.95
  5201.5  281.96  5479.5  282.75  5631.9  287.04  5696.7  290.48  5725.7  292.89
#Mann= 3 , 0 , 0
  3816.3     .06       0  4978.9     .06       0  5031.2     .06       0
Bank Sta=4978.9,5031.2
XS Rating Curve= 0 ,0
Exp/Cntr=0.3,0.1

Type RM Length L Ch R = 1 ,84239   ,499,499,499
BEGIN DESCRIPTION:
CANEY CREEK 130.0
END DESCRIPTION:
XS GIS Cut Line= 3
      3689917.85     10141161.07      3689455.82     10139356.99
      3688267.83     10138261.05
#Sta/Elev= 30
  3137.7  314.91  3522.7  300.91  3633.2   299.3  3767.5  294.19  3953.2  291.95
  3973.8  290.47  4035.8  291.37  4083.6  287.37    4364   283.3  4717.1  281.32
  4883.7  278.21    4976  281.18  5002.7  278.96  5031.1  281.45  5278.9  279.91
  5448.4  281.92  5519.3  285.15    5555  283.97  5618.5  285.14  5936.6  302.02
  6170.3  307.55  6177.7  306.22  6212.8  308.59  6234.4  307.87  6262.5     311
  6340.4   312.8  6411.3  317.58  6425.5  317.01  6481.6   322.3  6616.3  326.77
#Mann= 3 , 0 , 0
  3137.7     .06       0    4976     .06       0  5031.1     .06       0
Bank Sta=4976,5031.1
XS Rating Curve= 0 ,0
Exp/Cntr=0.3,0.1

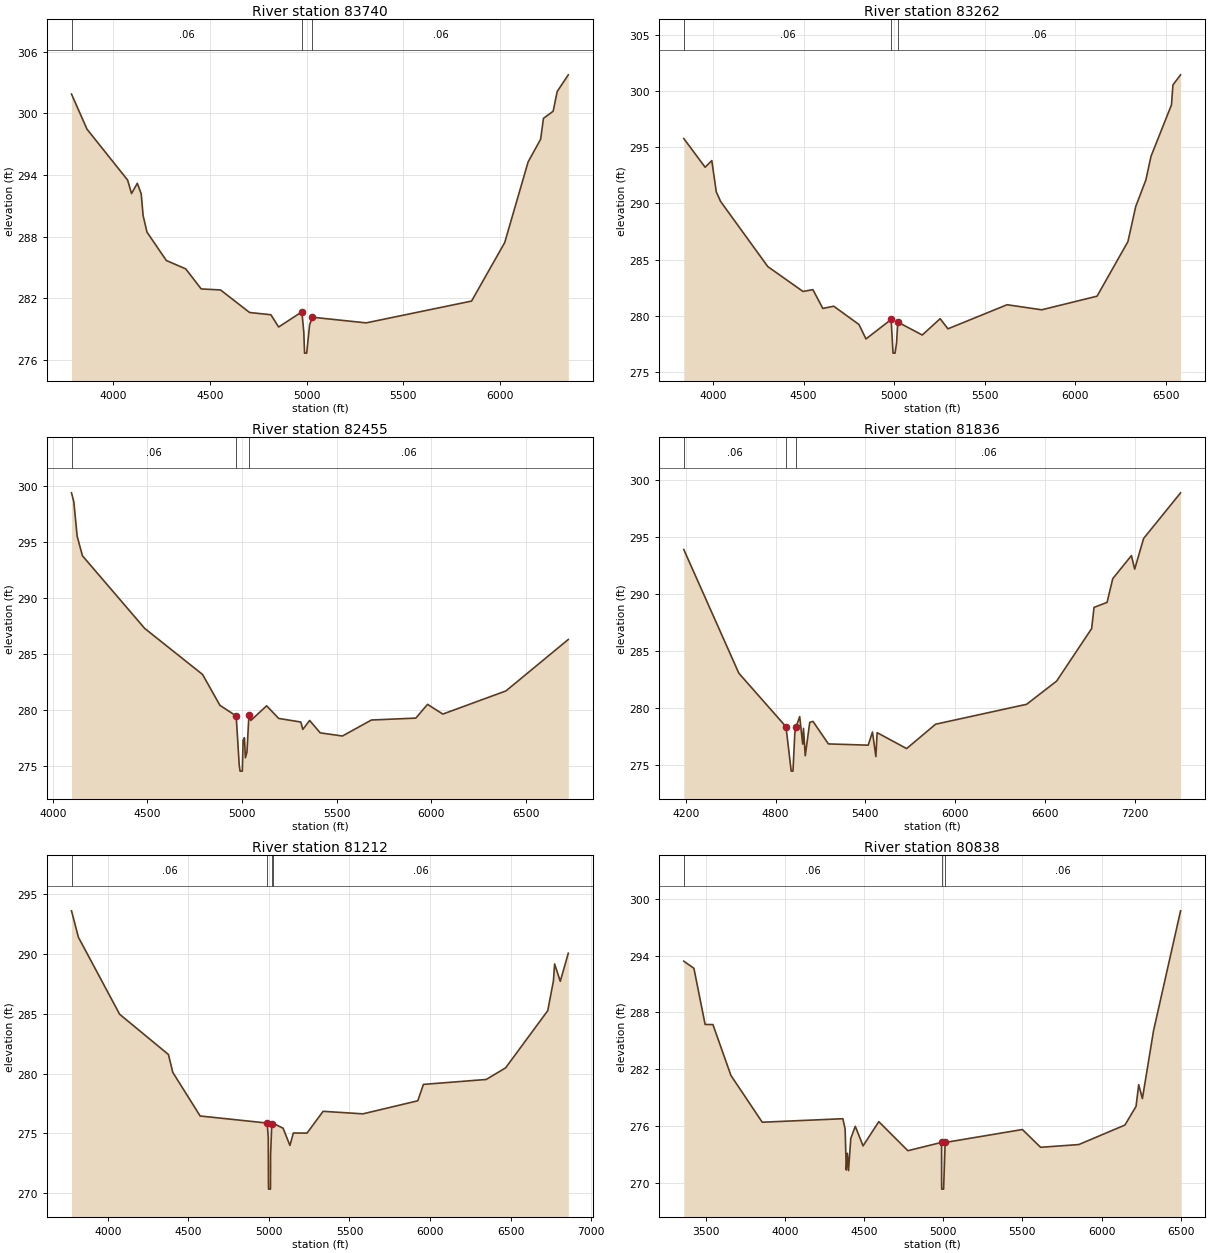
Type RM Length L Ch R = 1 ,83740   ,478,478,478
BEGIN DESCRIPTION:
CANEY CREEK 129.0
END DESCRIPTION:
XS GIS Cut Line= 3
      3689867.85     10140661.02      3689873.66     10139446.94
      3689067.85     10138361.07
#Sta/Elev= 30
  3785.9  301.87  3865.9  298.46  4075.9  293.51  4095.9   292.2  4125.9   293.2
  4145.9  292.18  4155.9  290.05  4175.9  288.45  4275.9  285.69  4375.9  284.88
  4455.9  282.93  4555.9  282.83  4705.9  280.64  4815.9  280.42  4855.9  279.23
  4975.9   280.7  4985.9  278.75  4989.9  276.69  5000.9  276.69  5015.8  279.44
  5030.5  280.18  5307.9  279.63  5852.5  281.75  6023.6  287.43  6144.6  295.27
  6209.3  297.48  6223.9  299.51    6274   300.2  6294.8  302.12  6352.2  303.74
#Mann= 3 , 0 , 0
  3785.9     .06       0  4975.9     .06       0  5030.5     .06       0
Bank Sta=4975.9,5030.5
XS Rating Curve= 0 ,0
Exp/Cntr=0.3,0.1

Type RM Length L Ch R = 1 ,83262   ,807,807,807
BEGIN DESCRIPTION:
CANEY CREEK 128.0
END DESCRIPTION:
XS GIS Cut Line= 3
      3689917.84     10140461.11      3690332.24     10139375.94
      3689117.87     10138361.09
#Sta/Elev= 30
  3838.4  295.77  3956.2  293.22  3993.1  293.81  4017.9  291.03  4041.8  290.18
  4302.5  284.39    4497  282.18  4551.7  282.34  4606.5  280.67  4666.7  280.87
  4806.3  279.24  4844.7  277.96  4983.8  279.69  4994.3   276.7  5005.5   276.7
  5013.8  277.62  5020.3  279.46  5155.7  278.31  5254.6  279.76  5297.5  278.86
  5624.2     281  5815.5  280.55  6121.3  281.76  6291.8  286.61  6334.7  289.72
  6390.7  292.08  6419.3  294.19  6532.5  298.77  6540.3  300.53  6582.6  301.43
#Mann= 3 , 0 , 0
  3838.4     .06       0  4983.8     .06       0  5020.3     .06       0
Bank Sta=4983.8,5020.3
XS Rating Curve= 0 ,0
Exp/Cntr=0.3,0.1

Type RM Length L Ch R = 1 ,82455   ,619,619,619
BEGIN DESCRIPTION:
CANEY CREEK 127.0
END DESCRIPTION:
XS GIS Cut Line= 3
      3690730.81     10140370.26      3690926.13     10139406.71
      3690367.86     10137861.09
#Sta/Elev= 30
  4098.7  299.42  4111.1   298.6  4128.5  295.55  4156.6  293.79  4485.6   287.3
  4791.7  283.18  4883.5  280.42  4969.4279.4765  4985.6  275.04  4989.9  274.54
  5001.7  274.54    5006   277.3    5013  277.53  5018.1  275.73  5026.4  276.24
  5036.6  279.53  5046.8  279.07  5130.4  280.38  5194.2  279.25  5311.1  278.93
  5321.7  278.27  5357.7  279.07  5413.7  277.96  5531.1  277.68  5684.4  279.11
  5919.1  279.28    5981  280.51  6061.8  279.64  6395.6  281.71  6725.2  286.31
#Mann= 3 , 0 , 0
  4098.7     .06       0  4969.4     .06       0  5036.6     .06       0
Bank Sta=4969.4,5036.6
XS Rating Curve= 0 ,0
Exp/Cntr=0.3,0.1

Type RM Length L Ch R = 1 ,81836   ,624,624,624
BEGIN DESCRIPTION:
CANEY CREEK 126.0
END DESCRIPTION:
XS GIS Cut Line= 3
       3691277.7     10140352.85       3691425.3     10139553.05
      3690214.34     10137358.14
#Sta/Elev= 30
  4186.7  293.88  4554.6  283.02  4869.8  278.32  4904.6  274.42  4916.4  274.42
  4928.6  277.74 4937.47 278.321  4961.3  279.21  4981.5  276.79  4986.6  278.18
  4998.5  275.77  5028.3   278.7  5050.1  278.79  5153.2  276.81  5419.1   276.7
  5447.7  277.85  5470.5   275.7  5478.7   277.8  5676.1   276.4  5869.5  278.54
  6478.1  280.29  6678.6  282.33  6912.4  286.94  6928.5   288.8  7015.6  289.24
  7053.4  291.32  7178.3  293.35  7200.1  292.16  7259.7  294.85  7506.8  298.86
#Mann= 3 , 0 , 0
  4186.7     .06       0  4869.8     .06       0 4937.47     .06       0
Bank Sta=4869.8,4937.47
XS Rating Curve= 0 ,0
Exp/Cntr=0.3,0.1

Type RM Length L Ch R = 1 ,81212   ,374,374,374
BEGIN DESCRIPTION:
CANEY CREEK 125.0
END DESCRIPTION:
XS GIS Cut Line= 3
      3691490.37     10140357.21      3691815.88     10139280.85
      3690517.86     10137811.08
#Sta/Elev= 30
  3773.5   293.6  3816.5  291.39  4072.4  284.96  4375.4   281.6  4402.7   280.1
  4572.6  276.46  4988.8  275.87  4995.5  274.65  4996.7  270.85  4997.2  270.35
    5009  270.35  5009.5  270.85  5009.7  273.11  5017.3  275.81  5023.9  275.86
  5087.5  275.44  5130.2     274  5151.2  275.04  5236.4  275.03    5336  276.85
  5583.6  276.64  5924.1  277.73  5959.2   279.1    6349  279.51  6469.5  280.48
  6731.3  285.26  6766.5  287.74    6774  289.16  6809.1  287.71  6858.9  290.06
#Mann= 4 ,-1 , 0
  3773.5     .06       0  4988.8     .06       0  5017.3     .04       0
  5023.9     .06       0
Bank Sta=4988.8,5017.3
XS Rating Curve= 0 ,0
Exp/Cntr=0.3,0.1

Type RM Length L Ch R = 1 ,80838   ,678,678,678
BEGIN DESCRIPTION:
CANEY CREEK 124.0
END DESCRIPTION:
XS GIS Cut Line= 3
      3693217.89      10140161.1       3692010.5     10139053.44
      3691867.85     10137561.04
#Sta/Elev= 30
  3361.5  293.41  3425.4  292.66  3496.3  286.72  3545.6  286.71  3659.1  281.34
    3857  276.39  4366.3  276.76  4380.5  275.67  4387.9  271.34  4394.7  273.11
  4402.1  271.28  4416.2  274.67  4444.6  275.96  4493.9  273.89  4593.2  276.45
    4777  273.38  4989.7  274.26  4990.1  269.82  4990.6  269.32  5002.4  269.32
  5012.4  274.25  5500.2  275.62  5615.2  273.74  5856.3  274.03  6147.6  276.09
  6217.9  278.06  6234.7  280.36  6258.1  278.89  6328.4  286.06  6499.2  298.73
#Mann= 3 ,-1 , 0
  3361.5     .06       0  4989.7     .06       0  5012.4     .06       0
Bank Sta=4989.7,5012.4
XS Rating Curve= 0 ,0
Exp/Cntr=0.3,0.1

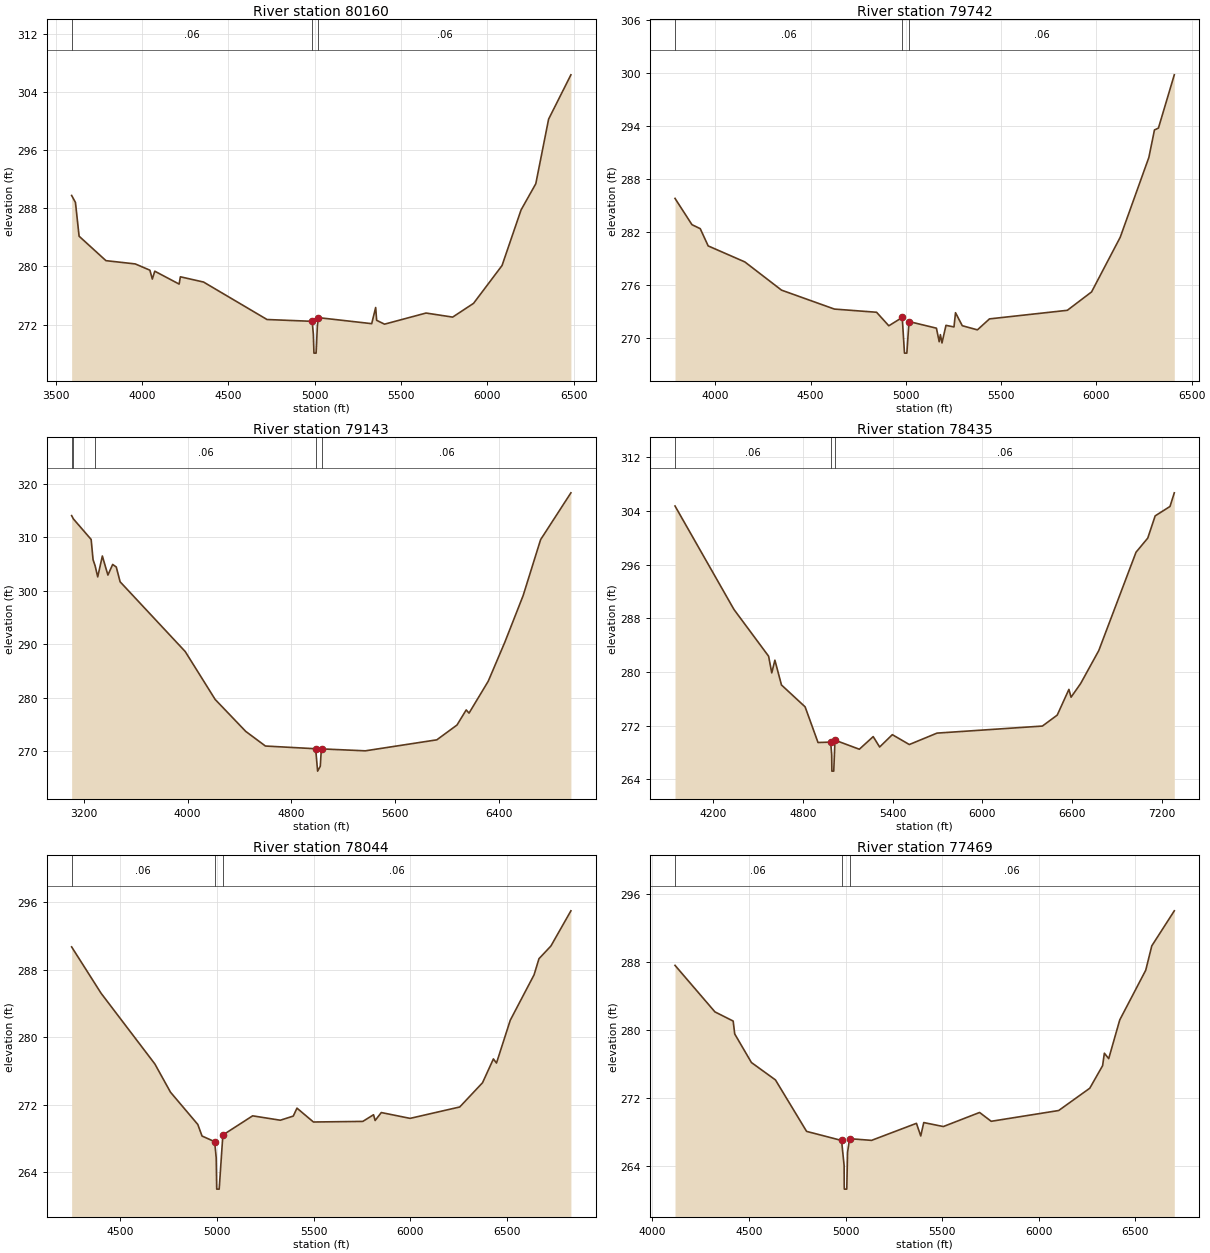
Type RM Length L Ch R = 1 ,80160   ,418,418,418
BEGIN DESCRIPTION:
CANEY CREEK 123.0
END DESCRIPTION:
XS GIS Cut Line= 3
      3693655.04      10139815.1      3692639.45     10138834.23
      3692018.78     10137488.71
#Sta/Elev= 30
    3591  289.75  3613.2  288.79  3634.3  284.15  3789.9  280.79  3959.7  280.34
  4044.6  279.48  4058.7  278.26  4072.9  279.34  4214.1  277.57  4221.3  278.57
  4355.6  277.85  4723.5   272.7  4985.1  272.45    4992  270.68  4995.4  268.08
  5007.9  268.08  5015.3  271.81  5020.8  272.96  5330.2  272.13  5353.1  274.35
  5358.8  272.59  5404.5  272.06  5645.1  273.59  5799.3  273.03  5920.4  274.92
  6085.6  280.12  6195.8  287.76  6281.2  291.36  6355.5  300.24  6484.7  306.33
#Mann= 3 , 0 , 0
    3591     .06       0  4985.1     .06       0  5020.8     .06       0
Bank Sta=4985.1,5020.8
XS Rating Curve= 0 ,0
Exp/Cntr=0.3,0.1

Type RM Length L Ch R = 1 ,79742   ,599,599,599
BEGIN DESCRIPTION:
CANEY CREEK 122.0
END DESCRIPTION:
XS GIS Cut Line= 3
      3693776.63      10139667.6      3693028.52      10138714.3
      3692192.61     10137580.17
#Sta/Elev= 30
  3788.2   285.8  3877.2  282.83  3920.6  282.38  3962.2  280.43  4154.7  278.62
  4347.3  275.43  4624.8  273.29  4846.2  272.93  4910.4   271.4  4980.9  272.34
  4992.6  268.31  5005.1  268.31  5016.4  271.88  5160.3  271.13  5174.9   269.6
  5181.1   270.4  5189.5  269.46  5210.4  271.45  5252.5  271.27  5260.5  272.88
    5296  271.41  5375.4  270.94  5438.8  272.18  5847.4  273.15  5974.7  275.23
  6125.1  281.41  6275.5  290.44  6304.8  293.54  6325.6  293.75  6408.9  299.77
#Mann= 3 , 0 , 0
  3788.2     .06       0  4980.9     .06       0  5016.4     .06       0
Bank Sta=4980.9,5016.4
XS Rating Curve= 0 ,0
Exp/Cntr=0.3,0.1

Type RM Length L Ch R = 1 ,79143   ,708,708,708
BEGIN DESCRIPTION:
CANEY CREEK 121.0
END DESCRIPTION:
XS GIS Cut Line= 3
      3694667.87      10140111.1      3693587.36      10138554.7
      3692117.84     10137261.07
#Sta/Elev= 30
  3105.3  314.07  3118.8  313.46  3255.9  309.61  3270.8  305.81  3286.7  304.67
  3306.6   302.6  3342.4  306.51  3385.3  302.94  3421.9  304.93  3449.8  304.45
  3479.5  301.68  3981.8  288.62  4212.9  279.65  4448.7  273.67  4600.6  270.93
  4988.3  270.42  5003.3  266.23  5023.8  267.13  5030.4  269.66    5038  270.39
    5371  270.03  5923.2  272.09  6078.8  274.86  6149.9  277.69  6171.7  277.09
  6319.8  283.06  6447.8  290.36  6589.2   299.1  6723.9  309.57  6957.8  318.34
#Mann= 5 ,-1 , 0
  3105.3     .06       0  3118.8     .12       0  3286.7     .06       0
  4988.3     .06       0    5038     .06       0
Bank Sta=4988.3,5038
XS Rating Curve= 0 ,0
Exp/Cntr=0.3,0.1

Type RM Length L Ch R = 1 ,78435   ,391,391,391
BEGIN DESCRIPTION:
CANEY CREEK 120.0
END DESCRIPTION:
XS GIS Cut Line= 3
      3694817.84     10139511.06      3694258.38     10138721.38
      3692432.44      10137216.4
#Sta/Elev= 30
    3947  304.72  4340.7  289.31    4572  282.35    4593  279.87  4613.9  281.76
  4657.8  278.07  4815.8  274.81  4901.9   269.5  4986.4  269.56  4993.2  267.69
  4994.5  265.24    5007  265.24  5015.1  269.85  5177.9   268.5  5270.4  270.38
  5313.4  268.83  5398.1  270.67  5511.6   269.2  5696.5   270.9  6400.2  271.95
  6499.2  273.58  6577.3  277.41  6591.7  276.25  6655.5  278.28  6776.7  283.19
  7025.6  297.84  7103.8  299.94  7153.3  303.25  7252.3  304.65    7281  306.68
#Mann= 3 , 0 , 0
    3947     .06       0  4986.4     .06       0  5015.1     .06       0
Bank Sta=4986.4,5015.1
XS Rating Curve= 0 ,0
Exp/Cntr=0.3,0.1

Type RM Length L Ch R = 1 ,78044   ,575,575,575
BEGIN DESCRIPTION:
CANEY CREEK 119.0
END DESCRIPTION:
XS GIS Cut Line= 3
      3694846.89     10139087.66      3694485.18     10138431.11
      3693867.76     10136709.26
#Sta/Elev= 30
  4250.4   290.7  4402.2  285.22  4680.4  276.83  4761.1  273.49  4902.1  269.67
  4923.9   268.3  4989.2  267.63  4997.2   265.7  4999.8  262.01  5012.5  262.01
  5031.6  268.42  5185.3  270.69  5328.4  270.17  5395.2  270.66  5414.4   271.6
  5499.3  269.96  5754.3  270.03  5809.8  270.82    5818  270.14  5849.9  271.08
  5998.6  270.39  6255.1  271.74  6372.7  274.61  6428.9  277.43  6444.8  276.94
  6515.9  282.01  6638.9  287.39  6664.3   289.3  6725.8   290.8  6829.2  294.97
#Mann= 3 , 0 , 0
  4250.4     .06       0  4989.2     .06       0  5031.6     .06       0
Bank Sta=4989.2,5031.6
XS Rating Curve= 0 ,0
Exp/Cntr=0.3,0.1

Type RM Length L Ch R = 1 ,77469   ,423,423,423
BEGIN DESCRIPTION:
CANEY CREEK 118.0
END DESCRIPTION:
XS GIS Cut Line= 4
      3695346.94     10138872.47      3694964.97     10138202.29
      3694770.53      10138150.2      3694030.95     10136719.66
#Sta/Elev= 30
  4117.9  287.62  4324.5  282.13  4418.8  281.05  4426.8  279.53  4513.2  276.16
  4637.5  274.11  4798.6  268.04  4979.5  266.97  4992.8  264.01  4993.3  261.73
  4993.8  261.23  5006.5  261.23  5010.5  265.55  5020.9  267.18  5134.7  266.98
    5367  268.99  5389.2   267.5  5404.8  269.08  5506.1  268.61  5693.6  270.27
  5753.8  269.23  6102.8   270.5  6263.7  273.13  6330.1  275.79  6339.2  277.26
  6361.7  276.62  6418.7  281.18  6553.1  287.04  6584.6  289.92    6701  294.05
#Mann= 3 , 0 , 0
  4117.9     .06       0  4979.5     .06       0  5020.9     .06       0
Bank Sta=4979.5,5020.9
XS Rating Curve= 0 ,0
Exp/Cntr=0.3,0.1

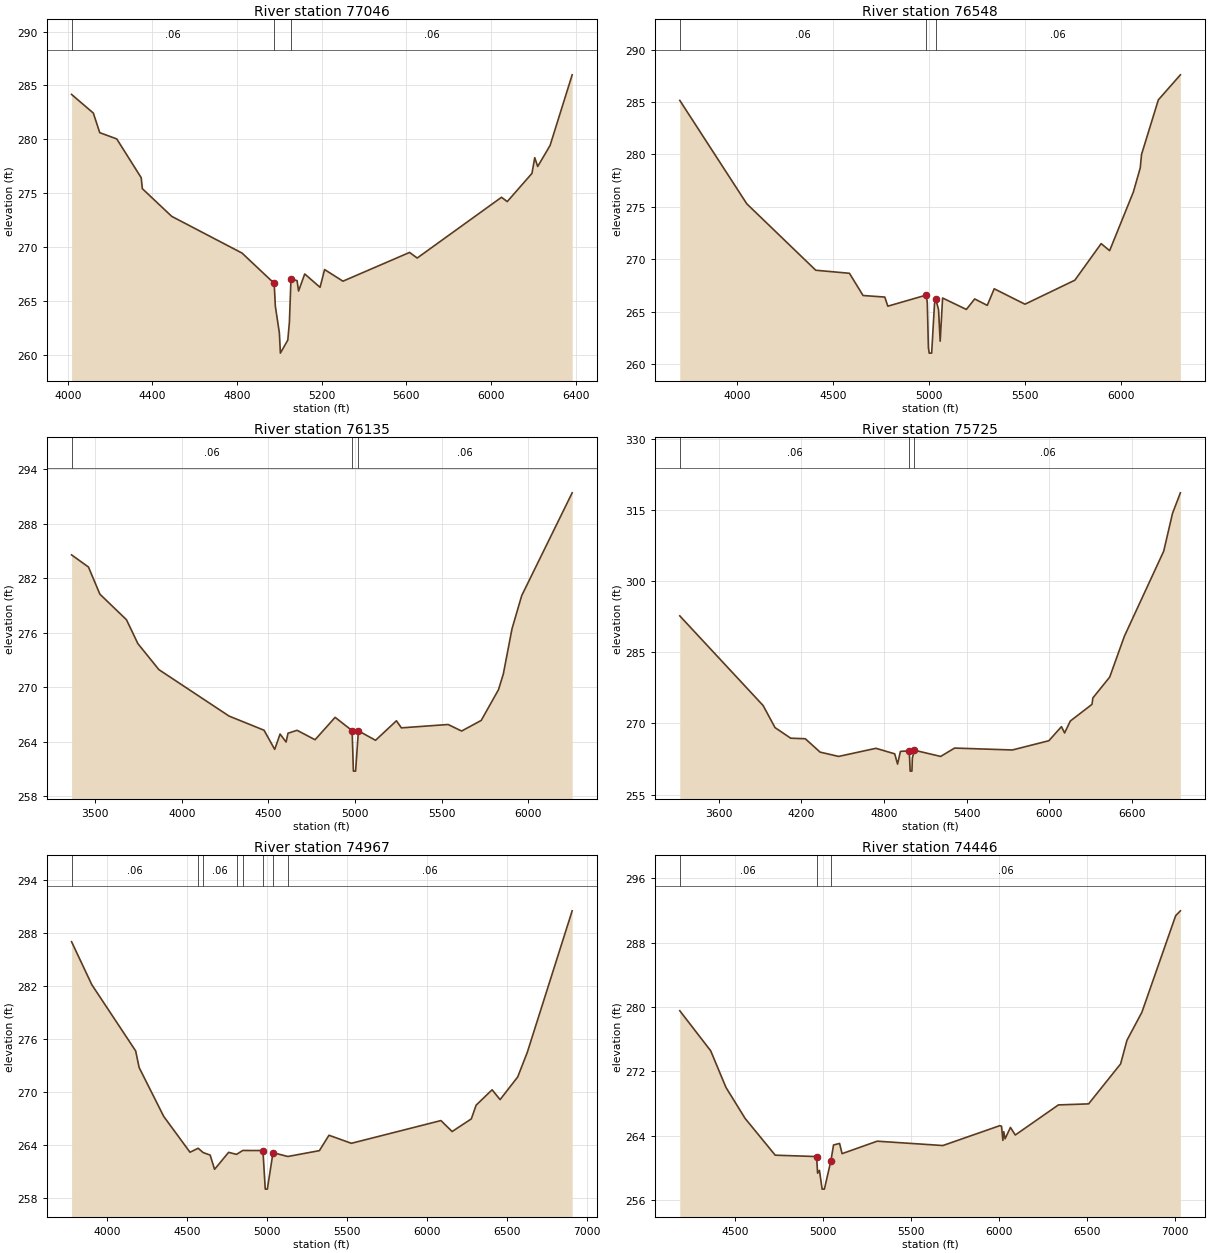
Type RM Length L Ch R = 1 ,77046   ,498,498,498
BEGIN DESCRIPTION:
CANEY CREEK 117.0
END DESCRIPTION:
XS GIS Cut Line= 3
      3695478.86     10138764.78      3695074.33      10137870.3
      3694299.32     10136724.61
#Sta/Elev= 30
  4018.3  284.17  4121.1  282.44  4151.4  280.62  4231.7  280.04  4347.2  276.44
  4352.7  275.42  4491.4  272.85  4823.6  269.44  4975.5  266.63    4981   264.5
    5000  262.03  5004.8  260.15  5039.8  261.36  5047.4  263.03  5054.8  267.04
  5083.6  266.88  5090.7  265.92  5119.8   267.5  5192.2  266.26  5213.6  267.91
  5300.4  266.83  5615.1   269.5  5651.1  268.98  6049.4  274.62  6076.5  274.22
  6193.3  276.84  6206.4   278.3  6220.4  277.48  6278.8  279.43  6383.2  285.99
#Mann= 3 , 0 , 0
  4018.3     .06       0  4975.5     .06       0  5054.8     .06       0
Bank Sta=4975.5,5054.8
XS Rating Curve= 0 ,0
Exp/Cntr=0.3,0.1

Type RM Length L Ch R = 1 ,76548   ,413,413,413
BEGIN DESCRIPTION:
CANEY CREEK 116.0
END DESCRIPTION:
XS GIS Cut Line= 3
      3695917.85     10138711.08      3695408.29     10137519.13
      3694692.53     10136426.49
#Sta/Elev= 30
  3703.7  285.16  4052.1  275.29  4410.6  268.95  4585.7  268.66  4656.5  266.54
  4769.5  266.39  4785.3  265.52    4985  266.58  4990.4  265.87  4996.2  261.57
  5000.4  261.04  5013.1  261.04  5027.9  265.74  5033.8  266.24  5048.9   265.2
  5057.4  262.18    5070   266.3  5193.7  265.21  5236.8  266.21  5302.2   265.6
  5338.4  267.18  5498.2  265.71  5757.5     268  5894.3  271.49  5938.4  270.82
  6061.6  276.41  6097.5  278.71  6104.2     280  6191.6  285.21  6306.2   287.6
#Mann= 3 , 0 , 0
  3703.7     .06       0    4985     .06       0  5033.8     .06       0
Bank Sta=4985,5033.8
XS Rating Curve= 0 ,0
Exp/Cntr=0.3,0.1

Type RM Length L Ch R = 1 ,76135   ,410,410,410
BEGIN DESCRIPTION:
CANEY CREEK 115.0
END DESCRIPTION:
XS GIS Cut Line= 3
      3696357.32       10138750.      3695684.59     10137252.63
      3694867.84     10136311.06
#Sta/Elev= 30
  3364.3  284.58  3461.8  283.24  3527.6  280.25  3681.1  277.43  3746.8   274.8
  3868.1  271.93  4272.8  266.81  4474.6  265.25  4536.2  263.14  4567.2  264.83
  4601.9  263.95  4612.9  264.92  4665.4  265.24    4769   264.2  4884.8  266.67
  4982.9   265.2  4990.2  260.74  5002.9  260.74  5019.1  265.18  5117.9  264.14
  5238.5  266.29    5267  265.51  5536.7  265.88  5614.6  265.16  5727.6  266.33
  5827.3  269.72  5855.1  271.45  5905.2  276.43  5961.2  280.09  6252.3  291.42
#Mann= 3 , 0 , 0
  3364.3     .06       0  4982.9     .06       0  5019.1     .06       0
Bank Sta=4982.9,5019.1
XS Rating Curve= 0 ,0
Exp/Cntr=0.3,0.1

Type RM Length L Ch R = 1 ,75725   ,758,758,758
BEGIN DESCRIPTION:
CANEY CREEK 114.0
END DESCRIPTION:
XS GIS Cut Line= 3
      3697117.84     10138461.06      3696070.88     10137148.47
      3694867.88      10135611.1
#Sta/Elev= 30
    3319  292.66  3923.5  273.76  4009.7  269.11  4123.6  266.87  4229.3  266.76
  4336.6  263.94  4471.1  263.03  4741.7  264.74  4877.9  263.58  4898.7  261.41
  4919.5  264.09  4983.5  264.21  4990.1  259.93  5002.8  259.93    5006  262.67
  5020.1  264.34  5211.3  263.03  5312.1  264.79  5731.3  264.39  5996.2  266.34
  6087.5  269.31  6110.1  267.98  6151.7  270.49    6309  274.01  6315.4  275.36
  6437.4  279.76  6543.8  288.36    6829  306.29  6893.2  314.29  6950.1   318.6
#Mann= 3 , 0 , 0
    3319     .06       0  4983.5     .06       0  5020.1     .06       0
Bank Sta=4983.5,5020.1
XS Rating Curve= 0 ,0
Exp/Cntr=0.3,0.1

Type RM Length L Ch R = 1 ,74967   ,521,521,521
BEGIN DESCRIPTION:
CANEY CREEK 113.0
END DESCRIPTION:
XS GIS Cut Line= 3
      3697293.08     10138206.59      3696717.68     10137128.99
      3696728.86     10135220.52
#Sta/Elev= 30
  3778.4  286.98    3905  282.12    4179  274.64    4201  272.75  4354.6  267.23
  4518.9  263.18  4569.9  263.63  4601.4  263.14  4644.9  262.86  4672.6  261.25
  4760.4  263.17    4810  262.94  4848.9  263.38    4975  263.37  4989.5  259.01
  5002.4  259.01  5037.9  263.13  5130.7   262.7  5327.9  263.36  5387.9   265.1
  5527.9  264.19  6087.9  266.76  6157.9  265.52  6277.9  266.95  6307.9   268.5
  6407.9  270.24  6457.9  269.13  6567.9  271.69  6627.9  274.47  6908.5  290.47
#Mann= 8 ,-1 , 0
  3778.4     .06       0  4569.9      .1       0  4601.4     .06       0
    4810     .12       0  4848.9     .06       0    4975     .06       0
  5037.9     .12       0  5130.7     .06       0
Bank Sta=4975,5037.9
XS Rating Curve= 0 ,0
Exp/Cntr=0.3,0.1

Type RM Length L Ch R = 1 ,74446   ,428,428,428
BEGIN DESCRIPTION:
CANEY CREEK 112.0
END DESCRIPTION:
XS GIS Cut Line= 3
      3697510.13     10137915.86      3697063.06     10137108.54
      3696789.83     10135204.58
#Sta/Elev= 30
  4183.8  279.52  4359.5  274.54  4446.5  269.98  4555.3  266.13  4726.5  261.56
  4961.7  261.39  4967.4  259.32  4977.8  259.68  4993.1  257.34    5006  257.34
    5043  260.87    5058  262.83  5092.3  263.02  5106.6  261.75  5306.1   263.3
  5679.9  262.76  6003.2  265.23  6013.3  265.16  6020.8   263.4  6025.9  264.48
  6033.5   263.6  6063.8  265.01  6091.4  264.07  6336.6  267.81  6508.3  267.94
  6690.2  272.91  6726.4  275.85  6811.4  279.34  7003.3  291.34  7030.1  291.94
#Mann= 3 , 0 , 0
  4183.8     .06       0  4961.7     .07       0    5043     .06       0
Bank Sta=4961.7,5043
XS Rating Curve= 0 ,0
Exp/Cntr=0.3,0.1

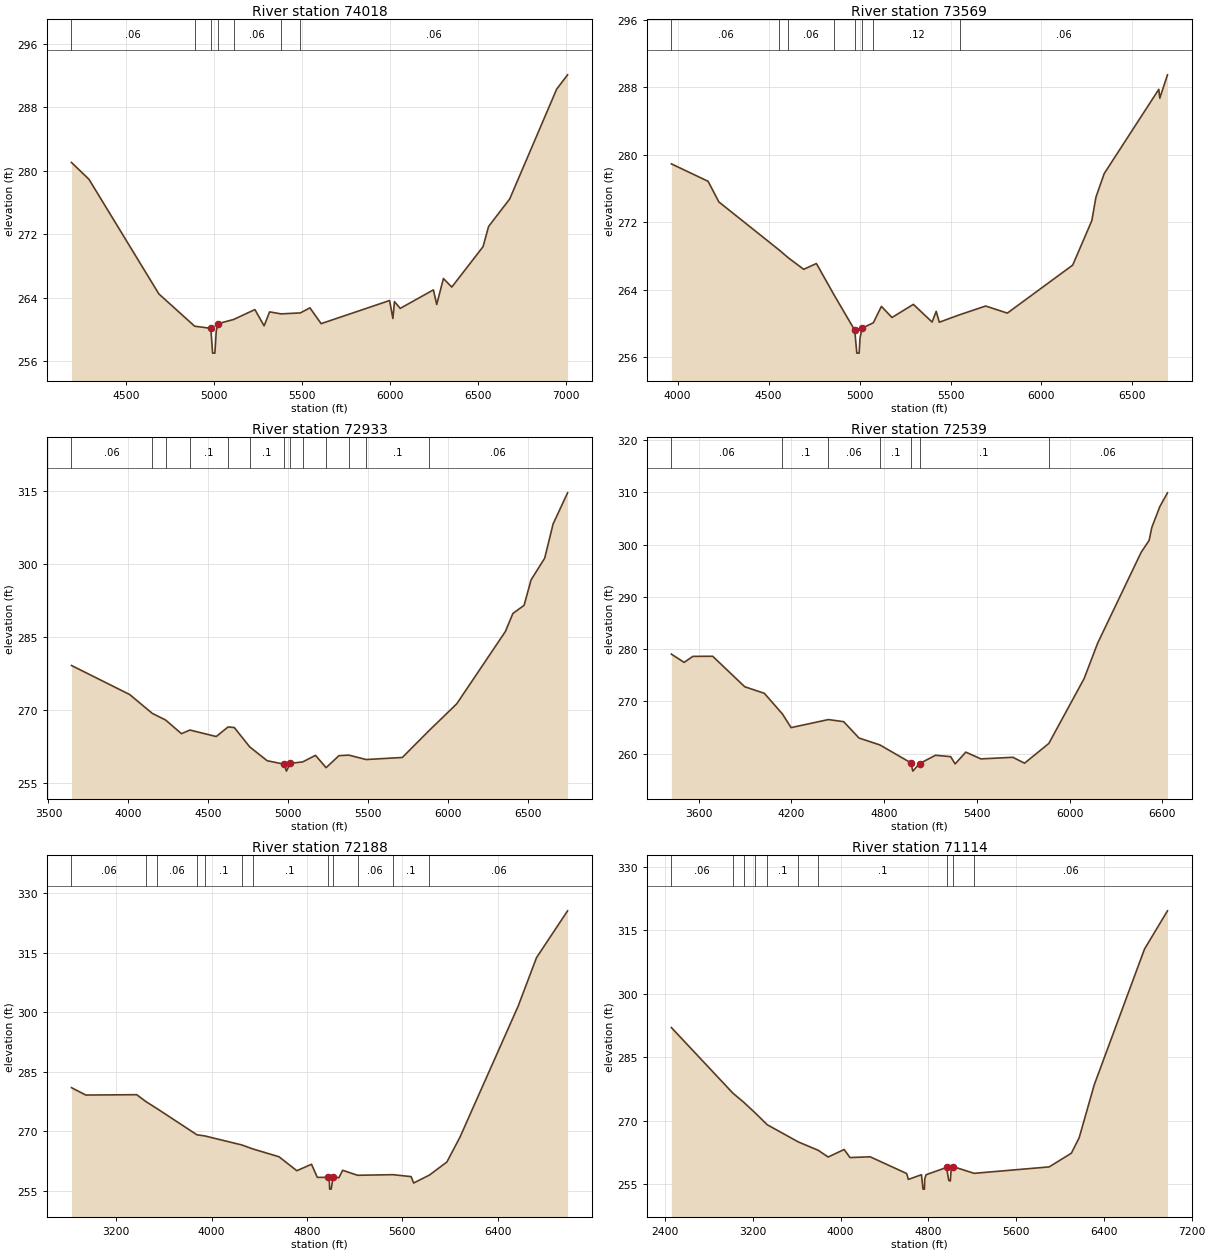
Type RM Length L Ch R = 1 ,74018   ,449,449,449
BEGIN DESCRIPTION:
CANEY CREEK 111.0
END DESCRIPTION:
XS GIS Cut Line= 3
      3697644.66     10137928.86      3697492.42     10137131.16
      3696906.81     10135211.81
#Sta/Elev= 30
  4187.9  281.03  4287.5  278.91  4684.5  264.49  4887.7  260.43  4979.7  260.16
  4989.9  257.04  5002.8  257.04  5010.5  259.83    5021  260.75  5108.9  261.27
  5230.1  262.52  5282.4  260.48  5313.7  262.23  5378.7  261.98  5488.6   262.1
  5542.7  262.74  5606.5  260.75  5995.4  263.66  6014.2   261.4    6023  263.52
  6055.8  262.67  6244.3     265  6263.2  263.16  6301.2  266.43  6348.8  265.35
  6526.5  270.44  6557.9  272.98  6677.9  276.44  6944.7  290.26  7006.7  292.06
#Mann= 7 ,-1 , 0
  4187.9     .06       0  4887.7     .12       0  4979.7     .09       0
    5021     .12       0  5108.9     .06       0  5378.7     .12       0
  5488.6     .06       0
Bank Sta=4979.7,5021
XS Rating Curve= 0 ,0
Exp/Cntr=0.3,0.1

Type RM Length L Ch R = 1 ,73569   ,636,636,636
BEGIN DESCRIPTION:
CANEY CREEK 110.0
END DESCRIPTION:
XS GIS Cut Line= 4
      3697822.61      10137781.3      3697982.39     10137278.76
      3697648.31     10136503.36      3697063.07      10135281.3
#Sta/Elev= 30
  3965.9  278.93  4167.7  276.86    4227  274.41  4559.7  268.68  4607.9  267.79
  4693.2  266.41  4762.9   267.1  4858.8  263.42  4973.7  259.18  4985.1  256.46
    4998  256.46  5002.7  258.24  5013.4   259.4  5076.1  260.07  5120.3  262.01
  5178.3  260.69  5295.9  262.25  5398.8  260.15  5421.4  261.42  5438.5  260.13
    5552  261.03  5693.4  262.05  5812.3  261.21  6171.6  266.91  6276.6  272.18
  6299.3  274.97  6344.6  277.77  6644.8  287.78  6650.3  286.73  6692.5   289.5
#Mann= 8 ,-1 , 0
  3965.9     .06       0  4559.7     .12       0  4607.9     .06       0
  4858.8      .1       0  4973.7     .07       0  5013.4     .06       0
  5076.1     .12       0    5552     .06       0
Bank Sta=4973.7,5013.4
XS Rating Curve= 0 ,0
Exp/Cntr=0.3,0.1

Type RM Length L Ch R = 1 ,72933   ,394,394,394
BEGIN DESCRIPTION:
CANEY CREEK 109.0
END DESCRIPTION:
XS GIS Cut Line= 3
      3697883.39     10137720.48      3698258.48     10136417.18
      3697567.85     10134811.08
#Sta/Elev= 30
  3643.8   279.1    4008  273.14  4149.1  269.28  4232.8  267.91    4332  265.11
  4385.2  265.85  4549.7  264.52  4624.1  266.49    4663  266.36  4759.1   262.4
  4868.5  259.55  4974.8  258.85  4988.9  257.42  5013.2  259.02  5090.7  259.31
  5170.8  260.66  5237.2  258.13  5317.5  260.59  5378.9  260.71  5487.7   259.8
  5714.2  260.22  5879.8  265.68  6054.6  271.23  6358.9  286.06    6406  289.77
  6476.2  291.45  6519.7  296.65  6605.2  301.13  6657.7  308.14  6748.3  314.53
#Mann= 13 ,-1 , 0
  3643.8     .06       0  4149.1     .12       0  4232.8     .06       0
  4385.2      .1       0  4624.1     .06       0  4759.1      .1       0
  4974.8     .09       0  5013.2      .1       0  5090.7     .06       0
  5237.2      .1       0  5378.9     .06       0  5487.7      .1       0
  5879.8     .06       0
Bank Sta=4974.8,5013.2
XS Rating Curve= 0 ,0
Exp/Cntr=0.3,0.1

Type RM Length L Ch R = 1 ,72539   ,351,351,351
BEGIN DESCRIPTION:
CANEY CREEK 108.0
END DESCRIPTION:
XS GIS Cut Line= 3
      3697922.46     10137724.82       3698629.9     10136322.95
      3697952.85     10134829.95
#Sta/Elev= 30
    3423  279.05  3505.6  277.47  3562.1  278.62  3690.3  278.64  3897.6  272.81
  4024.8  271.54  4141.5  267.59  4197.6  264.98  4438.7  266.52  4537.7  266.12
  4636.9  262.99  4772.4  261.66  4972.5  258.24  4985.1  256.65  5028.3  258.09
    5132  259.69  5229.8  259.42  5258.8  258.03  5327.7  260.29  5425.5  258.99
  5632.2   259.3    5708  258.17    5865  261.95  6093.3  274.37  6181.2  281.17
  6462.1  298.53  6513.8  300.82  6531.4  303.32  6583.1  307.29  6632.6  309.93
#Mann= 7 ,-1 , 0
    3423     .06       0  4141.5      .1       0  4438.7     .06       0
  4772.4      .1       0  4972.5     .09       0  5028.3      .1       0
    5865     .06       0
Bank Sta=4972.5,5028.3
XS Rating Curve= 0 ,0
Exp/Cntr=0.3,0.1

Type RM Length L Ch R = 1 ,72188   ,1074,1074,1074
BEGIN DESCRIPTION:
CANEY CREEK 107.0
END DESCRIPTION:
XS GIS Cut Line= 3
      3697767.06     10137980.06      3699037.89     10136417.56
      3697940.65     10134570.32
#Sta/Elev= 30
  2824.8     281  2945.4  279.14  3372.1  279.23  3449.7  277.49  3545.1  275.68
  3877.9  269.12  3942.3  268.85  4255.4  266.56  4345.9  265.57  4565.8   263.6
  4715.9  260.08  4838.9  261.71  4887.5  258.41  4974.3  258.41  4988.8  257.27
  4991.2  255.44  5004.1  255.44    5020  258.58  5068.7  258.31  5099.9  260.19
  5225.6  258.93  5522.5  259.08  5674.6  258.59    5696  256.98  5828.1  258.98
  5974.6  262.27  6083.7  268.48  6572.8  301.54  6726.7  313.75  6987.4  325.55
#Mann= 12 ,-1 , 0
  2824.8     .06       0  3449.7     .12       0  3545.1     .06       0
  3877.9     .12       0  3942.3      .1       0  4255.4     .06       0
  4345.9      .1       0  4974.3     .09       0    5020      .1       0
  5225.6     .06       0  5522.5      .1       0  5828.1     .06       0
Bank Sta=4974.3,5020
XS Rating Curve= 0 ,0
Exp/Cntr=0.3,0.1

Type RM Length L Ch R = 1 ,71114   ,337,337,337
BEGIN DESCRIPTION:
CANEY CREEK 106.0
END DESCRIPTION:
XS GIS Cut Line= 3
      3700267.85     10138261.05      3699530.95     10135542.56
      3698135.13     10134563.41
#Sta/Elev= 30
  2457.4  292.03  3017.9  276.51  3120.8  274.26  3223.7  271.77  3331.1  269.03
  3614.4  264.96  3795.5  262.98  3886.4  261.39  4032.2  263.17  4085.5  261.26
  4269.1  261.44  4602.1  257.48  4617.3  256.09  4736.8   257.2  4750.8  253.79
  4764.1  253.79  4766.2  256.11  4778.2  257.19  4965.4  258.92  4985.4  255.86
  5000.1  255.72  5006.2   258.1  5026.9   259.1    5217  257.53  5900.8  259.05
    6103  262.29  6174.5  265.98  6311.3  278.46  6769.8  310.61    6979  319.65
#Mann= 10 ,-1 , 0
  2457.4     .06       0  3017.9     .12       0  3120.8     .06       0
  3223.7     .12       0  3331.1      .1       0  3614.4     .12       0
  3795.5      .1       0  4965.4     .09       0  5026.9      .1       0
    5217     .06       0
Bank Sta=4965.4,5026.9
XS Rating Curve= 0 ,0
Exp/Cntr=0.3,0.1