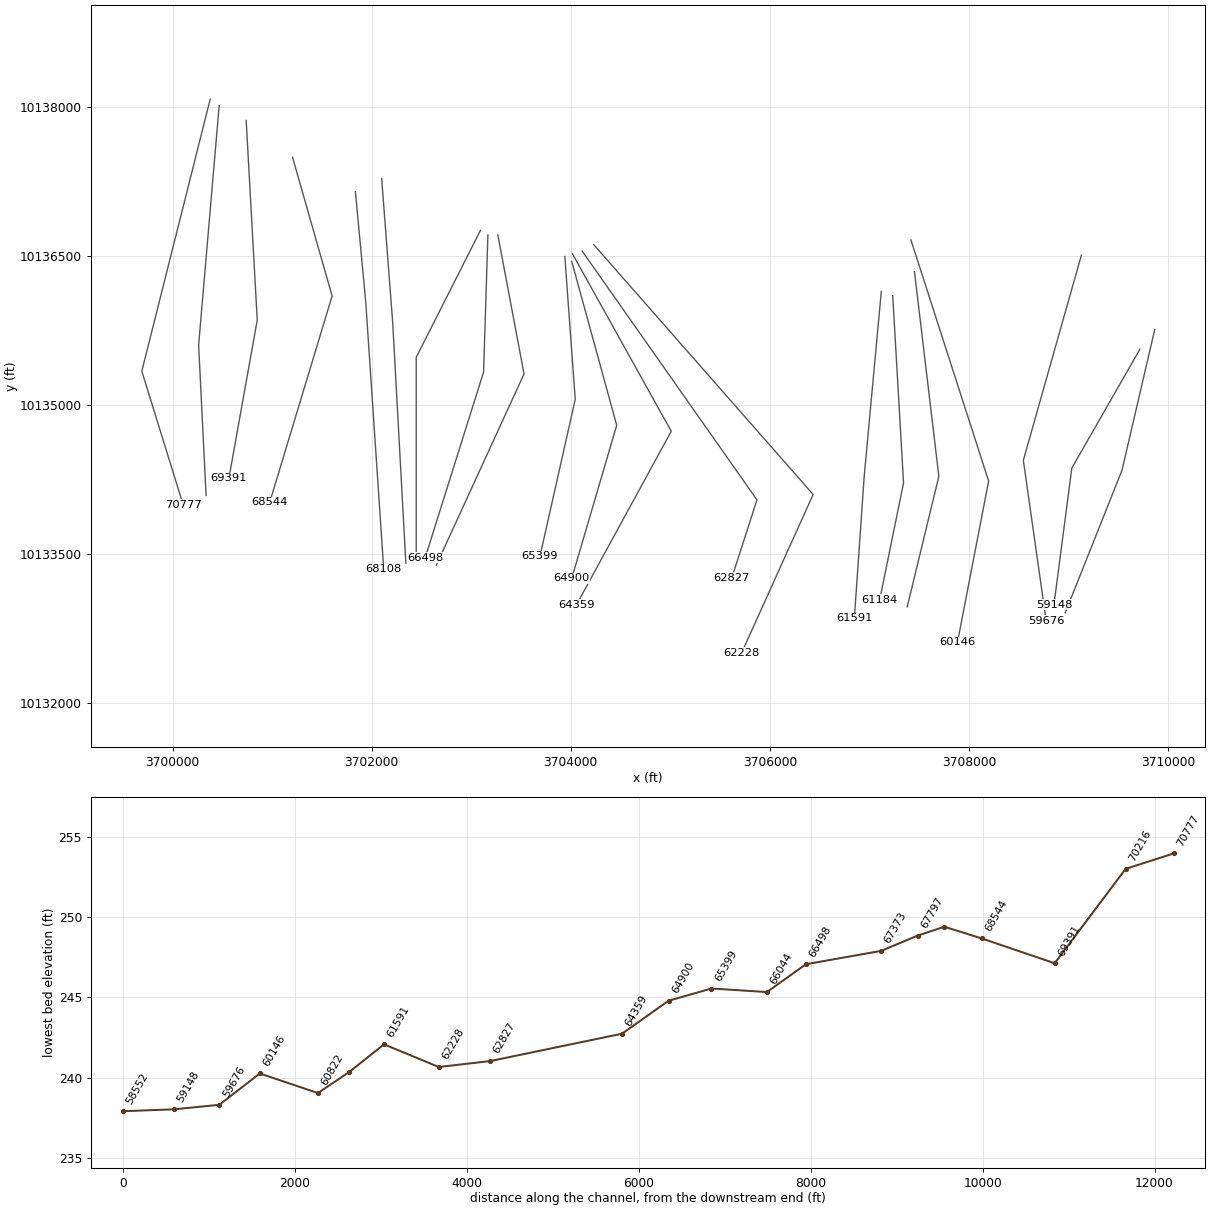
HEC-RAS study CANEY CREEK.prj: CANEY CREEK Base Level Engineering

--- CANEY CREEK.g01 (geometry) --- (continued)

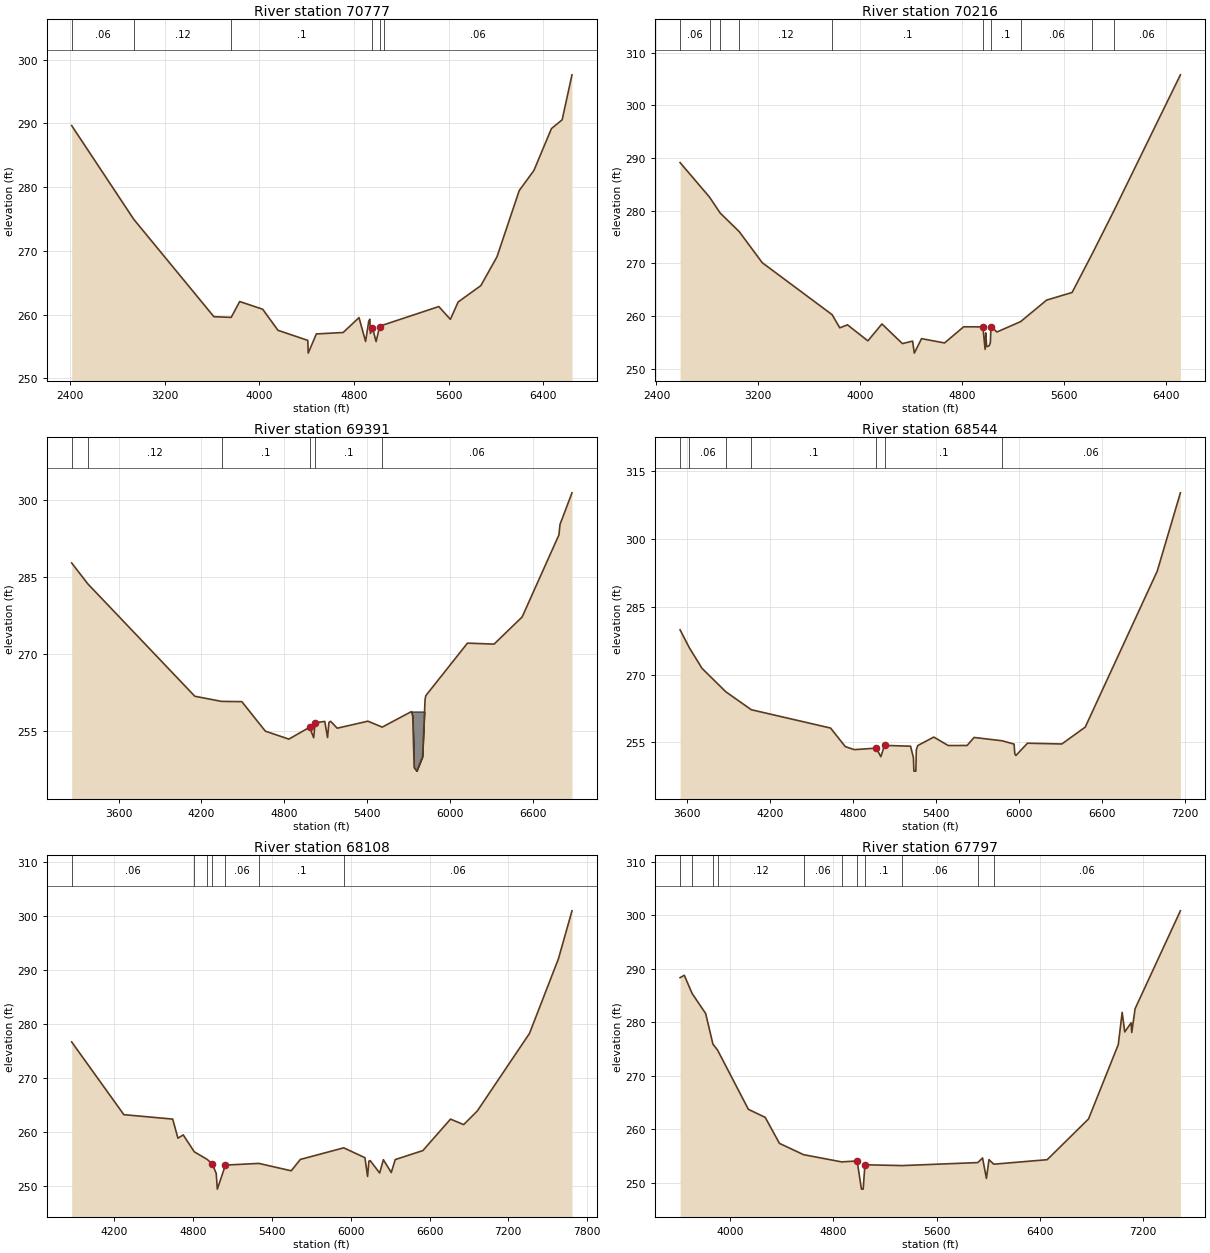
Type RM Length L Ch R = 1 ,70777   ,561,561,561
BEGIN DESCRIPTION:
CANEY CREEK 105.0
END DESCRIPTION:
XS GIS Cut Line= 3
      3700378.18     10138077.32      3699690.67     10135341.18
      3700107.01     10133994.99
#Sta/Elev= 30
  2413.4  289.66  2938.2  274.96  3615.9  259.67  3762.1  259.56    3834  262.05
  4028.3  260.84    4158  257.53    4410  255.95  4413.5  253.95  4481.9  256.96
  4708.9  257.19  4842.9  259.53  4898.5  255.78  4925.4  258.99  4934.5  259.27
  4939.6  257.05  4956.3  257.96  4987.2  255.76  5016.7  258.08  5054.7  258.41
  5517.7  261.26  5615.5  259.25  5680.8  261.97  5873.2  264.55  6009.3  269.06
  6197.7  279.47  6321.5  282.61  6469.9  289.19  6560.4  290.57  6643.7  297.63
#Mann= 6 ,-1 , 0
  2413.4     .06       0  2938.2     .12       0  3762.1      .1       0
  4956.3     .09       0  5016.7      .1       0  5054.7     .06       0
Bank Sta=4956.3,5016.7
XS Rating Curve= 0 ,0
Exp/Cntr=0.3,0.1

Type RM Length L Ch R = 1 ,70216   ,825,825,825
BEGIN DESCRIPTION:
CANEY CREEK 104.0
END DESCRIPTION:
XS GIS Cut Line= 3
      3700467.86     10138011.12      3700261.52     10135605.55
       3700336.5     10134091.21
#Sta/Elev= 30
  2585.6  289.15    2817  282.59  2901.4  279.55  3050.5  276.04  3231.1  270.15
  3779.9  260.29  3840.2  257.79  3900.5  258.36    4061  255.32  4171.4  258.53
    4332   254.8  4412.3  255.27  4425.8  252.99  4482.6  255.74  4663.2  254.92
  4813.8  257.99  4964.4  257.97  4981.9   253.7  4986.9  256.83  4994.5  254.21
  5014.5  254.39  5023.2  254.99  5028.2  258.02  5074.6     257  5261.1  258.97
    5465  263.05  5665.3   264.5  5824.6  271.89  5991.9  279.91  6516.2   305.8
#Mann= 10 ,-1 , 0
  2585.6     .06       0    2817     .12       0  2901.4     .06       0
  3050.5     .12       0  3779.9      .1       0  4964.4     .09       0
  5028.2      .1       0  5261.1     .06       0  5824.6     .12       0
  5991.9     .06       0
Bank Sta=4964.4,5028.2
XS Rating Curve= 0 ,0
Exp/Cntr=0.3,0.1

Type RM Length L Ch R = 1 ,69391   ,847,847,847
BEGIN DESCRIPTION:
CANEY CREEK 103.0
END DESCRIPTION:
XS GIS Cut Line= 3
      3700739.28     10137862.03      3700850.39     10135855.06
      3700565.79     10134265.48
#Sta/Elev= 30
  3259.7  287.71  3377.6  283.61    4152  261.72  4345.5  260.72  4492.5  260.67
  4662.8  254.92  4833.1  253.36  4983.3  255.67  5013.3  253.63  5023.4  256.57
  5093.5  256.81  5113.5  253.67  5123.5  256.62  5135.9  256.84  5183.6  255.49
  5405.9  256.86  5509.9   255.7  5720.8  258.73  5730.9  257.85  5741.1  247.82
  5759.8  247.12  5802.1  249.95  5820.2  261.12  5825.3  261.83  6127.2  272.08
  6320.2  271.89  6523.4  277.18  6790.2   293.2  6797.6  295.21  6884.6  301.39
#Mann= 6 ,-1 , 0
  3259.7     .06       0  3377.6     .12       0  4345.5      .1       0
  4983.3     .09       0  5023.4      .1       0  5509.9     .06       0
#Block Obstruct= 1 ,-1
 5720.84  5824.2  258.75
Bank Sta=4983.3,5023.4
XS Rating Curve= 0 ,0
Exp/Cntr=0.3,0.1

Type RM Length L Ch R = 1 ,68544   ,436,436,436
BEGIN DESCRIPTION:
CANEY CREEK 102.0
END DESCRIPTION:
XS GIS Cut Line= 3
      3701204.56     10137493.95      3701602.58     10136096.94
      3700975.39     10134021.75
#Sta/Elev= 30
  3547.4   279.9  3614.6  275.91  3706.4  271.37  3878.2   266.2  4062.9  262.23
  4636.5  258.18  4743.2  254.07  4808.5  253.41  4967.1  253.74    5000  251.85
    5027  254.35  5215.1  254.17  5235.9  251.67  5239.2  248.66  5253.6  248.66
  5256.9   253.4  5267.3  254.31  5383.4  256.19  5487.4  254.32  5624.5  254.33
  5674.7   256.1  5877.8  255.37  5964.5  254.63  5969.7  252.47  5977.7  252.12
  6061.3  254.83  6309.7  254.66  6479.1  258.38    7000  292.84  7167.9  310.17
#Mann= 7 ,-1 , 0
  3547.4     .12       0  3614.6     .06       0  3878.2     .12       0
  4062.9      .1       0  4967.1     .09       0    5027      .1       0
  5877.8     .06       0
Bank Sta=4967.1,5027
XS Rating Curve= 0 ,0
Exp/Cntr=0.3,0.1

Type RM Length L Ch R = 1 ,68108   ,311,311,311
BEGIN DESCRIPTION:
CANEY CREEK 101.0
END DESCRIPTION:
XS GIS Cut Line= 3
       3701836.5     10137146.78      3701940.67     10136035.62
      3702121.22     10133348.11
#Sta/Elev= 30
  3875.2  276.69  4272.6   263.2  4644.3  262.38  4684.4  258.84  4724.6  259.45
  4808.9  256.31  4907.3   254.9  4945.6  254.07  4975.7  252.32  4984.3  249.39
  5045.9  253.85  5300.5  254.16    5547  252.79  5616.4   254.9    5947  257.05
  6108.3  255.22  6128.3  251.75  6138.4  254.57  6148.4  254.68  6220.4  252.38
  6248.6  254.85  6308.7  252.47  6338.8  254.87  6549.3  256.54  6759.8  262.38
    6860  261.36  6964.2   263.9  7361.1  278.27  7581.6  292.11  7684.8  301.01
#Mann= 7 ,-1 , 0
  3875.2     .06       0  4808.9      .1       0  4907.3     .06       0
  4945.6     .06       0  5045.9     .06       0  5300.5      .1       0
    5947     .06       0
Bank Sta=4945.6,5045.9
XS Rating Curve= 0 ,0
Exp/Cntr=0.3,0.1

Type RM Length L Ch R = 1 ,67797   ,424,424,424
BEGIN DESCRIPTION:
CANEY CREEK 100.0
END DESCRIPTION:
XS GIS Cut Line= 3
      3702100.39     10137278.67       3702211.5     10135827.29
      3702343.45     10133410.62
#Sta/Elev= 30
  3612.8  288.35  3645.3   288.8  3706.3  285.39    3811  281.65  3867.2  275.94
  3903.6   274.8  4141.9  263.75  4272.3  262.25  4382.6  257.39  4569.1  255.28
  4864.1  253.93  4984.4   254.1  5017.8  248.84  5031.2  248.84  5044.6  253.39
  5334.4  253.24  5919.3   253.8    5956  254.67    5986  250.84  6005.7  254.35
  6043.1   253.5  6456.7  254.34  6777.2  261.96  7007.5  275.85  7037.6  281.86
  7057.6  278.21  7106.8  279.92  7111.8  278.11  7137.7  282.55  7488.7  300.84
#Mann= 11 ,-1 , 0
  3612.8     .06       0  3706.3     .12       0  3867.2     .06       0
  3903.6     .12       0  4569.1     .06       0  4864.1      .1       0
  4984.4     .09       0  5044.6      .1       0  5334.4     .06       0
  5919.3      .1       0  6043.1     .06       0
Bank Sta=4984.4,5044.6
XS Rating Curve= 0 ,0
Exp/Cntr=0.3,0.1

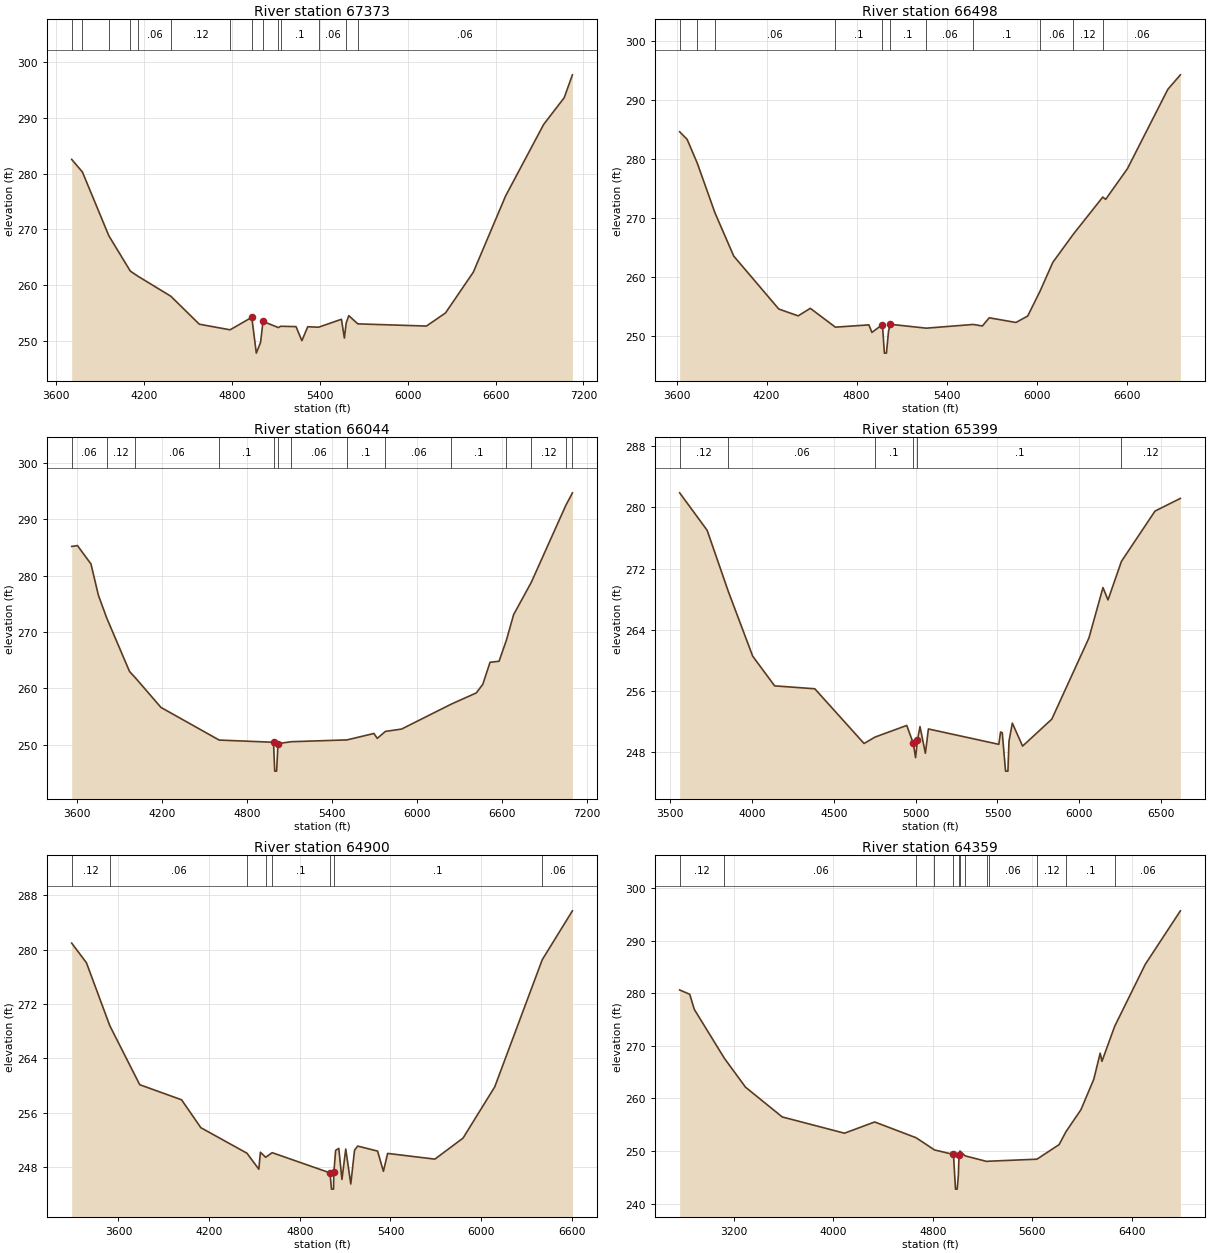
Type RM Length L Ch R = 1 ,67373   ,875,875,875
BEGIN DESCRIPTION:
CANEY CREEK 99.0
END DESCRIPTION:
XS GIS Cut Line= 3
      3703093.43     10136757.82      3702447.61     10135480.06
      3702447.61     10133495.05
#Sta/Elev= 30
  3707.9  282.52    3781  280.27  3961.6  268.86    4108  262.55  4162.9  261.59
  4384.4  258.06  4578.8  253.06  4788.5  252.06  4936.8  254.29  4967.7  247.89
  4996.7  249.81  5013.4  253.56  5118.1  252.46  5133.8  252.69  5238.6  252.63
  5278.6  250.11  5318.6  252.61  5392.4  252.52  5548.6  253.94  5568.6  250.58
  5580.8  253.27  5598.6  254.59  5660.2  253.12  6128.6  252.73  6258.6  255.07
  6448.6  262.37  6668.6  275.98  6928.6  288.78  7068.6  293.55  7124.6  297.64
#Mann= 14 ,-1 , 0
  3707.9     .06       0    3781     .12       0  3961.6     .06       0
    4108     .12       0  4162.9     .06       0  4384.4     .12       0
  4788.5      .1       0  4936.8     .09       0  5013.4      .1       0
  5118.1     .06       0  5133.8      .1       0  5392.4     .06       0
  5580.8      .1       0  5660.2     .06       0
Bank Sta=4936.8,5013.4
XS Rating Curve= 0 ,0
Exp/Cntr=0.3,0.1

Type RM Length L Ch R = 1 ,66498   ,454,454,454
BEGIN DESCRIPTION:
CANEY CREEK 98.0
END DESCRIPTION:
XS GIS Cut Line= 3
      3703167.85     10136711.03      3703124.39     10135332.51
       3702537.9      10133466.2
#Sta/Elev= 30
  3620.8  284.66  3670.8  283.36    3739  279.27  3855.5  270.92  3980.9  263.55
  4281.1  254.55  4410.1  253.39  4491.2  254.67  4658.1  251.47  4881.4  251.86
  4901.4  250.58  4971.4   251.9  4984.7  247.06  4998.1  247.06    5012  250.75
  5022.5  251.96  5263.7   251.3  5576.7  251.93  5637.3  251.67  5682.9  253.06
    5861  252.27  5939.4  253.36  6022.5  257.64  6106.6  262.48  6244.1  267.29
  6439.4  273.57  6458.5  273.18  6603.1  278.37  6872.8  291.87  6956.3  294.33
#Mann= 11 ,-1 , 0
  3620.8     .06       0    3739     .12       0  3855.5     .06       0
  4658.1      .1       0  4971.4     .09       0  5022.5      .1       0
  5263.7     .06       0  5576.7      .1       0  6022.5     .06       0
  6244.1     .12       0  6439.4     .06       0
Bank Sta=4971.4,5022.5
XS Rating Curve= 0 ,0
Exp/Cntr=0.3,0.1

Type RM Length L Ch R = 1 ,66044   ,645,645,645
BEGIN DESCRIPTION:
CANEY CREEK 97.0
END DESCRIPTION:
XS GIS Cut Line= 3
      3703267.86     10136711.05      3703530.95      10135313.4
      3702649.02     10133389.83
#Sta/Elev= 30
  3560.5  285.19  3601.2  285.34  3696.7  282.08  3749.2  276.53  3808.2  272.49
  3969.2  263.01  4006.8  261.99  4191.4  256.63  4602.6  250.84  4986.7  250.45
  4995.2  245.33  5008.6  245.33  5018.3  250.21  5112.9  250.55    5506  250.87
  5696.4  252.01  5719.4  251.14  5777.7  252.38  5891.4  252.79    6243  257.22
  6419.3   259.2  6465.3  260.72  6516.8  264.64  6580.3  264.82  6632.6  268.58
  6683.3  273.09  6808.3  278.83  7052.8  292.51  7093.8  294.43  7098.8   294.7
#Mann= 14 ,-1 , 0
  3560.5     .06       0  3808.2     .12       0  4006.8     .06       0
  4602.6      .1       0  4986.7     .09       0  5018.3      .1       0
  5112.9     .06       0    5506      .1       0  5777.7     .06       0
    6243      .1       0  6632.6     .06       0  6808.3     .12       0
  7052.8     .06       0  7093.8     .12       0
Bank Sta=4986.7,5018.3
XS Rating Curve= 0 ,0
Exp/Cntr=0.3,0.1

Type RM Length L Ch R = 1 ,65399   ,499,499,499
BEGIN DESCRIPTION:
CANEY CREEK 96.0
END DESCRIPTION:
XS GIS Cut Line= 3
      3703940.67     10136493.92      3704045.36     10135057.33
      3703690.66     10133480.02
#Sta/Elev= 30
  3559.6  281.91  3727.5  277.01  3856.4  269.04  4005.5  260.57  4139.5  256.69
  4384.6  256.31  4685.4  249.16  4752.6     250  4946.1  251.52  4986.2  249.16
    5000  247.31  5011.5  249.62  5026.9  251.37  5059.9  247.88  5078.2  251.06
  5508.2  249.05  5518.9  250.66  5529.2  250.57  5549.3  245.55  5563.8  245.55
  5570.2  249.45  5590.7  251.82  5653.4  248.82  5831.7  252.34  6058.4  262.95
  6144.1  269.53  6174.9  267.92  6256.9  272.96  6461.9  279.53  6616.7  281.18
#Mann= 6 ,-1 , 0
  3559.6     .12       0  3856.4     .06       0  4752.6      .1       0
  4986.2     .09       0  5011.5      .1       0  6256.9     .12       0
Bank Sta=4986.2,5011.5
XS Rating Curve= 0 ,0
Exp/Cntr=0.3,0.1

Type RM Length L Ch R = 1 ,64900   ,541,541,541
BEGIN DESCRIPTION:
CANEY CREEK 95.0
END DESCRIPTION:
XS GIS Cut Line= 3
      3704010.12     10136445.31      3704461.89     10134796.89
      3704010.11     10133257.83
#Sta/Elev= 30
  3290.8  280.95  3388.5  278.06  3542.8  268.82    3741  260.14  4017.9  257.92
  4145.4  253.82  4450.5  250.07  4529.1  247.72  4539.4  250.21  4574.3  249.47
  4617.2  250.15    5000  247.18  5009.7  244.79  5023.2  244.79 5025.44247.2474
  5037.3  250.49  5058.2  250.78    5079  246.21  5104.1  250.68  5137.5  245.54
  5162.4  250.52  5183.2  251.12  5314.8  250.38  5353.4  247.41  5381.3  250.04
  5693.9   249.2  5880.2  252.29    6090  259.82  6404.5  278.52    6604   285.7
#Mann= 8 ,-1 , 0
  3290.8     .12       0  3542.8     .06       0  4450.5      .1       0
  4574.3     .06       0  4617.2      .1       0    5000     .09       0
 5025.44      .1       0  6404.5     .06       0
Bank Sta=5000,5025.44
XS Rating Curve= 0 ,0
Exp/Cntr=0.3,0.1

Type RM Length L Ch R = 1 ,64359   ,1532,1532,1532
BEGIN DESCRIPTION:
Mapping XS c25cc803
END DESCRIPTION:
XS GIS Cut Line= 3
      3704017.07     10136521.71      3705010.11     10134737.01
      3704059.28     10132994.98
#Sta/Elev= 30
  2764.7  280.67  2845.5  279.85  2882.5  276.97  3125.1  267.63  3294.2  262.16
  3589.4  256.49    4090  253.39  4333.2  255.53  4666.8  252.52  4813.6  250.21
  4961.9  249.37    4968  248.89  4983.1  242.74  4996.6  242.74  5005.9   245.3
  5011.6   249.3  5018.9     250  5061.1  249.07  5233.5  248.02  5253.4  248.06
    5638  248.44  5816.4  251.22  5871.1  253.66    5992  257.87  6095.5  263.68
  6146.8  268.64    6161  267.08  6263.3  273.75  6509.3  285.55  6791.7  295.74
#Mann= 13 ,-1 , 0
  2764.7     .12       0  3125.1     .06       0  4666.8     .12       0
  4813.6     .06       0  4961.9     .07       0  5011.6     .06       0
  5018.9     .12       0  5061.1     .06       0  5233.5      .1       0
  5253.4     .06       0    5638     .12       0  5871.1      .1       0
  6263.3     .06       0
Bank Sta=4961.9,5011.6
XS Rating Curve= 0 ,0
Exp/Cntr=0.3,0.1

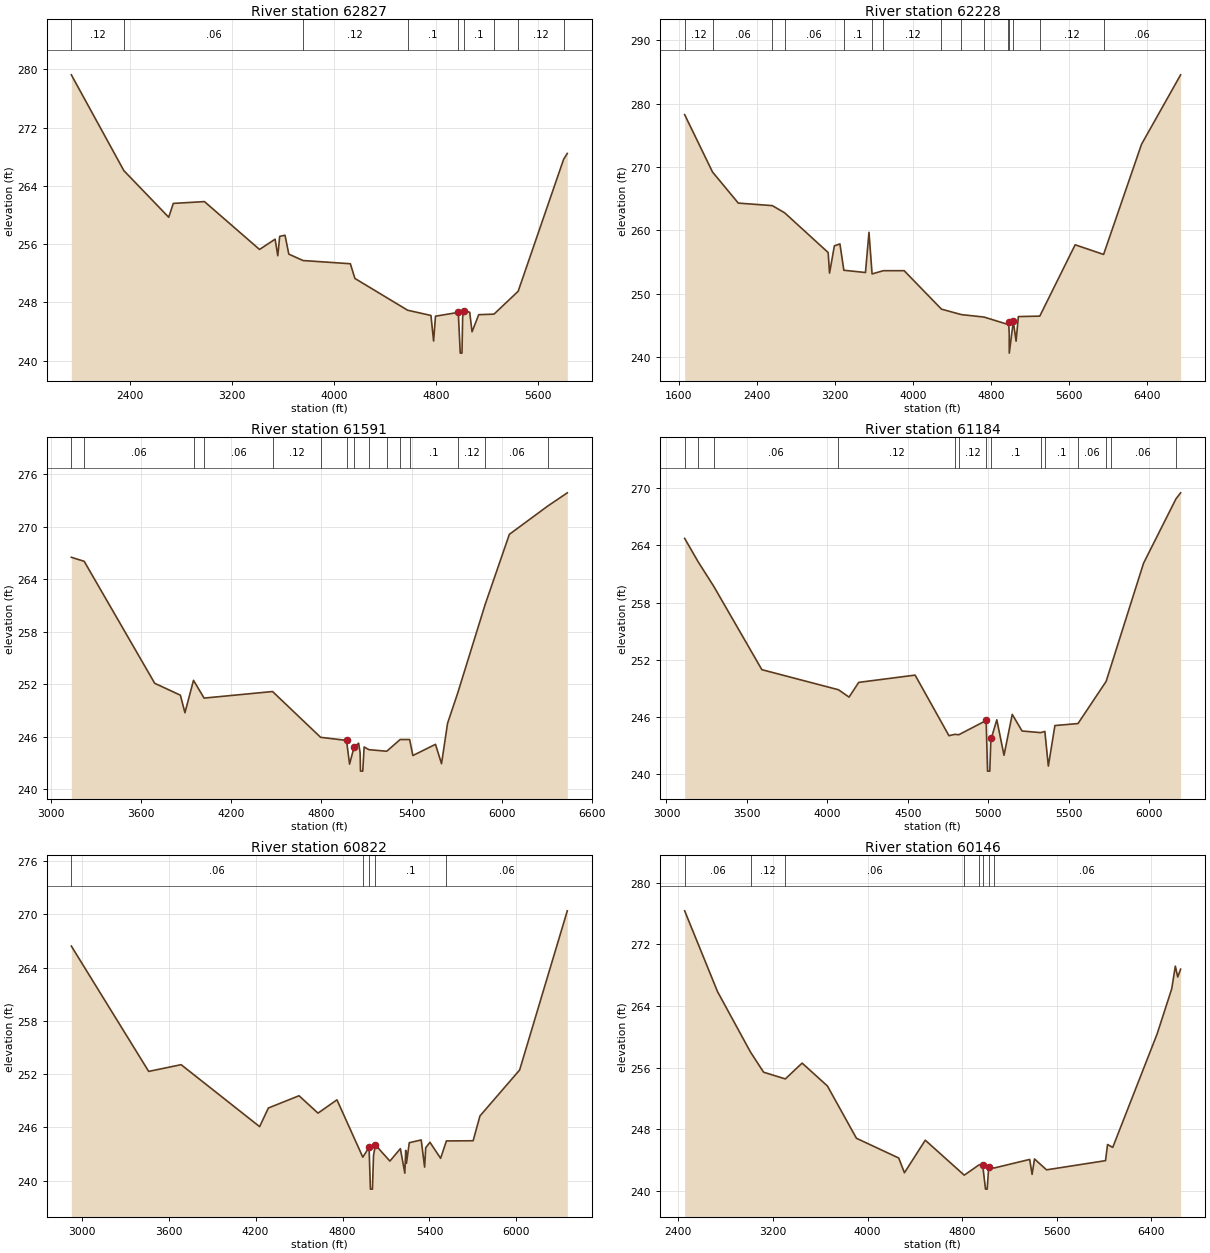
Type RM Length L Ch R = 1 ,62827   ,599,599,599
BEGIN DESCRIPTION:
CANEY CREEK 94.0
END DESCRIPTION:
XS GIS Cut Line= 3
      3704114.25     10136549.55      3705871.08     10134047.42
      3705617.86     10133261.09
#Sta/Elev= 30
  1942.7  279.24    2354  266.09  2705.2  259.69    2741  261.59    2985  261.84
  3416.3  255.27  3538.3  256.68  3559.3  254.41  3574.1  257.07  3615.9  257.22
  3645.5  254.63  3757.2  253.75  4127.4  253.31  4163.2  251.29  4575.8  246.93
  4758.4  246.21  4779.3   242.7  4794.1  246.11  4972.7  246.63  4987.9  241.04
  5001.5  241.04  5006.7  246.03  5017.2  246.86    5062  246.65  5080.2  243.97
  5132.7  246.32  5252.1  246.39  5441.4  249.53  5797.4  267.65  5826.1  268.45
#Mann= 9 ,-1 , 0
  1942.7     .12       0    2354     .06       0  3757.2     .12       0
  4575.8      .1       0  4972.7     .09       0  5017.2      .1       0
  5252.1     .06       0  5441.4     .12       0  5797.4     .06       0
Bank Sta=4972.7,5017.2
XS Rating Curve= 0 ,0
Exp/Cntr=0.3,0.1

Type RM Length L Ch R = 1 ,62228   ,637,637,637
BEGIN DESCRIPTION:
CANEY CREEK 93.0
END DESCRIPTION:
XS GIS Cut Line= 3
      3704232.32     10136612.02      3706435.57     10134101.65
      3705717.85     10132511.08
#Sta/Elev= 30
  1659.9  278.25  1945.5  269.21  2209.9  264.31  2558.8  263.91  2685.3  262.78
  3131.3  256.52  3145.5  253.28  3194.9  257.57  3251.8  257.88  3292.3  253.73
  3513.7  253.37  3549.8  259.71  3581.6  253.15  3697.3  253.66  3910.4  253.66
  4293.1   247.6  4497.5  246.74  4730.4  246.35  4974.1  245.19  4980.8  245.52
  4987.5  243.95  4988.2  240.67  5029.5  245.66  5058.1  242.55  5081.2  246.43
  5300.9   246.5  5663.7  257.74  5955.2  256.22  6344.2  273.58    6745  284.52
#Mann= 15 ,-1 , 0
  1659.9     .12       0  1945.5     .06       0  2558.8     .12       0
  2685.3     .06       0  3292.3      .1       0  3581.6     .06       0
  3697.3     .12       0  4293.1      .1       0  4497.5     .06       0
  4730.4      .1       0  4974.1     .07       0  4980.8     .09       0
  5029.5      .1       0  5300.9     .12       0  5955.2     .06       0
Bank Sta=4980.8,5029.5
XS Rating Curve= 0 ,0
Exp/Cntr=0.3,0.1

Type RM Length L Ch R = 1 ,61591   ,407,407,407
BEGIN DESCRIPTION:
CANEY CREEK 92.0
END DESCRIPTION:
XS GIS Cut Line= 3
      3707120.35     10136143.22      3706948.48     10134283.88
      3706849.52     10132856.78
#Sta/Elev= 30
  3137.6   266.5  3223.1  266.04  3692.1  252.11  3862.8  250.75    3893  248.75
  3949.9  252.45  4020.4  250.42  4475.6  251.17  4795.3  245.94  4967.5  245.59
  4987.6  242.88  5017.7  244.81  5047.8  245.27  5057.8  244.19  5060.3  242.08
  5075.3  242.08  5084.5  244.84  5116.4  244.53  5234.8  244.35    5324  245.69
    5387  245.69  5408.6  243.86    5559  245.14  5599.1  242.93  5639.2  247.54
  5706.6  250.99  5889.2  261.11  6050.2  269.12  6305.4  272.35  6435.4  273.86
#Mann= 15 ,-1 , 0
  3137.6     .12       0  3223.1     .06       0  3949.9     .12       0
  4020.4     .06       0  4475.6     .12       0  4795.3     .06       0
  4967.5     .07       0  5017.7      .1       0  5116.4     .12       0
  5234.8      .1       0    5324     .12       0    5387      .1       0
  5706.6     .12       0  5889.2     .06       0  6305.4     .12       0
Bank Sta=4967.5,5017.7
XS Rating Curve= 0 ,0
Exp/Cntr=0.3,0.1

Type RM Length L Ch R = 1 ,61184   ,362,362,362
BEGIN DESCRIPTION:
CANEY CREEK 91.0
END DESCRIPTION:
XS GIS Cut Line= 3
      3707234.94     10136101.57      3707343.81     10134217.71
      3707104.91      10133045.2
#Sta/Elev= 30
    3113  264.71  3196.3  262.28  3295.1  259.66    3593  250.97    4069  248.87
  4135.2   248.1  4195.3  249.64  4545.9   250.4  4756.2  244.06  4792.6   244.2
  4817.6  244.16  4987.6  245.65  4996.2  240.35  5010.2  240.35    5017  243.78
  5020.6  243.84  5053.8  245.72  5098.6  242.01  5149.7  246.29  5210.9  244.55
  5326.3  244.38  5352.5  244.51  5374.2  240.88    5415  245.12  5558.6  245.33
  5733.7  249.75  5760.9   251.2  5966.1  262.11  6167.7  268.85  6196.6  269.48
#Mann= 14 ,-1 , 0
    3113     .06       0  3196.3     .12       0  3295.1     .06       0
    4069     .12       0  4792.6     .06       0  4817.6     .12       0
  4987.6     .09       0  5020.6      .1       0  5326.3     .12       0
  5352.5      .1       0  5558.6     .06       0  5733.7      .1       0
  5760.9     .06       0  6167.7     .12       0
Bank Sta=4987.6,5020.6
XS Rating Curve= 0 ,0
Exp/Cntr=0.3,0.1

Type RM Length L Ch R = 1 ,60822   ,676,676,676
BEGIN DESCRIPTION:
CANEY CREEK 90.0
END DESCRIPTION:
XS GIS Cut Line= 3
      3707453.69     10136341.15      3707698.48     10134283.88
      3707380.77     10132971.37
#Sta/Elev= 30
  2928.7  266.43  3462.5  252.31  3686.2  253.07  4227.9  246.09  4288.3  248.19
  4499.8  249.57  4630.7  247.61  4761.6  249.11    4940  242.65  4983.2  243.76
  4992.4  239.05  5006.4  239.05  5013.7  242.83  5026.7  244.03  5126.8  242.21
  5199.2  243.61  5229.7  240.85  5235.9  243.42    5241  241.95  5260.6  244.28
  5342.9  244.59  5366.5  241.53  5373.8  243.71  5403.2  244.33  5476.7  242.52
  5516.9  244.48  5701.2   244.5  5748.1  247.29    6022  252.47  6350.9   270.4
#Mann= 5 ,-1 , 0
  2928.7     .06       0    4940      .1       0  4983.2     .09       0
  5026.7      .1       0  5516.9     .06       0
Bank Sta=4983.2,5026.7
XS Rating Curve= 0 ,0
Exp/Cntr=0.3,0.1

Type RM Length L Ch R = 1 ,60146   ,470,470,470
BEGIN DESCRIPTION:
CANEY CREEK 89.0
END DESCRIPTION:
XS GIS Cut Line= 3
      3707417.84     10136661.09      3708198.62     10134236.61
      3707885.98     10132617.22
#Sta/Elev= 30
  2452.9  276.33  2730.8  265.87  3010.4  258.02  3120.9  255.42  3304.6  254.55
  3446.8   256.6  3661.1  253.63  3906.3  246.86  4264.3   244.3  4312.4  242.39
  4488.8  246.61  4818.4  242.08  4945.3  243.43  4974.3  243.41  4998.6  240.27
  5012.6  240.27  5025.7  243.17  5069.9     243  5372.3  244.12  5392.7  242.18
    5413  244.18  5514.9  242.77  6013.9  243.96    6031  246.05    6075  245.68
  6450.8  260.39  6574.1  266.23  6604.6  269.16    6625  267.75  6649.3  268.77
#Mann= 8 ,-1 , 0
  2452.9     .06       0  3010.4     .12       0  3304.6     .06       0
  4818.4      .1       0  4945.3     .12       0  4974.3     .09       0
  5025.7     .12       0  5069.9     .06       0
Bank Sta=4974.3,5025.7
XS Rating Curve= 0 ,0
Exp/Cntr=0.3,0.1

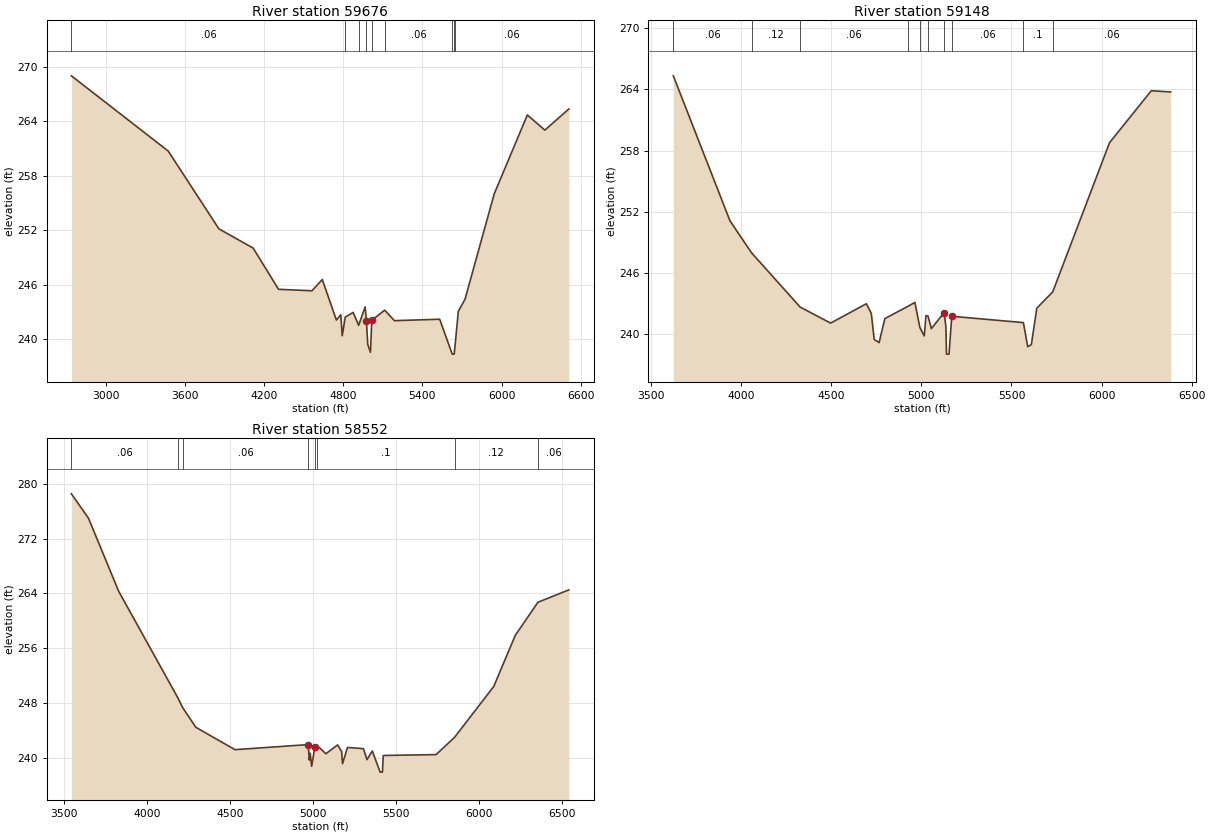
Type RM Length L Ch R = 1 ,59676   ,528,528,528
BEGIN DESCRIPTION:
CANEY CREEK 88.0
END DESCRIPTION:
XS GIS Cut Line= 3
      3709130.76      10136507.8      3708547.44     10134445.34
       3708776.6     10132830.79
#Sta/Elev= 30
  2736.8  269.02  3471.3  260.72  3855.8  252.14  4115.6  250.02  4308.5  245.47
  4561.8  245.31  4640.1  246.55  4747.2  242.08  4780.7  242.66  4791.5  240.35
  4814.6  242.41  4874.2  242.92  4916.2   241.5  4965.3  243.54  4975.4  241.95
  4985.1  239.39  5005.7  238.53  5015.8  242.05  5113.7  243.17  5187.5  242.01
  5530.9  242.17  5626.1  238.32  5641.1  238.32  5648.1  239.35  5672.3  243.04
  5722.8  244.36    5945  256.01    6196   264.7  6328.8  263.03  6510.9  265.36
#Mann= 9 ,-1 , 0
  2736.8     .06       0  4814.6     .12       0  4916.2      .1       0
  4975.4     .09       0  5015.8      .1       0  5113.7     .06       0
  5626.1     .07       0  5641.1     .06       0  5648.1     .06       0
Bank Sta=4975.4,5015.8
XS Rating Curve= 0 ,0
Exp/Cntr=0.3,0.1

Type RM Length L Ch R = 1 ,59148   ,596,596,596
BEGIN DESCRIPTION:
CANEY CREEK 87.0
END DESCRIPTION:
XS GIS Cut Line= 3
      3709717.84     10135561.05      3709034.35     10134366.46
      3708854.98     10132994.13
#Sta/Elev= 30
  3623.7  265.32  3938.1  251.11  4057.9  247.97  4327.7  242.65  4496.6  241.08
  4695.1  242.98  4722.5  242.02  4738.4  239.48  4765.7  239.17  4797.4  241.52
  4927.1  242.74  4964.3  243.11    4992  240.64  5016.1  239.83  5025.6  241.81
  5036.9  241.78  5055.9  240.54  5126.5  242.12  5136.5  240.67  5139.6  238.04
  5153.6  238.04  5168.9  241.75  5566.2  241.13  5590.4  238.77  5610.5  238.98
  5640.8  242.55  5729.2  244.14  6044.2  258.76  6276.1  263.86    6384  263.74
#Mann= 10 ,-1 , 0
  3623.7     .06       0  4057.9     .12       0  4327.7     .06       0
  4927.1      .1       0    4992     .12       0  5036.9      .1       0
  5126.5     .09       0  5168.9     .06       0  5566.2      .1       0
  5729.2     .06       0
Bank Sta=5126.5,5168.9
XS Rating Curve= 0 ,0
Exp/Cntr=0.3,0.1

Type RM Length L Ch R = 1 ,58552   ,750,750,750
BEGIN DESCRIPTION:
CANEY CREEK 86.0
END DESCRIPTION:
XS GIS Cut Line= 3
      3709867.85     10135761.06       3709538.5     10134344.75
      3708967.84     10132911.04
#Sta/Elev= 30
  3545.9  278.55  3648.6     275  3830.5  264.33  4186.5   248.8  4217.4   247.3
  4295.4  244.47  4531.5   241.2    4973  241.94  4979.4  239.68  4984.6  240.66
  4993.5  238.77  5012.3  241.52  5024.1  241.85  5079.3  240.61  5149.9  241.89
  5174.1  240.94  5179.5  239.15  5209.2  241.52  5305.3  241.35  5326.8  239.74
  5359.1     241    5406  237.92    5420  237.92    5425  240.35  5743.3  240.48
  5854.5     243    6091  250.44  6220.2  257.88    6357  262.72  6543.1  264.53
#Mann= 8 ,-1 , 0
  3545.9     .06       0  4186.5     .12       0  4217.4     .06       0
    4973     .42       0  5012.3      .5       0  5024.1      .1       0
  5854.5     .12       0    6357     .06       0
Bank Sta=4973,5012.3
XS Rating Curve= 0 ,0
Exp/Cntr=0.3,0.1