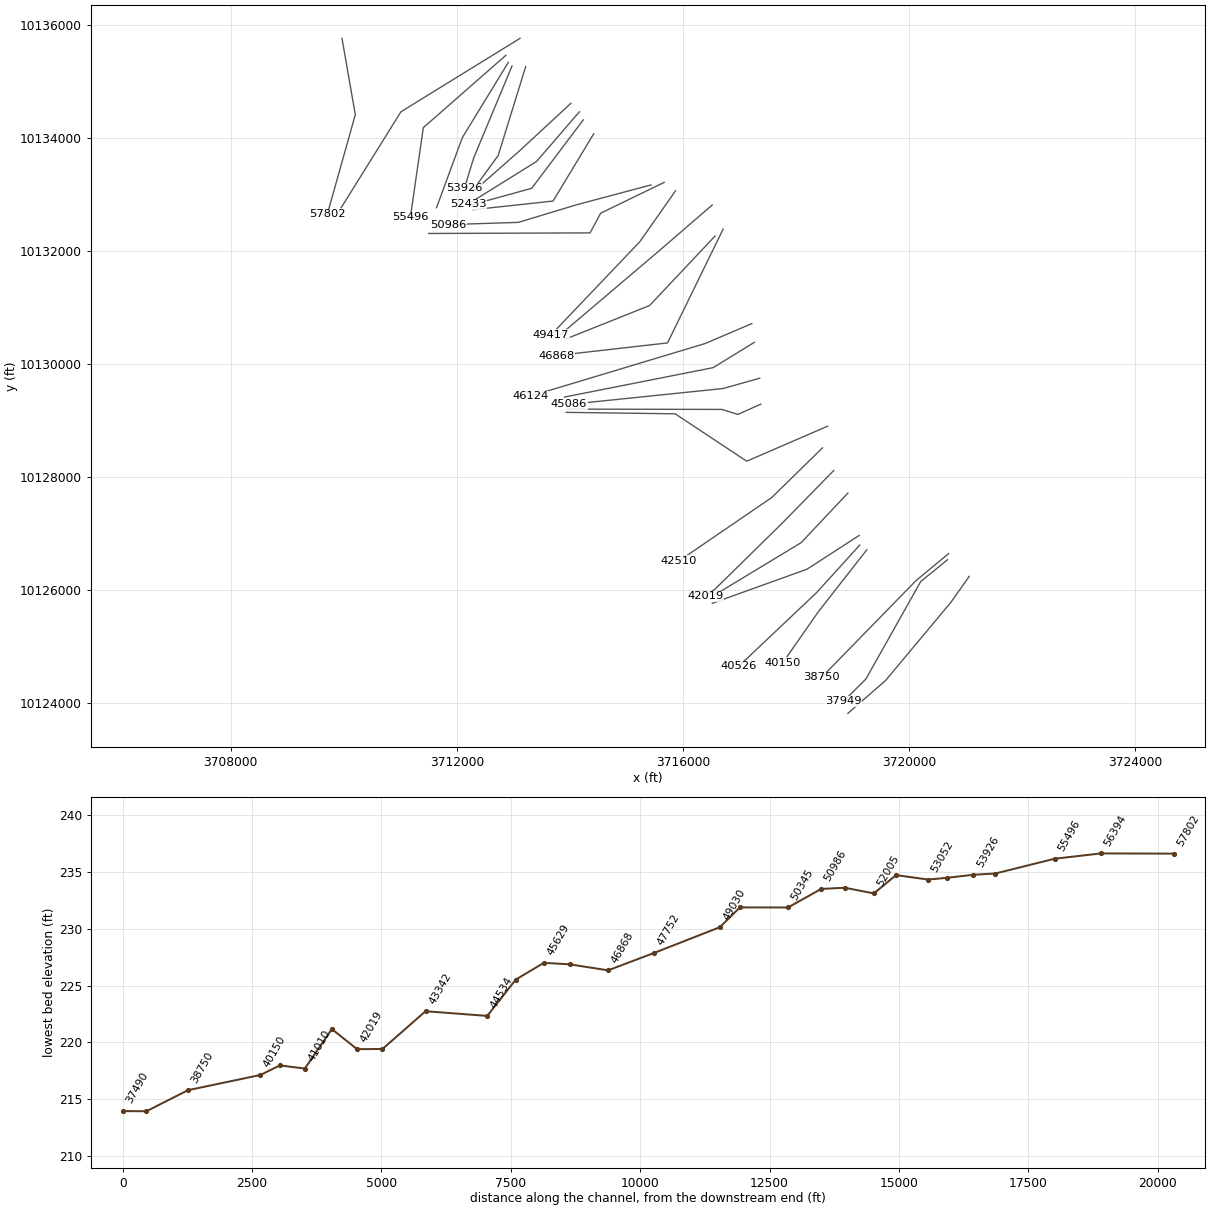
HEC-RAS study CANEY CREEK.prj: CANEY CREEK Base Level Engineering

--- CANEY CREEK.g01 (geometry) --- (continued)

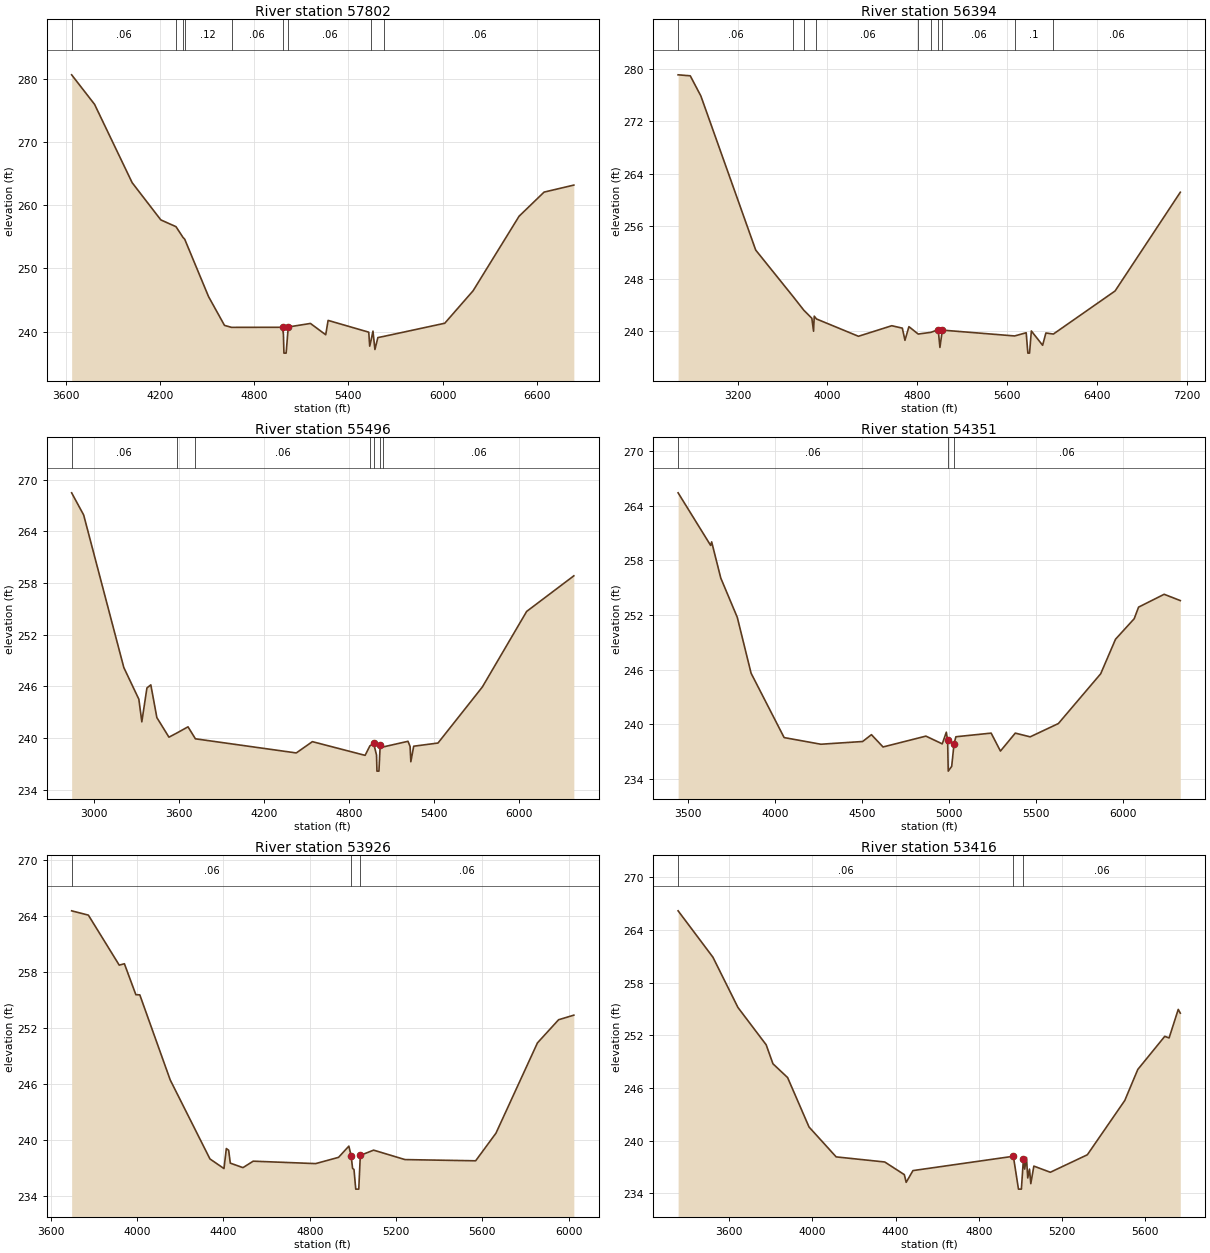
Type RM Length L Ch R = 1 ,57802   ,1408,1408,1408
BEGIN DESCRIPTION:
CANEY CREEK 85.0
END DESCRIPTION:
XS GIS Cut Line= 3
      3709967.86     10135761.02      3710203.69     10134408.88
      3709708.89     10132648.45
#Sta/Elev= 30
  3635.8  280.59  3782.1  275.92  4021.5  263.55  4204.2  257.67  4300.9   256.6
  4346.3  254.88  4356.5  254.62  4508.7  245.54  4610.2     241    4655  240.69
 4980.13 240.704  4985.8  239.57    4989  236.62    5003  236.62  5016.6  240.75
    5158  241.31  5255.4  239.52  5270.6  241.79  5529.7  239.93  5535.8  237.72
  5545.2  238.73  5556.6   240.1    5569  237.19  5587.8  239.08  5624.8  239.26
  6014.1  241.34  6194.8  246.47    6488  258.25  6647.3  262.06    6837  263.17
#Mann= 9 ,-1 , 0
  3635.8     .06       0  4300.9     .12       0  4346.3     .06       0
  4356.5     .12       0    4655     .06       0 4980.13     .06       0
  5016.6     .06       0  5545.2      .1       0  5624.8     .06       0
Bank Sta=4980.13,5016.6
XS Rating Curve= 0 ,0
Exp/Cntr=0.3,0.1

Type RM Length L Ch R = 1 ,56394   ,898,898,898
BEGIN DESCRIPTION:
CANEY CREEK 84.0
END DESCRIPTION:
XS GIS Cut Line= 3
      3713117.87     10135761.08      3711010.98     10134460.97
      3709954.61     10132764.52
#Sta/Elev= 30
  2670.2  279.09  2778.4  278.94    2873  275.86  3361.5  252.36  3694.6  245.27
  3789.9  243.19  3861.6  241.96    3877  239.98  3882.9  242.28  3903.1  241.85
  4276.7  239.21  4573.8  240.82  4667.8  240.45  4691.3   238.6  4726.6  240.68
  4809.1  239.55  4922.3  239.81  4987.4  240.22  5002.8  237.51  5024.1  240.15
  5668.5  239.26  5771.4  239.75  5786.2  236.64  5801.2  236.64  5817.3  240.02
  5917.7  237.84  5946.9  239.71  6013.5  239.55  6563.3  246.12  7144.4  261.18
#Mann= 10 ,-1 , 0
  2670.2     .06       0  3694.6     .12       0  3789.9      .1       0
  3903.1     .06       0  4809.1     .12       0  4922.3      .1       0
  4987.4     .09       0  5024.1     .06       0  5668.5      .1       0
  6013.5     .06       0
Bank Sta=4987.4,5024.1
XS Rating Curve= 0 ,0
Exp/Cntr=0.3,0.1

Type RM Length L Ch R = 1 ,55496   ,1145,1145,1145
BEGIN DESCRIPTION:
CANEY CREEK 83.0
END DESCRIPTION:
XS GIS Cut Line= 3
      3712867.83     10135461.05      3711406.81     10134179.72
      3711177.64     10132591.15
#Sta/Elev= 30
  2841.8  268.46  2926.7  265.89  3210.4  248.19  3316.7  244.51  3337.6  241.89
  3373.7  245.82  3401.2  246.18  3443.9  242.38  3529.3  240.11  3583.7  240.58
    3664  241.31  3716.2  239.92  4428.9  238.28  4542.8  239.59  4915.1     238
  4949.5  239.11  4975.7  239.38  4995.9  238.04    4999  236.17    5013  236.17
    5022  239.23  5043.9  238.98  5218.2  239.63  5233.2  239.03  5238.4  237.26
  5258.6  239.06  5430.3  239.43  5743.6  245.93  6056.8   254.7  6390.1  258.83
#Mann= 7 ,-1 , 0
  2841.8     .06       0  3583.7      .1       0  3716.2     .06       0
  4949.5      .1       0  4975.7     .09       0    5022      .1       0
  5043.9     .06       0
Bank Sta=4975.7,5022
XS Rating Curve= 0 ,0
Exp/Cntr=0.3,0.1

Type RM Length L Ch R = 1 ,54351   ,425,425,425
BEGIN DESCRIPTION:
CANEY CREEK 82.0
END DESCRIPTION:
XS GIS Cut Line= 3
      3712910.45     10135335.09      3712097.96     10134005.24
      3711639.62     10132762.16
#Sta/Elev= 30
    3445   265.4  3631.8  259.63  3637.6  260.02  3689.8  256.06  3784.7  251.74
    3864  245.61  4053.7  238.55  4264.7  237.82  4504.4  238.12    4555  238.87
  4621.6  237.52  4867.7  238.71  4961.5  237.86  4984.9  239.14  4992.4  238.23
  4995.9  234.87  5015.7  235.39  5029.2  237.86  5039.8  238.64  5242.3  239.04
  5295.6  237.07  5380.9  239.04  5466.2  238.63  5628.3  240.09  5871.2  245.55
  5956.4  249.34  6063.6  251.59  6088.7  252.86  6235.6  254.27  6328.3  253.58
#Mann= 3 , 0 , 0
    3445     .06       0  4992.4     .06       0  5029.2     .06       0
Bank Sta=4992.4,5029.2
XS Rating Curve= 0 ,0
Exp/Cntr=0.3,0.1

Type RM Length L Ch R = 1 ,53926   ,510,510,510
BEGIN DESCRIPTION:
Mapping XS 1001bdd9
END DESCRIPTION:
XS GIS Cut Line= 3
      3712976.44     10135272.62      3712299.35      10133647.6
      3712132.79     10133106.29
#Sta/Elev= 30
    3697  264.53  3774.5  264.07  3917.5  258.72  3941.4  258.87  3994.5  255.56
  4012.8  255.54  4153.7  246.44  4337.8  237.99  4402.8  236.96  4413.7   239.1
  4424.5  238.92  4432.1  237.54  4490.6  237.06  4538.3  237.75  4827.5  237.49
  4933.7  238.16  4981.4  239.36 4991.92238.3298  4998.7  236.98  5005.2  236.86
  5013.3  234.76  5027.3  234.76  5034.5  238.37  5096.2  238.93  5241.4  237.92
  5568.9  237.79  5663.1  240.75  5855.1   250.4  5953.2  252.88  6023.8  253.37
#Mann= 3 , 0 , 0
    3697     .06       0 4991.92     .06       0  5034.5     .06       0
Bank Sta=4991.92,5034.5
XS Rating Curve= 0 ,0
Exp/Cntr=0.3,0.1

Type RM Length L Ch R = 1 ,53416   ,364,364,364
BEGIN DESCRIPTION:
CANEY CREEK 81.0
END DESCRIPTION:
XS GIS Cut Line= 3
      3713217.85     10135261.07      3712731.91     10133688.12
      3712279.17     10133065.16
#Sta/Elev= 30
  3353.7  266.17  3521.2  260.89  3641.6  255.17  3777.4  250.92    3810  248.76
  3880.5  247.19  3983.7  241.56  4114.2  238.16  4347.9  237.58  4442.2  236.14
  4451.1  235.26  4483.7   236.6  4966.8  238.23  4991.4  234.49  5005.4  234.49
  5015.2  237.92  5021.3  236.77  5029.8  238.09    5036  235.76  5044.5  236.77
  5050.7  235.11  5065.4  237.11  5144.7  236.41  5322.8   238.4  5502.9  244.58
  5565.5  248.11  5695.3  251.88  5716.2   251.7  5760.2  254.95  5770.1  254.52
#Mann= 3 , 0 , 0
  3353.7     .06       0  4966.8     .06       0  5015.2     .06       0
Bank Sta=4966.8,5015.2
XS Rating Curve= 0 ,0
Exp/Cntr=0.3,0.1

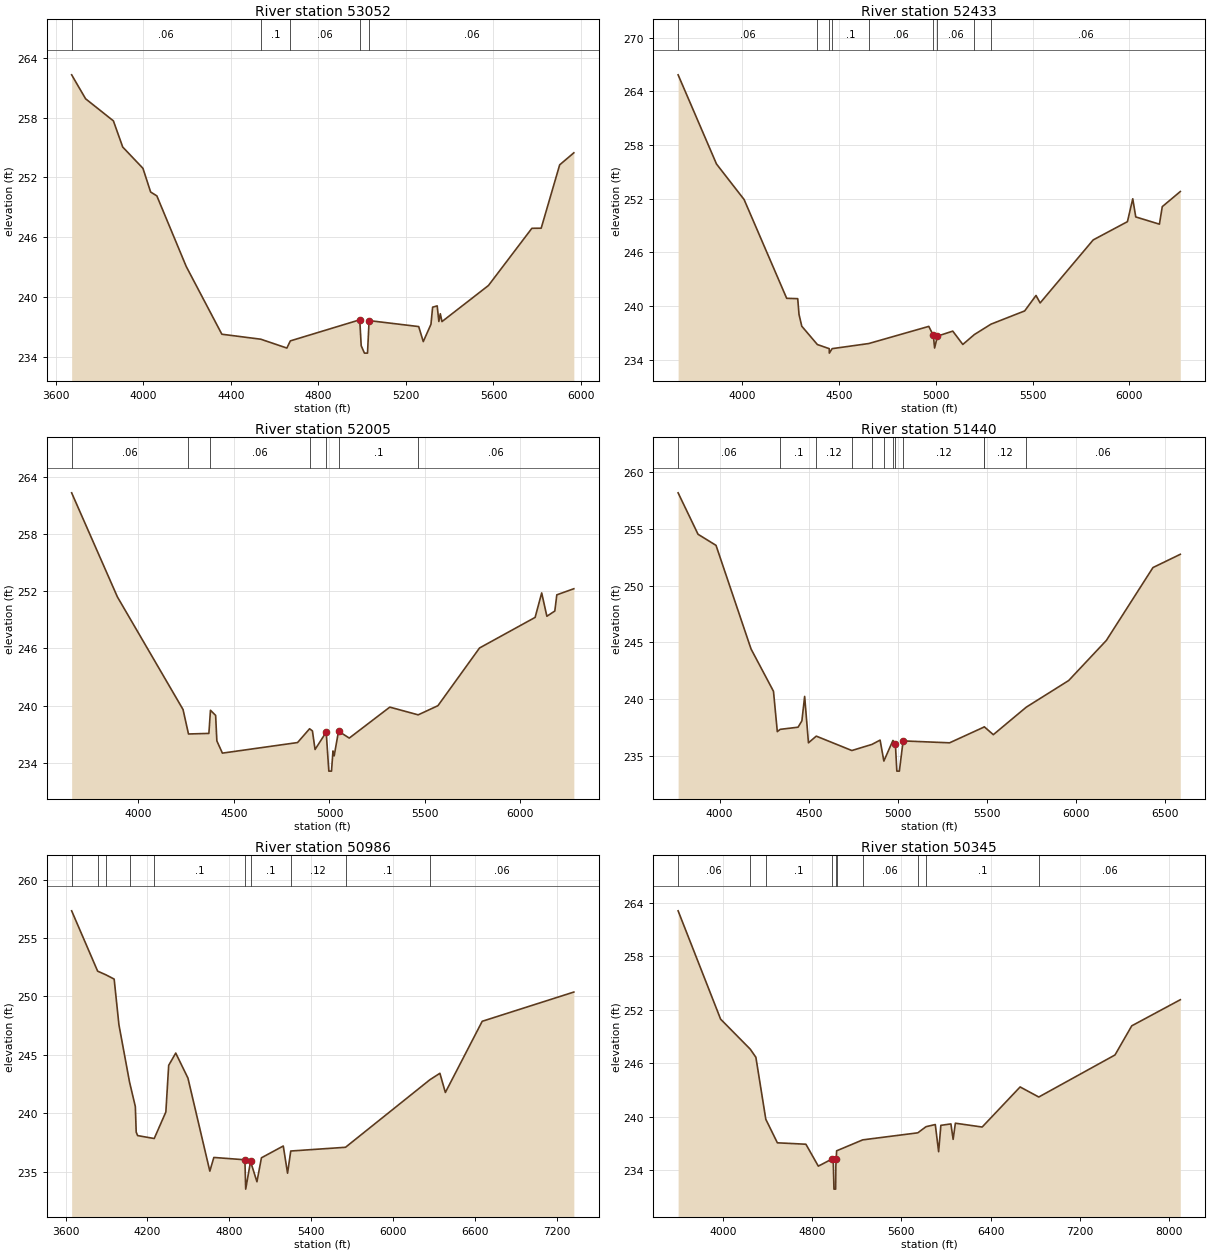
Type RM Length L Ch R = 1 ,53052   ,619,619,619
BEGIN DESCRIPTION:
CANEY CREEK 80.0
END DESCRIPTION:
XS GIS Cut Line= 3
      3714017.88      10134611.1      3713108.38     10133769.13
      3712316.69      10133071.2
#Sta/Elev= 30
  3672.5  262.32  3736.3  259.91  3863.3  257.69  3905.9  255.06  3998.3  252.92
  4033.4  250.54  4061.8  250.15  4196.1  243.05  4358.9  236.24  4536.7  235.74
    4656  234.85  4671.8  235.57    4989  237.69  4995.7  235.08  5010.5  234.34
  5024.5  234.34  5031.7  237.61  5258.4  237.01  5279.3   235.5  5314.4  237.24
    5322  238.96  5342.9  239.09  5350.5  237.52  5357.1   238.3  5364.7  237.51
  5577.2  241.14  5775.5  246.89  5818.1   246.9  5902.6  253.27  5967.3  254.48
#Mann= 5 ,-1 , 0
  3672.5     .06       0  4536.7      .1       0  4671.8     .06       0
    4989     .06       0  5031.7     .06       0
Bank Sta=4989,5031.7
XS Rating Curve= 0 ,0
Exp/Cntr=0.3,0.1

Type RM Length L Ch R = 1 ,52433   ,428,428,428
BEGIN DESCRIPTION:
CANEY CREEK 79.0
END DESCRIPTION:
XS GIS Cut Line= 3
      3714167.83     10134461.05      3713410.46     10133581.63
      3712196.32     10132825.39
#Sta/Elev= 30
  3671.4  265.85  3869.4  255.88    4012   251.9  4231.5  240.86  4288.5  240.82
  4295.1  239.07  4309.4  237.74  4389.9  235.69  4451.1  235.23  4451.6  234.73
  4466.1  235.23  4654.5   235.8  4964.7  237.72  4988.1  236.72 4994.74   235.3
  5009.3  236.63  5088.4  237.19  5140.3   235.7  5199.4   236.8  5285.7  237.97
  5459.5  239.45    5518  241.18  5539.2  240.34    5813  247.39  5989.6  249.43
  6017.1  251.99  6032.5  249.96  6154.6  249.15  6169.4  251.11  6262.4   252.8
#Mann= 9 ,-1 , 0
  3671.4     .06       0  4389.9      .1       0  4451.1     .06       0
  4466.1      .1       0  4654.5     .06       0  4988.1     .07       0
  5009.3     .06       0  5199.4      .1       0  5285.7     .06       0
Bank Sta=4988.1,5009.3
XS Rating Curve= 0 ,0
Exp/Cntr=0.3,0.1

Type RM Length L Ch R = 1 ,52005   ,565,565,565
BEGIN DESCRIPTION:
CANEY CREEK 78.0
END DESCRIPTION:
XS GIS Cut Line= 3
      3714236.83     10134317.71      3713323.65     10133105.93
       3712251.8     10132811.09
#Sta/Elev= 30
  3650.4  262.34    3890  251.41  4233.5  239.59  4262.1  237.02  4368.8  237.08
  4377.2  239.51  4404.2  238.97  4410.5   236.3  4439.6  235.01  4833.1  236.12
  4896.1  237.57  4910.9  237.34  4924.7  235.39    4983  237.22  4996.8  233.12
  5010.8  233.12  5018.4  235.24  5024.7  234.72  5047.5  237.31  5103.8  236.59
  5315.9  239.84  5464.5  239.03  5567.9  239.99  5785.7  246.05  6076.7  249.26
  6111.1  251.83  6138.3  249.38  6179.8  249.93  6190.3  251.63  6279.4  252.27
#Mann= 7 ,-1 , 0
  3650.4     .06       0  4262.1      .1       0  4377.2     .06       0
  4896.1      .1       0    4983     .09       0  5047.5      .1       0
  5464.5     .06       0
Bank Sta=4983,5047.5
XS Rating Curve= 0 ,0
Exp/Cntr=0.3,0.1

Type RM Length L Ch R = 1 ,51440   ,454,454,454
BEGIN DESCRIPTION:
CANEY CREEK 77.0
END DESCRIPTION:
XS GIS Cut Line= 3
      3714420.87      10134071.2      3713702.13     10132880.24
      3712285.48     10132727.46
#Sta/Elev= 30
  3767.5   258.2  3879.2  254.54  3980.1  253.56  4176.4  244.41  4302.3  240.67
  4323.7  237.11  4340.1  237.31  4440.1   237.5  4461.5  238.06    4477  240.22
  4498.4  236.12  4542.2  236.71  4741.7  235.44  4854.4  235.98  4900.1  236.36
  4921.2  234.51    4972  236.33  4985.6  236.06    4994  233.62  5008.1  233.62
  5029.1  236.29  5289.6  236.12  5482.5  237.51  5483.9  237.54    5535  236.84
  5719.7  239.27  5957.4  241.62  6168.6  245.16  6430.1   251.6  6583.4  252.77
#Mann= 12 ,-1 , 0
  3767.5     .06       0  4340.1      .1       0  4542.2     .12       0
  4741.7      .1       0  4854.4     .12       0  4921.2      .1       0
    4972     .12       0  4985.6     .09       0  5029.1     .12       0
  5482.5      .1       0  5483.9     .12       0  5719.7     .06       0
Bank Sta=4985.6,5029.1
XS Rating Curve= 0 ,0
Exp/Cntr=0.3,0.1

Type RM Length L Ch R = 1 ,50986   ,641,641,641
BEGIN DESCRIPTION:
CANEY CREEK 76.0
END DESCRIPTION:
XS GIS Cut Line= 4
      3715435.13     10133166.02      3714124.87     10132816.79
       3713088.1     10132503.27      3711846.59     10132462.89
#Sta/Elev= 30
    3644  257.32  3834.5  252.16    3896  251.84  3955.6  251.48  3990.6  247.57
  4068.2  242.68  4110.9  240.57  4117.2  238.39  4127.6  238.09  4249.3  237.84
  4334.6  240.11  4355.3   244.1    4407  245.15  4496.5  243.01  4656.9  235.05
  4686.4  236.22  4914.1  236.02  4919.8  233.51  4955.5  235.88  5002.3  234.14
  5035.2  236.19  5195.4   237.2  5226.7  234.87  5250.1  236.77  5651.6  237.09
  6270.2  242.87  6343.5  243.42  6383.5  241.78  6653.7  247.87  7325.3  250.37
#Mann= 10 ,-1 , 0
    3644     .06       0  3834.5     .12       0    3896     .06       0
  4068.2     .12       0  4249.3      .1       0  4914.1     .09       0
  4955.5      .1       0  5250.1     .12       0  5651.6      .1       0
  6270.2     .06       0
Bank Sta=4914.1,4955.5
XS Rating Curve= 0 ,0
Exp/Cntr=0.3,0.1

Type RM Length L Ch R = 1 ,50345   ,928,928,928
BEGIN DESCRIPTION:
CANEY CREEK 75.0
END DESCRIPTION:
XS GIS Cut Line= 4
      3715667.89     10133211.09      3714544.47     10132666.01
      3714356.97     10132317.05       3711502.8     10132306.63
#Sta/Elev= 30
  3600.2  263.12    3981  250.96  4246.5  247.59  4296.9  246.68  4385.9  239.72
  4489.4  237.08  4745.1  236.92  4856.2  234.46    4982  235.28  4990.7  234.74
  4996.4  231.88  5011.5  231.88  5013.4  234.47 5016.66235.2898  5020.2  236.18
  5254.2  237.41  5747.5   238.2  5821.4  238.89  5904.1  239.13  5934.1  236.08
  5954.1  239.04  6044.1   239.2  6064.1  237.47  6084.1  239.28  6324.1  238.85
  6664.1  243.35  6831.4  242.22  7514.1  246.94  7664.1  250.21  8099.2  253.14
#Mann= 10 ,-1 , 0
  3600.2     .06       0  4246.5     .12       0  4385.9      .1       0
    4982     .09       0 5016.66     .07       0  5020.2      .1       0
  5254.2     .06       0  5747.5     .12       0  5821.4      .1       0
  6831.4     .06       0
Bank Sta=4982,5016.66
XS Rating Curve= 0 ,0
Exp/Cntr=0.3,0.1

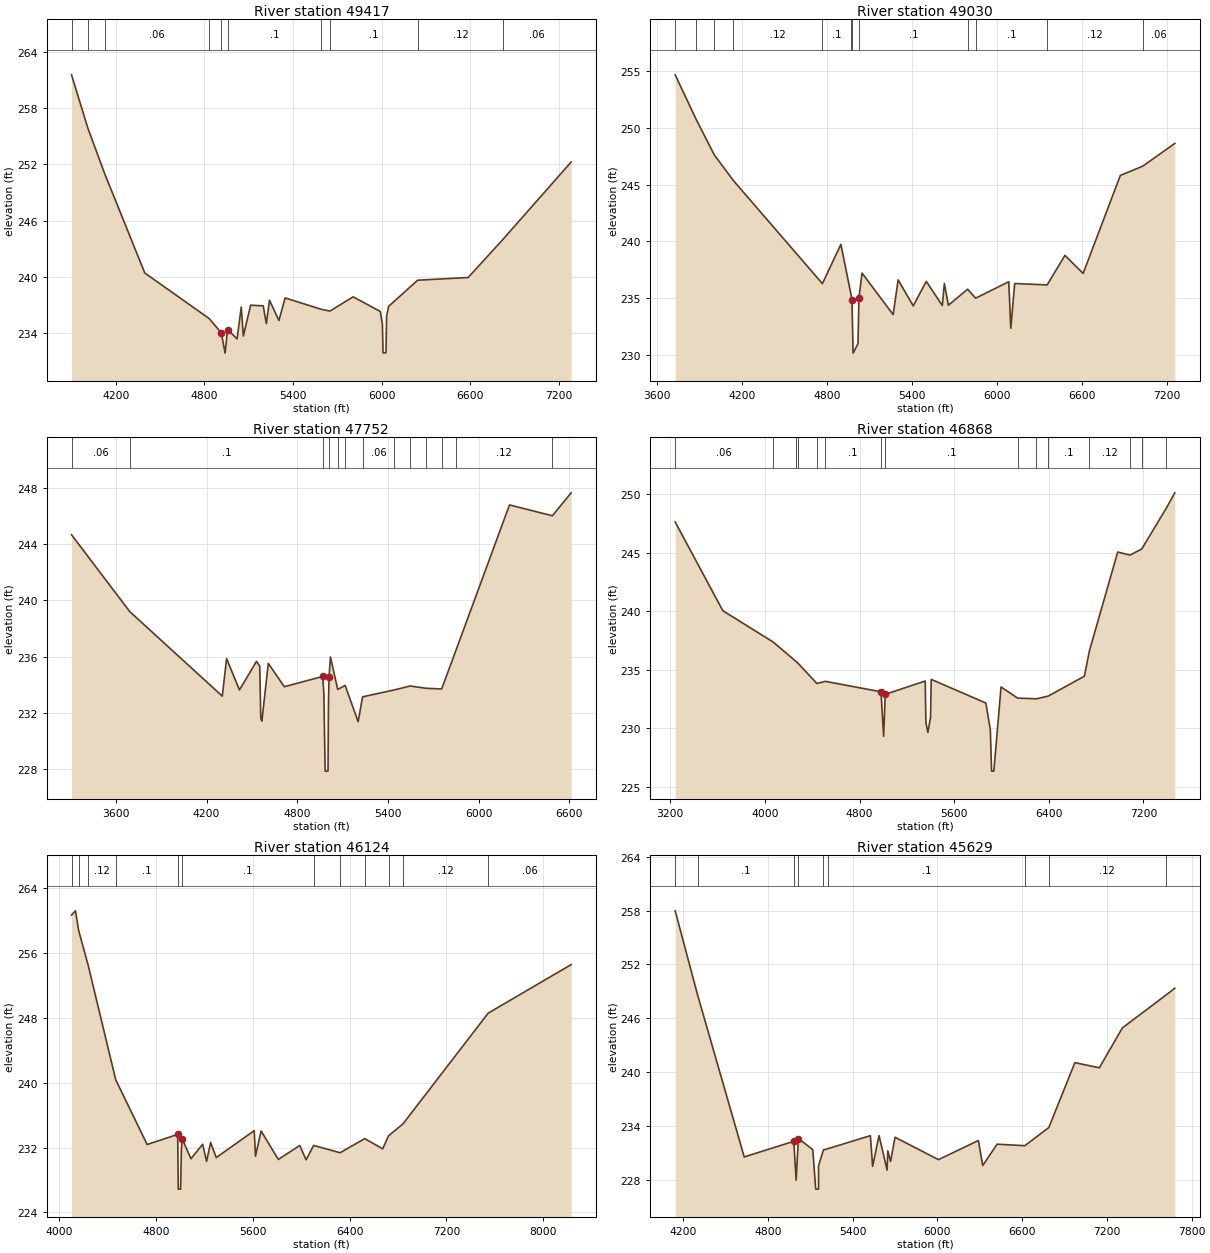
Type RM Length L Ch R = 1 ,49417   ,387,387,387
BEGIN DESCRIPTION:
CANEY CREEK 73.0
END DESCRIPTION:
XS GIS Cut Line= 3
      3715867.88     10133061.11      3715237.32     10132161.36
      3713664.23     10130509.73
#Sta/Elev= 30
  3901.3  261.55    4012  255.86  4125.7  251.01  4396.9  240.43    4833  235.57
  4914.7  234.04 4940.15  231.89  4956.5  234.39    5021  233.41  5049.4   236.8
  5063.5  233.71  5112.9     237  5197.8  236.93  5219.2  235.03  5240.3  237.53
  5304.1  235.37  5346.3  237.77  5589.5  236.57    5649  236.37  5806.1  237.89
  5990.1  236.33  6004.3  234.95  6008.4  231.92  6028.4  231.92  6032.6  235.84
  6046.7  236.88  6242.6  239.66  6584.3  239.95  6821.2  244.04  7280.9  252.26
#Mann= 10 ,-1 , 0
  3901.3     .06       0    4012     .12       0  4125.7     .06       0
    4833      .1       0  4914.7     .09       0  4956.5      .1       0
  5589.5     .06       0    5649      .1       0  6242.6     .12       0
  6821.2     .06       0
Bank Sta=4914.7,4956.5
XS Rating Curve= 0 ,0
Exp/Cntr=0.3,0.1

Type RM Length L Ch R = 1 ,49030   ,1278,1278,1278
BEGIN DESCRIPTION:
CANEY CREEK 72.0
END DESCRIPTION:
XS GIS Cut Line= 3
      3716517.85     10132811.07       3715560.1     10131983.72
      3713836.17      10130520.2
#Sta/Elev= 30
  3728.4  254.66  3877.9   250.7  4004.1  247.62  4137.8  245.37  4767.6  236.27
  4898.3  239.73  4969.5  235.32  4976.1  234.85  4984.5  230.15    5019  230.98
  5025.5  234.97  5047.5   237.2  5267.2  233.54  5302.3   236.6  5408.9  234.31
  5501.1  236.47  5614.3  234.34  5628.5  236.28  5657.1  234.37  5792.8  235.78
  5849.5  234.99  6083.3  236.44  6097.6  232.34  6125.1  236.28  6354.4  236.16
  6479.8  238.76  6608.3  237.17  6870.9   245.8  7029.5  246.62  7255.4  248.62
#Mann= 12 ,-1 , 0
  3728.4      .1       0  3877.9     .06       0  4004.1      .1       0
  4137.8     .12       0  4767.6      .1       0  4969.5     .07       0
  4976.1     .09       0  5025.5      .1       0  5792.8     .06       0
  5849.5      .1       0  6354.4     .12       0  7029.5     .06       0
Bank Sta=4976.1,5025.5
XS Rating Curve= 0 ,0
Exp/Cntr=0.3,0.1

Type RM Length L Ch R = 1 ,47752   ,884,884,884
BEGIN DESCRIPTION:
CANEY CREEK 71.0
END DESCRIPTION:
XS GIS Cut Line= 3
      3716567.84     10132261.06      3715409.05     10131030.59
      3713909.03     10130431.62
#Sta/Elev= 30
  3306.6  244.67  3691.7  239.21  4304.1   233.2  4332.4  235.87  4417.4  233.64
  4530.3  235.67  4551.7  235.33  4558.6  231.65  4565.9  231.42  4608.4  235.53
  4714.3  233.87  4968.8   234.6  4976.1  233.34  4984.5  227.87  5003.5  227.87
  5006.2  232.49 5010.07234.5538  5019.6  235.98  5067.6  233.68  5116.8  233.96
  5202.9  231.38  5232.2  233.15  5441.5  233.64  5546.1  233.92  5650.8  233.76
  5755.4  233.71  5850.7  236.48  6204.1  246.79  6487.8  246.02    6612  247.65
#Mann= 13 ,-1 , 0
  3306.6     .06       0  3691.7      .1       0  4968.8     .09       0
 5010.07      .1       0  5067.6     .06       0  5116.8      .1       0
  5232.2     .06       0  5441.5      .1       0  5546.1     .06       0
  5650.8     .12       0  5755.4      .1       0  5850.7     .12       0
  6487.8     .06       0
Bank Sta=4968.8,5010.07
XS Rating Curve= 0 ,0
Exp/Cntr=0.3,0.1

Type RM Length L Ch R = 1 ,46868   ,744,744,744
BEGIN DESCRIPTION:
Mapping XS ddf8b5b5
END DESCRIPTION:
XS GIS Cut Line= 3
      3716711.15     10132384.78      3715726.76     10130369.13
      3713758.03     10130145.18
#Sta/Elev= 30
  3240.9  247.64  3643.6  240.06  4069.5  237.38  4265.5   235.7  4277.8  235.59
  4438.8  233.84  4510.7  234.02  4981.1  233.13  5003.4  229.33  5017.3  232.91
  5355.1  234.05  5360.7  230.51  5377.6  229.66  5400.1  230.95  5405.7  234.19
  5867.8  232.17  5905.7  229.88  5916.3  226.35  5935.3  226.35  5996.3  233.54
  6136.5  232.59  6295.9  232.53  6394.8  232.76  6700.8  234.46  6743.1  236.61
  6982.6  245.07  7086.9  244.81  7185.8  245.33  7388.4  248.73  7465.5  250.13
#Mann= 15 ,-1 , 0
  3240.9     .06       0  4069.5      .1       0  4265.5     .06       0
  4277.8      .1       0  4438.8     .06       0  4510.7      .1       0
  4981.1     .09       0  5017.3      .1       0  6136.5     .12       0
  6295.9     .06       0  6394.8      .1       0  6743.1     .12       0
  7086.9     .06       0  7185.8     .12       0  7388.4     .06       0
Bank Sta=4981.1,5017.3
XS Rating Curve= 0 ,0
Exp/Cntr=0.3,0.1

Type RM Length L Ch R = 1 ,46124   ,495,495,495
BEGIN DESCRIPTION:
CANEY CREEK 70.0
END DESCRIPTION:
XS GIS Cut Line= 3
      3717217.84     10130711.07      3716394.65     10130359.04
       3713302.7     10129427.62
#Sta/Elev= 30
  4104.7  260.68  4137.3   261.2  4163.8  258.77  4242.4  254.47  4469.5  240.37
  4728.9  232.38  4981.2  233.63    4986  226.88    5005  226.88  5011.3  231.61
  5017.5  233.11  5090.7  230.63  5186.8  232.41  5219.8  230.31  5252.8  232.63
  5299.5  230.77  5612.8  234.09  5623.3  230.94  5669.6  234.05  5812.1  230.54
  5988.8  232.26    6041   230.5  6103.9  232.27  6321.7  231.37  6525.5  233.11
  6673.7  231.85  6721.4  233.45  6841.1  234.93  7544.1  248.58  8229.2  254.57
#Mann= 12 ,-1 , 0
  4104.7     .12       0  4163.8     .06       0  4242.4     .12       0
  4469.5      .1       0  4981.2     .09       0  5017.5      .1       0
  6103.9     .06       0  6321.7      .1       0  6525.5     .12       0
  6721.4      .1       0  6841.1     .12       0  7544.1     .06       0
Bank Sta=4981.2,5017.5
XS Rating Curve= 0 ,0
Exp/Cntr=0.3,0.1

Type RM Length L Ch R = 1 ,45629   ,543,543,543
BEGIN DESCRIPTION:
CANEY CREEK 69.0
END DESCRIPTION:
XS GIS Cut Line= 3
       3717263.2     10130379.54      3716533.59     10129931.28
      3713903.81     10129410.79
#Sta/Elev= 30
  4143.7  257.97  4302.1  248.63  4632.5  230.59  4983.3  232.33    5000  228.01
    5016  232.64    5118   231.4  5138.6  227.01  5158.6  227.01  5158.8  229.61
    5193  231.37  5227.2  231.52  5525.7  232.96  5541.5  229.55  5586.9  232.97
  5643.9  229.13    5649  231.27  5668.5   230.1  5700.3  232.78  6007.7  230.29
  6290.3  232.42  6320.9  229.63  6422.8  232.01  6618.7  231.84  6788.9  233.86
  6973.3  241.08  7146.6  240.51  7309.7  244.95  7616.9  248.58  7680.8  249.36
#Mann= 9 ,-1 , 0
  4143.7     .12       0  4302.1      .1       0  4983.3     .09       0
    5016      .1       0    5193     .06       0  5227.2      .1       0
  6618.7     .06       0  6788.9     .12       0  7616.9     .06       0
Bank Sta=4983.3,5016
XS Rating Curve= 0 ,0
Exp/Cntr=0.3,0.1

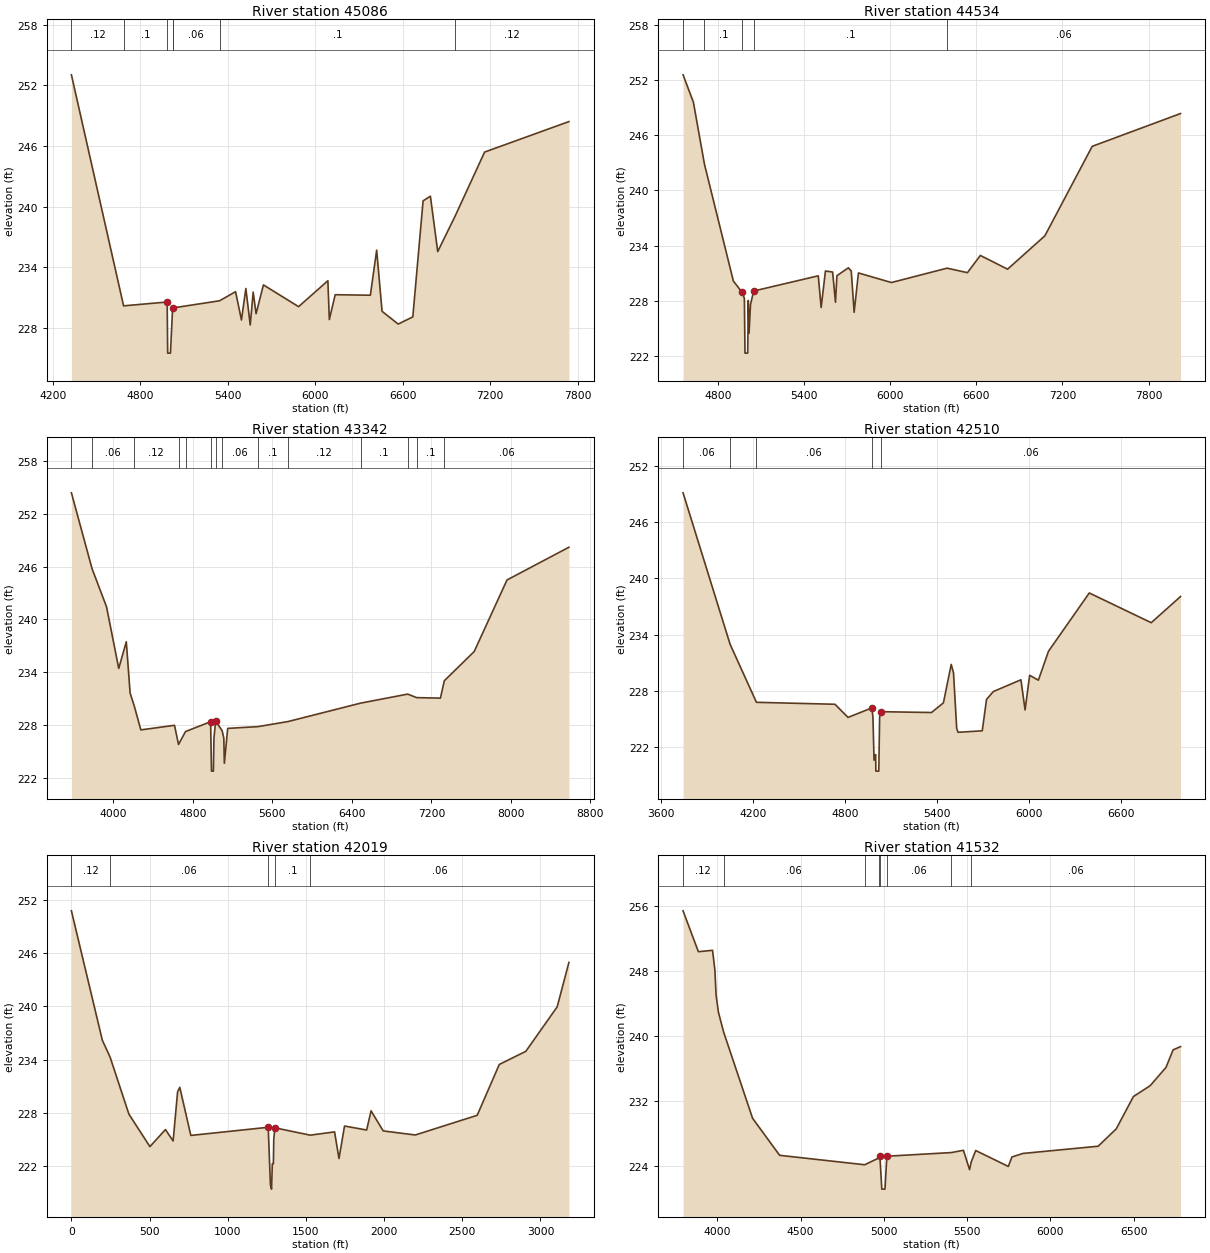
Type RM Length L Ch R = 1 ,45086   ,552,552,552
BEGIN DESCRIPTION:
CANEY CREEK 68.0
END DESCRIPTION:
XS GIS Cut Line= 3
        3717357.     10129744.14      3716711.14     10129561.84
      3713982.39     10129280.64
#Sta/Elev= 30
  4326.5  253.03  4684.6  230.21  4983.7  230.59  4987.2  225.54  5006.2  225.54
    5021  229.99  5021.4     230  5343.3  230.71  5453.3  231.61  5493.5  228.81
  5523.7  231.92  5553.8  228.32  5573.9  231.57    5594  229.43  5644.3  232.28
  5885.6  230.13  6086.6  232.69  6096.7  228.86  6136.9  231.31  6378.2  231.26
  6421.5  235.71  6458.6  229.67  6569.2  228.41  6669.7  229.12  6740.1  240.58
  6790.3  241.04  6840.6  235.57  6960.8   239.1  7162.3   245.4  7740.8  248.41
#Mann= 7 ,-1 , 0
  4326.5     .12       0  4684.6      .1       0  4983.7     .09       0
    5021      .1       0  5021.4     .06       0  5343.3      .1       0
  6960.8     .12       0
Bank Sta=4983.7,5021
XS Rating Curve= 0 ,0
Exp/Cntr=0.3,0.1

Type RM Length L Ch R = 1 ,44534   ,1192,1192,1192
BEGIN DESCRIPTION:
CANEY CREEK 67.0
END DESCRIPTION:
XS GIS Cut Line= 4
      3717377.81     10129285.81      3716971.44     10129103.23
       3716690.3     10129192.05      3713961.95     10129197.26
#Sta/Elev= 30
  4554.5  252.54  4626.4  249.58  4703.7  242.84  4905.3  230.16  4967.1  228.92
    4982  228.28  4986.3  222.34  5005.3  222.34  5009.2  228.05  5014.5  224.49
  5024.7  227.61  5046.8  229.08  5497.3  230.73  5517.3  227.29  5547.3  231.25
  5597.3  231.14  5617.3  227.86  5627.3  230.74  5707.3   231.6  5727.3  231.24
  5747.3  226.77  5777.3  231.04  6007.3     230  6395.4  231.56  6537.3  231.07
  6627.3  232.94  6817.3  231.45  7077.3  235.07  7407.3  244.78  8023.2  248.34
#Mann= 5 ,-1 , 0
  4554.5     .12       0  4703.7      .1       0  4967.1     .09       0
  5046.8      .1       0  6395.4     .06       0
Bank Sta=4967.1,5046.8
XS Rating Curve= 0 ,0
Exp/Cntr=0.3,0.1

Type RM Length L Ch R = 1 ,43342   ,832,832,832
BEGIN DESCRIPTION:
CANEY CREEK 65.0
END DESCRIPTION:
XS GIS Cut Line= 4
      3718560.11     10128895.18       3717127.8     10128275.38
      3715862.18     10129113.93      3713935.12     10129139.97
#Sta/Elev= 30
  3577.7   254.4  3785.1  245.78  3931.1  241.44    4054  234.43  4129.9  237.46
  4168.6  231.62  4209.5  230.18  4276.3  227.44  4615.3  227.96  4655.5  225.78
  4725.8  227.25 4978.47228.3686  4987.2  222.75  5006.2  222.75  5011.9  226.49
  5029.3  228.45  5094.8  227.34  5111.3   226.5  5116.7  223.64  5150.3  227.61
  5455.2  227.81  5758.3  228.39  6486.8  230.48  6961.7  231.51  7051.7  231.11
    7291  231.05  7330.3  233.03    7631  236.35    7961  244.49  8583.8  248.21
#Mann= 14 ,-1 , 0
  3577.7     .12       0  3785.1     .06       0  4209.5     .12       0
  4655.5     .06       0  4725.8     .12       0 4978.47     .09       0
  5029.3     .12       0  5094.8     .06       0  5455.2      .1       0
  5758.3     .12       0  6486.8      .1       0  6961.7     .06       0
  7051.7      .1       0  7330.3     .06       0
Bank Sta=4978.47,5029.3
XS Rating Curve= 0 ,0
Exp/Cntr=0.3,0.1

Type RM Length L Ch R = 1 ,42510   ,491,491,491
BEGIN DESCRIPTION:
CANEY CREEK 63.0
END DESCRIPTION:
XS GIS Cut Line= 3
      3718467.82     10128511.04       3717569.6     10127631.55
      3715931.39     10126510.79
#Sta/Elev= 30
  3742.9  249.11  4049.2  232.97    4221  226.77  4732.9  226.56  4817.8  225.16
  4973.4  226.17  4980.3  225.19  4987.5   220.6  4997.7  221.19  4999.4  219.43
  5018.4  219.43  5023.9  225.14  5029.9  225.77  5361.7  225.68  5439.6  226.71
  5490.4  230.81  5505.3  229.92  5526.2  223.99  5535.1  223.57  5692.7  223.73
  5720.6  227.08  5765.3  227.92  5944.7  229.17  5971.8  225.96  6001.6  229.65
  6058.5  229.13  6124.2  232.21  6390.3  238.43  6793.9  235.26  6984.9  238.05
#Mann= 5 ,-1 , 0
  3742.9     .06       0  4049.2     .12       0    4221     .06       0
  4973.4     .06       0  5029.9     .06       0
Bank Sta=4973.4,5029.9
XS Rating Curve= 0 ,0
Exp/Cntr=0.3,0.1

Type RM Length L Ch R = 1 ,42019   ,487,487,487
BEGIN DESCRIPTION:
CANEY CREEK 62.0
END DESCRIPTION:
XS GIS Cut Line= 4
      3718667.85     10128111.07      3717766.46     10127189.06
      3716567.85     10126011.07       3716396.5     10125883.95
#Sta/Elev= 30
       0  250.77   197.9  236.18   247.5  234.28   367.7  227.86   502.1   224.2
   601.2  226.12   650.6  224.84   678.9  230.36     693  230.89   763.7  225.46
  1258.7  226.38  1272.8  219.87  1279.9  219.41  1284.9  222.27  1291.6  222.27
  1294.1  225.02  1301.2  226.32  1527.4  225.49    1683  225.86  1711.3  222.86
  1746.7  226.52  1888.1  226.07  1916.4  228.23  1994.1  225.97  2199.2  225.51
  2595.2  227.73  2736.6  233.46  2906.3  234.94  3106.7  239.95  3181.6  244.95
#Mann= 5 ,-1 , 0
       0     .12       0   247.5     .06       0  1258.7     .06       0
  1301.2      .1       0  1527.4     .06       0
Bank Sta=1258.7,1301.2
XS Rating Curve= 0 ,0
Exp/Cntr=0.3,0.1

Type RM Length L Ch R = 1 ,41532   ,522,522,522
BEGIN DESCRIPTION:
CANEY CREEK 61.0
END DESCRIPTION:
XS GIS Cut Line= 3
      3718917.83     10127711.05      3718091.39      10126833.7
      3716567.87     10125911.08
#Sta/Elev= 30
  3794.7  255.43  3886.7   250.4  3971.7  250.57  3985.8  248.14  3992.7  245.12
  4006.9  242.96  4038.1  240.52    4212   229.9  4374.6  225.34  4885.1  224.18
  4970.6  225.02  4976.1   225.3  4987.8  221.18  5006.8  221.18  5018.2  225.23
  5405.7  225.68  5477.8  225.96  5514.7  223.57  5524.6  224.53  5551.5  225.93
  5747.4  223.97  5768.7  225.13  5834.2  225.57  6286.6  226.46  6395.3   228.6
    6498  232.57  6598.8  233.91  6693.8  236.16  6736.5  238.32  6781.1  238.72
#Mann= 8 ,-1 , 0
  3794.7     .12       0  4038.1     .06       0  4885.1     .12       0
  4970.6     .06       0  4976.1     .06       0  5018.2     .06       0
  5405.7     .12       0  5524.6     .06       0
Bank Sta=4976.1,5018.2
XS Rating Curve= 0 ,0
Exp/Cntr=0.3,0.1

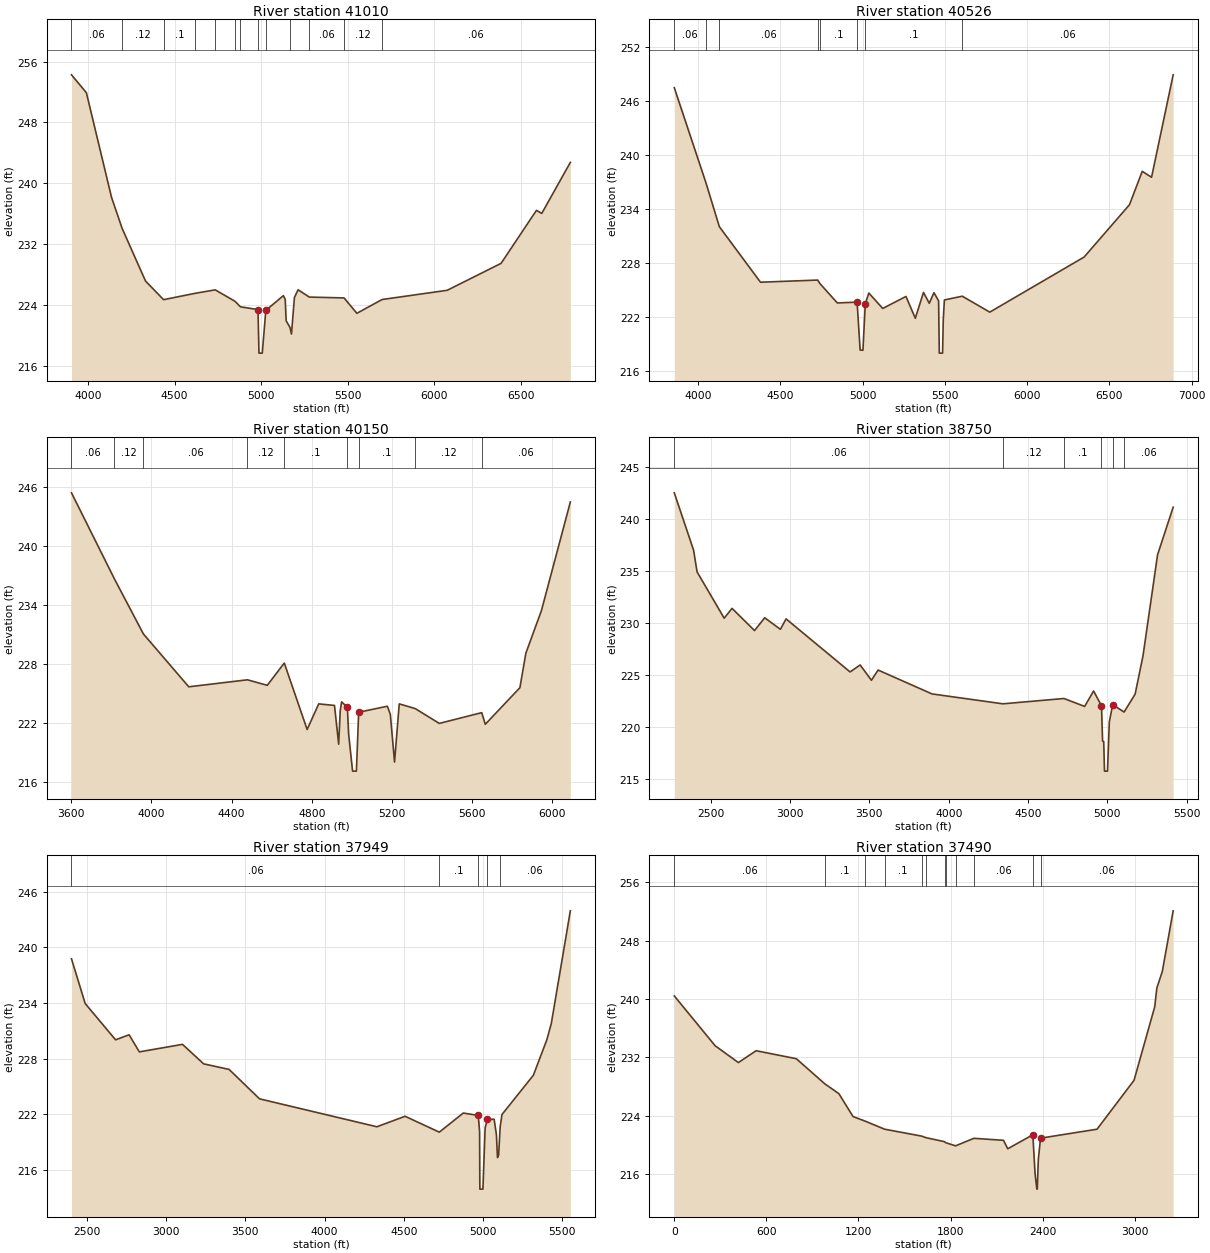
Type RM Length L Ch R = 1 ,41010   ,484,484,484
BEGIN DESCRIPTION:
CANEY CREEK 60.0
END DESCRIPTION:
XS GIS Cut Line= 3
      3719117.89      10126961.1      3718195.51     10126363.93
      3716518.43     10125759.76
#Sta/Elev= 30
  3904.5  254.26  3990.6  251.91  4135.7  238.18  4196.9   234.1  4332.2  227.18
  4436.4  224.73  4620.1  225.57  4734.8  226.02  4849.5  224.51  4880.4  223.79
  4981.8  223.43  4987.5  217.71  5006.5  217.71  5026.9  223.32  5128.4  225.26
    5139  224.76  5144.4  221.97  5166.5  221.08  5175.1  220.22  5192.2  225.02
  5213.4  226.03  5278.3  225.07  5478.9  224.96  5552.9  222.94  5698.4  224.75
  6074.4  225.96  6385.8   229.5  6590.1  236.46  6620.8  236.06  6785.9  242.76
#Mann= 13 ,-1 , 0
  3904.5     .06       0  4196.9     .12       0  4436.4      .1       0
  4620.1     .12       0  4734.8     .06       0  4849.5     .12       0
  4880.4     .06       0  4981.8     .06       0  5026.9     .06       0
  5166.5     .12       0  5278.3     .06       0  5478.9     .12       0
  5698.4     .06       0
Bank Sta=4981.8,5026.9
XS Rating Curve= 0 ,0
Exp/Cntr=0.3,0.1

Type RM Length L Ch R = 1 ,40526   ,376,376,376
BEGIN DESCRIPTION:
CANEY CREEK 59.0
END DESCRIPTION:
XS GIS Cut Line= 3
      3719127.83     10126791.04      3718367.39     10125952.47
      3716987.67     10124645.64
#Sta/Elev= 30
  3855.2  247.44  4047.2  236.91  4129.1  232.01  4379.3  225.85    4727  226.09
  4739.1  225.73  4846.2  223.55  4966.5  223.64  4984.8  218.32  5001.9   218.3
    5016  223.44  5037.5  224.65  5122.4  222.94  5263.6  224.27  5320.2  221.85
    5370  224.72  5405.2  223.51  5433.5  224.69  5461.8  223.78    5466  217.98
    5486  217.98  5490.1  221.68    5497  223.88  5605.5   224.3  5772.9  222.53
  6346.1  228.64    6622  234.45  6699.7  238.16  6756.3   237.5  6887.6  248.87
#Mann= 8 ,-1 , 0
  3855.2     .06       0  4047.2     .12       0  4129.1     .06       0
    4727     .12       0  4739.1      .1       0  4966.5     .09       0
    5016      .1       0  5605.5     .06       0
Bank Sta=4966.5,5016
XS Rating Curve= 0 ,0
Exp/Cntr=0.3,0.1

Type RM Length L Ch R = 1 ,40150   ,1400,1400,1400
BEGIN DESCRIPTION:
CANEY CREEK 58.0
END DESCRIPTION:
XS GIS Cut Line= 3
      3719252.77     10126707.64      3718391.45     10125605.22
      3717767.87     10124711.09
#Sta/Elev= 30
    3601  245.36  3814.8  236.65  3959.8  231.05  4186.2  225.69    4479   226.4
  4577.8  225.84  4662.8   228.1  4776.8  221.36  4834.6  223.96  4913.3   223.8
  4934.1  219.87  4941.8  223.23  4948.6  224.16  4977.5  223.63  4983.9  220.89
  5003.6  217.14  5022.6  217.14    5034  223.11  5177.1  223.72  5191.9   222.9
  5212.9  218.06  5236.4  223.96  5316.2  223.48  5436.2  221.98  5647.9  223.07
  5665.7  221.89  5838.4   225.6  5868.1   229.1  5945.7  233.41  6090.1  244.43
#Mann= 9 ,-1 , 0
    3601     .06       0  3814.8     .12       0  3959.8     .06       0
    4479     .12       0  4662.8      .1       0  4977.5     .09       0
    5034      .1       0  5316.2     .12       0  5647.9     .06       0
Bank Sta=4977.5,5034
XS Rating Curve= 0 ,0
Exp/Cntr=0.3,0.1

Type RM Length L Ch R = 1 ,38750   ,801,801,801
BEGIN DESCRIPTION:
Mapping XS 71847096
END DESCRIPTION:
XS GIS Cut Line= 3
      3720700.71     10126639.96       3720127.8     10126166.01
      3718451.79     10124448.36
#Sta/Elev= 30
    2271  242.51  2392.5  237.01  2414.6  234.92  2585.3  230.48  2634.8  231.42
  2776.7  229.29  2840.6  230.52  2939.5  229.41  2975.5  230.41  3378.7  225.32
  3442.2  225.99    3513  224.52  3555.4   225.5  3894.9  223.21  4341.5  222.26
  4726.2  222.77  4856.6  222.01  4913.2  223.49  4962.8  222.07  4969.7  218.68
  4976.9  218.64  4981.6   215.8  5000.6   215.8  5012.2  220.53  5033.4  222.18
  5105.2  221.47  5174.8  223.19  5224.4  226.87  5316.2  236.57  5414.4  241.13
#Mann= 6 ,-1 , 0
    2271     .06       0  4341.5     .12       0  4726.2      .1       0
  4962.8     .09       0  5033.4      .1       0  5105.2     .06       0
Bank Sta=4962.8,5033.4
XS Rating Curve= 0 ,0
Exp/Cntr=0.3,0.1

Type RM Length L Ch R = 1 ,37949   ,459,459,459
BEGIN DESCRIPTION:
CANEY CREEK 57.0
END DESCRIPTION:
XS GIS Cut Line= 4
       3720679.9      10126530.6      3720205.93     10126145.18
      3719237.18     10124421.22      3718842.47     10124026.51
#Sta/Elev= 30
  2403.4  238.77  2489.8  233.95  2681.6  230.04  2766.9  230.58  2831.4  228.74
  3103.6  229.55    3237  227.45  3397.5  226.85  3589.5  223.68  4329.7  220.67
  4507.6   221.8  4723.4  220.09  4874.8  222.15    4969  221.89  4977.5  220.17
    4979  214.45  4979.5  213.95  4998.5  213.95  5012.6  220.56  5026.8  221.46
  5069.2  221.48  5083.4  219.86  5090.4  217.35  5097.5   217.6  5107.4  220.65
  5118.7  221.99  5316.7  226.22  5401.6  230.04  5429.8  231.79    5550  243.94
#Mann= 5 ,-1 , 0
  2403.4     .06       0  4723.4      .1       0    4969     .09       0
  5026.8      .1       0  5107.4     .06       0
Bank Sta=4969,5026.8
XS Rating Curve= 0 ,0
Exp/Cntr=0.3,0.1

Type RM Length L Ch R = 1 ,37490   ,658,658,658
BEGIN DESCRIPTION:
CANEY CREEK 56.0
END DESCRIPTION:
XS GIS Cut Line= 4
      3721064.36     10126236.56      3720740.39     10125777.82
      3719586.14     10124395.18      3718917.85     10123811.07
#Sta/Elev= 30
       0  240.43   266.3   233.6   417.7   231.3   533.1  232.92   795.1  231.83
   979.9   228.4  1072.3  227.04  1164.7   223.9  1242.8  223.28  1370.4  222.17
  1612.4  221.22  1639.8  221.01  1760.8  220.46  1768.6  220.32  1832.4  219.89
  1952.1  220.92  2144.7  220.65  2172.7  219.49  2336.1  221.41  2350.4   216.1
  2362.1  213.96  2364.9  213.96  2371.8  218.03  2386.1  220.94  2754.3  222.17
  2995.4  228.87  3130.2  238.95    3144  241.52  3179.6  243.78  3250.3  252.09
#Mann= 12 ,-1 , 0
       0     .06       0   979.9      .1       0  1242.8     .06       0
  1370.4      .1       0  1612.4     .06       0  1639.8      .1       0
  1760.8     .06       0  1768.6     .09       0  1832.4     .06       0
  1952.1     .06       0  2336.1     .09       0  2386.1     .06       0
Bank Sta=2336.1,2386.1
XS Rating Curve= 0 ,0
Exp/Cntr=0.3,0.1