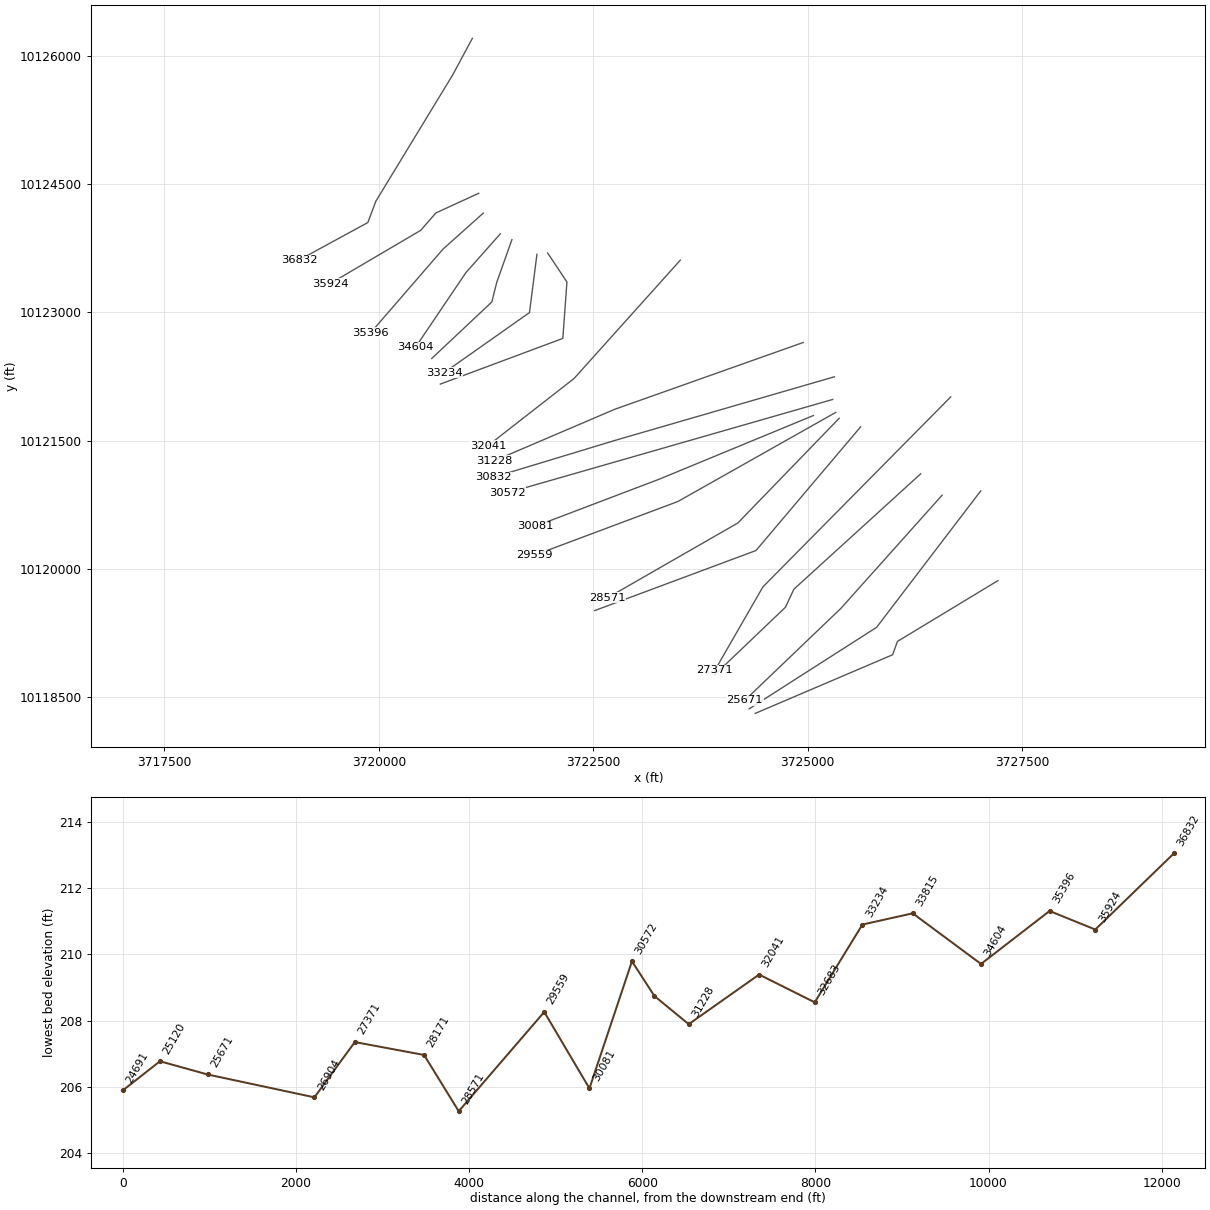
HEC-RAS study CANEY CREEK.prj: CANEY CREEK Base Level Engineering

--- CANEY CREEK.g01 (geometry) --- (continued)

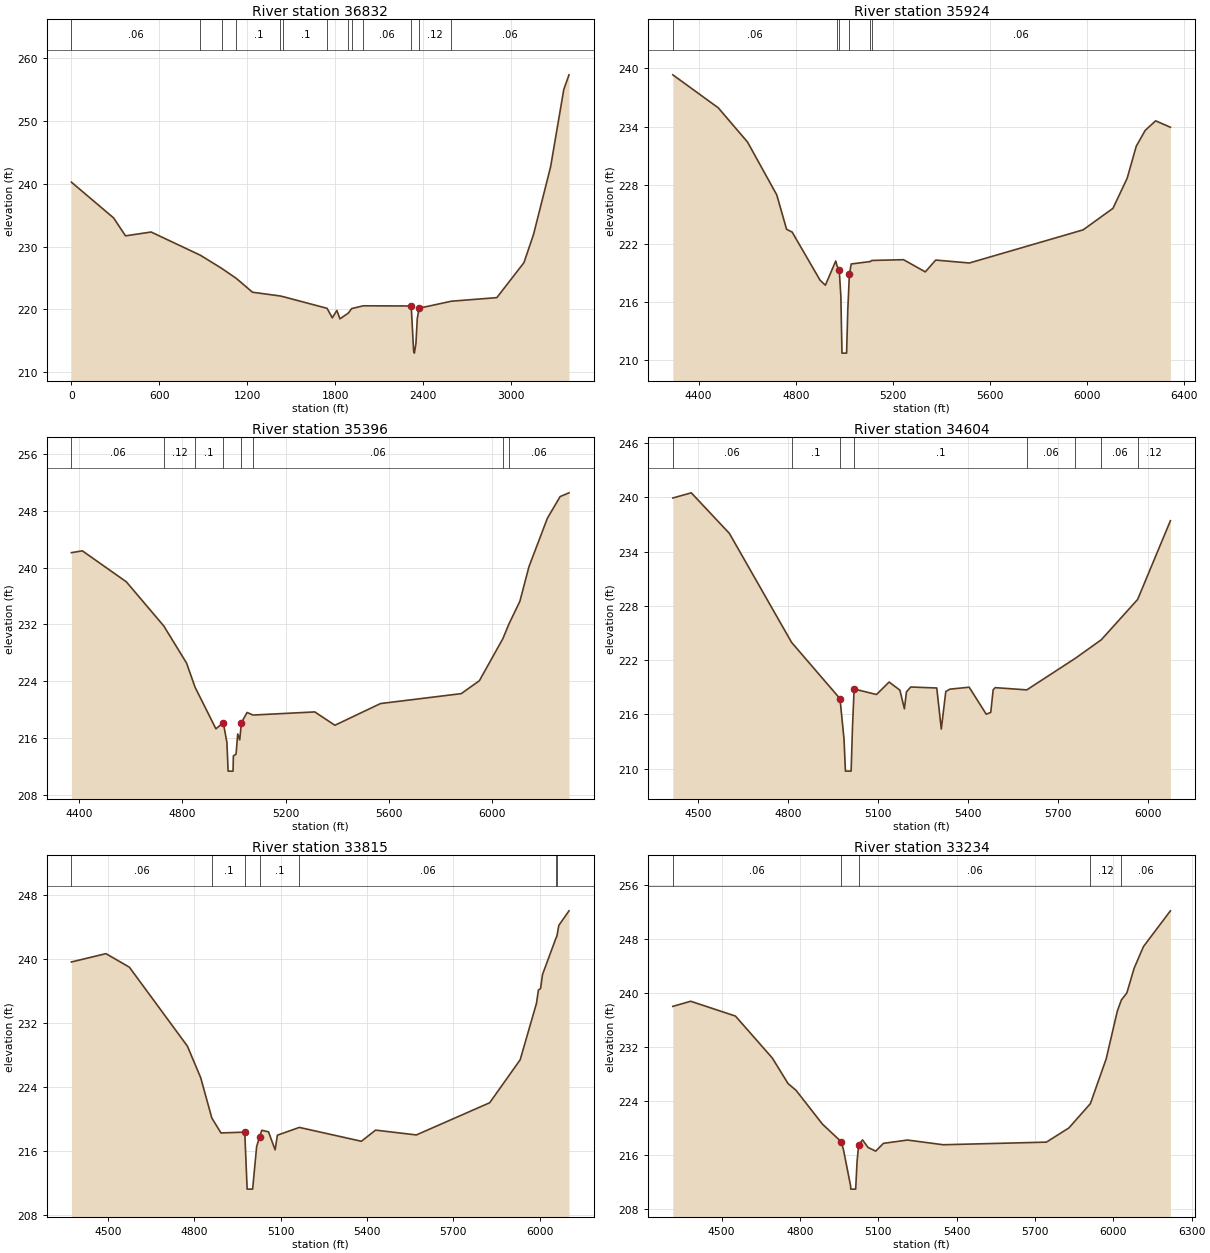
Type RM Length L Ch R = 1 ,36832   ,908,908,908
BEGIN DESCRIPTION:
CANEY CREEK 55.0
END DESCRIPTION:
XS GIS Cut Line= 5
      3721091.23     10126206.33      3720860.24     10125776.05
      3719966.35     10124301.43       3719872.6     10124051.43
      3719067.85     10123611.07
#Sta/Elev= 30
       0  240.25   288.3  234.56   369.2  231.71     544  232.32   880.1  228.63
  1024.9  226.55  1125.7  224.94  1236.2  222.74  1426.2  222.14  1447.6  222.02
  1745.4  220.18  1781.1  218.67  1812.1  219.84  1833.4  218.51  1891.6  219.44
  1912.9  220.13  1992.4  220.58  2319.9  220.55  2336.3   213.4  2341.6  213.05
    2352  214.57  2361.2  218.52  2373.3   220.2  2594.3  221.31  2904.4  221.88
  3089.3  227.44  3154.8  231.92  3271.7  242.72  3361.5     255  3397.1  257.33
#Mann= 13 ,-1 , 0
       0     .06       0   880.1      .1       0  1024.9     .06       0
  1125.7      .1       0  1426.2     .06       0  1447.6      .1       0
  1745.4     .06       0  1891.6      .1       0  1912.9     .09       0
  1992.4     .06       0  2319.9     .09       0  2373.3     .12       0
  2594.3     .06       0
Bank Sta=2319.9,2373.3
XS Rating Curve= 0 ,0
Exp/Cntr=0.3,0.1

Type RM Length L Ch R = 1 ,35924   ,528,528,528
BEGIN DESCRIPTION:
CANEY CREEK 54.0
END DESCRIPTION:
XS GIS Cut Line= 4
      3721165.18     10124393.46        3720666.     10124163.41
      3720488.05     10123959.41      3719430.43     10123335.25
#Sta/Elev= 30
  4294.2  239.31  4481.5  235.92  4601.8  232.41  4722.1  226.99  4762.5  223.46
  4785.5  223.17  4900.5  218.23  4922.3  217.72    4965  220.21  4970.4  219.69
  4979.3  219.28  4985.9  216.63  4990.6  210.75  5009.6  210.75  5014.4  215.14
    5021  218.82  5028.6   219.9  5107.3  220.15  5113.2  220.26  5243.7  220.34
  5333.6  219.09  5376.5   220.3    5515     220  5983.3   223.4  6106.2  225.61
  6164.8  228.71  6201.9  231.98  6238.9  233.61  6281.8  234.59  6342.6  233.93
#Mann= 6 ,-1 , 0
  4294.2     .06       0  4970.4      .1       0  4979.3     .06       0
    5021     .06       0  5107.3      .1       0  5113.2     .06       0
Bank Sta=4979.3,5021
XS Rating Curve= 0 ,0
Exp/Cntr=0.3,0.1

Type RM Length L Ch R = 1 ,35396   ,792,792,792
BEGIN DESCRIPTION:
CANEY CREEK 53.0
END DESCRIPTION:
XS GIS Cut Line= 3
      3721217.87     10124161.09      3720749.22     10123740.66
      3719902.02     10122758.06
#Sta/Elev= 30
  4370.4  242.12  4412.7  242.38  4583.1  238.01  4728.4  231.77  4816.3  226.55
  4849.3  223.14    4930  217.28  4958.4  218.15  4972.6  215.36  4977.3  211.31
  4996.3  211.31  4997.6  213.46  5007.9   213.7  5014.5  216.56  5022.2  215.72
  5028.8  218.16  5050.7  219.58  5073.8  219.22  5312.9  219.66  5390.8  217.78
  5567.4  220.84  5880.1  222.24  5950.3  224.06  6041.2  229.99    6065  232.08
  6107.2  235.27  6142.3  240.14  6213.6  246.97    6263  250.03  6297.4  250.56
#Mann= 8 ,-1 , 0
  4370.4     .06       0  4728.4     .12       0  4849.3      .1       0
  4958.4     .09       0  5028.8      .1       0  5073.8     .06       0
  6041.2     .12       0    6065     .06       0
Bank Sta=4958.4,5028.8
XS Rating Curve= 0 ,0
Exp/Cntr=0.3,0.1

Type RM Length L Ch R = 1 ,34604   ,789,789,789
BEGIN DESCRIPTION:
CANEY CREEK 52.0
END DESCRIPTION:
XS GIS Cut Line= 3
      3721416.87     10123918.62      3721015.82     10123465.49
       3720427.3     10122590.51
#Sta/Elev= 30
    4415  239.94  4476.6  240.51  4603.7  236.02  4811.3  223.95  4972.6  217.73
    4986  213.26  4990.7  209.71  5009.7  209.71  5014.4  214.73  5019.7   218.8
  5094.4  218.19  5136.4  219.57  5172.4  218.67  5187.4  216.61  5194.2  218.48
  5208.4  219.02  5295.4  218.91  5310.4  214.36  5325.4  218.51  5338.8  218.78
  5403.4     219  5460.4  216.01  5475.4  216.21  5483.4  218.71  5490.4  218.95
  5595.5   218.7  5757.2  222.19  5844.2  224.25  5965.3  228.71  6074.6  237.42
#Mann= 8 ,-1 , 0
    4415     .06       0  4811.3      .1       0  4972.6     .09       0
  5019.7      .1       0  5595.5     .06       0  5757.2     .12       0
  5844.2     .06       0  5965.3     .12       0
Bank Sta=4972.6,5019.7
XS Rating Curve= 0 ,0
Exp/Cntr=0.3,0.1

Type RM Length L Ch R = 1 ,33815   ,581,581,581
BEGIN DESCRIPTION:
CANEY CREEK 51.0
END DESCRIPTION:
XS GIS Cut Line= 4
      3721552.29     10123850.92       3721375.2     10123350.91
      3721317.91     10123121.74      3720617.88      10122461.1
#Sta/Elev= 30
  4373.3  239.62  4493.3  240.66  4574.7  238.97  4776.3  229.11  4822.5  225.17
  4861.2  220.13    4893  218.26  4975.7  218.36    4984  211.24    5003  211.24
    5017  216.56  5027.3  217.78  5034.8  218.59  5058.2   218.4  5081.2  216.15
  5089.1  217.98  5165.3  218.95    5381  217.22  5430.4  218.61    5572  218.01
  5826.8  222.03  5932.8   227.4  5989.5  234.46  5996.3  236.13  6003.6  236.29
  6010.5  238.06  6057.7  242.65  6060.3  242.82  6067.1  244.19  6102.5  246.01
#Mann= 7 ,-1 , 0
  4373.3     .06       0  4861.2      .1       0  4975.7     .09       0
  5027.3      .1       0  5165.3     .06       0  6057.7     .12       0
  6060.3     .06       0
Bank Sta=4975.7,5027.3
XS Rating Curve= 0 ,0
Exp/Cntr=0.3,0.1

Type RM Length L Ch R = 1 ,33234   ,551,551,551
BEGIN DESCRIPTION:
CANEY CREEK 50.0
END DESCRIPTION:
XS GIS Cut Line= 3
      3721843.95     10123679.05      3721756.98     10122997.58
      3720761.73      10122294.4
#Sta/Elev= 30
    4313  238.04  4381.5   238.8  4552.9   236.6    4694  230.37  4754.5  226.57
  4784.8  225.58  4885.6  220.57  4957.4  217.96  4966.2  216.82  4993.8   211.4
  4994.3   210.9  5013.3   210.9  5018.6  215.01  5024.7  217.44  5039.5  218.21
  5060.4   217.1    5090  216.54  5119.6   217.7  5211.9  218.19  5348.6  217.49
  5743.8  217.88  5829.9  219.99  5912.2   223.6  5972.7  230.25  6015.2  237.33
  6030.7  238.98  6051.9  240.05  6079.8  243.72  6115.5  246.93  6218.6  252.23
#Mann= 5 ,-1 , 0
    4313     .06       0  4957.4     .06       0  5024.7     .06       0
  5912.2     .12       0  6030.7     .06       0
Bank Sta=4957.4,5024.7
XS Rating Curve= 0 ,0
Exp/Cntr=0.3,0.1

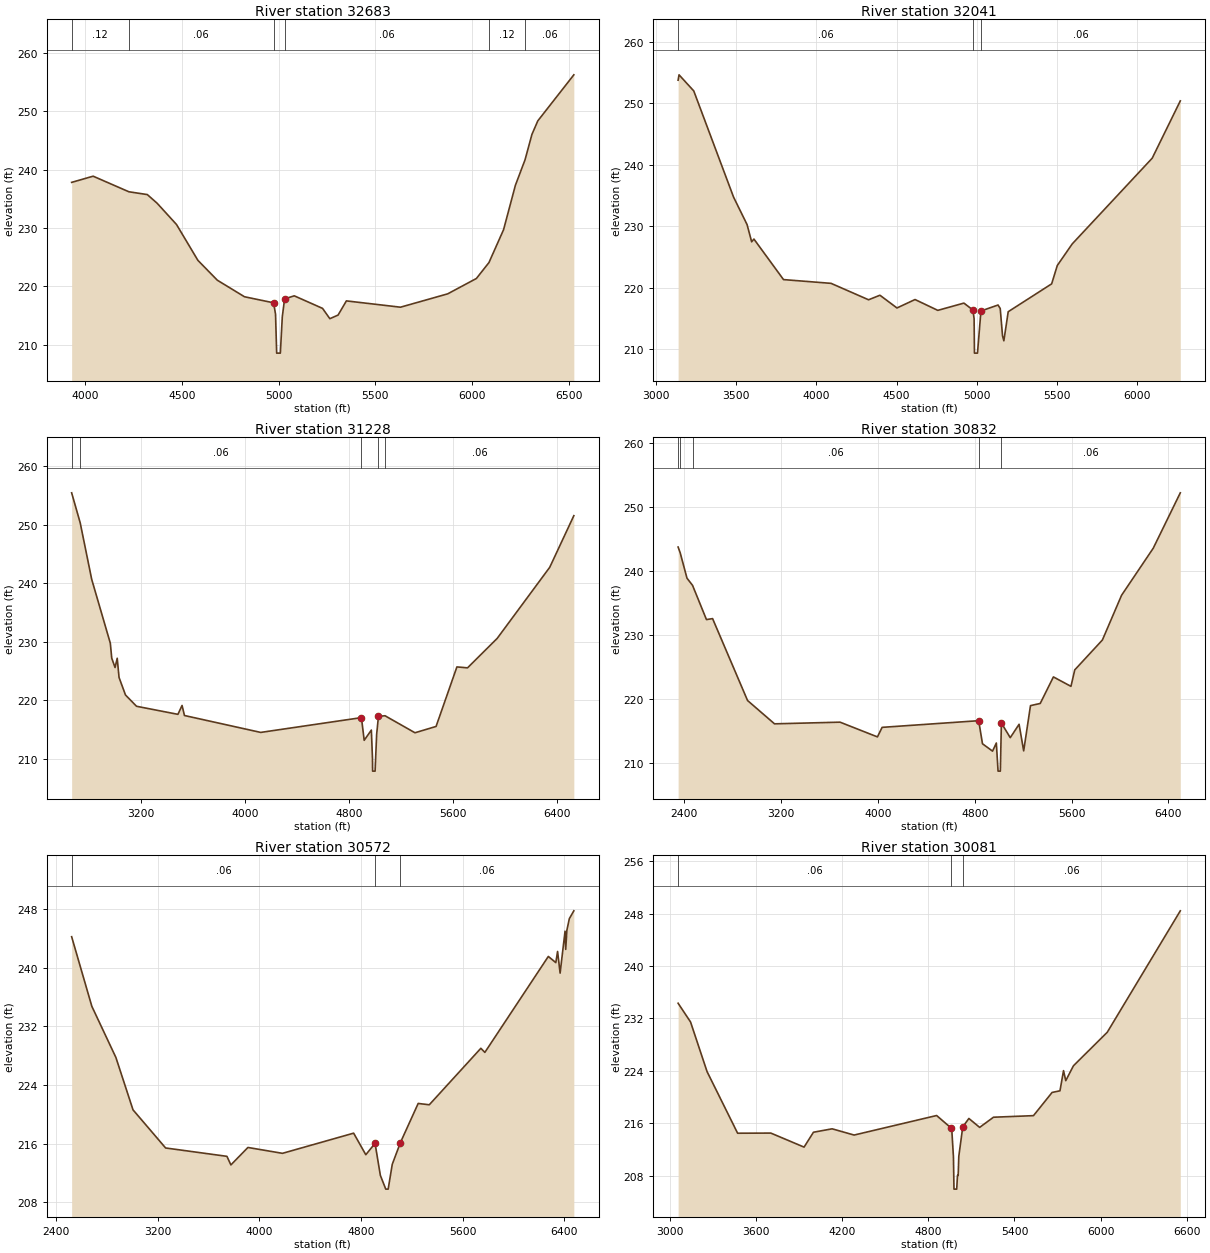
Type RM Length L Ch R = 1 ,32683   ,642,642,642
BEGIN DESCRIPTION:
CANEY CREEK 49.0
END DESCRIPTION:
XS GIS Cut Line= 4
      3721968.96     10123694.64      3722193.57     10123355.69
      3722145.92     10122695.53      3720717.85     10122161.07
#Sta/Elev= 30
  3931.5  237.81  4042.5  238.87    4227   236.2  4322.2  235.72  4372.8  234.24
  4473.1  230.59  4583.4  224.45  4683.6  221.05    4824  218.21  4974.4  217.17
  4984.4  215.21  4990.2  208.55  5009.2  208.55  5019.3  214.77  5031.1  217.84
    5081  218.37  5227.1  216.22  5264.9  214.45  5307.3  215.07  5350.3   217.5
  5629.7  216.42  5873.5  218.71  6021.6  221.34  6086.5  224.07  6161.8  229.69
  6222.9   237.3  6272.8  241.68  6308.4  246.03  6338.7  248.35  6524.8  256.24
#Mann= 6 ,-1 , 0
  3931.5     .12       0    4227     .06       0  4974.4     .06       0
  5031.1     .06       0  6086.5     .12       0  6272.8     .06       0
Bank Sta=4974.4,5031.1
XS Rating Curve= 0 ,0
Exp/Cntr=0.3,0.1

Type RM Length L Ch R = 1 ,32041   ,813,813,813
BEGIN DESCRIPTION:
CANEY CREEK 48.0
END DESCRIPTION:
XS GIS Cut Line= 3
      3723515.85     10123611.35      3722276.24     10122225.91
      3721271.94     10121440.16
#Sta/Elev= 30
  3136.5  253.75  3142.3  254.62  3234.2     252  3482.5  234.75  3566.9  230.28
  3595.4  227.48  3609.6  227.93  3794.3  221.34    4091  220.73  4325.1  218.06
  4396.1   218.8  4502.3  216.73  4615.2   218.1  4757.2  216.34  4920.2  217.52
  4976.3   216.4  4983.8  214.98  4985.9  209.39  5004.9  209.39  5026.5  216.24
  5133.2  217.21  5146.8  216.64  5161.2   212.2  5169.4  211.39  5196.7  216.12
  5467.8  220.65    5503  223.63  5596.2  227.14  6095.3  241.07  6270.7  250.38
#Mann= 3 ,-1 , 0
  3136.5     .06       0  4976.3     .06       0  5026.5     .06       0
Bank Sta=4976.3,5026.5
XS Rating Curve= 0 ,0
Exp/Cntr=0.3,0.1

Type RM Length L Ch R = 1 ,31228   ,396,396,396
BEGIN DESCRIPTION:
CANEY CREEK 47.0
END DESCRIPTION:
XS GIS Cut Line= 3
      3724948.08     10122647.77      3722749.58     10121865.59
      3721343.95     10121262.36
#Sta/Elev= 30
  2666.5  255.48  2732.2  250.36  2820.7  240.69  2963.9  229.77  2974.9  227.21
  3000.4  225.61    3017  227.19  3031.2   223.9  3080.7  220.91  3165.6  218.98
    3484   217.6  3515.9  219.12  3534.3   217.4  4120.9  214.51  4895.7  217.04
  4916.9  213.16    4972  214.91  4980.6  210.06  4981.7  207.89  5000.7  207.89
  5012.8  214.19  5026.6  217.25  5077.1  217.36  5307.5  214.45  5469.8  215.53
  5630.1  225.71  5711.7  225.55  5940.1  230.59  6344.3  242.75  6529.6  251.57
#Mann= 5 ,-1 , 0
  2666.5     .12       0  2732.2     .06       0  4895.7     .09       0
  5026.6      .1       0  5077.1     .06       0
Bank Sta=4895.7,5026.6
XS Rating Curve= 0 ,0
Exp/Cntr=0.3,0.1

Type RM Length L Ch R = 1 ,30832   ,260,260,260
BEGIN DESCRIPTION:
CANEY CREEK 46.0
END DESCRIPTION:
XS GIS Cut Line= 3
      3725312.69     10122246.74      3722771.03     10121507.16
      3721333.51     10121069.65
#Sta/Elev= 30
    2348  243.71  2365.7  242.78  2421.3  238.85  2467.3  237.73  2582.2  232.39
  2632.9  232.54  2921.8  219.76  3144.6  216.12  3686.1  216.38  3995.1  214.08
  4033.8  215.57  4831.8  216.61    4863  213.01  4946.3  211.86  4977.6  213.13
  4991.7  208.74  5010.7  208.74  5019.3  216.25  5092.5  213.96  5165.5  216.05
  5203.5   211.9  5259.7  218.96  5340.2   219.3  5449.2  223.44  5594.2  221.97
  5625.6  224.54  5853.9   229.2  6012.3  236.18  6274.2  243.53  6497.7  252.17
#Mann= 5 ,-1 , 0
    2348     .06       0  2365.7     .12       0  2467.3     .06       0
  4831.8     .06       0  5019.3     .06       0
Bank Sta=4831.8,5019.3
XS Rating Curve= 0 ,0
Exp/Cntr=0.3,0.1

Type RM Length L Ch R = 1 ,30572   ,491,491,491
BEGIN DESCRIPTION:
Mapping XS 2a97a3c3
END DESCRIPTION:
XS GIS Cut Line= 2
      3725291.87     10121981.12      3721494.97     10120887.36
#Sta/Elev= 30
  2522.7   244.2  2681.6  234.71  2870.8  227.74  3005.5   220.6    3262   215.4
  3744.5  214.26  3775.7  213.09  3909.7  215.47  4181.5  214.67  4741.4  217.42
  4837.2  214.48    4910  216.03  4951.6  211.67  4994.2  209.79  5013.2  209.79
  5045.3  213.17  5109.4  216.13  5249.3  221.47  5336.7  221.29  5742.5  228.99
  5773.8  228.43  6273.3  241.51  6332.3  240.67  6346.1  242.19    6366  239.24
  6404.9  244.95  6410.1  242.47    6419  245.05  6438.5  246.66    6474  247.73
#Mann= 3 ,-1 , 0
  2522.7     .06       0    4910     .06       0  5109.4     .06       0
Bank Sta=4910,5109.4
XS Rating Curve= 0 ,0
Exp/Cntr=0.3,0.1

Type RM Length L Ch R = 1 ,30081   ,522,522,522
BEGIN DESCRIPTION:
CANEY CREEK 45.0
END DESCRIPTION:
XS GIS Cut Line= 3
      3725067.87      10121793.6      3723271.03     10121048.82
      3721823.09     10120496.73
#Sta/Elev= 30
  3059.5  234.31  3146.1  231.45  3260.9  223.88  3473.6  214.48  3704.8   214.5
    3936  212.36  4001.3  214.63  4131.2  215.15  4284.3   214.2  4858.5  217.18
  4959.4  215.27  4964.8  214.71  4975.5  210.85  4979.2  205.95  4998.2  205.95
  5003.6  208.04  5008.4  208.04  5012.8  210.96 5040.42215.4501  5082.9  216.73
  5157.9  215.37  5254.1  216.92  5532.4  217.16    5662   220.7  5716.8  220.95
  5741.6  224.03  5757.1   222.5  5810.6  224.77  6045.8  229.88  6554.2  248.41
#Mann= 3 ,-1 , 0
  3059.5     .06       0  4959.4     .06       0 5040.42     .06       0
Bank Sta=4959.4,5040.42
XS Rating Curve= 0 ,0
Exp/Cntr=0.3,0.1

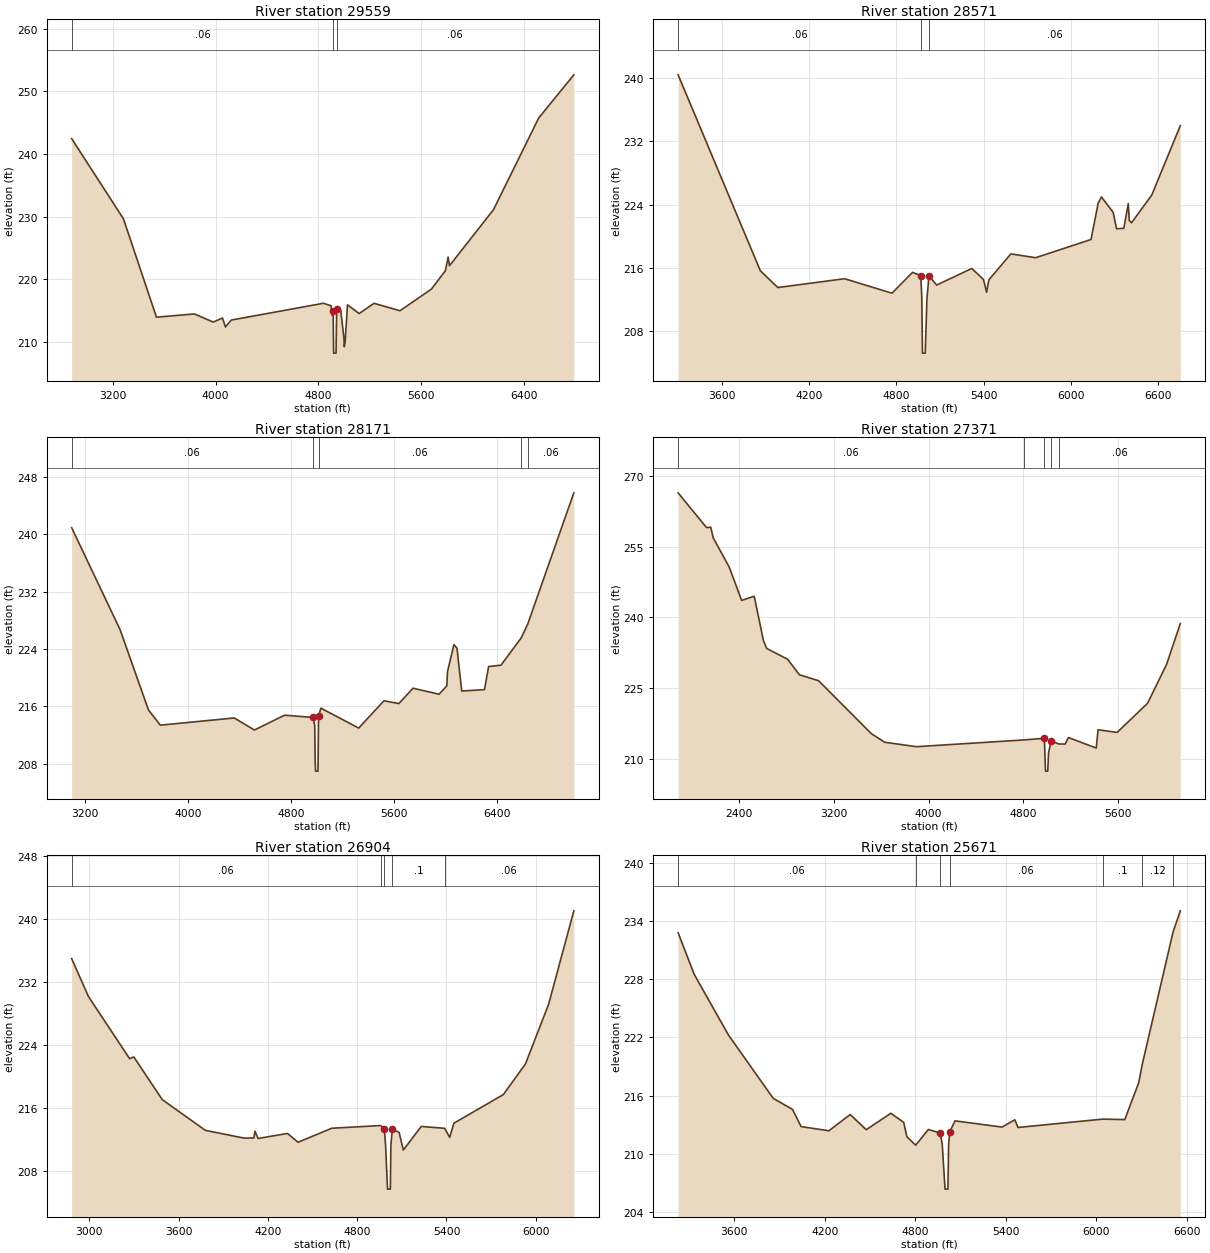
Type RM Length L Ch R = 1 ,29559   ,988,988,988
BEGIN DESCRIPTION:
CANEY CREEK 44.0
END DESCRIPTION:
XS GIS Cut Line= 3
      3725328.36     10121830.09      3723486.31     10120786.67
      3721812.76     10120158.22
#Sta/Elev= 30
  2881.3  242.46  3284.1  229.67  3540.7  213.99  3835.8  214.51  3982.3  213.21
  4054.2  213.86  4077.1  212.43  4122.2  213.53  4839.3  216.21  4898.5  215.81
  4904.6  214.35  4914.4  214.98  4918.1  208.26  4937.1  208.26  4941.8  215.25
  4973.6  215.07  4998.3  210.69    5001   209.3  5007.4  209.92  5025.9  215.96
  5116.7  214.57  5232.3   216.2  5434.7  215.02  5678.9  218.47  5787.2   221.4
  5808.5  223.58  5819.2   222.2    6161  231.12  6513.5  245.77    6786  252.63
#Mann= 3 ,-1 , 0
  2881.3     .06       0  4914.4     .06       0  4941.8     .06       0
Bank Sta=4914.4,4941.8
XS Rating Curve= 0 ,0
Exp/Cntr=0.3,0.1

Type RM Length L Ch R = 1 ,28571   ,400,400,400
BEGIN DESCRIPTION:
CANEY CREEK 43.0
END DESCRIPTION:
XS GIS Cut Line= 3
      3725367.83     10121761.05      3724186.49     10120536.08
      3722667.83     10119661.06
#Sta/Elev= 30
  3298.2  240.38    3864  215.65  3984.1  213.54  4443.9  214.65  4769.3  212.82
  4910.5  215.45  4967.1  215.05  4974.3  212.43    4979  205.26    4998  205.26
    5010  212.16  5023.7  215.01  5076.8  213.85  5318.2  215.94  5398.6  214.56
  5420.2  212.95  5435.9  214.51    5587  217.78  5757.8   217.3  6138.5   219.6
  6187.4  224.16  6210.2  224.97    6291  223.03  6314.1  220.96  6364.1  221.01
  6394.9  224.14  6401.4  222.02  6417.2  221.71  6556.5  225.21  6752.7  233.96
#Mann= 3 ,-1 , 0
  3298.2     .06       0  4967.1     .06       0  5023.7     .06       0
Bank Sta=4967.1,5023.7
XS Rating Curve= 0 ,0
Exp/Cntr=0.3,0.1

Type RM Length L Ch R = 1 ,28171   ,800,800,800
BEGIN DESCRIPTION:
CANEY CREEK 42.0
END DESCRIPTION:
XS GIS Cut Line= 3
      3725617.87     10121661.09      3724397.77     10120213.75
      3722517.89     10119511.09
#Sta/Elev= 30
  3095.5   240.9    3472  226.67  3691.7   215.5  3784.1  213.37  4358.8  214.37
  4514.9  212.69    4749  214.76  4968.7  214.44    4983  213.38    4987  208.19
  4989.6  206.96  5008.6  206.96  5012.8  214.59  5031.1  215.74  5324.6  212.96
  5520.7  216.77  5636.5  216.38  5746.4  218.52  5948.4  217.68    6009  218.84
  6014.3  220.83  6064.3   224.6    6088   224.1  6124.8  218.13  6301.5  218.32
  6333.5  221.54  6429.6  221.73    6587  225.54  6636.4  227.41  6995.4  245.76
#Mann= 5 ,-1 , 0
  3095.5     .06       0  4968.7     .06       0  5012.8     .06       0
    6587     .12       0  6636.4     .06       0
Bank Sta=4968.7,5012.8
XS Rating Curve= 0 ,0
Exp/Cntr=0.3,0.1

Type RM Length L Ch R = 1 ,27371   ,467,467,467
BEGIN DESCRIPTION:
CANEY CREEK 41.0
END DESCRIPTION:
XS GIS Cut Line= 3
      3726667.84     10122011.05       3724479.4     10119789.39
      3723917.86     10118811.09
#Sta/Elev= 30
  1881.5  266.45  2121.9  259.07  2157.3  259.15  2178.4  256.88  2312.8  250.73
  2418.9   243.6    2525  244.49  2602.7  235.09    2631   233.4  2807.9   231.1
  2906.8  227.82  3069.5  226.55  3514.9  215.32  3628.1  213.48  3896.8  212.54
    4803  213.97  4978.7  214.32    4988  207.35    5007  207.35  5014.3  211.28
  5035.8  213.78  5100.7  213.11  5153.7   213.1  5182.5  214.48  5416.9  212.25
  5432.7  216.14  5593.8  215.57  5851.2  221.76  6012.3  230.03    6128  238.69
#Mann= 5 ,-1 , 0
  1881.5     .06       0    4803      .1       0  4978.7     .09       0
  5035.8      .1       0  5100.7     .06       0
Bank Sta=4978.7,5035.8
XS Rating Curve= 0 ,0
Exp/Cntr=0.3,0.1

Type RM Length L Ch R = 1 ,26904   ,1233,1233,1233
BEGIN DESCRIPTION:
CANEY CREEK 40.0
END DESCRIPTION:
XS GIS Cut Line= 4
      3726317.82     10121111.04      3724840.48     10119762.36
      3724740.65     10119549.69      3723917.86     10118761.08
#Sta/Elev= 30
    2881  234.99  2994.1  230.16  3270.4  222.27  3298.8  222.48    3490  217.06
  3779.8  213.15    4042  212.16  4105.5  212.19  4112.9  213.04  4133.9  212.12
  4331.8  212.76  4402.7  211.64  4629.1  213.42  4957.2  213.76  4982.2  213.35
  4990.6  211.34  5003.9  205.68  5022.9  205.68  5026.4  211.27  5036.2  213.28
  5081.6   212.9  5110.2  210.65  5230.6  213.65    5388  213.41  5421.5  212.26
  5449.8  214.06  5782.2   217.7  5930.7  221.59  6086.3  229.17    6256  241.06
#Mann= 5 ,-1 , 0
    2881     .06       0  4957.2      .1       0  4982.2     .09       0
  5036.2      .1       0    5388     .06       0
Bank Sta=4982.2,5036.2
XS Rating Curve= 0 ,0
Exp/Cntr=0.3,0.1

Type RM Length L Ch R = 1 ,25671   ,551,551,551
BEGIN DESCRIPTION:
CANEY CREEK 39.0
END DESCRIPTION:
XS GIS Cut Line= 3
      3726567.83     10120861.04      3725387.35     10119536.67
      3724267.85     10118461.07
#Sta/Elev= 30
  3228.6  232.77  3335.2  228.49  3561.7  222.25  3858.6  215.72  3986.5  214.58
  4043.3  212.81  4227.3  212.38  4368.6  214.05  4474.8  212.49  4637.8  214.18
  4723.1  213.24    4744  211.77  4802.2  210.89  4886.1  212.51  4963.9  212.16
  4978.1  211.02  4996.8  206.37  5015.8  206.37  5020.4  210.91  5027.6  212.26
  5062.9   213.4  5374.2  212.76  5459.1  213.51  5480.2  212.72  6041.1  213.58
  6187.4  213.53  6279.3  217.31  6304.7  219.32  6507.5  232.86  6555.2  235.03
#Mann= 7 ,-1 , 0
  3228.6     .06       0  4802.2      .1       0  4963.9     .09       0
  5027.6     .06       0  6041.1      .1       0  6304.7     .12       0
  6507.5     .06       0
Bank Sta=4963.9,5027.6
XS Rating Curve= 0 ,0
Exp/Cntr=0.3,0.1

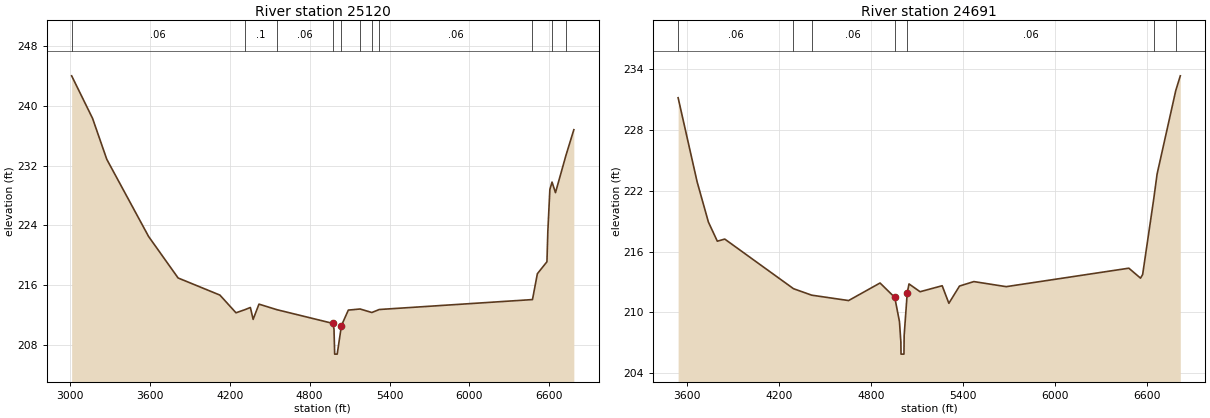
Type RM Length L Ch R = 1 ,25120   ,429,429,429
BEGIN DESCRIPTION:
CANEY CREEK 38.0
END DESCRIPTION:
XS GIS Cut Line= 3
      3727017.84     10120911.05      3725804.02     10119315.32
      3724317.83     10118361.06
#Sta/Elev= 30
  3012.7  244.01  3169.7  238.32  3276.5  232.84  3590.6  222.51  3812.1  216.96
  4126.1  214.67  4246.7   212.3  4312.3  212.71  4354.8  213.01  4375.6  211.42
  4419.3  213.46  4553.2  212.72  4974.5  210.88  4982.8  210.11  4987.8  206.77
  5006.8  206.77  5038.8   210.6  5090.3  212.66  5178.5  212.81  5266.8  212.34
  5322.5  212.74  6473.2  214.07    6510  217.53  6581.8  219.13  6588.6  223.21
  6603.8   228.8  6620.1  229.79    6646  228.38  6723.8  233.32  6783.8   236.8
#Mann= 11 ,-1 , 0
  3012.7     .06       0  4312.3      .1       0  4553.2     .06       0
  4974.5     .09       0  5038.8     .06       0  5178.5     .06       0
  5266.8      .1       0  5322.5     .06       0  6473.2      .1       0
  6620.1     .12       0  6723.8     .06       0
Bank Sta=4974.5,5038.8
XS Rating Curve= 0 ,0
Exp/Cntr=0.3,0.1

Type RM Length L Ch R = 1 ,24691   ,525,525,525
BEGIN DESCRIPTION:
CANEY CREEK 37.0
END DESCRIPTION:
XS GIS Cut Line= 4
      3727217.89      10119861.1      3726047.07     10119150.38
      3725990.65     10118994.13      3724389.06     10118308.36
#Sta/Elev= 30
  3541.5  231.16  3665.6  222.87  3739.2  218.91  3797.4  217.02  3845.9  217.23
  4294.6  212.34  4413.8   211.7  4654.2  211.17  4859.6   212.9  4955.6  211.48
  4986.3   209.1  4995.5  207.09  4996.6  205.89  5015.6  205.89    5017  207.73
    5037  211.91  5048.6  212.81  5120.8  212.04  5265.2  212.63  5308.8   210.9
  5378.3   212.6  5471.9  213.04  5683.1  212.54  6483.6  214.36  6559.7  213.38
  6573.7  213.74  6646.4  221.22    6668  223.64  6789.7  231.86  6819.5  233.32
#Mann= 7 ,-1 , 0
  3541.5     .06       0  4294.6     .12       0  4413.8     .06       0
  4955.6     .06       0    5037     .06       0  6646.4     .12       0
  6789.7     .06       0
Bank Sta=4955.6,5037
XS Rating Curve= 0 ,0
Exp/Cntr=0.3,0.1