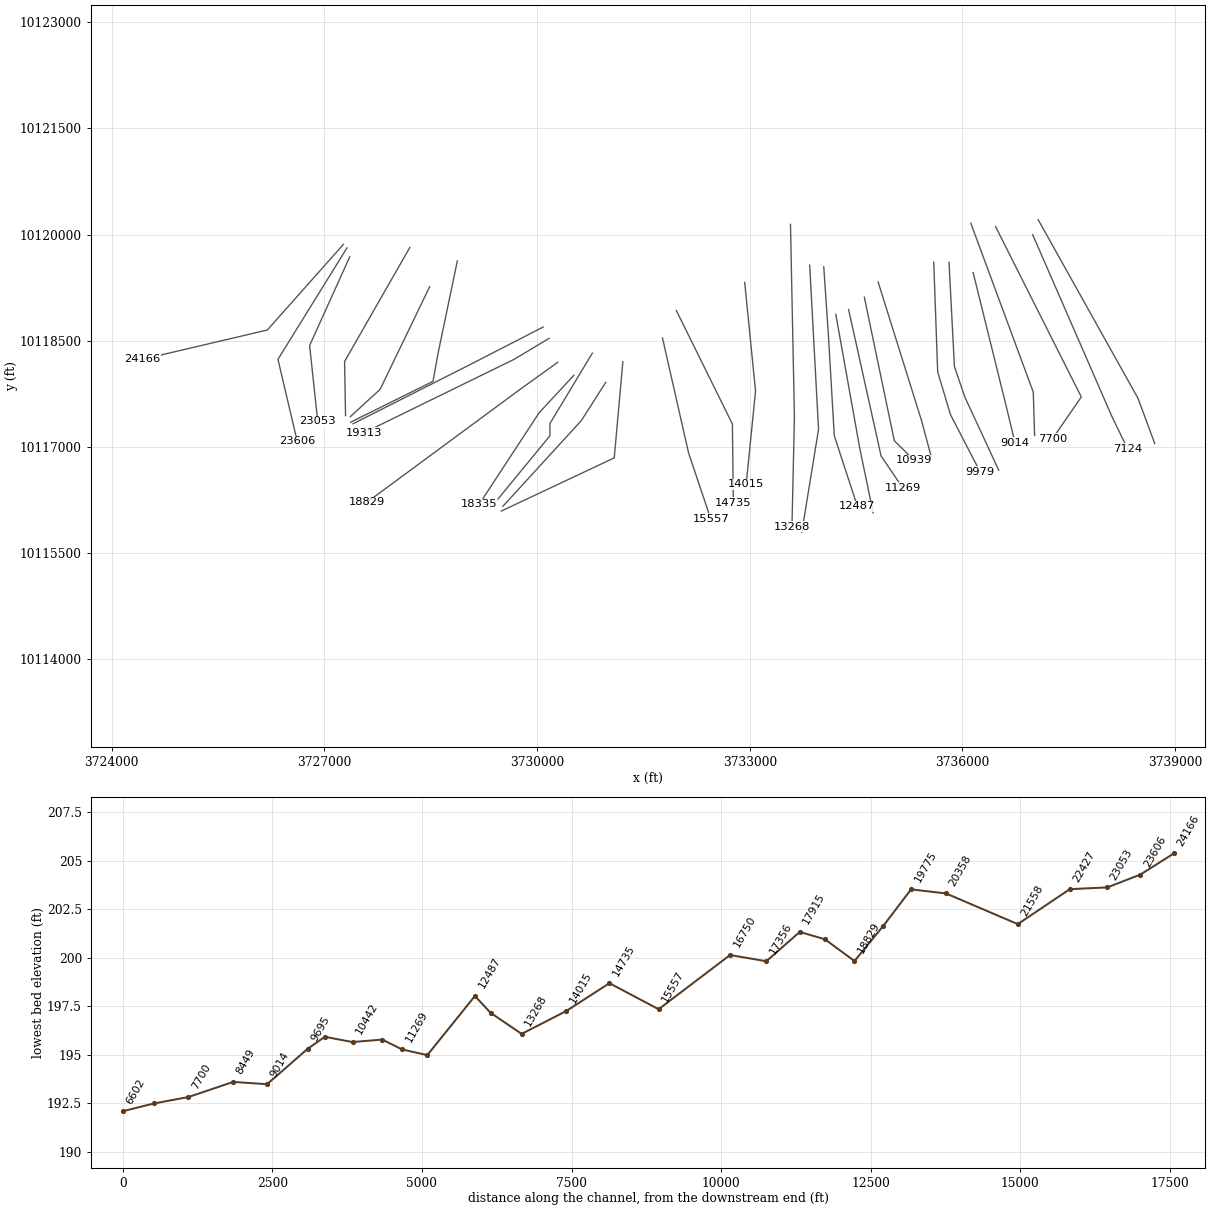
HEC-RAS study CANEY CREEK.prj: CANEY CREEK Base Level Engineering

--- CANEY CREEK.g01 (geometry) --- (continued)

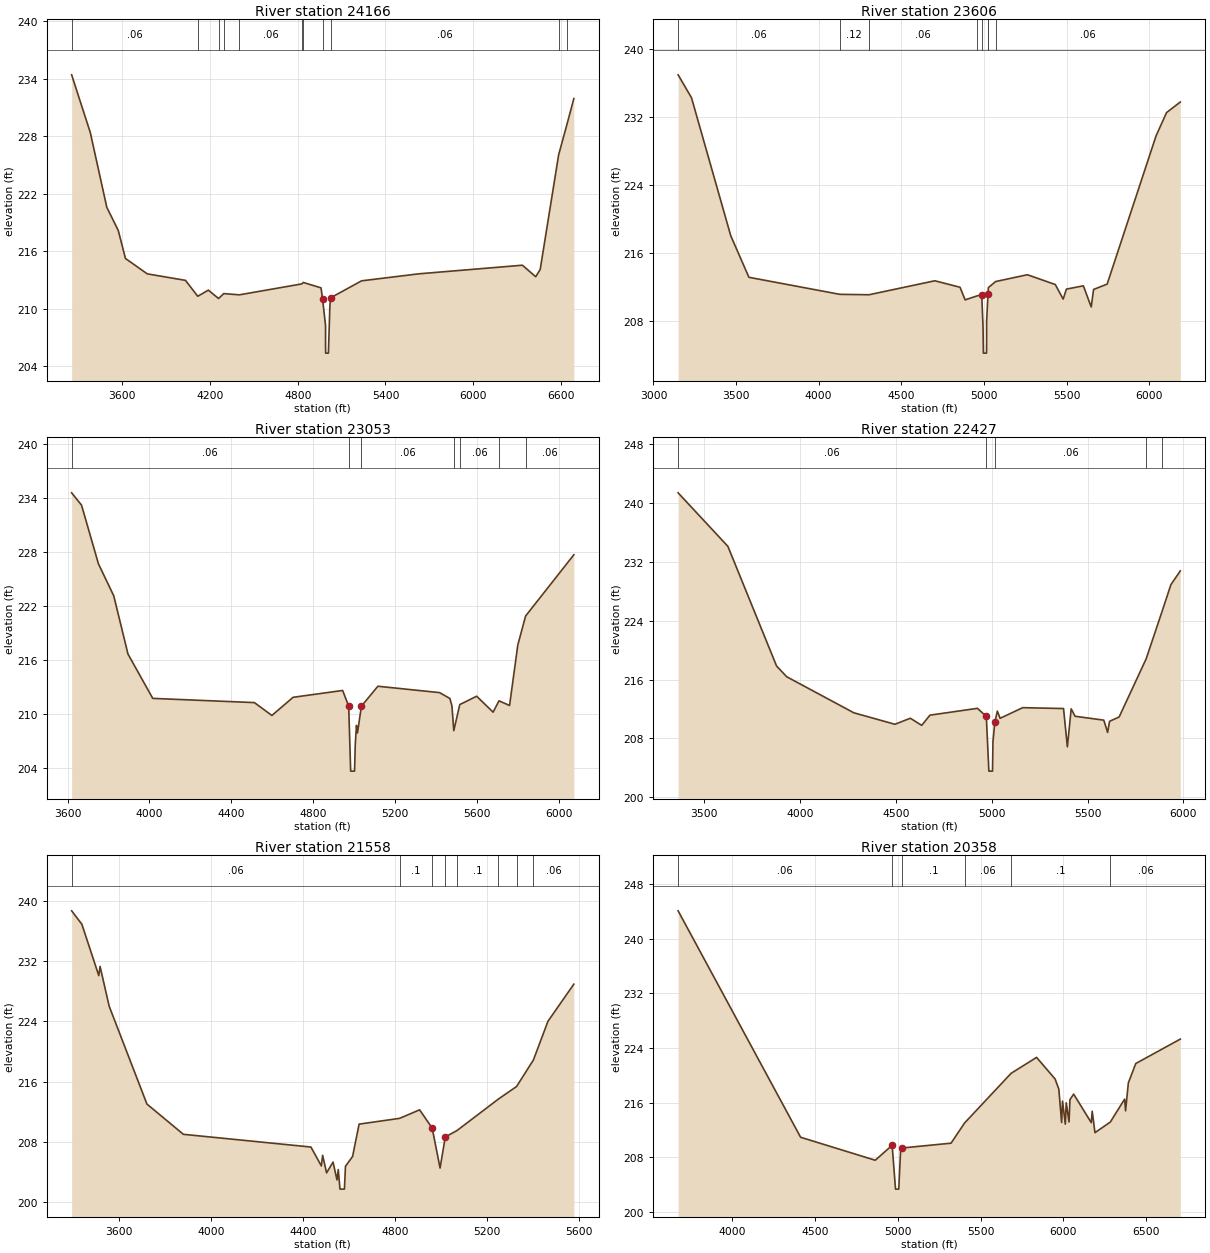
Type RM Length L Ch R = 1 ,24166   ,560,560,560
BEGIN DESCRIPTION:
CANEY CREEK 36.0
END DESCRIPTION:
XS GIS Cut Line= 3
      3727267.86     10119861.08      3726194.64     10118651.25
      3724423.85      10118234.6
#Sta/Elev= 30
  3252.8   234.4  3380.4  228.38  3493.4  220.58  3571.9  218.16  3621.2  215.24
  3770.1  213.64  4031.8  212.96  4115.5   211.3  4188.2  211.94    4258  211.07
  4293.7  211.58  4400.4  211.45  4827.9  212.59    4838  212.74  4959.2  212.18
  4969.5  211.06    4990  208.27  4990.3  205.97  4990.8  205.37  5009.8  205.37
  5019.7  210.24  5024.8  211.14  5236.6  212.91    5627  213.64  6337.2  214.54
  6428.3  213.34  6459.1   214.1  6585.2  226.05  6645.8  229.44  6689.2  231.92
#Mann= 11 ,-1 , 0
  3252.8     .06       0  4115.5     .12       0    4258     .06       0
  4293.7     .12       0  4400.4     .06       0  4827.9      .1       0
    4838     .06       0  4969.5     .06       0  5024.8     .06       0
  6585.2     .12       0  6645.8     .06       0
Bank Sta=4969.5,5024.8
XS Rating Curve= 0 ,0
Exp/Cntr=0.3,0.1

Type RM Length L Ch R = 1 ,23606   ,553,553,553
BEGIN DESCRIPTION:
CANEY CREEK 35.0
END DESCRIPTION:
XS GIS Cut Line= 3
      3727317.84     10119811.06      3726344.37     10118237.18
      3726615.65     10117080.06
#Sta/Elev= 30
  3149.4  236.94  3230.4  234.25  3467.9  218.06  3577.8  213.18  4127.8  211.18
  4304.3  211.13    4703  212.77  4855.5  212.01  4886.3  210.53    4956  210.98
  4986.7  211.15  4994.8   207.3  4996.8  204.28  5015.8  204.28  5016.3  205.18
  5016.5  208.06  5024.8211.2108  5026.8  211.97  5070.8  212.68  5263.1  213.48
    5432  212.33  5479.6  210.62  5499.3  211.79  5601.8  212.18  5649.4   209.7
  5663.6  211.75  5745.8  212.38  6041.7  229.77  6105.3  232.51  6188.5  233.75
#Mann= 8 ,-1 , 0
  3149.4     .06       0  4127.8     .12       0  4304.3     .06       0
    4956      .1       0  4986.7     .09       0  5024.8     .07       0
  5026.8      .1       0  5070.8     .06       0
Bank Sta=4986.7,5024.8
XS Rating Curve= 0 ,0
Exp/Cntr=0.3,0.1

Type RM Length L Ch R = 1 ,23053   ,626,626,626
BEGIN DESCRIPTION:
CANEY CREEK 34.0
END DESCRIPTION:
XS GIS Cut Line= 3
      3727356.96     10119685.09        3726791.     10118431.63
      3726905.58     10117358.74
#Sta/Elev= 30
  3620.2  234.57  3668.5   233.2  3751.2  226.67  3826.1  223.11  3895.5  216.64
  4016.6  211.71  4513.4  211.24  4598.9  209.81  4702.4  211.83  4944.6  212.59
  4974.2  210.85  4983.8  203.62  5002.8  203.62  5006.1  206.49  5012.1   208.7
  5017.1  207.87  5036.3  210.84  5116.8  213.06  5418.5  212.35  5468.7   211.7
  5478.8  210.87  5487.8  208.12  5517.1  211.02  5599.5  211.95  5679.9  210.18
  5708.9  211.44  5760.4  210.92  5800.6  217.64  5838.8  220.87  6074.5  227.68
#Mann= 7 ,-1 , 0
  3620.2     .06       0  4974.2     .06       0  5036.3     .06       0
  5487.8      .1       0  5517.1     .06       0  5708.9      .1       0
  5838.8     .06       0
Bank Sta=4974.2,5036.3
XS Rating Curve= 0 ,0
Exp/Cntr=0.3,0.1

Type RM Length L Ch R = 1 ,22427   ,869,869,869
BEGIN DESCRIPTION:
CANEY CREEK 33.0
END DESCRIPTION:
XS GIS Cut Line= 3
       3728204.2     10119817.07      3727284.05     10118205.94
      3727297.94     10117442.04
#Sta/Elev= 30
  3364.5  241.42  3624.2  234.13  3878.1  217.84  3930.9  216.38  4281.2  211.47
  4495.3  209.91  4575.9  210.73    4635  209.76  4678.2  211.15  4926.1  212.08
  4972.1  210.97  4985.4  203.53  5004.4  203.53  5006.7  207.53  5016.5  210.21
  5029.7   211.7  5043.9  210.72    5162  212.17  5374.8  212.05  5394.8  206.84
  5414.8  212.01  5434.8     211  5584.8  210.47  5604.8   208.8  5614.8  210.31
  5664.8   210.9  5805.7  218.81  5888.1  225.22  5934.9  228.92  5983.9  230.79
#Mann= 5 ,-1 , 0
  3364.5     .06       0  4972.1     .06       0  5016.5     .06       0
  5805.7      .1       0  5888.1     .06       0
Bank Sta=4972.1,5016.5
XS Rating Curve= 0 ,0
Exp/Cntr=0.3,0.1

Type RM Length L Ch R = 1 ,21558   ,1200,1200,1200
BEGIN DESCRIPTION:
CANEY CREEK 31.0
END DESCRIPTION:
XS GIS Cut Line= 3
      3728484.03     10119262.16      3727785.23     10117812.48
      3727364.21     10117426.19
#Sta/Elev= 30
  3396.2  238.69  3440.6  236.91    3514  230.09  3519.6  231.31  3559.2  226.02
  3723.1  213.03  3881.4  209.01  4435.3  207.32  4480.5  204.81  4486.1  206.22
  4503.2  203.89  4531.3  205.32  4548.4  202.95  4553.9  204.33  4561.4  201.73
  4580.7  201.73  4585.2  204.76  4616.2  206.07  4644.4  210.36  4820.3  211.13
  4907.2  212.26  4961.9  209.83    4996  204.53  5018.7  208.66  5069.6  209.51
  5249.7   213.7  5328.3  215.36  5401.5  218.89  5464.5  224.02  5576.9  228.95
#Mann= 8 ,-1 , 0
  3396.2     .06       0  4820.3      .1       0  4961.9     .06       0
  5018.7     .06       0  5069.6      .1       0  5249.7     .06       0
  5328.3      .1       0  5401.5     .06       0
Bank Sta=4961.9,5018.7
XS Rating Curve= 0 ,0
Exp/Cntr=0.3,0.1

Type RM Length L Ch R = 1 ,20358   ,583,583,583
BEGIN DESCRIPTION:
CANEY CREEK 29.0
END DESCRIPTION:
XS GIS Cut Line= 4
      3728874.63     10119626.71      3728603.62     10118326.86
      3728531.37     10117926.05      3727368.56     10117348.07
#Sta/Elev= 30
  3672.2  244.08  4412.1  210.91  4862.9  207.54  4965.1  209.73  4985.5  203.31
    5005  203.31    5016  208.87  5026.2  209.34  5320.9  210.04  5402.7     213
  5683.9  220.28  5837.6  222.61  5949.6  219.44    5972  217.96  5988.8  213.07
  5994.4   216.2  6011.2  212.82  6016.8  215.96  6033.6  213.15  6039.2  216.42
  6061.6  217.23    6168  213.05  6173.6  214.72  6190.4  211.58  6283.2  213.14
  6369.6   216.5  6375.2  214.78    6392  218.88  6436.8  221.71  6705.8  225.29
#Mann= 6 ,-1 , 0
  3672.2     .06       0  4965.1     .09       0  5026.2      .1       0
  5402.7     .06       0  5683.9      .1       0  6283.2     .06       0
Bank Sta=4965.1,5026.2
XS Rating Curve= 0 ,0
Exp/Cntr=0.3,0.1

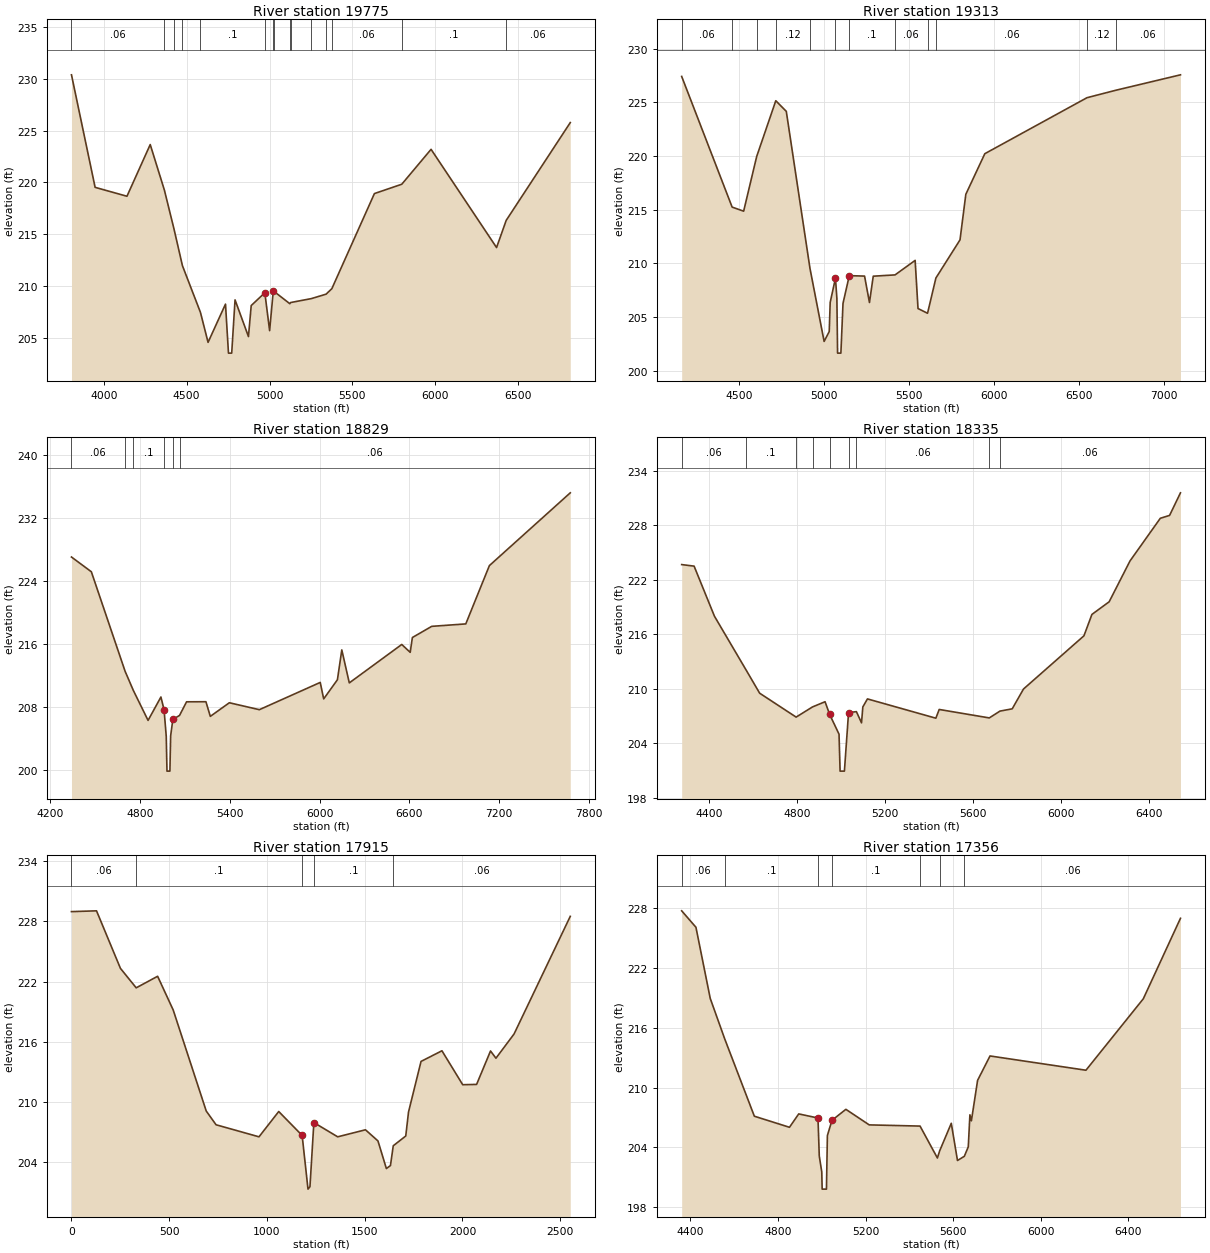
Type RM Length L Ch R = 1 ,19775   ,462,462,462
BEGIN DESCRIPTION:
CANEY CREEK 28.0
END DESCRIPTION:
XS GIS Cut Line= 3
      3730085.56     10118693.55      3729065.61     10118168.38
      3727403.31     10117326.38
#Sta/Elev= 30
  3804.8  230.38  3947.5  219.52  4139.7  218.66  4280.1  223.65  4365.7  219.25
  4423.6   215.5  4474.5  211.96  4583.3  207.45  4629.2  204.56  4734.4  208.25
  4752.4  203.52  4771.9  203.52    4792  208.66    4873  205.12  4889.6  208.11
  4971.9  209.35  5000.7  205.69  5022.9  209.53  5028.5  209.46  5122.7  208.29
  5126.9   208.4  5252.1  208.78  5341.5  209.21  5376.3  209.74  5633.3  218.92
  5798.4  219.82  5975.2  223.19  6370.5  213.71  6428.6  216.33  6815.4  225.77
#Mann= 15 ,-1 , 0
  3804.8     .06       0  4365.7     .12       0  4423.6     .06       0
  4474.5     .12       0  4583.3      .1       0  4971.9     .09       0
  5022.9     .07       0  5028.5      .1       0  5122.7     .12       0
  5126.9      .1       0  5252.1     .12       0  5341.5      .1       0
  5376.3     .06       0  5798.4      .1       0  6428.6     .06       0
Bank Sta=4971.9,5022.9
XS Rating Curve= 0 ,0
Exp/Cntr=0.3,0.1

Type RM Length L Ch R = 1 ,19313   ,484,484,484
BEGIN DESCRIPTION:
Mapping XS 05857dad
END DESCRIPTION:
XS GIS Cut Line= 3
      3730168.05     10118532.97      3729677.59     10118237.83
      3727551.89     10117196.67
#Sta/Elev= 30
  4159.9   227.4  4457.2  215.24  4525.1  214.86  4601.9  219.95  4714.5  225.14
  4776.4  224.15  4915.9  209.54  4999.3  202.74  5029.5  203.66    5035  206.36
  5066.1  208.63  5074.5  206.74  5078.6  201.65  5098.1  201.65  5110.6  206.28
  5147.6  208.86  5237.6  208.82  5266.5  206.36  5288.8  208.81  5417.3  208.93
  5535.7  210.28  5552.6   205.8  5608.8  205.36    5658  208.64  5800.1  212.19
  5834.4  216.43  5946.3  220.21  6548.3  225.42  6719.8  226.12  7099.3  227.55
#Mann= 12 ,-1 , 0
  4159.9     .06       0  4457.2     .12       0  4601.9     .06       0
  4714.5     .12       0  4915.9      .1       0  5066.1     .09       0
  5147.6      .1       0  5417.3     .06       0  5608.8     .12       0
    5658     .06       0  6548.3     .12       0  6719.8     .06       0
Bank Sta=5066.1,5147.6
XS Rating Curve= 0 ,0
Exp/Cntr=0.3,0.1

Type RM Length L Ch R = 1 ,18829   ,494,494,494
BEGIN DESCRIPTION:
CANEY CREEK 27.0
END DESCRIPTION:
XS GIS Cut Line= 3
      3730289.59     10118194.44      3729754.85     10117809.14
      3727602.95     10116219.61
#Sta/Elev= 30
  4340.9  227.01  4473.7  225.14  4699.1  212.52  4754.3  210.08  4852.9  206.27
  4938.8  209.24  4959.7  207.63  4974.4  204.25  4979.3  199.83  4998.9  199.83
  5003.8   204.3  5018.5   206.4  5063.2   206.9  5110.3  208.63  5239.7  208.64
    5269  206.78  5396.3  208.51  5596.7  207.63  6003.8  211.09  6026.9     209
  6118.7  211.43    6148  215.22  6198.1  211.03  6548.8  215.91  6605.2  214.91
  6619.8  216.79  6749.2  218.21  6976.8  218.52  7134.6  225.92  7675.3  235.16
#Mann= 6 ,-1 , 0
  4340.9     .06       0  4699.1     .12       0  4754.3      .1       0
  4959.7     .09       0  5018.5      .1       0  5063.2     .06       0
Bank Sta=4959.7,5018.5
XS Rating Curve= 0 ,0
Exp/Cntr=0.3,0.1

Type RM Length L Ch R = 1 ,18335   ,420,420,420
BEGIN DESCRIPTION:
CANEY CREEK 26.0
END DESCRIPTION:
XS GIS Cut Line= 3
      3730517.87     10118011.09      3730026.81     10117480.03
      3729182.83     10116189.27
#Sta/Elev= 30
  4276.7  223.66  4333.1  223.49  4425.6  217.98    4569  212.08  4630.8  209.52
  4796.5  206.89    4871  208.01  4927.9  208.58  4948.9  207.18  4991.4  205.01
  4996.2  200.95  5015.8  200.95  5034.6  207.38  5070.3  207.49  5093.5  206.26
  5099.5  208.01  5120.5  208.89  5431.2  206.77  5446.3  207.73  5673.8   206.8
  5722.3  207.55    5778   207.8  5829.3  209.98  6103.8  215.83    6140  218.18
  6218.3  219.57    6313  224.06  6450.6  228.75  6492.8  229.07  6542.2  231.55
#Mann= 9 ,-1 , 0
  4276.7     .06       0    4569      .1       0  4796.5     .06       0
    4871      .1       0  4948.9     .09       0  5034.6      .1       0
  5070.3     .06       0  5673.8      .1       0  5722.3     .06       0
Bank Sta=4948.9,5034.6
XS Rating Curve= 0 ,0
Exp/Cntr=0.3,0.1

Type RM Length L Ch R = 1 ,17915   ,559,559,559
BEGIN DESCRIPTION:
CANEY CREEK 25.0
END DESCRIPTION:
XS GIS Cut Line= 4
      3730779.55     10118324.71      3730181.06     10117330.71
      3730181.06      10117157.1      3729408.49     10116215.26
#Sta/Elev= 30
       0  228.97   128.1  229.05   250.4  223.32   331.1  221.38   440.7  222.53
   520.4  219.17   689.3  209.11   739.6  207.74   959.2  206.54  1060.2  209.06
  1179.9  206.68  1209.9  201.33  1219.9  201.57  1239.9  207.96  1361.8  206.54
  1503.9  207.24  1567.8  206.13  1610.8  203.38  1631.7  203.68    1646  205.65
  1709.9  206.62  1724.2  209.02  1788.1  214.05    1895  215.11  2001.3  211.73
  2072.3  211.76  2143.6  215.09  2171.3  214.37  2263.9  216.78  2551.5   228.5
#Mann= 5 ,-1 , 0
       0     .06       0   331.1      .1       0  1179.9     .09       0
  1239.9      .1       0    1646     .06       0
Bank Sta=1179.9,1239.9
XS Rating Curve= 0 ,0
Exp/Cntr=0.3,0.1

Type RM Length L Ch R = 1 ,17356   ,606,606,606
BEGIN DESCRIPTION:
CANEY CREEK 24.0
END DESCRIPTION:
XS GIS Cut Line= 3
      3730967.86     10117911.08      3730623.73     10117371.23
      3729517.88     10116161.11
#Sta/Elev= 30
  4359.8  227.72    4425  226.07  4490.3  218.94  4556.5  214.88  4691.9  207.13
  4852.4  206.02  4894.7  207.36  4982.7  206.95  4988.6  203.14    5000  201.54
  5001.8  199.82  5021.4  199.82  5025.7  205.19  5046.7  206.72  5110.2  207.82
  5216.9  206.26  5449.2  206.14  5528.4  202.94  5538.7  203.65  5591.9  206.42
  5620.2  202.69  5651.5  203.11  5669.6  204.06    5677  207.27  5683.8  206.67
  5712.1  210.72  5768.9  213.17  6207.3  211.74  6469.4   218.9  6639.3  226.97
#Mann= 7 ,-1 , 0
  4359.8     .06       0  4556.5      .1       0  4982.7     .09       0
  5046.7      .1       0  5449.2     .06       0  5538.7      .1       0
  5651.5     .06       0
Bank Sta=4982.7,5046.7
XS Rating Curve= 0 ,0
Exp/Cntr=0.3,0.1

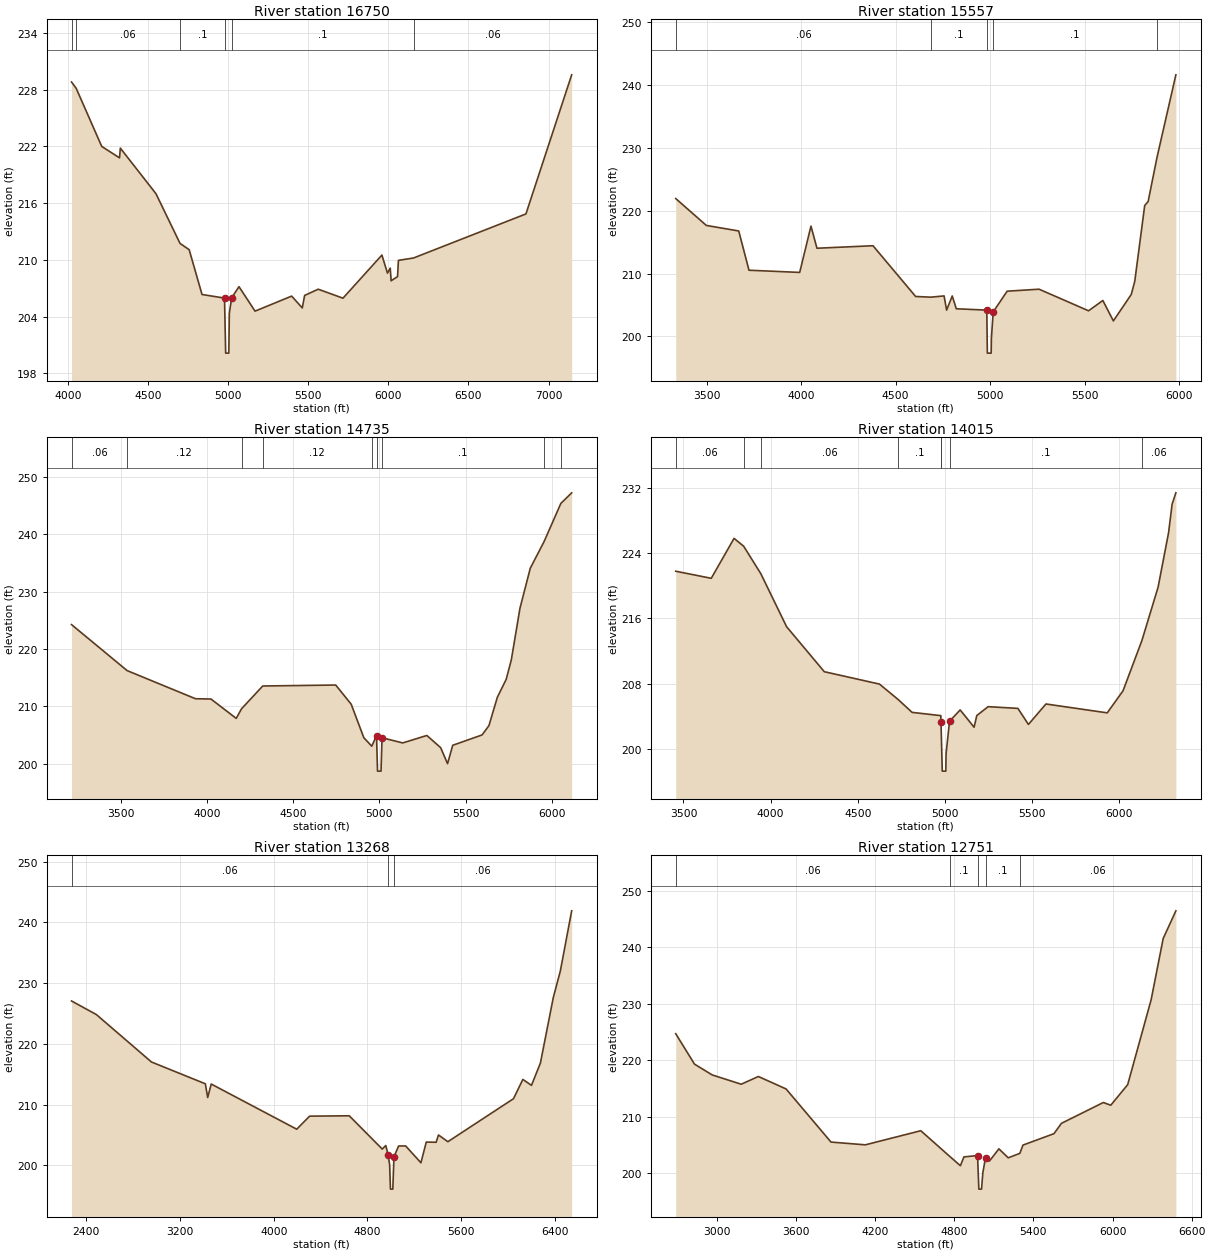
Type RM Length L Ch R = 1 ,16750   ,1193,1193,1193
BEGIN DESCRIPTION:
CANEY CREEK 23.0
END DESCRIPTION:
XS GIS Cut Line= 3
       3731209.7     10118203.09      3731088.18      10116844.6
       3729495.3     10116093.73
#Sta/Elev= 30
  4019.9  228.81  4049.1  228.14  4208.4     222  4319.7  220.79  4324.7  221.82
  4547.4     217  4697.8  211.74  4754.8  211.08  4835.2  206.34  4975.7  205.96
  4982.9  200.14  5002.5  200.14  5005.8  204.36 5020.37 205.991  5066.1  207.17
  5166.5  204.58  5395.2  206.17  5461.6  204.92  5476.2  206.24  5561.1   206.9
  5715.8  205.95  5959.1  210.51  5993.9   208.6  6011.2  209.13  6016.7  207.79
  6056.8  208.23  6062.3  209.95  6156.6   210.2    6859  214.86  7144.8  229.57
#Mann= 6 ,-1 , 0
  4019.9     .12       0  4049.1     .06       0  4697.8      .1       0
  4975.7     .09       0 5020.37      .1       0  6156.6     .06       0
Bank Sta=4975.7,5020.37
XS Rating Curve= 0 ,0
Exp/Cntr=0.3,0.1

Type RM Length L Ch R = 1 ,15557   ,822,822,822
BEGIN DESCRIPTION:
CANEY CREEK 22.0
END DESCRIPTION:
XS GIS Cut Line= 3
      3731768.74     10118538.99      3732136.79     10116914.04
      3732448.86     10115984.75
#Sta/Elev= 30
  3336.6  221.96  3498.5  217.68  3669.9   216.8  3724.1  210.55  3992.4   210.2
  4052.2  217.57  4083.8  214.05  4380.3  214.45  4605.9  206.37  4686.6  206.26
  4756.5  206.46  4769.9   204.2  4799.7  206.45  4821.2  204.41  4982.5   204.2
  4985.4  197.35  5005.7  197.35  5006.9  199.72  5016.4  203.91  5090.2  207.21
    5259  207.53  5520.9  204.09  5596.6  205.73  5652.3  202.48  5746.9  206.69
  5765.4  208.78  5818.1  220.86  5836.2  221.48  5882.8  228.47    5983  241.66
#Mann= 5 ,-1 , 0
  3336.6     .06       0  4686.6      .1       0  4982.5     .09       0
  5016.4      .1       0  5882.8     .12       0
Bank Sta=4982.5,5016.4
XS Rating Curve= 0 ,0
Exp/Cntr=0.3,0.1

Type RM Length L Ch R = 1 ,14735   ,720,720,720
BEGIN DESCRIPTION:
CANEY CREEK 21.0
END DESCRIPTION:
XS GIS Cut Line= 3
      3731963.17     10118927.95      3732754.84     10117323.76
      3732767.85     10116211.04
#Sta/Elev= 30
  3213.7  224.25    3536  216.23  3932.8  211.32  4022.6  211.27  4169.2  207.89
  4200.1  209.57    4323  213.54  4746.5  213.71  4836.3  210.36  4909.3  204.53
  4955.5  203.04  4983.3  204.89  4988.9  198.69  5009.2  198.69  5015.3  204.51
  5135.3  203.61  5275.3  204.91  5355.3  202.78  5395.3  199.99  5425.3   203.2
  5595.3     205  5635.3  206.62    5684  211.56  5735.3  214.69  5765.3  218.11
  5815.4  227.11  5875.4   234.1  5954.3  238.67  6052.6  245.39  6115.4  247.24
#Mann= 9 ,-1 , 0
  3213.7     .06       0    3536     .12       0  4200.1      .1       0
    4323     .12       0  4955.5      .1       0  4983.3     .09       0
  5015.3      .1       0  5954.3     .12       0  6052.6     .06       0
Bank Sta=4983.3,5015.3
XS Rating Curve= 0 ,0
Exp/Cntr=0.3,0.1

Type RM Length L Ch R = 1 ,14015   ,747,747,747
BEGIN DESCRIPTION:
CANEY CREEK 20.0
END DESCRIPTION:
XS GIS Cut Line= 3
      3732928.45     10119323.78      3733081.23     10117789.04
      3732949.28     10116469.55
#Sta/Elev= 30
  3455.7  221.79  3659.4  220.92  3790.1  225.82  3845.2  224.86  3943.6  221.49
  4091.5  214.98  4307.7  209.46  4624.2  207.94    4731  206.05  4811.3  204.47
  4975.9  204.07 4976.88203.3493  4984.3  197.26  5004.6  197.26    5006   199.4
  5026.1  203.38  5086.9  204.77  5166.8  202.65  5182.3  204.08  5247.2  205.17
  5418.1  204.96  5478.4  202.99  5578.9   205.5  5930.6  204.41  6021.1  207.12
  6129.3  213.29  6222.1  219.83  6282.4  226.54  6302.5  230.02  6324.1  231.41
#Mann= 8 ,-1 , 0
  3455.7     .06       0  3845.2     .12       0  3943.6     .06       0
    4731      .1       0  4975.9     .07       0 4976.88     .09       0
  5026.1      .1       0  6129.3     .06       0
Bank Sta=4976.88,5026.1
XS Rating Curve= 0 ,0
Exp/Cntr=0.3,0.1

Type RM Length L Ch R = 1 ,13268   ,517,517,517
BEGIN DESCRIPTION:
CANEY CREEK 19.0
END DESCRIPTION:
XS GIS Cut Line= 3
      3733574.29      10120143.2      3733629.84     10117427.93
      3733595.16     10115874.26
#Sta/Elev= 30
  2273.3  227.07  2485.5  224.83  2955.6  217.02  3415.7  213.43  3435.7  211.17
  3465.7  213.39  4195.8  205.95  4305.9   208.1  4644.1  208.16    4926  202.68
    4956  203.26    4976  201.75  4989.1  200.09  4995.9  196.08  5016.2  196.08
    5026  201.41    5066  203.19    5126  203.19  5256.1  200.42  5301.8  203.83
  5386.1   203.8  5406.1     205  5486.1  203.89  6046.3  210.97  6126.3  214.15
    6200  213.17  6276.3  216.85  6386.3  227.64  6446.4  232.01  6543.2  241.92
#Mann= 3 , 0 , 0
  2273.3     .06       0    4976     .09       0    5026     .06       0
Bank Sta=4976,5026
XS Rating Curve= 0 ,0
Exp/Cntr=0.3,0.1

Type RM Length L Ch R = 1 ,12751   ,264,264,264
BEGIN DESCRIPTION:
CANEY CREEK 18.0
END DESCRIPTION:
XS GIS Cut Line= 3
      3733845.12     10119566.84      3733970.12     10117247.38
      3733734.01     10115795.99
#Sta/Elev= 30
  2687.1   224.7  2829.4  219.31  2963.3   217.4  3183.6  215.75  3313.8  217.12
  3524.1  214.91  3864.6   205.5    4125  205.01  4545.6  207.51  4767.2  202.92
    4846  201.31  4872.9  202.87  4976.2  203.11    4986  197.16  5006.4  197.16
  5016.3  200.06  5036.6  202.75    5067  202.15  5137.9   204.3  5208.8  202.71
  5297.2   203.5  5320.3  204.96  5555.9  206.99  5612.4  208.82  5930.2  212.51
  5986.6  212.03  6114.8  215.67  6292.9  230.73  6384.1  241.57  6480.4  246.48
#Mann= 5 ,-1 , 0
  2687.1     .06       0  4767.2      .1       0  4976.2     .09       0
  5036.6      .1       0  5297.2     .06       0
Bank Sta=4976.2,5036.6
XS Rating Curve= 0 ,0
Exp/Cntr=0.3,0.1

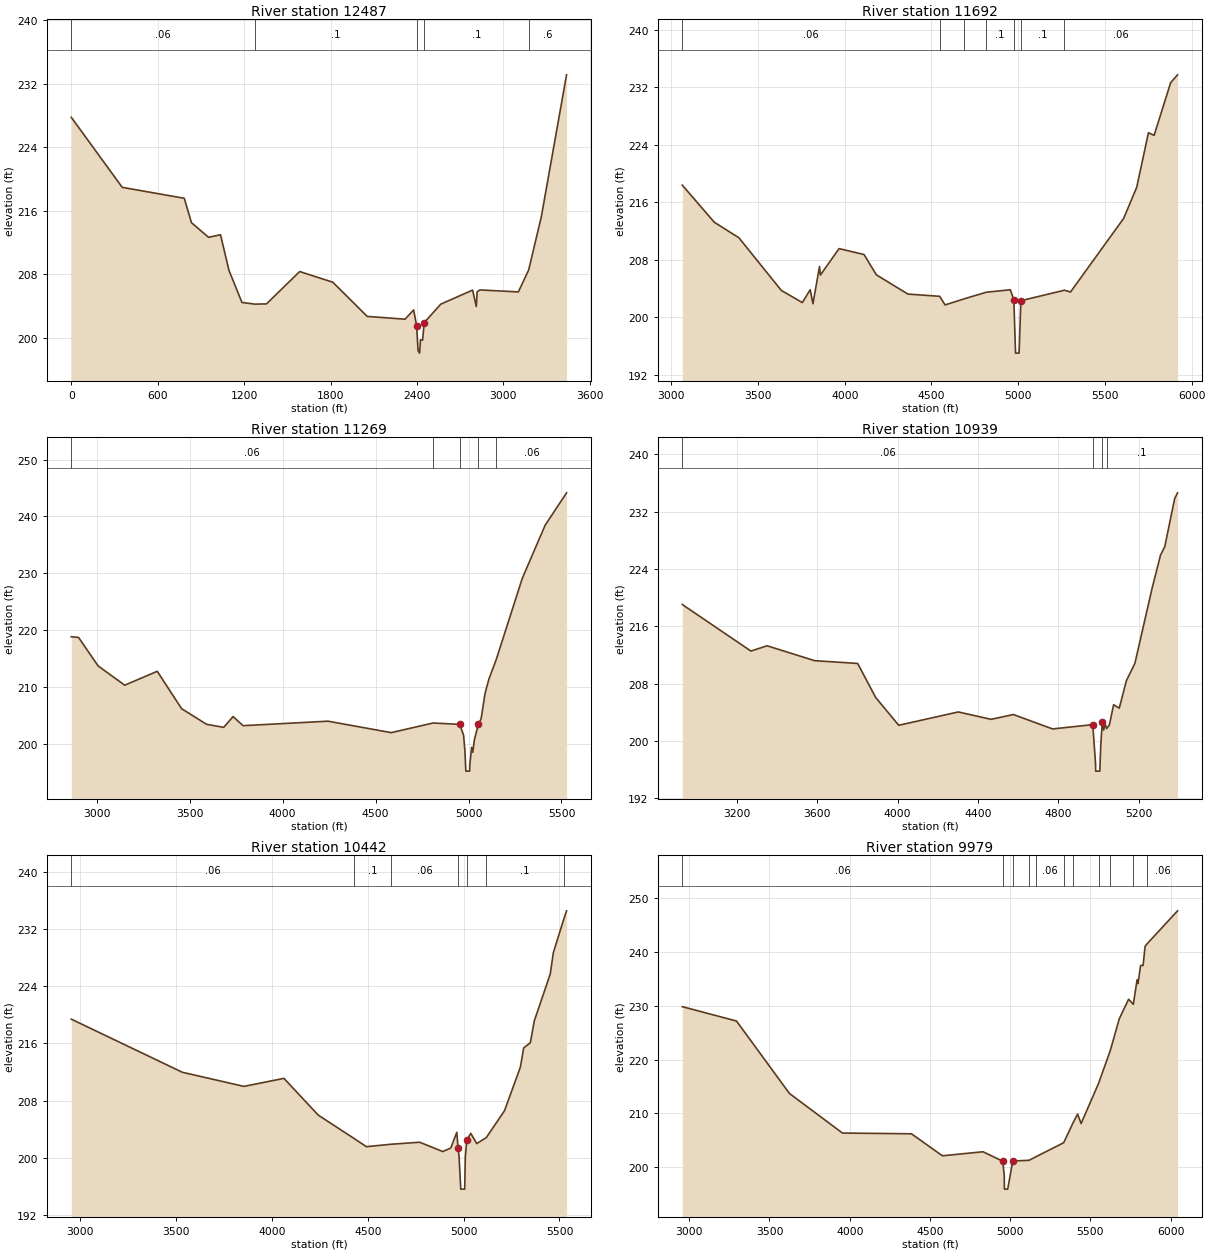
Type RM Length L Ch R = 1 ,12487   ,795,795,795
BEGIN DESCRIPTION:
CANEY CREEK 17.0
END DESCRIPTION:
XS GIS Cut Line= 4
      3734043.69     10119543.72      3734108.39     10118589.86
      3734192.34      10117157.1      3734517.85     10116161.07
#Sta/Elev= 30
       0  227.77   353.5  218.94   784.4  217.56   834.6  214.48   952.9  212.64
  1036.1  212.96  1095.1  208.46  1185.2  204.42  1275.4  204.21  1355.5  204.24
  1585.9  208.32  1816.3  206.97  2054.9  202.66  2317.2  202.31  2377.3  203.48
  2397.9  201.48  2408.1  198.33  2418.7  198.03  2424.5   199.7  2439.7  199.67
  2450.2  201.87  2565.9  204.21  2786.9  205.98  2812.3  203.91  2818.4  205.78
  2838.9     206  3104.4  205.75  3176.1  208.52  3263.8  215.22  3439.1  233.13
#Mann= 5 ,-1 , 0
       0     .06       0  1275.4      .1       0  2397.9     .09       0
  2450.2      .1       0  3176.1      .6       0
Bank Sta=2397.9,2450.2
XS Rating Curve= 0 ,0
Exp/Cntr=0.3,0.1

Type RM Length L Ch R = 1 ,11692   ,423,423,423
BEGIN DESCRIPTION:
CANEY CREEK 16.0
END DESCRIPTION:
XS GIS Cut Line= 3
      3734213.17      10118872.4      3734553.46      10116969.6
      3734740.95     10116066.85
#Sta/Elev= 30
  3063.8  218.38    3248  213.22  3390.2  211.05  3634.6  203.72  3755.9  202.03
    3801  203.82  3816.9  201.87  3854.8  207.04  3859.9  205.86  3967.5  209.54
  4111.5  208.72  4182.6  205.89  4364.4  203.21  4547.7   202.9  4578.8   201.7
  4690.2  202.56  4816.3  203.47  4954.7  203.81    4975  202.45  4984.8  194.99
  5005.3  194.99  5015.7  202.29  5266.8  203.75  5301.7   203.5  5608.1  213.75
  5683.5  218.09  5751.1  225.68  5783.7  225.31  5878.9  232.64  5918.8  233.74
#Mann= 7 ,-1 , 0
  3063.8     .06       0  4547.7      .1       0  4690.2     .06       0
  4816.3      .1       0    4975     .09       0  5015.7      .1       0
  5266.8     .06       0
Bank Sta=4975,5015.7
XS Rating Curve= 0 ,0
Exp/Cntr=0.3,0.1

Type RM Length L Ch R = 1 ,11269   ,330,330,330
BEGIN DESCRIPTION:
CANEY CREEK 15.0
END DESCRIPTION:
XS GIS Cut Line= 3
      3734393.74     10118941.78      3734852.07     10116872.38
       3735157.6     10116421.01
#Sta/Elev= 30
  2862.8  218.88  2902.1  218.75  3006.9  213.76  3150.3  210.37  3325.3  212.81
  3456.2  206.25  3590.7   203.5  3682.9  202.97  3733.2  204.86    3787  203.26
  4243.6  204.05  4584.2  202.04  4809.4  203.73    4953  203.49  4973.4  201.58
  4980.5  198.87  4985.5  195.28    5006  195.28  5006.5  196.28  5016.8  199.46
  5022.8  198.58  5031.7  200.83  5052.7  203.47  5067.7  204.47  5088.7   208.9
  5109.7  211.45  5148.3   214.8  5289.4  229.15  5412.2  238.46  5527.4  244.15
#Mann= 5 ,-1 , 0
  2862.8     .06       0  4809.4      .1       0    4953     .09       0
  5052.7      .1       0  5148.3     .06       0
Bank Sta=4953,5052.7
XS Rating Curve= 0 ,0
Exp/Cntr=0.3,0.1

Type RM Length L Ch R = 1 ,10939   ,497,497,497
BEGIN DESCRIPTION:
CANEY CREEK 14.0
END DESCRIPTION:
XS GIS Cut Line= 3
      3734615.95     10119115.44       3735038.7     10117087.23
      3735317.88     10116811.05
#Sta/Elev= 30
  2928.2  219.05  3269.8  212.55  3350.2  213.29  3586.4  211.21  3800.9  210.82
  3890.5  206.07  4005.2  202.19  4301.5  204.05  4464.9  203.02  4575.7  203.69
  4770.8  201.68  4970.9  202.28  4984.7  196.79  4985.2  195.79  5005.7  195.79
  5010.9  199.57  5017.9  202.58    5025  201.51    5032  202.41  5039.6  201.72
  5053.3  202.22  5074.5  205.06  5102.7  204.58  5138.1  208.41  5180.6  210.85
  5265.4  221.24  5307.8  225.93    5329  227.12  5378.6  233.86  5392.7  234.64
#Mann= 4 ,-1 , 0
  2928.2     .06       0  4970.9     .06       0  5017.9     .06       0
  5039.6      .1       0
Bank Sta=4970.9,5017.9
XS Rating Curve= 0 ,0
Exp/Cntr=0.3,0.1

Type RM Length L Ch R = 1 ,10442   ,463,463,463
BEGIN DESCRIPTION:
CANEY CREEK 13.0
END DESCRIPTION:
XS GIS Cut Line= 3
      3734810.41     10119330.67      3735421.19     10117377.13
       3735560.4     10116858.49
#Sta/Elev= 30
  2953.2   219.4  3532.7  211.98  3853.8  210.01  4062.7  211.13  4241.5     206
  4425.7  202.78    4493  201.59  4622.5  201.93  4770.8  202.21  4891.1  200.91
    4933   201.4  4964.4   203.6  4970.9  201.36  4976.1  200.27  4985.1  195.66
  5005.6  195.66  5008.9  200.19  5016.6  202.49  5037.3  203.45  5068.4  202.02
  5118.7  202.87  5213.4  206.62  5296.2  212.71  5313.4  215.39    5348   216.1
  5368.7  219.16  5451.5  225.67  5468.2   228.7  5521.7   233.3    5537  234.53
#Mann= 7 ,-1 , 0
  2953.2     .06       0  4425.7      .1       0  4622.5     .06       0
  4970.9     .06       0  5016.6     .06       0  5118.7      .1       0
  5521.7     .12       0
Bank Sta=4970.9,5016.6
XS Rating Curve= 0 ,0
Exp/Cntr=0.3,0.1

Type RM Length L Ch R = 1 ,9979    ,284,284,284
BEGIN DESCRIPTION:
Mapping XS 270ff743
END DESCRIPTION:
XS GIS Cut Line= 4
      3735595.12     10119608.51      3735650.68     10118059.88
      3735831.23     10117455.71      3736247.88     10116650.18
#Sta/Elev= 30
  2956.6  229.86  3294.3  227.19  3624.5  213.72  3954.7  206.36    4385  206.22
    4578  202.13  4830.9  202.88  4953.8  201.13  4963.4  198.49  4964.3  195.93
  4984.9  195.93  5016.4  201.15  5118.2  201.29  5159.5  201.93  5333.9  204.56
  5391.6  208.21  5420.6  209.88  5442.7  208.13    5551  215.57  5623.7  221.63
  5680.6  227.61  5738.7  231.24    5768   230.3  5791.3  234.84    5797  234.15
  5813.5  237.53  5828.8  237.51  5841.3  241.07  5855.8  241.61  6043.7  247.68
#Mann= 11 ,-1 , 0
  2956.6     .06       0  4953.8     .07       0  5016.4     .06       0
  5118.2      .1       0  5159.5     .06       0  5333.9      .1       0
  5391.6     .06       0    5551     .12       0  5623.7     .06       0
    5768     .12       0  5855.8     .06       0
Bank Sta=4953.8,5016.4
XS Rating Curve= 0 ,0
Exp/Cntr=0.3,0.1

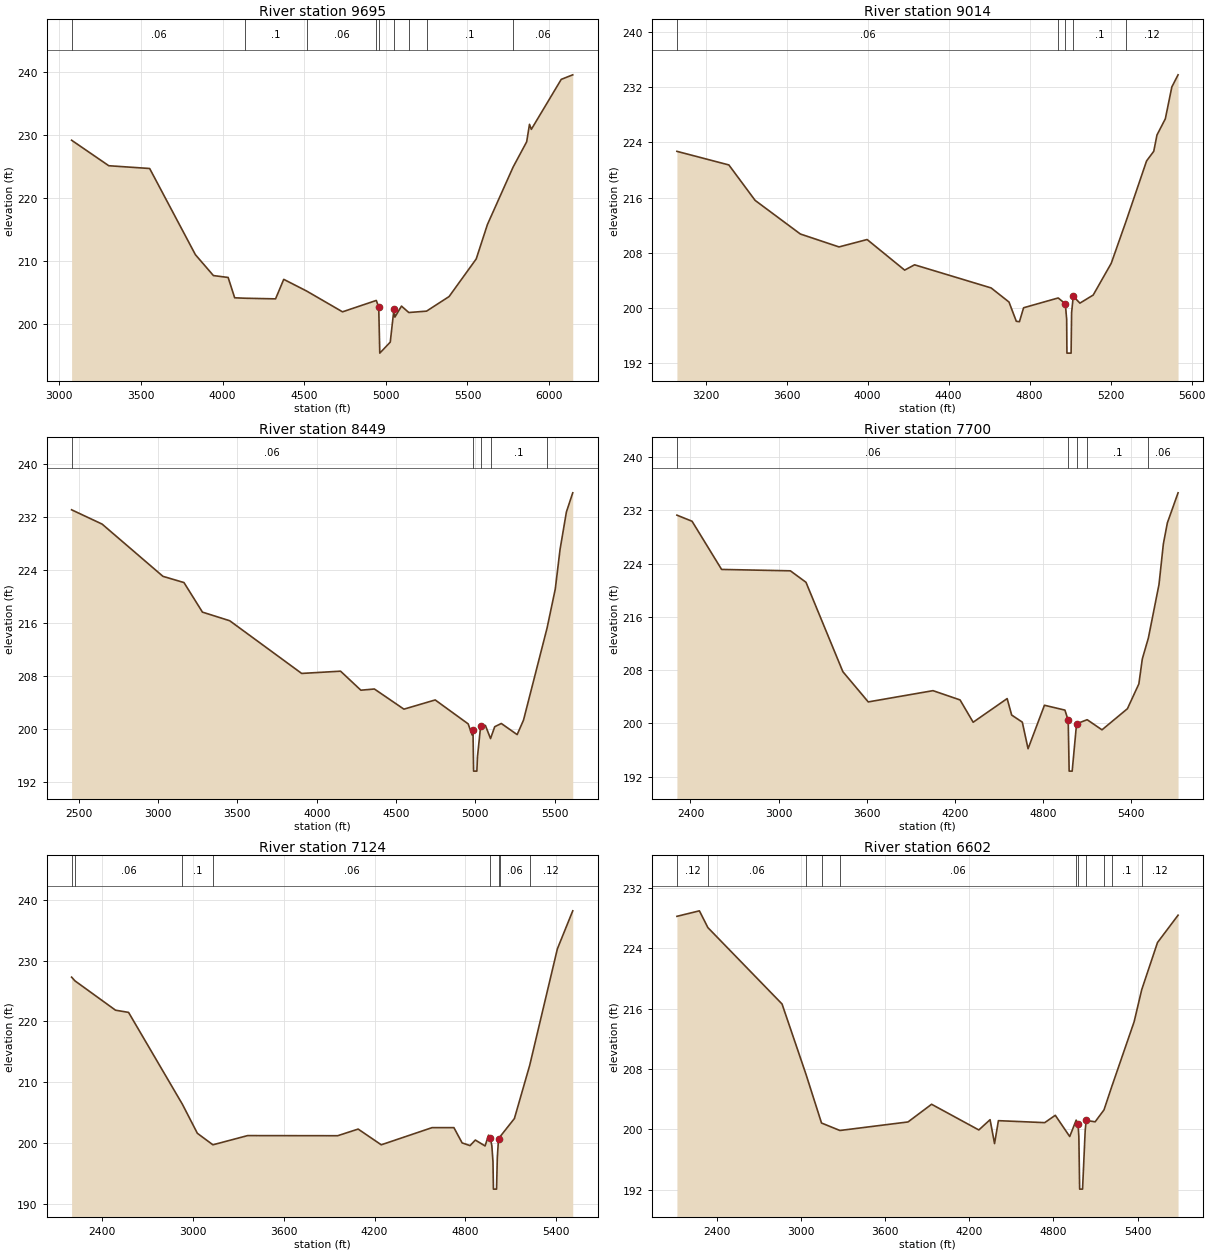
Type RM Length L Ch R = 1 ,9695    ,681,681,681
BEGIN DESCRIPTION:
CANEY CREEK 12.0
END DESCRIPTION:
XS GIS Cut Line= 4
       3735810.4     10119608.49      3735886.79     10118136.26
      3736031.13     10117709.73      3736511.81     10116670.95
#Sta/Elev= 30
  3075.5  229.14  3303.2  225.09  3553.6  224.65  3833.9  210.95  3944.1  207.64
  4034.2  207.34  4074.3  204.11  4139.3  204.04  4324.6  203.94  4374.7  207.04
  4514.4  205.19  4734.7  201.88  4941.6  203.69  4956.4  202.62  4962.9  195.32
    5027  197.07  5049.9  202.35  5055.4  201.04  5095.8  202.79  5140.7  201.77
  5249.3  201.99  5387.4  204.31  5553.4  210.28  5622.1  215.75  5779.3  224.87
  5862.4  228.89  5879.8  231.67    5891  230.87  6074.2  238.81  6144.6  239.53
#Mann= 9 ,-1 , 0
  3075.5     .06       0  4139.3      .1       0  4514.4     .06       0
  4941.6      .1       0  4956.4     .09       0  5049.9      .1       0
  5140.7     .06       0  5249.3      .1       0  5779.3     .06       0
Bank Sta=4956.4,5049.9
XS Rating Curve= 0 ,0
Exp/Cntr=0.3,0.1

Type RM Length L Ch R = 1 ,9014    ,565,565,565
BEGIN DESCRIPTION:
CANEY CREEK 11.0
END DESCRIPTION:
XS GIS Cut Line= 3
      3736150.68     10119462.63      3736615.96     10117580.71
      3736740.95     10117059.88
#Sta/Elev= 30
  3058.8  222.71  3315.3  220.74  3444.8  215.61  3668.2  210.74  3859.1  208.87
  3997.8  209.94  4183.2  205.51    4232  206.28  4610.1  202.93  4698.3  200.89
  4734.4   198.1  4749.8  198.04  4770.4  200.06  4941.3  201.48  4976.4  200.63
    4983  198.38  4984.3  193.49  5004.9  193.49  5007.3  199.34 5015.57201.7326
  5048.4  200.73    5114   201.9  5203.1   206.5  5275.8  212.55  5377.5  221.32
    5413  222.72  5428.9  225.08  5470.1  227.42  5502.2  232.03    5533  233.79
#Mann= 5 ,-1 , 0
  3058.8     .06       0  4941.3      .1       0  4976.4     .09       0
 5015.57      .1       0  5275.8     .12       0
Bank Sta=4976.4,5015.57
XS Rating Curve= 0 ,0
Exp/Cntr=0.3,0.1

Type RM Length L Ch R = 1 ,8449    ,749,749,749
BEGIN DESCRIPTION:
CANEY CREEK 10.0
END DESCRIPTION:
XS GIS Cut Line= 3
      3736117.87     10120161.03        3736999.     10117774.07
      3737017.85     10117161.06
#Sta/Elev= 30
  2455.6  233.04    2648  230.88  3031.2     223  3163.7  222.06  3280.1   217.6
    3452   216.3  3905.3  208.35  4150.4  208.69  4278.3  205.82  4363.6     206
  4549.6  202.96  4746.6  204.35  4954.3  200.74  4979.4  199.07  4984.7  199.87
  4988.6  193.61  5009.2  193.61    5013  195.77    5033  200.42    5063   200.5
  5095.3  198.52  5121.7  200.31  5163.1   200.8  5263.1  199.12  5303.1  201.31
  5451.5   215.2  5503.2  221.08  5533.3  227.05  5573.3  232.71  5613.3   235.6
#Mann= 5 ,-1 , 0
  2455.6     .06       0  4984.7     .06       0    5033     .06       0
  5095.3      .1       0  5451.5     .12       0
Bank Sta=4984.7,5033
XS Rating Curve= 0 ,0
Exp/Cntr=0.3,0.1

Type RM Length L Ch R = 1 ,7700    ,576,576,576
BEGIN DESCRIPTION:
CANEY CREEK 9.0
END DESCRIPTION:
XS GIS Cut Line= 3
      3736467.83     10120111.11      3737676.65     10117705.44
      3737267.84     10117111.06
#Sta/Elev= 30
  2307.7  231.26    2411  230.34    2612  223.11  3080.8   222.9  3186.9  221.18
  3438.1  207.76  3611.1  203.22  4052.1  204.91  4236.3  203.52  4325.6  200.17
  4557.2  203.72  4587.9  201.25  4660.5  200.18  4699.6  196.19  4811.2  202.72
  4950.8  201.99  4973.1  200.45  4979.5  192.83  5000.1  192.83    5030  199.94
  5102.2  200.55  5203.2  199.03  5376.4   202.2  5454.4  205.93  5477.9  209.68
  5519.2  212.82  5591.5  220.85  5621.3  226.95  5648.6  230.11  5721.4  234.61
#Mann= 5 ,-1 , 0
  2307.7     .06       0  4973.1     .06       0    5030     .06       0
  5102.2      .1       0  5519.2     .06       0
Bank Sta=4973.1,5030
XS Rating Curve= 0 ,0
Exp/Cntr=0.3,0.1

Type RM Length L Ch R = 1 ,7124    ,522,522,522
BEGIN DESCRIPTION:
CANEY CREEK 8.0
END DESCRIPTION:
XS GIS Cut Line= 3
      3736990.96     10119997.35      3738109.01     10117427.93
      3738331.23      10116969.6
#Sta/Elev= 30
  2197.7  227.27  2220.1  226.66  2488.1  221.85  2574.1  221.49  2929.9  206.42
  3028.7  201.66  3131.4  199.77  3360.7  201.28  3955.9  201.26  4091.2  202.35
  4243.9  199.77    4580  202.59  4723.8  202.59  4778.3  200.08  4830.7  199.64
  4865.5  200.55  4929.9  199.58  4952.8  201.35  4964.2  200.89  4974.6  199.64
  4982.2  196.98    4985   192.5  5005.7   192.5  5010.8  197.69  5018.6  200.69
  5027.8  201.07  5123.7  204.08  5224.9  212.82  5407.5   231.9  5509.2  238.15
#Mann= 8 ,-1 , 0
  2197.7     .12       0  2220.1     .06       0  2929.9      .1       0
  3131.4     .06       0  4964.2     .09       0  5018.6     .07       0
  5027.8     .06       0  5224.9     .12       0
Bank Sta=4964.2,5018.6
XS Rating Curve= 0 ,0
Exp/Cntr=0.3,0.1

Type RM Length L Ch R = 1 ,6602    ,608,608,608
BEGIN DESCRIPTION:
CANEY CREEK 7.0
END DESCRIPTION:
XS GIS Cut Line= 3
      3737067.86     10120211.06      3738477.07     10117684.88
      3738713.01     10117046.43
#Sta/Elev= 30
  2115.3   228.2  2275.6  228.93  2336.1  226.71  2864.9   216.6  3036.1  207.27
  3146.3  200.85  3277.3  199.86  3763.1  200.99  3931.1  203.33    4268  199.93
  4348.2  201.29  4380.1  198.13  4407.6  201.16  4737.8   200.9  4813.2  201.87
  4916.1  199.06  4962.1  201.23  4975.5  200.69  4981.2  199.03  4986.9   192.1
  5007.6   192.1  5026.3  199.81  5033.3  201.19  5097.3  201.01  5160.5  202.59
  5217.2  205.74  5375.3  214.25  5429.1  218.47  5541.8  224.73  5688.6  228.35
#Mann= 11 ,-1 , 0
  2115.3     .12       0  2336.1     .06       0  3036.1     .12       0
  3146.3      .1       0  3277.3     .06       0  4962.1      .1       0
  4975.5     .09       0  5033.3      .1       0  5160.5     .12       0
  5217.2      .1       0  5429.1     .12       0
Bank Sta=4975.5,5033.3
XS Rating Curve= 0 ,0
Exp/Cntr=0.3,0.1