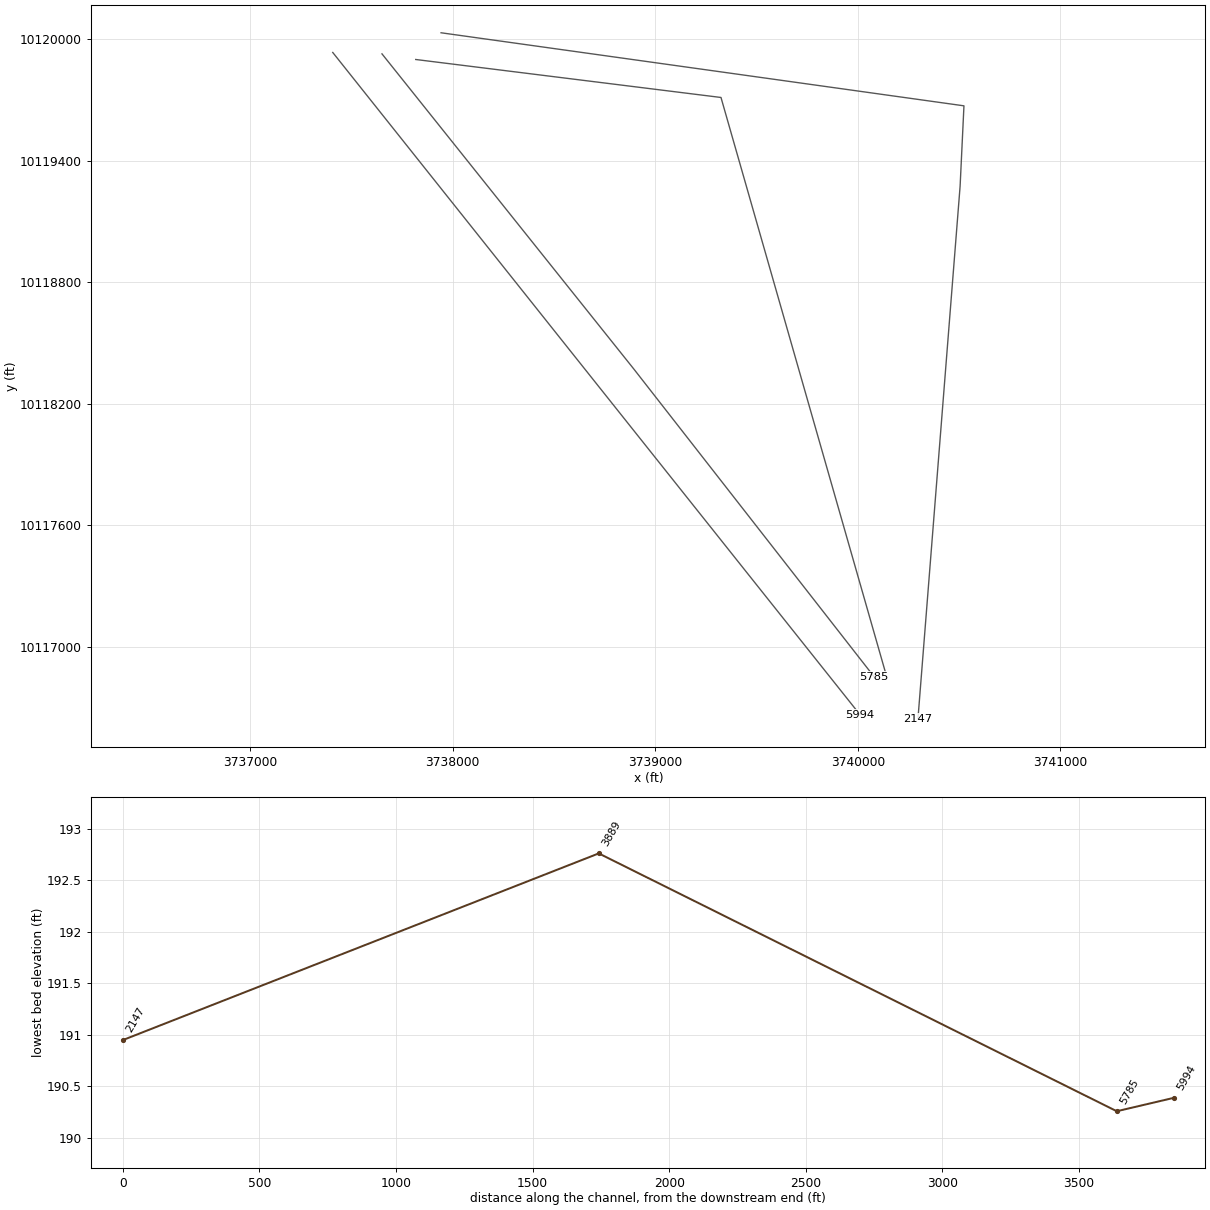
HEC-RAS study CANEY CREEK.prj: CANEY CREEK Base Level Engineering

--- CANEY CREEK.g01 (geometry) --- (continued)

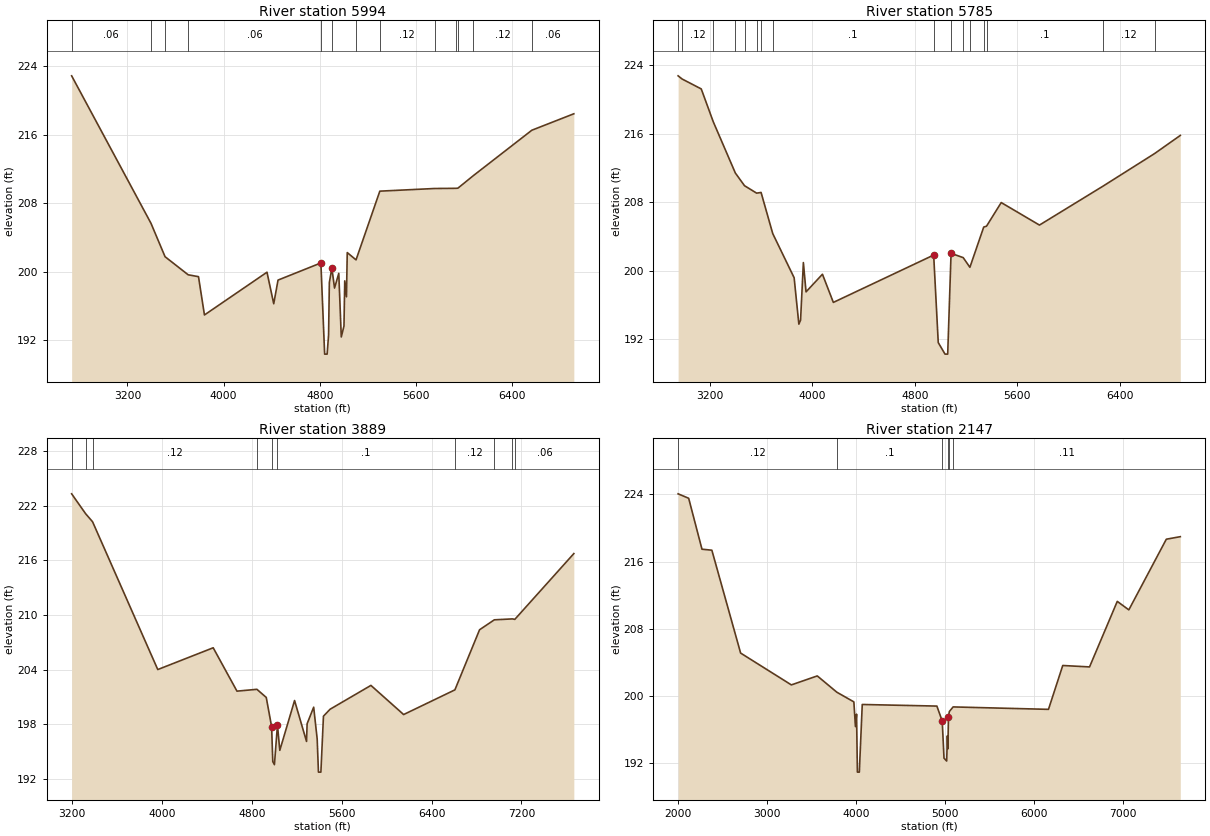
Type RM Length L Ch R = 1 ,5994    ,209,209,209
BEGIN DESCRIPTION:
Mapping XS c6b397ba
END DESCRIPTION:
XS GIS Cut Line= 2
      3737407.64     10119934.85      3740010.99     10116665.05
#Sta/Elev= 30
  2735.4  222.87  3395.3  205.67  3512.8  201.76  3705.1  199.65  3791.1  199.43
  3840.7  194.96  4361.2  199.95  4417.3  196.27  4453.1  199.03  4809.7  201.03
    4841  190.39  4861.7  190.39  4873.8  192.63  4880.2  198.74    4901  200.43
  4923.4   198.1  4958.6  199.82  4979.5  192.39  5001.9  193.67  5008.3  198.94
  5022.7  197.08  5029.1  202.24  5102.3  201.39  5300.3  209.41  5757.2  209.72
  5932.6  209.74  5950.3  209.76  6077.7  211.21  6565.4  216.52    6915  218.44
#Mann= 13 ,-1 , 0
  2735.4     .06       0  3395.3     .12       0  3512.8      .1       0
  3705.1     .06       0  4809.7     .06       0    4901     .06       0
  5102.3      .1       0  5300.3     .12       0  5757.2      .1       0
  5932.6     .12       0  5950.3      .1       0  6077.7     .12       0
  6565.4     .06       0
Bank Sta=4809.7,4901
XS Rating Curve= 0 ,0
Exp/Cntr=0.3,0.1

Type RM Length L Ch R = 1 ,5785    ,1896,1896,1896
BEGIN DESCRIPTION:
CANEY CREEK 6.0
END DESCRIPTION:
XS GIS Cut Line= 3
      3737650.71     10119927.89      3738893.73     10118372.38
      3740081.23     10116851.54
#Sta/Elev= 30
  2951.8  222.76  2982.8  222.39  3132.4  221.23  3226.1   217.4  3398.6  211.41
  3470.2  209.93  3564.7  209.06  3599.5  209.14  3690.5  204.34  3857.6  199.18
  3894.5  193.76  3907.8  194.23  3929.7  200.95  3950.5  197.53  4078.6  199.59
  4163.8   196.3    4947  201.83  4982.7  191.61  5035.8  190.26  5056.5  190.26
  5082.8  202.03  5177.5  201.53  5229.8   200.4  5337.8   205.1  5359.5   205.2
  5474.4  207.96  5772.9  205.33  6267.3  209.86  6671.6  213.68  6872.5   215.8
#Mann= 16 ,-1 , 0
  2951.8     .06       0  2982.8     .12       0  3226.1     .06       0
  3398.6      .1       0  3470.2     .12       0  3564.7      .1       0
  3599.5     .12       0  3690.5      .1       0    4947     .09       0
  5082.8      .1       0  5177.5     .12       0  5229.8      .1       0
  5337.8     .12       0  5359.5      .1       0  6267.3     .12       0
  6671.6     .06       0
Bank Sta=4947,5082.8
XS Rating Curve= 0 ,0
Exp/Cntr=0.3,0.1

Type RM Length L Ch R = 1 ,3889    ,1742,1742,1742
BEGIN DESCRIPTION:
CANEY CREEK 4.0
END DESCRIPTION:
XS GIS Cut Line= 3
      3737817.31     10119900.16      3739324.29     10119712.65
      3740136.26     10116874.21
#Sta/Elev= 30
  3195.6  223.31  3319.8  221.13    3382  220.24  3962.3  204.02  4455.8  206.41
  4667.4  201.65  4844.9  201.85  4928.1  200.96  4975.9  197.75  4986.3  193.91
  5000.9  193.58  5027.9  197.93  5048.7  195.15  5180.2  200.62  5286.7  196.13
  5291.9  198.07  5350.3  199.89  5381.5   196.4  5392.8  192.76  5414.5  192.76
  5437.4   198.9  5495.9  199.66    5860  202.28  6151.2  199.08  6607.6  201.79
  6827.3  208.39  6958.9  209.48    7120  209.58  7141.1  209.53  7666.5  216.75
#Mann= 10 ,-1 , 0
  3195.6     .12       0  3319.8     .06       0    3382     .12       0
  4844.9      .1       0  4975.9     .09       0  5027.9      .1       0
  6607.6     .12       0  6958.9     .06       0    7120     .12       0
  7141.1     .06       0
Bank Sta=4975.9,5027.9
XS Rating Curve= 0 ,0
Exp/Cntr=0.3,0.1

Type RM Length L Ch R = 1 ,2147    ,0,0,0
BEGIN DESCRIPTION:
CANEY CREEK 2.0
END DESCRIPTION:
XS GIS Cut Line= 4
      3737942.39     10120032.09      3740523.79     10119671.45
      3740504.84     10119275.15      3740296.62      10116644.6
#Sta/Elev= 30
  1998.3  224.07    2117  223.54  2266.3  217.48  2377.4  217.36  2700.5  205.12
  3270.7  201.33  3561.7   202.4  3781.7  200.46  3972.8  199.31  3990.5  196.37
    4003  197.85  4012.4  190.95  4034.1  190.95  4067.1     199  4905.5  198.81
  4965.6  197.03  4985.6  192.61  5015.6  192.27  5023.7  195.27  5028.7  193.71
  5035.7  197.55  5045.7  198.16  5087.9  198.71  6159.2  198.42  6319.7  203.64
  6620.6  203.47  6932.2  211.27    7062  210.26  7483.3  218.67  7640.3  218.97
#Mann= 6 ,-1 , 0
  1998.3     .12       0  3781.7      .1       0  4965.6     .09       0
  5035.7     .07       0  5045.7      .1       0  5087.9     .11       0
Bank Sta=4965.6,5035.7
XS Rating Curve= 0 ,0
Exp/Cntr=0.3,0.1

Chan Stop Cuts=-1
Use User Specified Reach Order=0
Composite Channel Slope=5