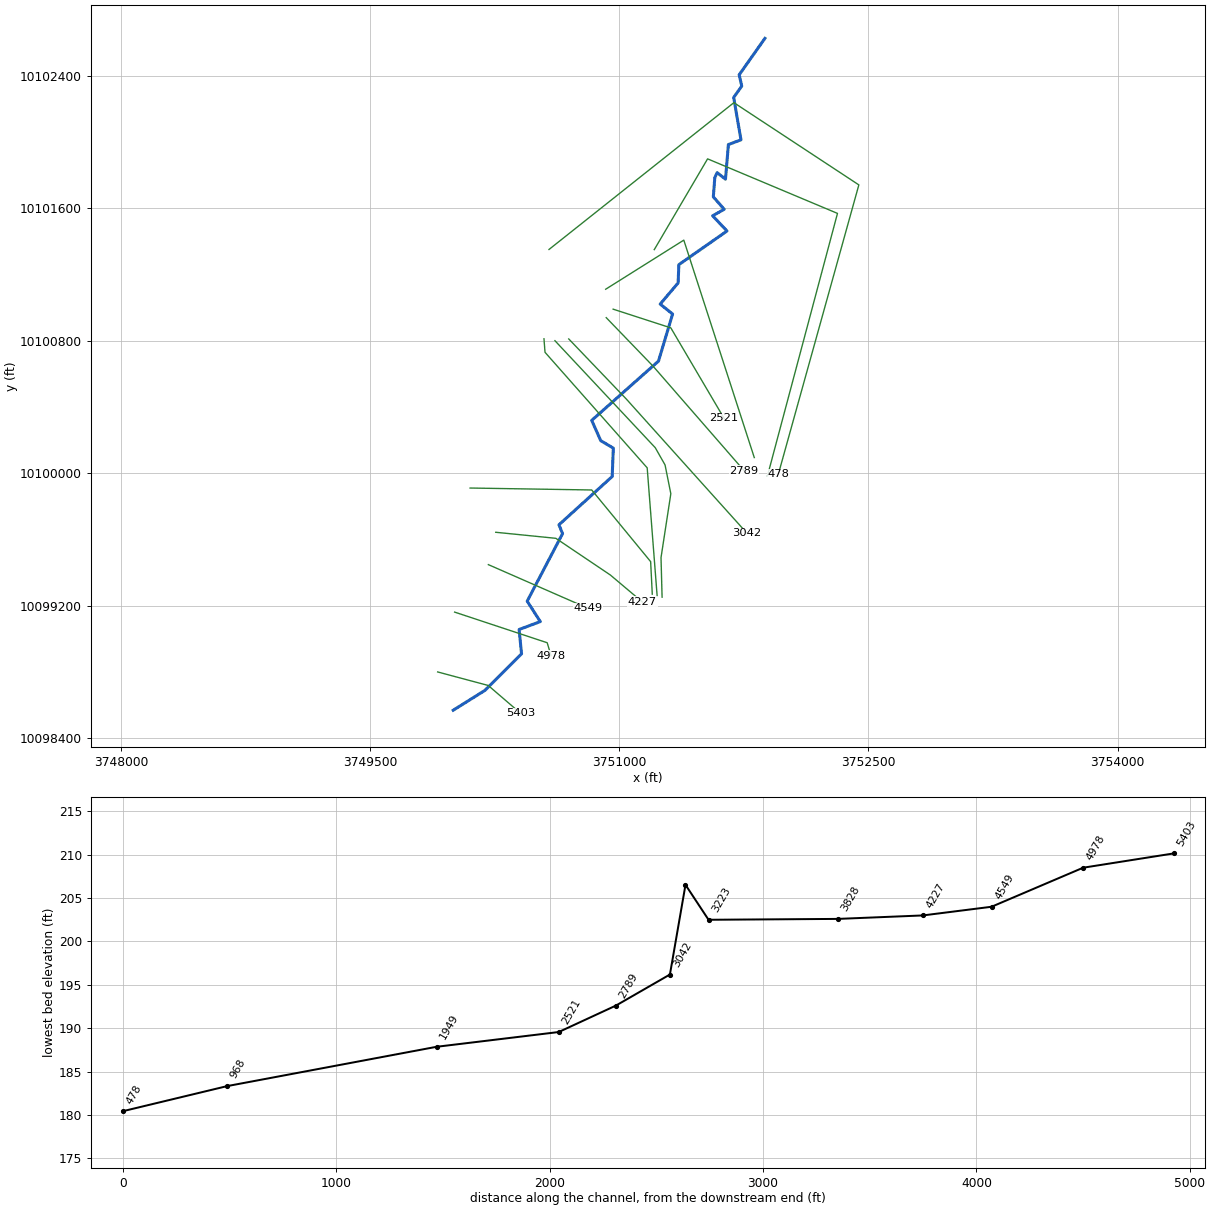
--- CCLC 007.prj (project) ---

Proj Title=CCLC 007 Base Level Engineering
Current Plan=p01
Default Exp/Contr=0.3,0.1
English Units
Geom File=g01
Flow File=f01
Flow File=f02
Plan File=p01
Y Axis Title=Elevation
X Axis Title(PF)=Main Channel Distance
X Axis Title(XS)=Station
BEGIN DESCRIPTION:
CCLC 007
END DESCRIPTION:
DSS Export Rating Curves= 0
DSS Export Rating Curve Sorted= 0
DSS Export Volume Flow Curves= 0
DXF OffsetX= 0
DXF OffsetY= 0
DXF ScaleX= 1
DXF ScaleY= 10

--- CCLC 007.p01 (plan) ---

Plan Title=Multiple Run
Short Identifier=Multiple
Geom File=g01
Flow File=f01
Subcritical Flow
K Sum by GR= 0
Std Step Tol= 0.01
Critical Tol= 0.01
Num of Std Step Trials= 20
Max Error Tol= 0.3
Flow Tol Ratio= 0.001
Split Flow NTrial= 30
Split Flow Tol= 0.02
Split Flow Ratio= 0.02
Log Output Level= 0
Friction Slope Method= 1
Unsteady Friction Slope Method= 2
Unsteady Bridges Friction Slope Method= 1
Parabolic Critical Depth
Global Vel Dist=  1 , 1 , 1
Global Log Level= 0
CheckData=True
Encroach Param= -1, 0, 0, 0
BEGIN DESCRIPTION:
Multiple Run
END DESCRIPTION:

--- CCLC 007.f01 (steady flow) ---

Flow Title=Multiple
Program Version=4.10
Number of Profiles= 7
Profile Names=10-year,25-year,50-year,1pct_min,100-year,1pct_plu,500-year
River Rch & RM=CCLC 007,Reach-1         ,5403
     624     846    1144     510    1539    4648    2878
River Rch & RM=CCLC 007,Reach-1         ,3042
     640     864    1166     518    1564    4723    2907
Boundary for River Rch & Prof#=CCLC 007,Reach-1         , 1
Up Type= 0
Dn Type= 3
Dn Slope=0.005
Boundary for River Rch & Prof#=CCLC 007,Reach-1         , 2
Up Type= 0
Dn Type= 3
Dn Slope=0.005
Boundary for River Rch & Prof#=CCLC 007,Reach-1         , 3
Up Type= 0
Dn Type= 3
Dn Slope=0.005
Boundary for River Rch & Prof#=CCLC 007,Reach-1         , 4
Up Type= 0
Dn Type= 3
Dn Slope=0.005
Boundary for River Rch & Prof#=CCLC 007,Reach-1         , 5
Up Type= 0
Dn Type= 3
Dn Slope=0.005
Boundary for River Rch & Prof#=CCLC 007,Reach-1         , 6
Up Type= 0
Dn Type= 3
Dn Slope=0.005
Boundary for River Rch & Prof#=CCLC 007,Reach-1         , 7
Up Type= 0
Dn Type= 3
Dn Slope=0.005
DSS Import GetInterval= 0
DSS Import GetPeak= 0
DSS Import FillOption= 0

--- CCLC 007.f02 (steady flow) ---

Flow Title=Orig_BLE_Flows
Program Version=4.10
Number of Profiles= 7
Profile Names=10-year,25-year,50-year,1pct_min,100-year,1pct_plu,500-year
River Rch & RM=CCLC 007,Reach-1         ,5403
     624     829     995     392    1184    3575    1673
River Rch & RM=CCLC 007,Reach-1         ,3042
     640     847    1014     398    1203    3633    1690
Boundary for River Rch & Prof#=CCLC 007,Reach-1         , 1
Up Type= 0
Dn Type= 3
Dn Slope=0.005
Boundary for River Rch & Prof#=CCLC 007,Reach-1         , 2
Up Type= 0
Dn Type= 3
Dn Slope=0.005
Boundary for River Rch & Prof#=CCLC 007,Reach-1         , 3
Up Type= 0
Dn Type= 3
Dn Slope=0.005
Boundary for River Rch & Prof#=CCLC 007,Reach-1         , 4
Up Type= 0
Dn Type= 3
Dn Slope=0.005
Boundary for River Rch & Prof#=CCLC 007,Reach-1         , 5
Up Type= 0
Dn Type= 3
Dn Slope=0.005
Boundary for River Rch & Prof#=CCLC 007,Reach-1         , 6
Up Type= 0
Dn Type= 3
Dn Slope=0.005
Boundary for River Rch & Prof#=CCLC 007,Reach-1         , 7
Up Type= 0
Dn Type= 3
Dn Slope=0.005
DSS Import GetInterval= 0
DSS Import GetPeak= 0
DSS Import FillOption= 0

--- CCLC 007.g01 (geometry) ---

Geom Title=Existing Conditions
Program Version=4.10

River Reach=CCLC 007        ,Reach-1
Reach XY= 30
      3749999.83     10098570.68       3750190.8     10098690.48
      3750411.28     10098910.96      3750396.53     10099057.66
      3750524.13     10099105.41      3750445.14     10099228.67
      3750658.11     10099636.22      3750636.38     10099689.53
      3750956.93     10099980.81       3750963.9     10100152.24
      3750888.08     10100197.23      3750833.71     10100319.72
      3751235.71     10100677.14      3751320.76     10100961.37
      3751245.98     10101021.34      3751354.07      10101149.3
      3751358.38     10101259.48      3751648.22     10101462.34
      3751561.81     10101554.32      3751631.49     10101593.35
      3751565.99     10101668.61       3751574.9     10101784.55
      3751588.67     10101814.55      3751639.21     10101775.26
      3751656.79     10101984.18      3751732.44     10102012.65
      3751688.55     10102268.31      3751737.08     10102336.99
      3751721.68     10102405.15      3751876.68      10102625.1

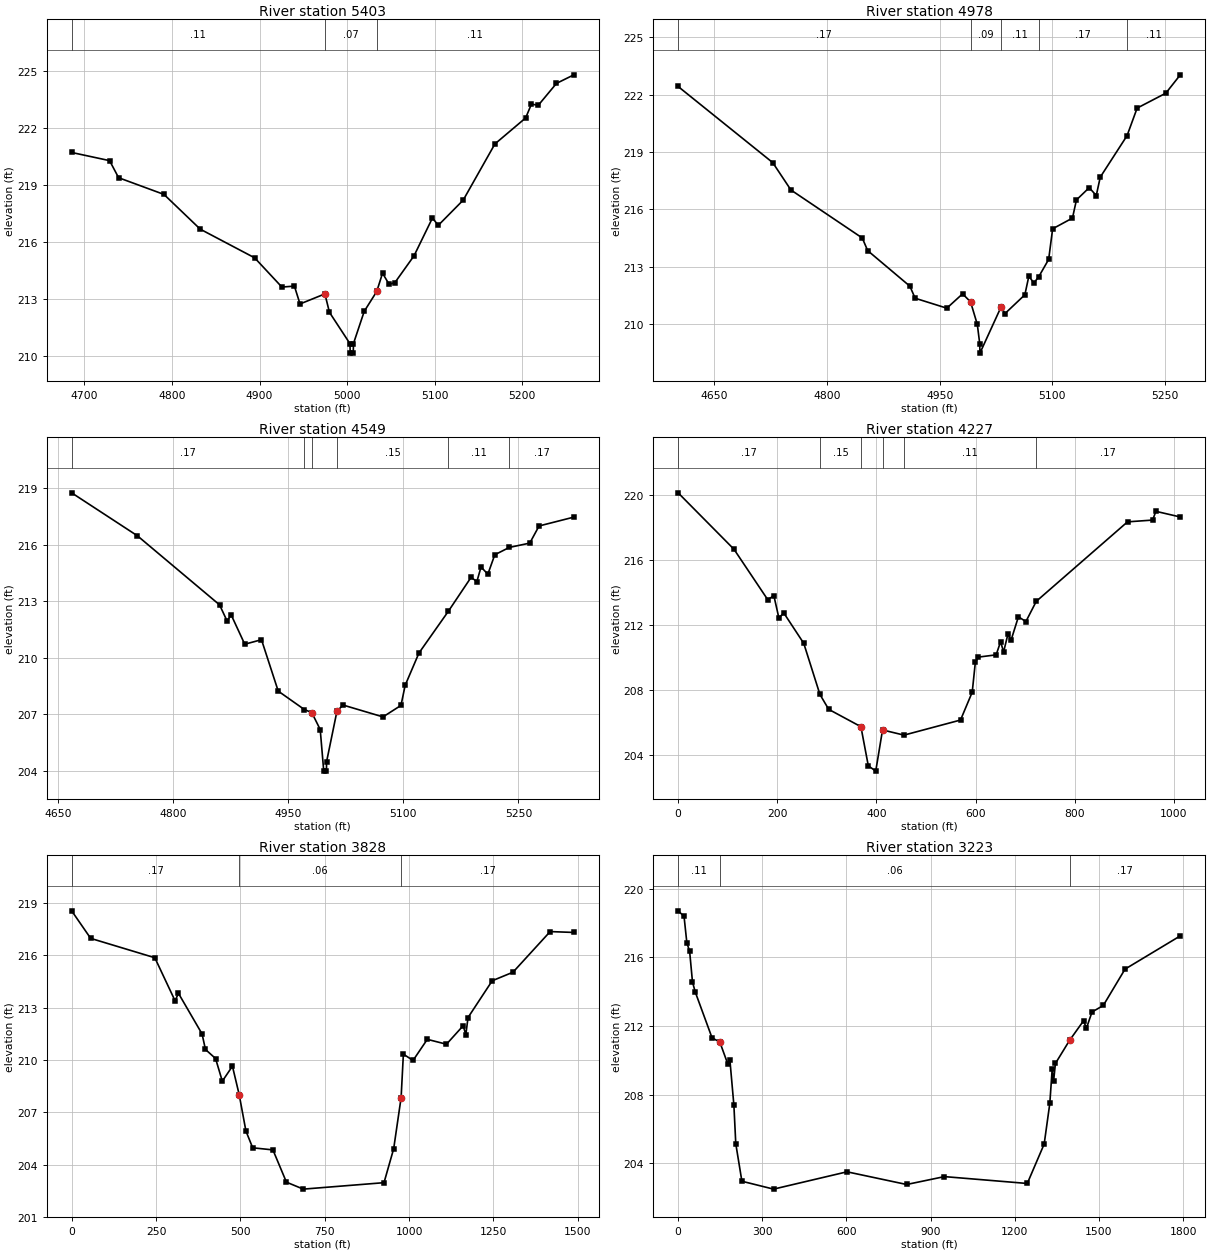
Type RM Length L Ch R = 1 ,5403    ,425,425,425
BEGIN DESCRIPTION:
CCLC 007 8.0
END DESCRIPTION:
XS GIS Cut Line= 3
      3749906.07     10098801.59      3750210.55     10098719.99
      3750406.09     10098551.57
#Sta/Elev= 30
  4685.5  220.71  4728.8  220.28  4739.1  219.38  4790.9   218.5  4832.3  216.67
  4894.4  215.16  4925.5  213.62  4939.8  213.67  4946.2  212.73  4974.6  213.26
  4979.8  212.29  5003.2  210.64  5003.5  210.14    5007  210.14  5007.2  210.64
  5019.5  212.34  5033.8  213.39  5040.4  214.35    5048  213.76  5054.6  213.86
  5076.4  215.27  5097.4  217.26    5104  216.87  5132.5   218.2  5168.7  221.16
  5203.8  222.53  5210.4  223.26  5218.1  223.19    5239  224.35  5258.8   224.8
#Mann= 3 ,-1 , 0
  4685.5     .11       0  4974.6     .07       0  5033.8     .11       0
Bank Sta=4974.6,5033.8
XS Rating Curve= 0 ,0
Exp/Cntr=0.3,0.1

Type RM Length L Ch R = 1 ,4978    ,429,429,429
BEGIN DESCRIPTION:
Mapping XS d60e0b61
END DESCRIPTION:
XS GIS Cut Line= 3
      3750008.29      10099162.7      3750565.58      10098977.8
      3750589.01      10098899.7
#Sta/Elev= 30
  4601.7  222.43  4727.7  218.45  4751.9  217.02  4846.9  214.51  4854.1  213.85
  4910.3  211.99  4917.3  211.36  4959.5  210.84  4980.5  211.59  4991.1  211.17
  5000.1  209.99  5003.3  208.99  5003.6  208.49  5031.8  210.91    5037  210.56
  5063.4  211.54  5068.7  212.51  5075.4  212.16  5081.7  212.47  5095.1  213.39
  5100.4  214.99  5126.8  215.55  5132.1   216.5  5149.1  217.14  5158.5  216.73
  5163.8  217.69  5199.5  219.86  5212.9   221.3  5251.1  222.08  5270.4  223.04
#Mann= 5 ,-1 , 0
  4601.7     .17       0  4991.1     .09       0  5031.8     .11       0
  5081.7     .17       0  5199.5     .11       0
Bank Sta=4991.1,5031.8
XS Rating Curve= 0 ,0
Exp/Cntr=0.3,0.1

Type RM Length L Ch R = 1 ,4549    ,322,322,322
BEGIN DESCRIPTION:
Mapping XS 4f80f787
END DESCRIPTION:
XS GIS Cut Line= 2
      3750211.42     10099449.15      3750810.41     10099186.12
#Sta/Elev= 30
    4668  218.77  4753.6  216.49  4860.7  212.82  4870.4  211.97  4875.9  212.28
  4893.5  210.73  4915.3  210.97  4937.1  208.24  4971.2  207.26  4980.8   207.1
  4991.8   206.2  4996.4  203.99  4999.9  203.99  5000.1  204.49  5013.6  207.17
  5021.5   207.5  5073.6  206.87    5097  207.48  5102.5  208.55  5120.4  210.26
  5158.9  212.49  5188.3  214.28  5195.9  214.06  5201.3  214.83  5210.2  214.45
  5219.2  215.48  5238.1  215.87  5264.8   216.1  5276.9  217.01  5322.2  217.48
#Mann= 6 ,-1 , 0
    4668     .17       0  4971.2     .15       0  4980.8     .09       0
  5013.6     .15       0  5158.9     .11       0  5238.1     .17       0
Bank Sta=4980.8,5013.6
XS Rating Curve= 0 ,0
Exp/Cntr=0.3,0.1

Type RM Length L Ch R = 1 ,4227    ,399,399,399
BEGIN DESCRIPTION:
Mapping XS cbe2c386
END DESCRIPTION:
XS GIS Cut Line= 4
      3750255.68     10099644.47      3750617.66     10099608.01
      3750945.79     10099386.66      3751139.34     10099223.26
#Sta/Elev= 30
       0  220.15   112.7  216.67   180.8  213.56   193.1  213.81   203.2  212.44
   213.2  212.74   253.4  210.87     286  207.72   303.7   206.8   368.7  205.73
   383.6  203.32   398.6  202.99   412.3  205.53   455.6  205.21   569.6  206.14
   593.2  207.86   599.5  209.71   605.5  210.02   641.5  210.16   650.4  210.97
   656.5  210.34   665.4  211.46   671.4  211.05   686.4  212.51   701.4  212.21
   722.4  213.46   906.4  218.36   957.1  218.47   963.6  219.01  1012.9  218.66
#Mann= 6 ,-1 , 0
       0     .17       0     286     .15       0   368.7     .09       0
   412.3     .15       0   455.6     .11       0   722.4     .17       0
Bank Sta=368.7,412.3
XS Rating Curve= 0 ,0
Exp/Cntr=0.3,0.1

Type RM Length L Ch R = 1 ,3828    ,605,605,605
BEGIN DESCRIPTION:
CCLC 007 7.0
END DESCRIPTION:
XS GIS Cut Line= 4
      3750101.43     10099911.42      3750833.81     10099899.68
      3751188.55      10099467.3      3751198.39     10099270.95
#Sta/Elev= 30
       0  218.55    56.4  216.97   246.5  215.86   306.5  213.39   316.5  213.82
   386.5  211.49   396.5   210.6   426.5  210.08   446.5  208.78   476.5  209.64
   496.5  208.01   516.5  205.92   536.5  204.96   596.5  204.84   636.5  202.99
   686.5  202.59   925.7  202.96   954.4  204.91   976.4  207.84   983.1  210.33
  1011.8  209.97    1054  211.18  1110.8   210.9  1160.3  211.96  1168.2  211.45
  1174.7  212.43  1246.4  214.54    1308  215.03  1418.1  217.36  1488.3  217.31
#Mann= 3 ,-1 , 0
       0     .17       0   496.5     .06       0   976.4     .17       0
Bank Sta=496.5,976.4
XS Rating Curve= 0 ,0
Exp/Cntr=0.3,0.1

Type RM Length L Ch R = 1 ,3223    ,108,108,108
BEGIN DESCRIPTION:
Mapping XS 006454d2
END DESCRIPTION:
XS GIS Cut Line= 4
      3750546.26     10100812.07      3750552.53     10100730.48
      3751167.72     10100033.27      3751227.91     10099257.33
#Sta/Elev= 30
       0  218.72    21.1   218.4    31.1  216.86    41.1  216.35    51.2  214.57
    61.2  213.98     121  211.31   148.6  211.07     177  209.79   184.6  210.01
   198.8  207.38   205.5  205.14   227.3  202.95   340.2  202.49     602   203.5
   814.5  202.76   949.2  203.22  1244.5  202.82  1304.7  205.12  1324.8  207.49
  1333.2  209.48  1338.2  208.78  1344.8  209.82    1395  211.16  1445.1  212.31
  1455.2  211.87  1475.2  212.82  1515.4   213.2  1592.9  215.32  1789.9  217.26
#Mann= 3 ,-1 , 0
       0     .11       0   148.6     .06       0    1395     .17       0
Bank Sta=148.6,1395
XS Rating Curve= 0 ,0
Exp/Cntr=0.3,0.1

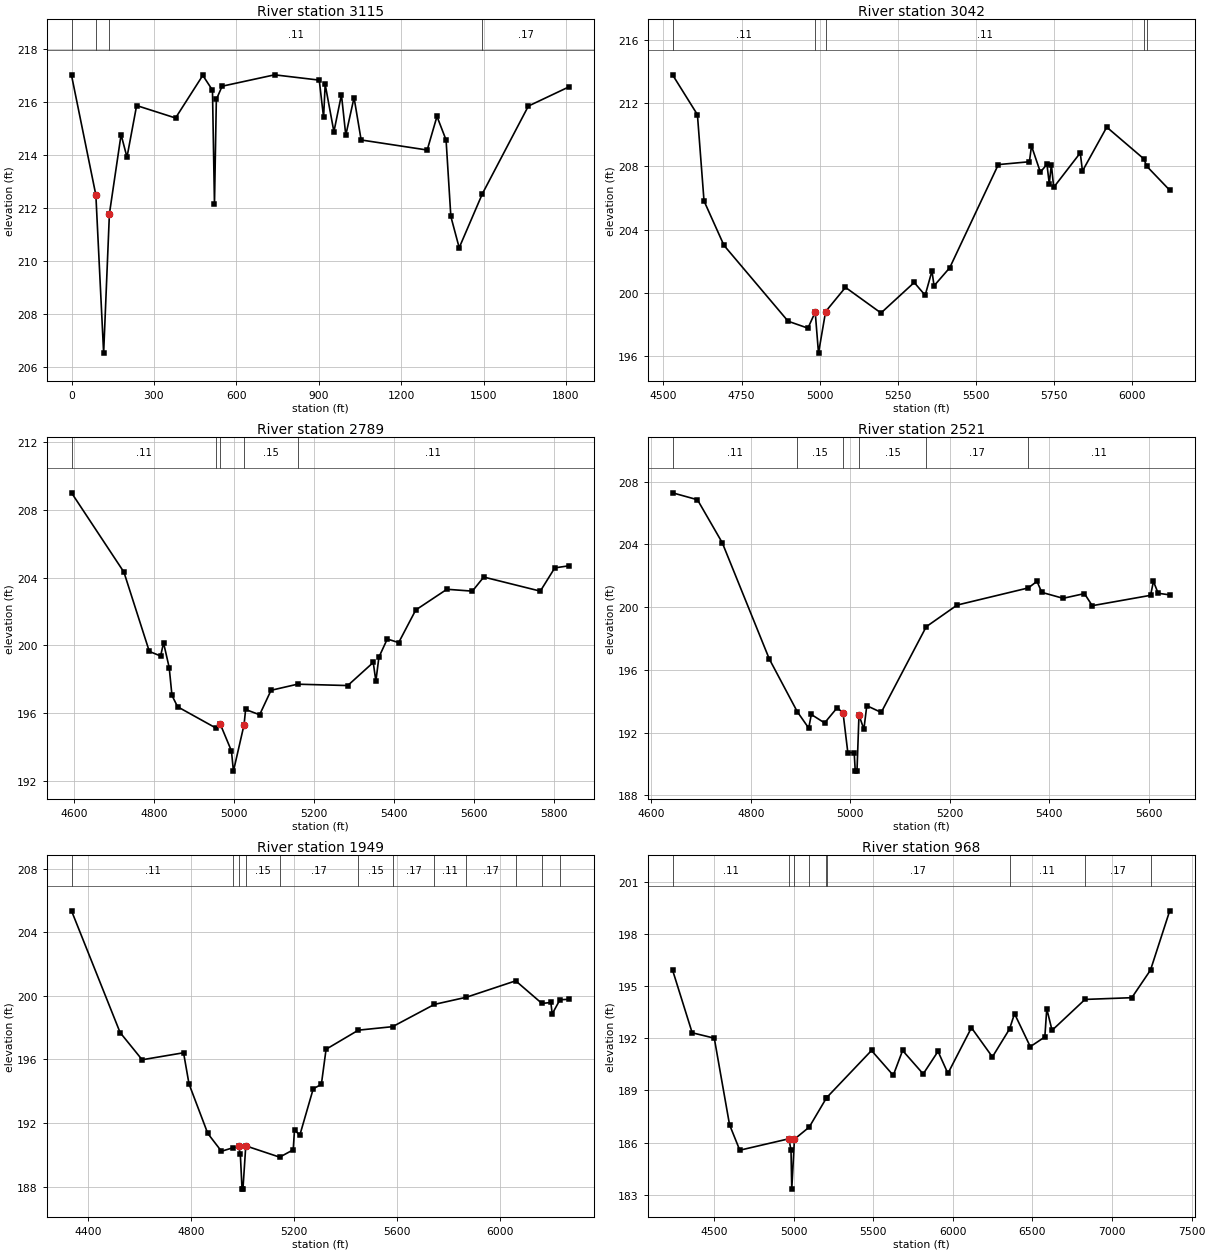
Type RM Length L Ch R = 1 ,3115    ,73,73,73
BEGIN DESCRIPTION:
Mapping XS fb638e77
END DESCRIPTION:
XS GIS Cut Line= 6
      3750612.16     10100800.63      3751216.33      10100154.8
      3751275.36     10100050.63      3751310.08     10099877.02
      3751251.05      10099491.6      3751257.44     10099252.78
#Sta/Elev= 30
       0  217.01    88.6  212.49   116.9  206.52   137.9  211.78   180.4  214.77
   201.9  213.92     237  215.87   378.7   215.4   477.9  217.01   513.1  216.45
   520.4  212.14   527.2   216.1   548.2   216.6   739.3  217.03   901.8  216.83
   917.6  215.42   923.4  216.67   955.2  214.88   982.6  216.28   998.4  214.75
  1028.5  216.17  1054.3  214.57  1294.8  214.19  1330.4  215.46  1363.5  214.57
  1380.9  211.68  1411.3   210.5  1495.7  212.54  1663.1  215.85  1809.8  216.57
#Mann= 4 ,-1 , 0
       0     .11       0    88.6     .06       0   137.9     .11       0
  1495.7     .17       0
Bank Sta=88.6,137.9
XS Rating Curve= 0 ,0
Exp/Cntr=0.3,0.1

Type RM Length L Ch R = 1 ,3042    ,253,253,253
BEGIN DESCRIPTION:
CCLC 007 6.0
END DESCRIPTION:
XS GIS Cut Line= 3
      3750695.52     10100811.02       3751041.1     10100449.42
      3751769.07     10099638.12
#Sta/Elev= 30
  4529.4  213.79  4608.9  211.27    4630  205.81  4693.8     203  4898.9   198.2
  4962.4  197.76 4985.67 198.776  4996.2  196.18    5019  198.81  5082.5  200.34
  5196.1  198.72  5302.3  200.65  5337.4  199.84  5359.1  201.38  5365.8  200.44
  5415.9  201.58  5571.4  208.11  5670.8  208.29  5677.5  209.29  5705.9  207.63
  5726.9  208.13  5734.3  206.91  5741.1  208.11  5748.5  206.67  5833.5  208.85
  5840.5   207.7  5918.2  210.48  6036.4  208.48  6046.5     208  6119.6  206.49
#Mann= 5 ,-1 , 0
  4529.4     .11       0 4985.67     .08       0    5019     .11       0
  6036.4     .17       0  6046.5     .11       0
Bank Sta=4985.67,5019
XS Rating Curve= 0 ,0
Exp/Cntr=0.3,0.1

Type RM Length L Ch R = 1 ,2789    ,268,268,268
BEGIN DESCRIPTION:
CCLC 007 5.0
END DESCRIPTION:
XS GIS Cut Line= 3
      3750921.18     10100939.53      3751203.58     10100646.31
      3751751.77      10100015.4
#Sta/Elev= 30
  4592.9  208.99  4723.9  204.32  4787.4  199.65  4815.7  199.38  4822.9  200.16
  4837.1   198.7    4844  197.06  4858.1  196.39  4955.3  195.12  4964.4  195.39
  4992.7  193.79  4997.7   192.6 5024.32195.3397  5028.1  196.23  5063.2  195.92
  5091.7  197.36    5158  197.72  5283.5  197.64  5347.2     199  5353.8   197.9
  5361.4  199.31  5382.3  200.38  5410.8  200.17  5453.5  202.09  5531.4  203.31
    5595   203.2  5623.5  204.03  5764.9   203.2  5801.1  204.57  5835.8  204.69
#Mann= 5 ,-1 , 0
  4592.9     .11       0  4955.3     .15       0  4964.4     .09       0
 5024.32     .15       0    5158     .11       0
Bank Sta=4964.4,5024.32
XS Rating Curve= 0 ,0
Exp/Cntr=0.3,0.1

Type RM Length L Ch R = 1 ,2521    ,572,572,572
BEGIN DESCRIPTION:
CCLC 007 4.0
END DESCRIPTION:
XS GIS Cut Line= 3
      3750962.84     10100990.74      3751310.08     10100877.89
      3751631.24     10100331.04
#Sta/Elev= 30
  4642.8  207.28  4692.8  206.84  4742.7   204.1  4837.3  196.69  4893.6  193.33
  4916.5  192.29  4921.7  193.16  4948.4  192.62    4974   193.6  4985.6  193.23
  4995.1  190.73  5007.9  190.73    5010  189.55  5013.5  189.55  5017.5  193.12
  5027.4  192.22  5033.2  193.72  5062.2  193.29  5152.7  198.75  5214.8  200.13
  5357.7  201.22  5375.3  201.64  5384.9  200.94  5427.8  200.56  5470.7  200.86
  5486.4  200.09  5603.6  200.75  5609.4  201.64  5618.9  200.88  5642.1  200.78
#Mann= 6 ,-1 , 0
  4642.8     .11       0  4893.6     .15       0  4985.6     .09       0
  5017.5     .15       0  5152.7     .17       0  5357.7     .11       0
Bank Sta=4985.6,5017.5
XS Rating Curve= 0 ,0
Exp/Cntr=0.3,0.1

Type RM Length L Ch R = 1 ,1949    ,981,981,981
BEGIN DESCRIPTION:
CCLC 007 3.0
END DESCRIPTION:
XS GIS Cut Line= 3
      3750917.87     10101111.08       3751388.2      10101407.4
       3751812.6     10100095.22
#Sta/Elev= 30
  4334.1  205.34  4523.2  197.69    4609  195.98  4770.2  196.42  4791.4  194.46
  4864.4  191.35  4917.7  190.23  4964.5  190.46 4984.19190.5708  4991.2  190.03
  4997.8  187.85  5001.3  187.85  5012.3  190.57  5144.2  189.86  5196.9  190.32
  5202.1  191.58  5222.5  191.23    5275  194.16  5306.5  194.43  5324.9  196.64
  5450.5  197.84  5583.8  198.06  5746.6  199.46  5871.1  199.91  6062.9  200.94
    6165  199.52  6199.8  199.58    6205  198.86  6235.1  199.75  6269.1  199.78
#Mann= 12 ,-1 , 0
  4334.1     .11       0  4964.5     .15       0 4984.19     .09       0
  5012.3     .15       0  5144.2     .17       0  5450.5     .15       0
  5583.8     .17       0  5746.6     .11       0  5871.1     .17       0
  6062.9     .11       0    6165     .17       0  6235.1     .11       0
Bank Sta=4984.19,5012.3
XS Rating Curve= 0 ,0
Exp/Cntr=0.3,0.1

Type RM Length L Ch R = 1 ,968     ,490,490,490
BEGIN DESCRIPTION:
CCLC 007 2.0
END DESCRIPTION:
XS GIS Cut Line= 4
      3751210.41       10101350.      3751531.43     10101897.85
      3752313.54     10101568.71      3751891.97     10099984.88
#Sta/Elev= 30
  4239.6  195.93  4362.8  192.32  4501.6  192.01  4597.4  187.03  4661.8  185.56
 4970.03186.2177  4983.5  185.57  4988.3  183.32 5005.08 186.195  5097.9  186.89
  5204.9  188.55  5206.7  188.58  5489.1   191.3  5625.8  189.87  5684.4   191.3
  5813.8  189.95  5906.9  191.25    5969  189.98  6116.8  192.61  6248.4  190.93
  6356.3  192.54  6387.4  193.42  6486.4  191.52  6577.8  192.08  6589.9   193.7
  6623.1  192.46  6830.2  194.24  7124.1  194.34  7241.5  195.93  7362.1  199.34
#Mann= 9 ,-1 , 0
  4239.6     .11       0 4970.03     .06       0 5005.08     .15       0
  5097.9     .15       0  5204.9     .11       0  5206.7     .17       0
  6356.3     .11       0  6830.2     .17       0  7241.5     .11       0
Bank Sta=4970.03,5005.08
XS Rating Curve= 0 ,0
Exp/Cntr=0.3,0.1

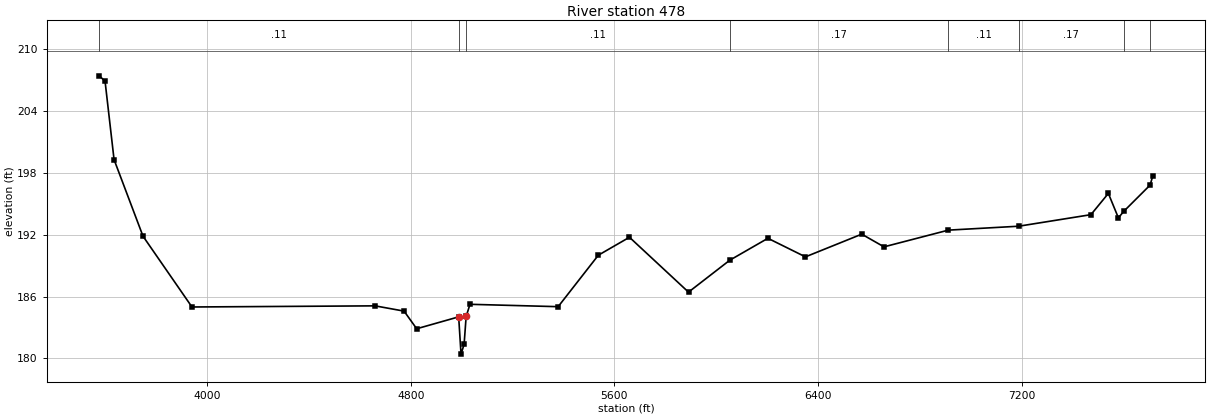
Type RM Length L Ch R = 1 ,478     ,0,0,0
BEGIN DESCRIPTION:
CCLC 007 1.0
END DESCRIPTION:
XS GIS Cut Line= 4
      3750576.57     10101350.98      3751689.75     10102236.92
      3752442.27     10101740.66      3751957.28     10099994.27
#Sta/Elev= 30
  3577.3   207.4  3599.8  206.87  3635.1  199.28  3748.8  191.85    3941  184.99
  4660.1   185.1  4773.9  184.59  4823.5  182.88 4988.36184.0331  4997.6  180.42
  5009.7  181.37  5017.7  184.07  5032.8  185.25    5379  185.02  5536.8  190.01
    5659  191.75  5890.9  186.43  6052.7  189.52  6202.7  191.65  6350.1  189.85
  6571.2  192.05  6658.6  190.82  6911.1  192.44  7187.4  192.82  7471.1  193.94
  7539.6     196    7579  193.63    7600  194.26  7703.2   196.8  7713.9  197.67
#Mann= 8 ,-1 , 0
  3577.3     .11       0 4988.36     .06       0  5017.7     .11       0
  6052.7     .17       0  6911.1     .11       0  7187.4     .17       0
    7600     .11       0  7703.2     .17       0
Bank Sta=4988.36,5017.7
XS Rating Curve= 0 ,0
Exp/Cntr=0.3,0.1

Chan Stop Cuts=-1
Use User Specified Reach Order=0
Composite Channel Slope=5