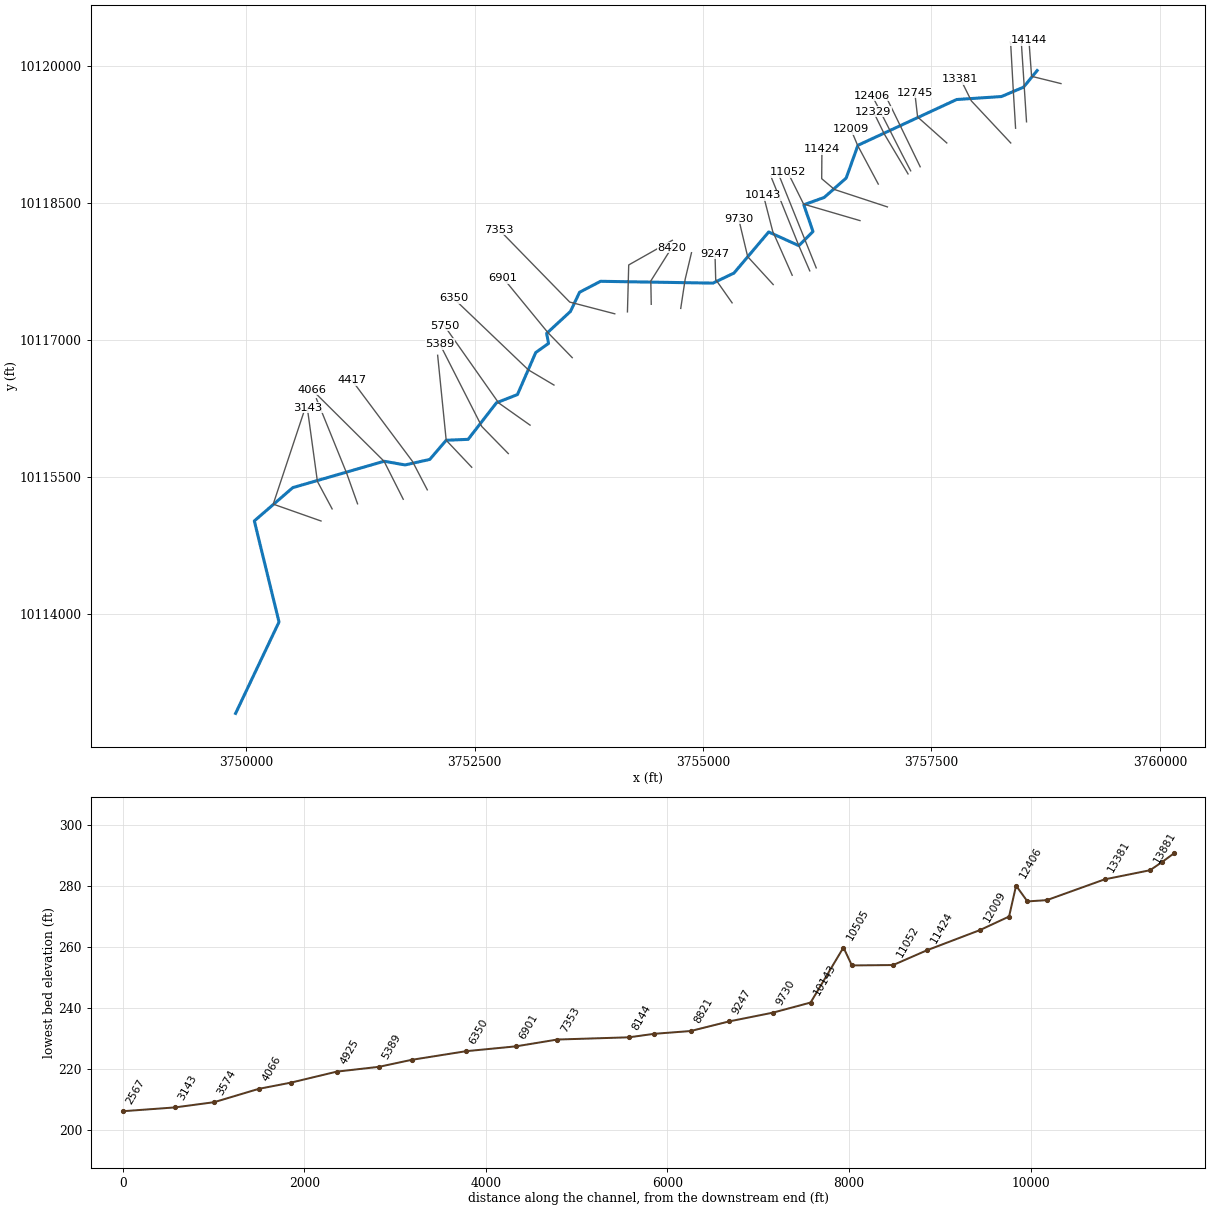
--- CCLC 010.prj (project) ---

Proj Title=CCLC 010 Base Level Engineering
Current Plan=p01
Default Exp/Contr=0.3,0.1
English Units
Geom File=g01
Flow File=f01
Flow File=f02
Plan File=p01
Y Axis Title=Elevation
X Axis Title(PF)=Main Channel Distance
X Axis Title(XS)=Station
BEGIN DESCRIPTION:
CCLC 010
END DESCRIPTION:
DSS Export Rating Curves= 0
DSS Export Rating Curve Sorted= 0
DSS Export Volume Flow Curves= 0
DXF OffsetX= 0
DXF OffsetY= 0
DXF ScaleX= 1
DXF ScaleY= 10

--- CCLC 010.p01 (plan) ---

Plan Title=Multiple Run
Short Identifier=Multiple
Geom File=g01
Flow File=f01
Subcritical Flow
K Sum by GR= 0
Std Step Tol= 0.01
Critical Tol= 0.01
Num of Std Step Trials= 20
Max Error Tol= 0.3
Flow Tol Ratio= 0.001
Split Flow NTrial= 30
Split Flow Tol= 0.02
Split Flow Ratio= 0.02
Log Output Level= 0
Friction Slope Method= 1
Unsteady Friction Slope Method= 2
Unsteady Bridges Friction Slope Method= 1
Parabolic Critical Depth
Global Vel Dist=  1 , 1 , 1
Global Log Level= 0
CheckData=True
Encroach Param= -1, 0, 0, 0
BEGIN DESCRIPTION:
Multiple Run
END DESCRIPTION:

--- CCLC 010.f01 (steady flow) ---

Flow Title=Multiple
Program Version=4.10
Number of Profiles= 7
Profile Names=10-year,25-year,50-year,1pct_min,100-year,1pct_plu,500-year
River Rch & RM=CCLC 010,Reach-1         ,14144
     436     584     784     348    1052    3177    1947
River Rch & RM=CCLC 010,Reach-1         ,12406
     586     801    1088     488    1473    4448    2790
River Rch & RM=CCLC 010,Reach-1         ,10143
     690     949    1297     584    1764    5327    3371
River Rch & RM=CCLC 010,Reach-1         ,7353
    1251    1766    2454    1120    3383   10216    6650
Boundary for River Rch & Prof#=CCLC 010,Reach-1         , 1
Up Type= 0
Dn Type= 3
Dn Slope=0.005
Boundary for River Rch & Prof#=CCLC 010,Reach-1         , 2
Up Type= 0
Dn Type= 3
Dn Slope=0.005
Boundary for River Rch & Prof#=CCLC 010,Reach-1         , 3
Up Type= 0
Dn Type= 3
Dn Slope=0.005
Boundary for River Rch & Prof#=CCLC 010,Reach-1         , 4
Up Type= 0
Dn Type= 3
Dn Slope=0.005
Boundary for River Rch & Prof#=CCLC 010,Reach-1         , 5
Up Type= 0
Dn Type= 3
Dn Slope=0.005
Boundary for River Rch & Prof#=CCLC 010,Reach-1         , 6
Up Type= 0
Dn Type= 3
Dn Slope=0.005
Boundary for River Rch & Prof#=CCLC 010,Reach-1         , 7
Up Type= 0
Dn Type= 3
Dn Slope=0.005
DSS Import GetInterval= 0
DSS Import GetPeak= 0
DSS Import FillOption= 0

--- CCLC 010.f02 (steady flow) ---

Flow Title=Orig_BLE_Flows
Program Version=4.10
Number of Profiles= 7
Profile Names=10-year,25-year,50-year,1pct_min,100-year,1pct_plu,500-year
River Rch & RM=CCLC 010,Reach-1         ,14144
     436     573     682     268     809    2443    1132
River Rch & RM=CCLC 010,Reach-1         ,12406
     586     785     946     375    1133    3423    1622
River Rch & RM=CCLC 010,Reach-1         ,10143
     690     930    1128     449    1357    4097    1960
River Rch & RM=CCLC 010,Reach-1         ,7353
    1251    1731    2134     861    2602    7857    3866
Boundary for River Rch & Prof#=CCLC 010,Reach-1         , 1
Up Type= 0
Dn Type= 3
Dn Slope=0.005
Boundary for River Rch & Prof#=CCLC 010,Reach-1         , 2
Up Type= 0
Dn Type= 3
Dn Slope=0.005
Boundary for River Rch & Prof#=CCLC 010,Reach-1         , 3
Up Type= 0
Dn Type= 3
Dn Slope=0.005
Boundary for River Rch & Prof#=CCLC 010,Reach-1         , 4
Up Type= 0
Dn Type= 3
Dn Slope=0.005
Boundary for River Rch & Prof#=CCLC 010,Reach-1         , 5
Up Type= 0
Dn Type= 3
Dn Slope=0.005
Boundary for River Rch & Prof#=CCLC 010,Reach-1         , 6
Up Type= 0
Dn Type= 3
Dn Slope=0.005
Boundary for River Rch & Prof#=CCLC 010,Reach-1         , 7
Up Type= 0
Dn Type= 3
Dn Slope=0.005
DSS Import GetInterval= 0
DSS Import GetPeak= 0
DSS Import FillOption= 0

--- CCLC 010.g01 (geometry) ---

Geom Title=Existing Conditions
Program Version=4.10

River Reach=CCLC 010        ,Reach-1
Reach XY= 30
      3758656.85     10119953.58      3758507.11     10119771.28
      3758266.23     10119669.29      3757775.78     10119636.74
      3756695.05     10119135.43      3756567.01     10118777.36
      3756326.12     10118564.69       3756102.6     10118484.39
      3756203.23     10118191.84      3756048.23     10118036.84
      3755718.23     10118186.84      3755338.23     10117736.84
      3755108.23     10117626.84      3753878.23     10117646.84
      3753648.23     10117526.84      3753548.23     10117316.84
      3753288.23     10117076.84      3753308.23     10116966.84
      3753168.23     10116866.84      3752968.23     10116406.84
      3752738.23     10116316.84      3752428.23     10115916.84
      3752188.23     10115906.84      3752008.23     10115696.84
      3751738.23     10115636.84      3751508.23     10115676.84
      3750508.96     10115388.17      3750087.96     10115023.72
      3750358.15     10113917.81      3749882.91     10112917.14

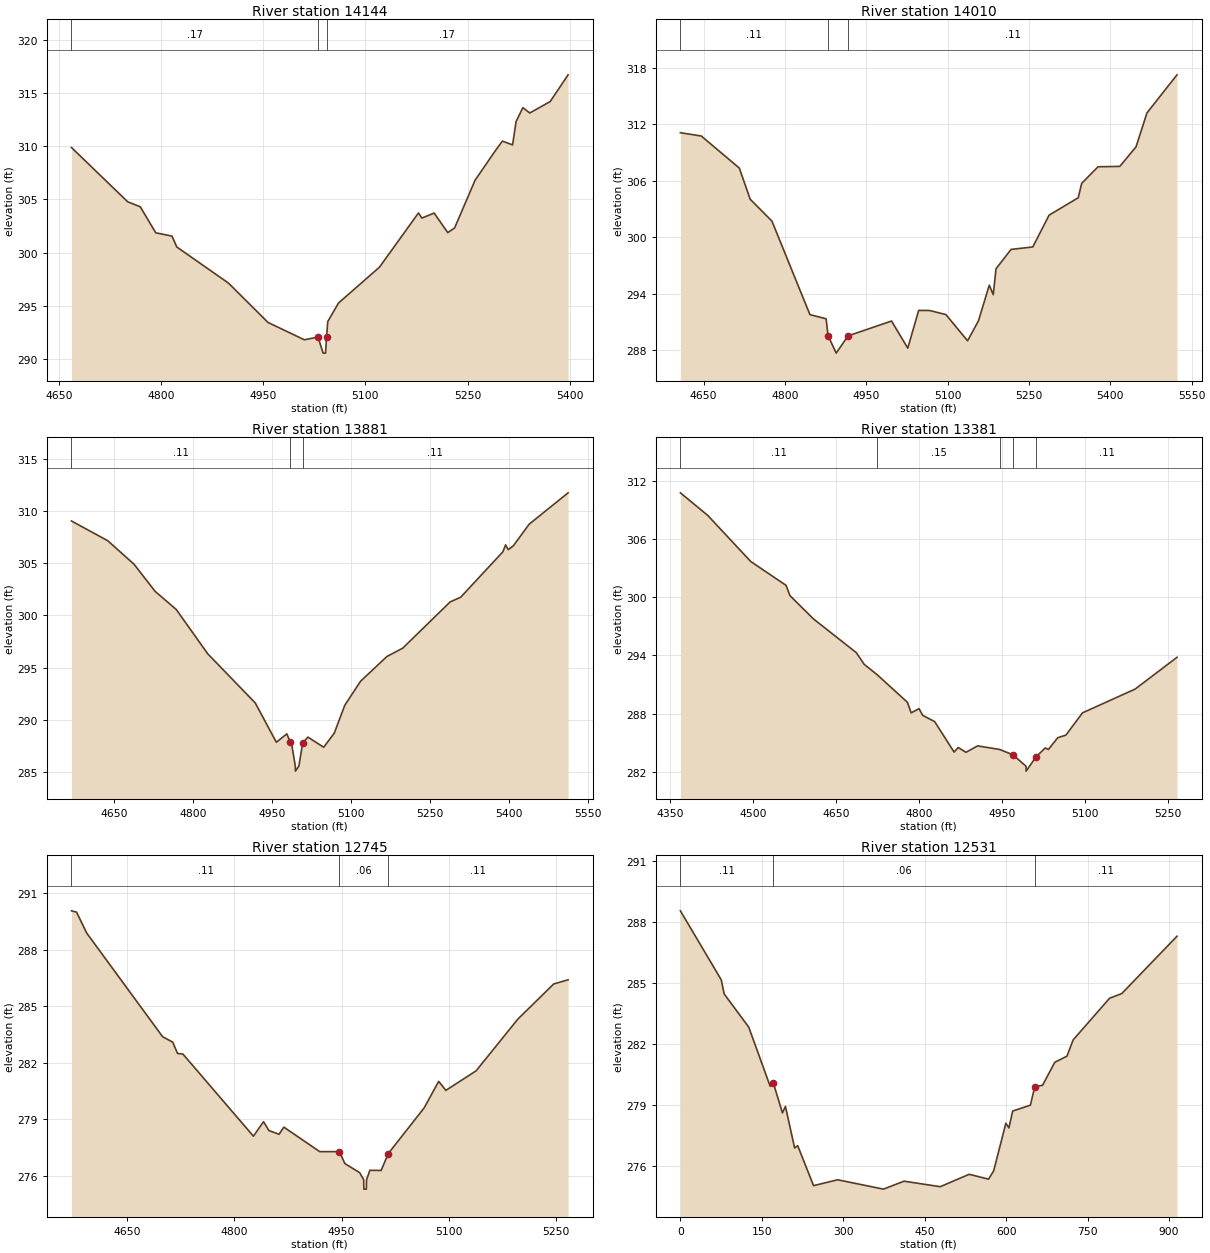
Type RM Length L Ch R = 1 ,14144   ,134,134,134
BEGIN DESCRIPTION:
CCLC 010 25.0
END DESCRIPTION:
XS GIS Cut Line= 3
      3758917.89     10119811.06      3758596.09     10119890.64
      3758566.86     10120287.27
#Sta/Elev= 30
  4668.5  309.87    4751  304.78  4769.5  304.31  4792.2  301.87  4816.1  301.56
  4823.1  300.54    4899  297.15    4957  293.46  5010.5  291.83  5030.5  292.09
    5038  290.58  5041.5  290.58 5043.08292.1298  5044.8  293.54  5060.6  295.28
  5120.8  298.65    5178  303.73    5183  303.25    5201  303.72    5221  301.89
  5231.1  302.33  5261.1   306.8  5291.2   309.6  5301.2  310.47  5316.2  310.12
  5321.3   312.3  5331.3  313.61  5341.4  313.11  5371.4  314.18  5397.7  316.69
#Mann= 3 ,-1 , 0
  4668.5     .17       0  5030.5     .09       0 5043.08     .17       0
Bank Sta=5030.5,5043.08
XS Rating Curve= 0 ,0
Exp/Cntr=0.3,0.1

Type RM Length L Ch R = 1 ,14010   ,129,129,129
BEGIN DESCRIPTION:
Mapping XS e7bcb52e
END DESCRIPTION:
XS GIS Cut Line= 2
      3758540.73     10119392.65      3758480.85     10120306.39
#Sta/Elev= 30
  4607.3  311.09  4645.8  310.74    4716  307.33    4736  304.02  4776.1   301.7
  4846.2  291.76    4876  291.32 4879.61289.5295  4894.6  287.67  4916.4   289.5
  4996.6  291.08  5026.6   288.2  5046.7  292.21  5066.7   292.2  5096.8  291.77
  5136.9  288.98  5156.9   291.1  5176.9  294.89  5184.2  293.88  5189.3  296.63
    5217  298.69  5257.1  298.95  5287.2  302.33  5340.9  304.18  5347.3  305.71
  5377.4  307.47  5417.5  307.51  5447.5  309.59  5467.6  313.19    5523  317.24
#Mann= 3 ,-1 , 0
  4607.3     .11       0 4879.61     .06       0  4916.4     .11       0
Bank Sta=4879.61,4916.4
XS Rating Curve= 0 ,0
Exp/Cntr=0.3,0.1

Type RM Length L Ch R = 1 ,13881   ,500,500,500
BEGIN DESCRIPTION:
CCLC 010 24.0
END DESCRIPTION:
XS GIS Cut Line= 3
      3758420.94      10119322.3      3758394.89     10119752.02
      3758366.25     10120265.02
#Sta/Elev= 30
  4568.6  309.05  4637.5  307.16  4687.6   304.9  4727.7   302.3  4767.7  300.57
  4827.8  296.31    4918  291.61  4958.1  287.84  4978.1  288.64 4984.19 287.891
  4988.1  287.41  4994.1  285.57  4994.4  285.07  5001.1  285.57  5008.2  287.79
  5018.2  288.33  5048.2  287.36  5068.3  288.71  5088.3  291.39  5118.3  293.69
  5168.4  296.06  5198.5  296.86  5288.6  301.29  5308.6  301.74  5388.8  306.09
  5394.1  306.76  5399.1   306.3  5408.8  306.67  5438.8  308.74  5512.9  311.75
#Mann= 3 , 0 , 0
  4568.6     .11       0 4984.19     .06       0  5008.2     .11       0
Bank Sta=4984.19,5008.2
XS Rating Curve= 0 ,0
Exp/Cntr=0.3,0.1

Type RM Length L Ch R = 1 ,13381   ,636,636,636
BEGIN DESCRIPTION:
CCLC 010 23.0
END DESCRIPTION:
XS GIS Cut Line= 3
      3758367.85     10119161.08      3757936.56     10119621.81
      3757817.85     10119861.08
#Sta/Elev= 30
  4368.5  310.74  4418.1  308.41  4495.7  303.67  4559.7  301.21  4566.6  300.16
  4609.1  297.76  4686.7  294.28  4700.9  293.08  4724.8  291.99  4779.1  289.17
  4785.9  288.08  4800.1  288.51  4806.9  287.82  4828.4  287.18  4863.6  284.04
  4870.9  284.51  4885.1  284.02  4906.1  284.68  4945.9  284.31  4970.1  283.76
  4993.7  282.58  4993.9  282.08  5011.7  283.55  5028.6  284.47  5034.1  284.31
    5051  285.52  5065.8  285.79  5095.8  288.08    5191  290.53  5266.7   293.8
#Mann= 5 ,-1 , 0
  4368.5     .11       0  4724.8     .15       0  4945.9     .11       0
  4970.1     .06       0  5011.7     .11       0
Bank Sta=4970.1,5011.7
XS Rating Curve= 0 ,0
Exp/Cntr=0.3,0.1

Type RM Length L Ch R = 1 ,12745   ,214,214,214
BEGIN DESCRIPTION:
CCLC 010 22.0
END DESCRIPTION:
XS GIS Cut Line= 3
      3757667.85     10119161.08      3757348.26     10119445.76
      3757317.86     10119711.03
#Sta/Elev= 30
    4572  290.06  4579.1  289.99  4593.3  288.88  4699.5  283.38  4713.7  283.09
  4720.4  282.49  4727.9  282.46  4826.6   278.1  4840.8  278.87  4848.3   278.4
  4862.5   278.2  4869.2  278.58  4919.4  277.28    4947  277.28  4954.5  276.65
  4975.4  276.16  4980.9  275.79  4981.2  275.29  4984.7  275.29  4984.9  275.79
  4989.6  276.29  5005.3  276.28  5015.4  277.18  5065.7  279.61  5085.9  281.01
  5095.9  280.53  5138.3  281.57  5196.6  284.31  5246.9  286.18    5267   286.4
#Mann= 3 , 0 , 0
    4572     .11       0    4947     .06       0  5015.4     .11       0
Bank Sta=4947,5015.4
XS Rating Curve= 0 ,0
Exp/Cntr=0.3,0.1

Type RM Length L Ch R = 1 ,12531   ,125,125,125
BEGIN DESCRIPTION:
Mapping XS 56061c78
END DESCRIPTION:
XS GIS Cut Line= 3
      3757376.66     10118900.46      3757091.47     10119487.62
       3756975.5      10119722.6
#Sta/Elev= 30
       0  288.56    75.2  285.17    80.7  284.47   125.9  282.84   165.4  279.93
     171  280.11     188  278.62   193.5  278.94   210.5  276.89   216.1  277.01
   245.3  275.04   289.7  275.33     374  274.87     412  275.26   478.7  274.99
     532   275.6   567.7  275.36   577.1  275.77   599.6  278.11   605.2  277.88
   612.1  278.71   644.8     279   652.8  279.91   667.2  279.98   689.7  281.11
   712.1  281.41   723.5  282.21   790.6  284.26   813.1  284.49   914.8  287.31
#Mann= 3 , 0 , 0
       0     .11       0     171     .06       0   652.8     .11       0
Bank Sta=171,652.8
XS Rating Curve= 0 ,0
Exp/Cntr=0.3,0.1

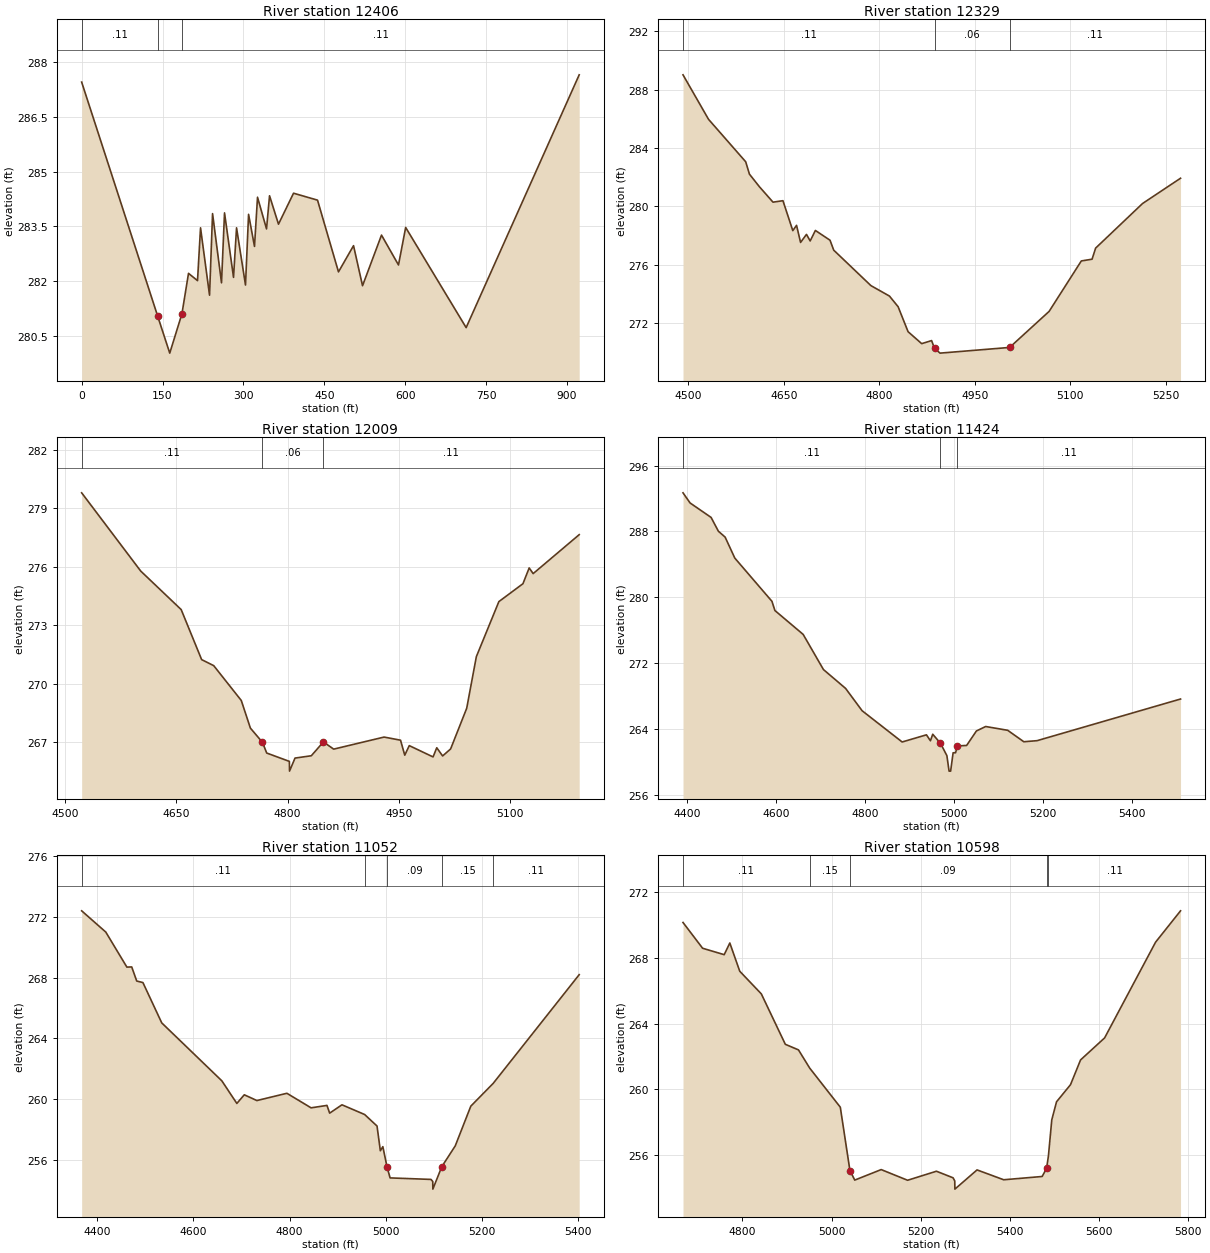
Type RM Length L Ch R = 1 ,12406   ,77,77,77
BEGIN DESCRIPTION:
Mapping XS 9bc97dd0
END DESCRIPTION:
XS GIS Cut Line= 4
       3757272.5     10118856.19      3757178.75     10119035.87
      3756930.92      10119524.1       3756850.5     10119678.33
#Sta/Elev= 30
       0  287.46   140.9  281.04   163.4  280.02     186   281.1   198.2  282.21
   214.9  282.01   220.5  283.46   237.2  281.61   242.8  283.85   259.4  281.95
     265  283.87   281.7   282.1   287.3  283.46   303.9  281.89   309.6  283.83
   320.6  282.95   326.2   284.3   342.9  283.43   348.5  284.34   365.1  283.56
     393  284.41   437.5  284.22   476.4  282.25   504.3  282.97     521  281.87
   556.2  283.26   587.7  282.44     601  283.47   713.2  280.72   922.9  287.66
#Mann= 3 , 0 , 0
       0     .11       0   140.9     .06       0     186     .11       0
Bank Sta=140.9,186
XS Rating Curve= 0 ,0
Exp/Cntr=0.3,0.1

Type RM Length L Ch R = 1 ,12329   ,320,320,320
BEGIN DESCRIPTION:
CCLC 010 21.0
END DESCRIPTION:
XS GIS Cut Line= 3
      3757243.84     10118822.35      3756983.67     10119259.13
      3756863.63     10119504.66
#Sta/Elev= 30
  4491.6  289.01  4531.7  285.96  4590.1  283.05    4596   282.2  4611.6  281.34
    4633  280.28  4648.6  280.38  4664.1  278.33    4670  278.69  4676.3  277.52
  4685.6  278.07  4691.4  277.62  4699.6  278.34  4722.6  277.67  4728.4  276.99
  4786.8  274.56    4816  273.84  4829.6  273.11  4845.2   271.4  4866.6  270.58
  4882.2  270.79 4886.75270.2487  4895.5  269.93  5004.8  270.32  5066.8  272.79
  5117.4  276.25  5134.3  276.37  5139.9  277.13  5213.7  280.19  5273.3  281.92
#Mann= 3 ,-1 , 0
  4491.6     .11       0 4886.75     .06       0  5004.8     .11       0
Bank Sta=4886.75,5004.8
XS Rating Curve= 0 ,0
Exp/Cntr=0.3,0.1

Type RM Length L Ch R = 1 ,12009   ,585,585,585
BEGIN DESCRIPTION:
CCLC 010 20.0
END DESCRIPTION:
XS GIS Cut Line= 3
      3756917.87     10118711.04      3756691.77     10119134.83
      3756617.87     10119311.03
#Sta/Elev= 30
  4522.2   279.8  4601.9  275.78  4656.5   273.8  4684.1  271.23  4700.4  270.92
  4737.6  269.13  4749.9  267.71  4766.2  266.98  4771.9  266.43  4802.5     266
  4802.7   265.5  4810.1  266.17  4832.1  266.29  4848.4     267  4862.3  266.63
  4930.3  267.25  4952.5  267.09  4958.2  266.32  4964.3  266.81  4996.4  266.23
  5001.4   266.7  5009.3  266.28  5020.1  266.64  5041.8  268.73  5054.8  271.38
  5085.2  274.21  5117.7  275.13  5126.1  275.94  5131.5  275.65  5193.6  277.65
#Mann= 3 , 0 , 0
  4522.2     .11       0  4766.2     .06       0  4848.4     .11       0
Bank Sta=4766.2,4848.4
XS Rating Curve= 0 ,0
Exp/Cntr=0.3,0.1

Type RM Length L Ch R = 1 ,11424   ,372,372,372
BEGIN DESCRIPTION:
CCLC 010 19.0
END DESCRIPTION:
XS GIS Cut Line= 4
      3757017.85     10118461.07      3756438.97     10118651.49
      3756298.54     10118770.25      3756301.14     10119095.73
#Sta/Elev= 30
  4390.6  292.69  4406.5  291.46  4453.8   289.7  4470.1  288.03  4485.3  287.31
  4507.1  284.76  4590.6  279.51  4597.3  278.39  4660.8  275.49  4706.4  271.22
  4756.2  268.93  4793.3  266.22  4883.4  262.42    4938  263.29    4947  262.57
  4952.2  263.36  4969.6  262.26    4984  260.76  4988.9  258.88  4992.4  258.88
    4998  261.11  5003.5  261.11  5007.6  261.94  5028.4     262  5050.4  263.76
  5071.3   264.3  5120.7  263.84    5157  262.45  5186.8  262.58  5509.4  267.64
#Mann= 3 , 0 , 0
  4390.6     .11       0  4969.6     .06       0  5007.6     .11       0
Bank Sta=4969.6,5007.6
XS Rating Curve= 0 ,0
Exp/Cntr=0.3,0.1

Type RM Length L Ch R = 1 ,11052   ,454,454,454
BEGIN DESCRIPTION:
CCLC 010 18.0
END DESCRIPTION:
XS GIS Cut Line= 3
      3756717.89     10118311.06      3756100.62      10118491.6
      3755926.15     10118843.16
#Sta/Elev= 30
  4367.3   272.4  4417.5     271  4461.4  268.69  4471.5   268.7  4481.9  267.77
  4494.8  267.67    4534  265.01  4659.1  261.19  4690.3   259.7  4705.8  260.27
    4732  259.89  4794.5  260.37  4844.8  259.41  4877.9  259.57  4883.5  259.06
  4909.1  259.61  4956.3  258.97  4982.1  258.21    4989  256.58  4994.2  256.85
  5002.9  255.52  5009.3  254.79  5094.5  254.69  5098.1  254.55  5098.3  254.05
  5116.9  255.53  5144.9   256.9  5177.3  259.52  5223.8  261.02  5402.9  268.19
#Mann= 5 ,-1 , 0
  4367.3     .11       0  4956.3     .15       0  5002.9     .09       0
  5116.9     .15       0  5223.8     .11       0
Bank Sta=5002.9,5116.9
XS Rating Curve= 0 ,0
Exp/Cntr=0.3,0.1

Type RM Length L Ch R = 1 ,10598   ,93,93,93
BEGIN DESCRIPTION:
Mapping XS 1a5d4e3e
END DESCRIPTION:
XS GIS Cut Line= 2
      3756238.64     10117793.69      3755822.41     10118829.06
#Sta/Elev= 30
  4666.7  270.17  4710.7   268.6  4759.1  268.21  4771.7  268.92    4794   267.2
  4842.4  265.82  4896.2  262.75  4925.7  262.41  4950.9   261.3  5019.5  258.92
  5041.1  255.06  5051.9  254.48  5111.2  255.12  5170.4  254.47  5235.1  255.02
  5272.4  254.62  5276.2  254.43  5276.5  253.93  5326.2   255.1    5386   254.5
  5472.2   254.7  5482.1  255.19  5486.3  255.95  5493.8  258.15  5504.5  259.25
  5535.8  260.29  5558.4   261.8  5612.3  263.14  5726.6  268.97  5782.6  270.88
#Mann= 5 ,-1 , 0
  4666.7     .11       0  4950.9     .15       0  5041.1     .09       0
  5482.1     .15       0  5486.3     .11       0
Bank Sta=5041.1,5482.1
XS Rating Curve= 0 ,0
Exp/Cntr=0.3,0.1

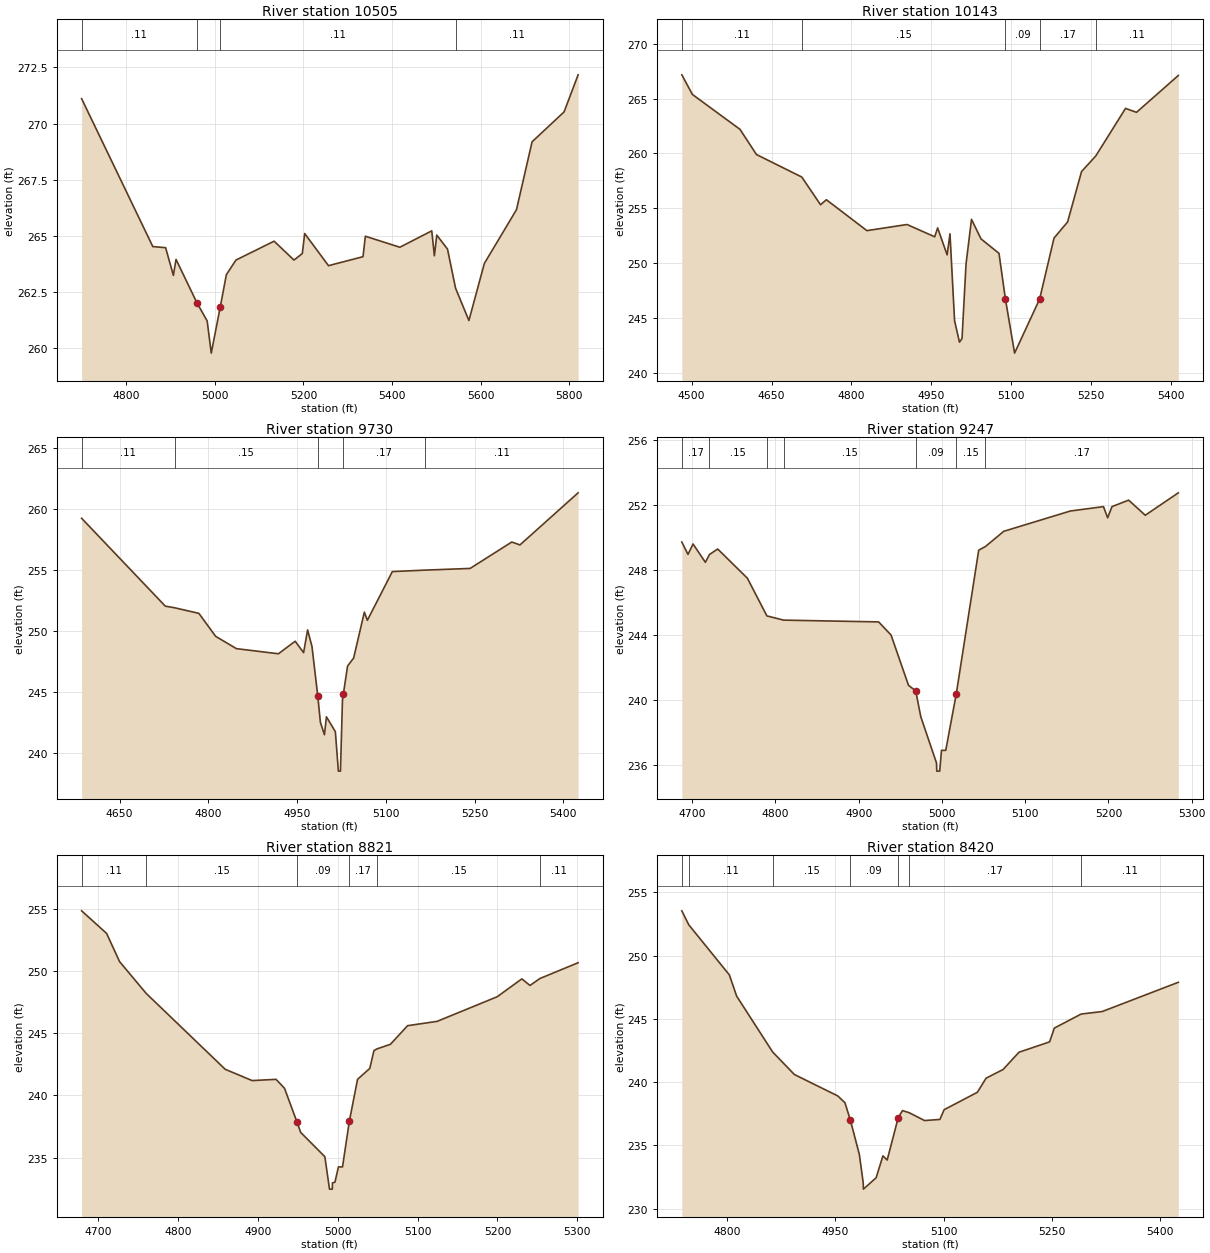
Type RM Length L Ch R = 1 ,10505   ,362,362,362
BEGIN DESCRIPTION:
CCLC 010 17.0
END DESCRIPTION:
XS GIS Cut Line= 3
      3756167.85     10117761.07      3756048.23     10118036.84
      3755741.83     10118797.45
#Sta/Elev= 30
  4699.4  271.11  4860.1  264.53    4889  264.48  4906.5  263.25  4912.5  263.96
  4959.4  262.04  4982.8  261.22    4992  259.79  5012.2  261.83  5026.1  263.28
  5047.7  263.93  5133.9  264.77  5178.7  263.93  5197.5  264.22  5202.9  265.11
  5256.6  263.68  5334.5  264.08  5339.8  264.99  5417.7   264.5  5489.7  265.23
  5495.6  264.12    5501  265.04  5525.2  264.42  5543.4  262.68  5573.5  261.24
  5608.4  263.78  5680.9  266.17  5716.1  269.19  5788.3  270.52    5820  272.17
#Mann= 4 ,-1 , 0
  4699.4     .11       0  4959.4     .09       0  5012.2     .11       0
  5543.4     .11       0
Bank Sta=4959.4,5012.2
XS Rating Curve= 0 ,0
Exp/Cntr=0.3,0.1

Type RM Length L Ch R = 1 ,10143   ,413,413,413
BEGIN DESCRIPTION:
CCLC 010 16.0
END DESCRIPTION:
XS GIS Cut Line= 3
      3755975.64     10117712.91      3755762.08     10118194.73
      3755660.76     10118587.03
#Sta/Elev= 30
  4481.6  267.16  4501.5  265.37  4590.8  262.19  4621.8  259.89  4706.8  257.84
  4742.1  255.31    4753  255.77  4829.1  252.95  4904.4  253.51  4956.4  252.39
  4961.9   253.2  4979.7  250.74  4985.1  252.66  4993.7  244.74  5002.9  242.78
  5007.7  243.11  5015.2   249.9  5025.5  253.98  5043.3   252.2  5077.1  250.88
  5089.1  246.73  5106.4  241.78  5153.4  246.71  5180.4  252.27  5205.9  253.74
  5232.1  258.34  5258.8  259.76  5314.7   264.1  5335.3  263.74  5413.8   267.1
#Mann= 5 ,-1 , 0
  4481.6     .11       0  4706.8     .15       0  5089.1     .09       0
  5153.4     .17       0  5258.8     .11       0
Bank Sta=5089.1,5153.4
XS Rating Curve= 0 ,0
Exp/Cntr=0.3,0.1

Type RM Length L Ch R = 1 ,9730    ,483,483,483
BEGIN DESCRIPTION:
CCLC 010 15.0
END DESCRIPTION:
XS GIS Cut Line= 3
      3755767.82     10117611.11      3755488.23     10117916.84
      3755389.68     10118330.16
#Sta/Elev= 30
  4585.7  259.26  4727.2  252.04  4742.7  251.91  4783.9  251.45  4812.3  249.56
  4847.4  248.55  4918.4  248.13  4946.7  249.16  4960.9  248.22  4967.7  250.09
  4975.1  248.72 4984.96 244.623  4989.3   242.5  4996.1  241.48  4999.5  242.95
  5014.6  241.73  5019.7  238.49  5023.2  238.49  5026.6  244.33 5028.12244.8231
  5035.2  247.12  5045.5  247.78  5063.6  251.55  5068.7  250.88  5110.9  254.88
  5165.7     255  5242.4  255.14  5312.8  257.31  5326.6  257.07  5424.9  261.35
#Mann= 5 ,-1 , 0
  4585.7     .11       0  4742.7     .15       0 4984.96     .09       0
 5028.12     .17       0  5165.7     .11       0
Bank Sta=4984.96,5028.12
XS Rating Curve= 0 ,0
Exp/Cntr=0.3,0.1

Type RM Length L Ch R = 1 ,9247    ,426,426,426
BEGIN DESCRIPTION:
CCLC 010 14.0
END DESCRIPTION:
XS GIS Cut Line= 3
      3755317.83     10117411.11      3755138.23     10117666.84
      3755130.55     10117950.74
#Sta/Elev= 30
  4687.5  249.73  4694.9  248.97    4701  249.61  4715.8  248.48  4720.7  248.96
  4730.6   249.3  4766.3   247.5  4789.7  245.18  4809.8  244.92    4924  244.81
  4938.9     244  4959.8  240.91  4968.5  240.56  4974.6  238.97  4993.5  236.12
  4993.8  235.62  4997.3  235.62  4999.5   236.9  5004.6   236.9 5017.19240.3658
  5044.2  249.23  5052.2  249.45  5074.3  250.39  5154.3  251.64  5194.1  251.91
  5199.1  251.22  5204.3  251.91  5224.3  252.31  5244.3  251.38    5284  252.76
#Mann= 7 ,-1 , 0
  4687.5     .17       0  4720.7     .15       0  4789.7     .17       0
  4809.8     .15       0  4968.5     .09       0 5017.19     .15       0
  5052.2     .17       0
Bank Sta=4968.5,5017.19
XS Rating Curve= 0 ,0
Exp/Cntr=0.3,0.1

Type RM Length L Ch R = 1 ,8821    ,401,401,401
BEGIN DESCRIPTION:
CCLC 010 13.0
END DESCRIPTION:
XS GIS Cut Line= 3
      3754755.55     10117350.09      3754804.16      10117669.5
      3754873.23      10117959.6
#Sta/Elev= 30
  4679.6  254.87  4710.9  253.05  4727.1  250.78  4760.4  248.22  4859.3  242.11
    4893   241.2  4922.9   241.3  4933.5  240.58 4949.05237.8726  4953.7  237.03
    4984  235.07  4989.8  232.46  4993.3  232.46  4993.5  232.96  4996.6  233.02
    5001  234.25  5006.1  234.25  5014.6  237.92  5024.9   241.3  5040.2  242.18
  5045.4  243.61  5049.1  243.75    5066  244.12  5087.5  245.62  5124.5  245.97
  5199.6  247.95  5230.5  249.39  5240.7  248.86  5253.1  249.42  5300.9  250.69
#Mann= 6 ,-1 , 0
  4679.6     .11       0  4760.4     .15       0 4949.05     .09       0
  5014.6     .17       0  5049.1     .15       0  5253.1     .11       0
Bank Sta=4949.05,5014.6
XS Rating Curve= 0 ,0
Exp/Cntr=0.3,0.1

Type RM Length L Ch R = 1 ,8420    ,276,276,276
BEGIN DESCRIPTION:
CCLC 010 12.0
END DESCRIPTION:
XS GIS Cut Line= 3
      3754432.63     10117395.19      3754428.09     10117650.73
      3754658.13     10118016.41
#Sta/Elev= 30
  4737.2  253.55  4746.9  252.44  4803.1  248.48  4813.1  246.81    4863  242.39
  4893.1  240.61  4953.1  238.92  4963.1  238.38 4970.56237.0223  4983.1  234.28
  4988.4  232.05  4988.7  231.55  5006.3  232.45  5015.7  234.18  5021.6  233.85
  5036.9   237.2  5042.8  237.76  5052.1  237.59  5073.4  236.97  5094.6  237.06
  5100.5  237.83  5146.4   239.2  5158.6  240.32  5182.2  241.01  5204.1  242.37
  5246.5  243.19  5253.1  244.28  5290.2  245.39  5319.5  245.59  5424.8   247.9
#Mann= 7 ,-1 , 0
  4737.2     .17       0  4746.9     .11       0    4863     .15       0
 4970.56     .09       0  5036.9     .15       0  5052.1     .17       0
  5290.2     .11       0
Bank Sta=4970.56,5036.9
XS Rating Curve= 0 ,0
Exp/Cntr=0.3,0.1

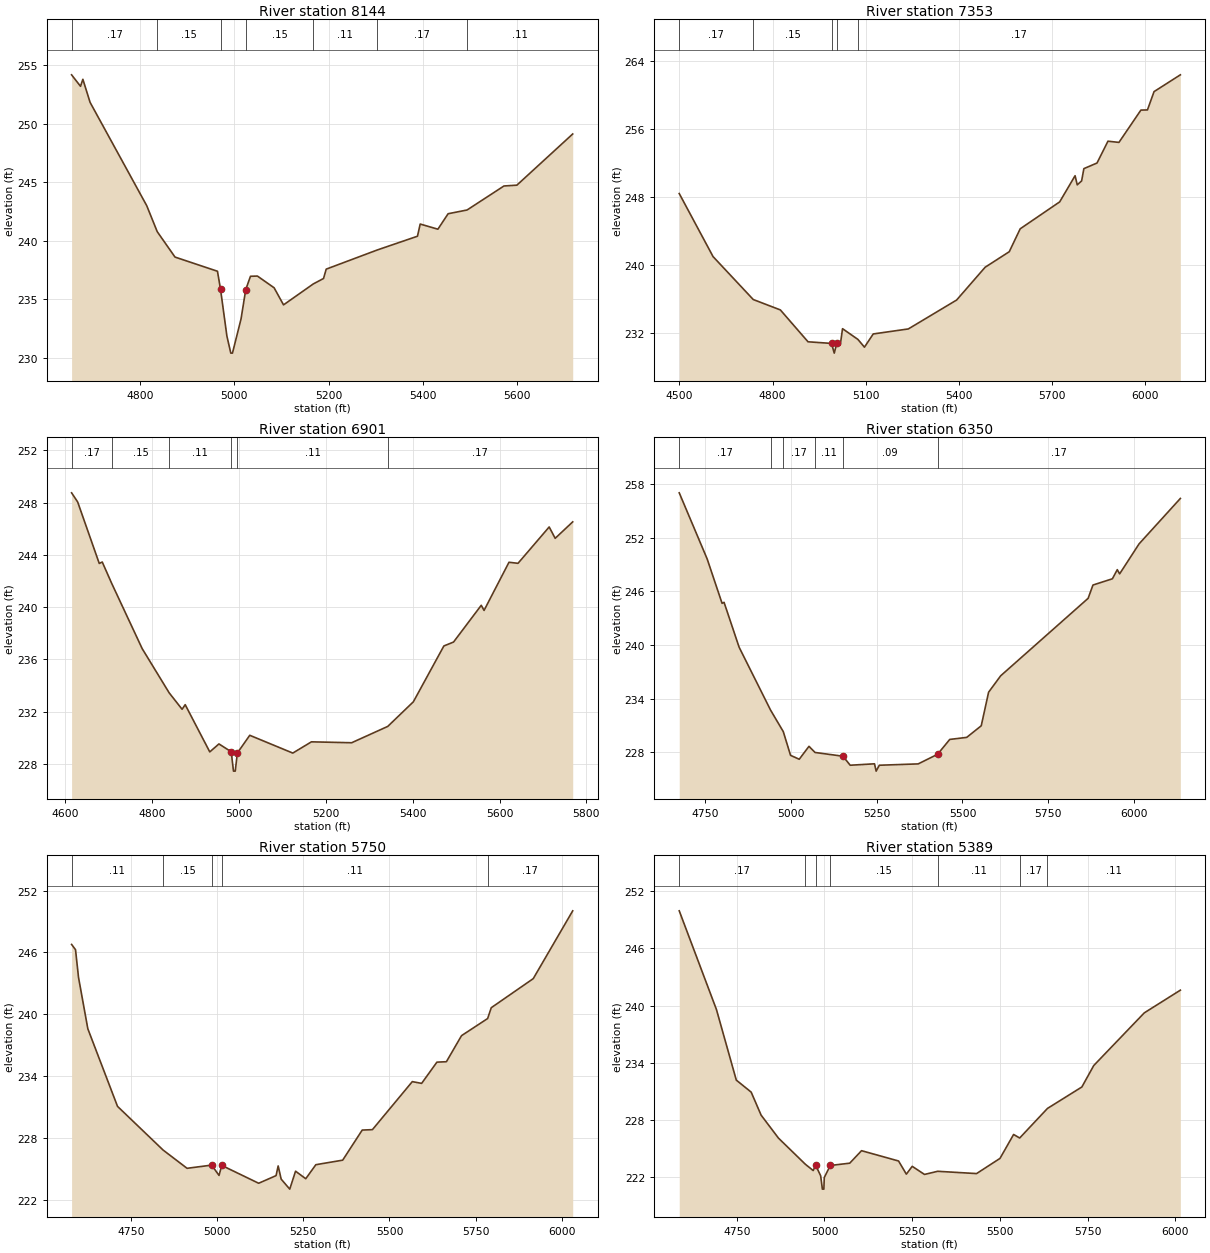
Type RM Length L Ch R = 1 ,8144    ,791,791,791
BEGIN DESCRIPTION:
CCLC 010 11.0
END DESCRIPTION:
XS GIS Cut Line= 3
      3754172.22     10117311.87       3754186.1     10117825.75
      3754663.63     10118095.66
#Sta/Elev= 30
  4654.9  254.17  4673.8  253.19  4678.8  253.79  4694.1  251.82  4814.2     243
  4836.5  240.78  4874.2  238.61  4964.2   237.4  4970.7 235.866  4984.2  231.87
  4992.5  230.41    4996  230.41  5014.2  233.33  5024.2  235.84  5034.2  236.97
  5048.9  236.99  5084.3  235.99  5104.3  234.53  5167.5  236.32  5189.1  236.78
  5194.8  237.58  5302.6  239.21  5388.3  240.39  5394.1  241.43  5431.6  240.99
  5453.3  242.31  5493.5  242.63  5571.7  244.68  5599.1  244.75  5717.5  249.12
#Mann= 7 ,-1 , 0
  4654.9     .17       0  4836.5     .15       0  4970.7     .09       0
  5024.2     .15       0  5167.5     .11       0  5302.6     .17       0
  5493.5     .11       0
Bank Sta=4970.7,5024.2
XS Rating Curve= 0 ,0
Exp/Cntr=0.3,0.1

Type RM Length L Ch R = 1 ,7353    ,452,452,452
BEGIN DESCRIPTION:
CCLC 010 10.0
END DESCRIPTION:
XS GIS Cut Line= 3
      3754033.31     10117291.03      3753540.27      10117419.5
      3752767.85     10118211.08
#Sta/Elev= 30
  4499.2  248.41  4608.2  241.01  4737.8  235.97  4825.2  234.75  4914.4  231.01
  4990.2  230.82  4998.9  229.68  5007.4  230.86  5018.6   230.7  5025.6  232.55
  5075.2  231.29  5096.3  230.38  5124.6  231.93  5237.8  232.52  5393.4  235.91
  5485.4  239.76  5563.1  241.58  5598.4  244.27  5725.7  247.43  5775.3   250.5
  5782.3  249.43  5796.4  249.89  5803.6  251.33    5846  251.99  5881.3  254.55
  5916.7  254.41  5987.5   258.2  6008.6  258.22  6029.9  260.37  6114.7  262.34
#Mann= 5 ,-1 , 0
  4499.2     .17       0  4737.8     .15       0  4990.2     .09       0
  5007.4     .15       0  5075.2     .17       0
Bank Sta=4990.2,5007.4
XS Rating Curve= 0 ,0
Exp/Cntr=0.3,0.1

Type RM Length L Ch R = 1 ,6901    ,551,551,551
BEGIN DESCRIPTION:
CCLC 010 9.0
END DESCRIPTION:
XS GIS Cut Line= 3
      3753567.85     10116811.07      3753300.69     10117086.17
      3752812.01     10117682.29
#Sta/Elev= 30
  4614.3  248.74  4628.3  248.04    4678  243.34  4684.9  243.45  4706.9   241.8
    4777  236.82    4839  233.45  4868.8  232.19    4876  232.54  4932.6  228.93
  4953.7  229.54    4982  228.94  4987.2  227.46  4991.2  227.46  4996.2  228.85
  5024.7   230.2  5123.8  228.84  5166.8   229.7  5259.4  229.63  5342.6  230.88
  5401.5  232.76  5471.8  237.03  5494.1  237.33  5557.9  240.14  5564.4  239.75
  5621.8  243.43  5642.6  243.35  5714.4  246.13  5728.2  245.26  5768.6  246.52
#Mann= 6 ,-1 , 0
  4614.3     .17       0  4706.9     .15       0    4839     .11       0
    4982     .06       0  4996.2     .11       0  5342.6     .17       0
Bank Sta=4982,4996.2
XS Rating Curve= 0 ,0
Exp/Cntr=0.3,0.1

Type RM Length L Ch R = 1 ,6350    ,600,600,600
BEGIN DESCRIPTION:
CCLC 010 8.0
END DESCRIPTION:
XS GIS Cut Line= 3
      3753367.88     10116511.06      3753088.23     10116676.84
      3752267.86     10117461.06
#Sta/Elev= 30
  4674.9  257.05  4756.3  249.64  4799.7  244.67  4805.5  244.78  4849.3  239.76
  4941.1   232.7    4978   230.3  4999.2  227.64  5024.5   227.2  5052.9  228.65
  5070.6  227.96  5151.9  227.54    5173  226.53  5243.8  226.69  5248.6  225.87
  5257.9  226.53  5371.1  226.68  5427.7  227.76    5463  229.42  5512.4  229.65
  5554.8  230.95  5576.2  234.71  5611.4  236.55  5866.2  245.23  5880.3  246.72
  5936.9  247.42  5951.1  248.44    5958  247.97  6014.6  251.33  6134.9  256.42
#Mann= 6 ,-1 , 0
  4674.9     .17       0  4941.1     .15       0    4978     .17       0
  5070.6     .11       0  5151.9     .09       0  5427.7     .17       0
Bank Sta=5151.9,5427.7
XS Rating Curve= 0 ,0
Exp/Cntr=0.3,0.1

Type RM Length L Ch R = 1 ,5750    ,361,361,361
BEGIN DESCRIPTION:
CCLC 010 7.0
END DESCRIPTION:
XS GIS Cut Line= 3
      3753106.21     10116072.31      3752762.49     10116315.34
      3752167.86     10117161.06
#Sta/Elev= 30
  4577.2  246.78  4588.6  246.27  4597.3  243.58  4624.3   238.6  4710.5  231.07
  4842.9  226.83  4912.4  225.06  4983.8  225.37  5005.2  224.37  5013.1  225.34
  5120.3  223.61  5170.8  224.35  5176.9  225.29  5185.6  224.01  5210.5  223.04
  5227.4  224.78    5257  224.05  5286.3  225.41  5364.2  225.85  5420.9  228.77
  5450.5  228.81  5566.3  233.47  5593.4   233.3  5637.8  235.36  5665.3   235.4
  5709.2  237.93    5785  239.59  5795.5  240.64  5917.4  243.46    6032  250.04
#Mann= 5 ,-1 , 0
  4577.2     .11       0  4842.9     .15       0  4983.8     .07       0
  5013.1     .11       0    5785     .17       0
Bank Sta=4983.8,5013.1
XS Rating Curve= 0 ,0
Exp/Cntr=0.3,0.1

Type RM Length L Ch R = 1 ,5389    ,464,464,464
BEGIN DESCRIPTION:
CCLC 010 6.0
END DESCRIPTION:
XS GIS Cut Line= 3
      3752867.88     10115761.04      3752578.23     10116056.84
      3752117.84     10116961.09
#Sta/Elev= 30
    4586  249.93  4692.1  239.58  4748.7  232.18  4791.1  230.92  4819.4  228.51
  4868.9   226.1  4945.5  223.36  4967.9   222.7    4975  223.25  4989.2  222.15
  4994.1  220.75  4998.3  220.75  4999.5  221.97  5016.7  223.23  5072.1  223.47
  5105.7  224.78  5211.3   223.7  5233.5  222.32  5250.2  223.14  5285.3  222.29
  5322.9  222.62  5433.7  222.38  5500.4  223.97  5539.3  226.48  5556.6  226.11
  5635.8  229.21  5733.9  231.46  5767.8  233.71  5911.8  239.23  6014.7  241.61
#Mann= 7 ,-1 , 0
    4586     .17       0  4945.5     .15       0    4975     .09       0
  5016.7     .15       0  5322.9     .11       0  5556.6     .17       0
  5635.8     .11       0
Bank Sta=4975,5016.7
XS Rating Curve= 0 ,0
Exp/Cntr=0.3,0.1

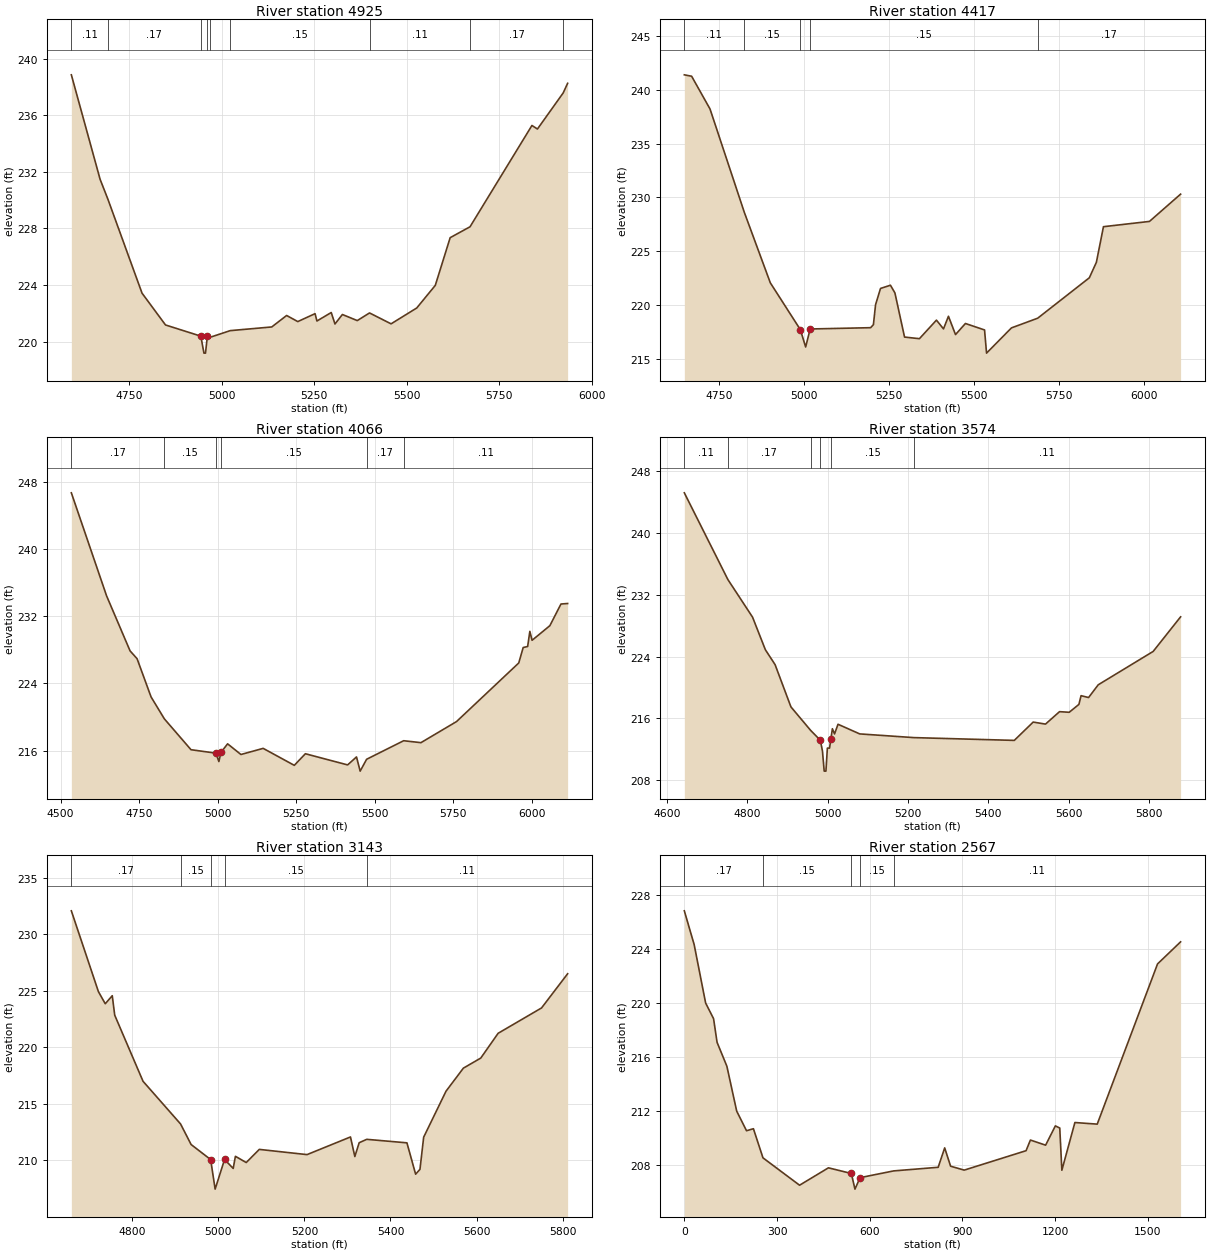
Type RM Length L Ch R = 1 ,4925    ,508,508,508
BEGIN DESCRIPTION:
CCLC 010 5.0
END DESCRIPTION:
XS GIS Cut Line= 3
      3752467.83     10115611.09      3752188.23     10115906.84
      3752094.66     10116837.05
#Sta/Elev= 30
    4593  238.85  4670.8  231.46  4691.4  230.09  4784.1  223.42  4847.6  221.17
  4943.1  220.38  4951.5  219.18  4955.7  219.18  4960.9  220.41  4967.1  220.29
  5022.6  220.77  5134.9  221.03  5175.1  221.84  5205.3  221.41    5252  221.97
    5257  221.45  5295.7  222.05  5305.8  221.24  5325.9  221.91  5366.1  221.48
  5399.3  222.02  5457.5  221.25  5526.9  222.37  5577.1  223.97  5617.3  227.34
    5671  228.11  5838.4  235.27  5853.3  235.02  5922.9  237.57  5934.9  238.25
#Mann= 9 ,-1 , 0
    4593     .11       0  4691.4     .17       0  4943.1     .09       0
  4960.9     .17       0  4967.1     .17       0  5022.6     .15       0
  5399.3     .11       0    5671     .17       0  5922.9     .11       0
Bank Sta=4943.1,4960.9
XS Rating Curve= 0 ,0
Exp/Cntr=0.3,0.1

Type RM Length L Ch R = 1 ,4417    ,351,351,351
BEGIN DESCRIPTION:
CCLC 010 4.0
END DESCRIPTION:
XS GIS Cut Line= 3
      3751981.24     10115363.96      3751818.23     10115676.84
      3751154.87     10116565.32
#Sta/Elev= 30
  4647.2  241.38  4668.7  241.25  4722.9  238.21  4823.9  228.62  4900.5  222.08
  4988.9  217.74  5004.5  216.13  5017.8   217.8  5195.8  217.92  5204.1   218.2
  5210.4  220.05    5225  221.56  5254.2  221.86  5267.4  221.15  5295.8  217.05
  5339.6   216.9  5389.7  218.62  5410.5  217.81  5425.1  218.98  5445.9  217.28
  5475.1  218.31  5531.4  217.71  5537.3  215.56  5610.6   217.9  5687.9   218.8
    5840  222.55  5860.8  223.99  5881.6  227.29  6017.1  227.78  6108.8  230.31
#Mann= 5 ,-1 , 0
  4647.2     .11       0  4823.9     .15       0  4988.9     .09       0
  5017.8     .15       0  5687.9     .17       0
Bank Sta=4988.9,5017.8
XS Rating Curve= 0 ,0
Exp/Cntr=0.3,0.1

Type RM Length L Ch R = 1 ,4066    ,492,492,492
BEGIN DESCRIPTION:
CCLC 010 3.0
END DESCRIPTION:
XS GIS Cut Line= 3
      3751717.84      10115261.1      3751508.23     10115676.84
      3750717.87     10116461.06
#Sta/Elev= 30
  4534.4  246.69  4646.4  234.43  4721.2  227.87  4743.5  226.94  4788.1  222.38
  4830.4  219.77  4915.1   216.1  4994.4  215.69  5003.8  214.69  5010.3  215.77
  5031.5   216.8    5074  215.53  5144.7  216.26  5243.7  214.24    5279  215.62
  5413.4  214.29  5441.7  215.24  5453.3  213.55  5473.8  214.96  5591.7  217.17
  5646.7  216.94  5759.9  219.45  5957.9  226.43    5972  228.27  5986.2  228.39
  5993.2  230.19  6000.3  229.13  6056.9  230.87  6092.2  233.45  6113.4  233.51
#Mann= 6 ,-1 , 0
  4534.4     .17       0  4830.4     .15       0  4994.4     .09       0
  5010.3     .15       0  5473.8     .17       0  5591.7     .11       0
Bank Sta=4994.4,5010.3
XS Rating Curve= 0 ,0
Exp/Cntr=0.3,0.1

Type RM Length L Ch R = 1 ,3574    ,431,431,431
BEGIN DESCRIPTION:
CCLC 010 2.0
END DESCRIPTION:
XS GIS Cut Line= 3
      3751217.84     10115211.11      3751098.23     10115546.84
      3750767.85     10116361.07
#Sta/Elev= 30
  4643.6  245.22    4752  233.99  4813.4  229.12  4845.3   224.9  4869.4  222.98
  4908.9   217.5  4957.9  214.46  4982.1  213.18  4987.4  211.78  4991.7  209.18
    4996  209.18  4999.6  212.16    5005  212.16 5008.36213.3478  5012.1  214.67
  5017.5     214  5026.1  215.25  5080.1     214    5215  213.52  5464.8  213.16
  5511.8  215.53  5542.5  215.27  5577.4  216.88  5601.5   216.8  5625.6  217.82
    5631  218.95  5649.7  218.71  5673.7  220.36  5810.4  224.68  5878.7  229.16
#Mann= 6 ,-1 , 0
  4643.6     .11       0    4752     .17       0  4957.9     .15       0
  4982.1     .09       0 5008.36     .15       0    5215     .11       0
Bank Sta=4982.1,5008.36
XS Rating Curve= 0 ,0
Exp/Cntr=0.3,0.1

Type RM Length L Ch R = 1 ,3143    ,576,576,576
BEGIN DESCRIPTION:
CCLC 010 1.0
END DESCRIPTION:
XS GIS Cut Line= 3
      3750939.57     10115155.63      3750778.23     10115456.84
      3750667.85     10116261.11
#Sta/Elev= 30
  4658.3  232.06  4721.2  224.92  4737.1  223.85  4753.4  224.56  4759.1  222.84
  4824.9     217  4912.1  213.23  4936.7  211.41  4982.1  210.08  4992.5  207.47
  5014.4  210.09  5034.5   209.3  5039.6  210.37  5064.8  209.82  5095.1  210.98
  5206.1  210.52  5307.1  212.08  5317.2  210.35  5327.3  211.57  5344.9  211.87
  5438.3  211.56  5458.5  208.79  5468.6  209.22  5477.2  212.06  5529.1  216.12
  5569.5  218.16  5609.9  219.05  5650.3  221.24  5751.2  223.48  5811.8   226.5
#Mann= 5 ,-1 , 0
  4658.3     .17       0  4912.1     .15       0  4982.1     .09       0
  5014.4     .15       0  5344.9     .11       0
Bank Sta=4982.1,5014.4
XS Rating Curve= 0 ,0
Exp/Cntr=0.3,0.1

Type RM Length L Ch R = 1 ,2567    ,0,0,0
BEGIN DESCRIPTION:
CCLC 010 0.5
END DESCRIPTION:
XS GIS Cut Line= 3
      3750817.79     10115023.07      3750294.79     10115207.53
      3750626.82     10116205.79
#Sta/Elev= 30
       0  226.86    31.8  224.36      69  220.02    94.7  218.86     106  217.11
   137.8  215.33   169.6     212   201.4  210.55   223.7   210.7   254.6  208.54
   373.1  206.51   466.5   207.8   540.7  207.38   552.4  206.22   568.9  207.07
   677.3  207.57   821.8  207.84   842.9  209.28     862  207.92   906.1  207.63
  1106.3  209.07  1120.4  209.86  1169.6  209.48  1201.2  210.91  1215.4  210.75
  1222.2  207.62  1264.4  211.16  1336.7  211.04  1531.9  222.92  1606.6  224.56
#Mann= 5 ,-1 , 0
       0     .17       0   254.6     .15       0   540.7     .09       0
   568.9     .15       0   677.3     .11       0
Bank Sta=540.7,568.9
XS Rating Curve= 0 ,0
Exp/Cntr=0.3,0.1

Chan Stop Cuts=-1
Use User Specified Reach Order=0
Composite Channel Slope=5