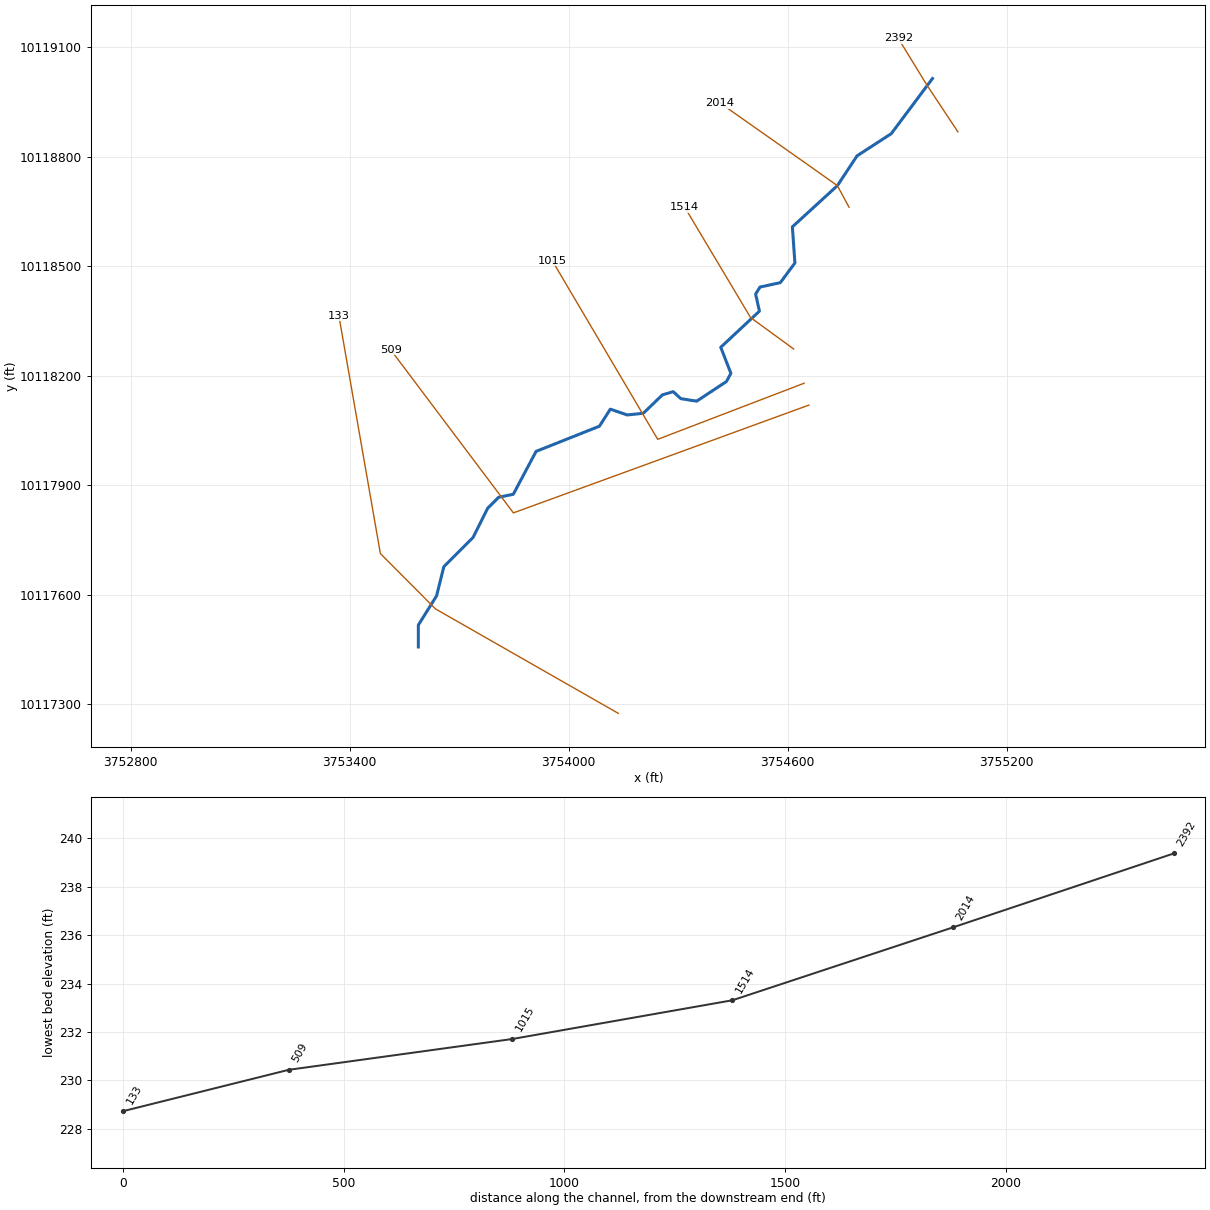
--- CCLC 011.prj (project) ---

Proj Title=CCLC 011 Base Level Engineering
Current Plan=p01
Default Exp/Contr=0.3,0.1
English Units
Geom File=g01
Flow File=f01
Flow File=f02
Plan File=p01
Y Axis Title=Elevation
X Axis Title(PF)=Main Channel Distance
X Axis Title(XS)=Station
BEGIN DESCRIPTION:
CCLC 011
END DESCRIPTION:
DSS Export Rating Curves= 0
DSS Export Rating Curve Sorted= 0
DSS Export Volume Flow Curves= 0
DXF OffsetX= 0
DXF OffsetY= 0
DXF ScaleX= 1
DXF ScaleY= 10

--- CCLC 011.p01 (plan) ---

Plan Title=Multiple Run
Short Identifier=Multiple
Geom File=g01
Flow File=f01
Subcritical Flow
K Sum by GR= 0
Std Step Tol= 0.01
Critical Tol= 0.01
Num of Std Step Trials= 20
Max Error Tol= 0.3
Flow Tol Ratio= 0.001
Split Flow NTrial= 30
Split Flow Tol= 0.02
Split Flow Ratio= 0.02
Log Output Level= 0
Friction Slope Method= 1
Unsteady Friction Slope Method= 2
Unsteady Bridges Friction Slope Method= 1
Parabolic Critical Depth
Global Vel Dist=  1 , 1 , 1
Global Log Level= 0
CheckData=True
Encroach Param= -1, 0, 0, 0
BEGIN DESCRIPTION:
Multiple Run
END DESCRIPTION:

--- CCLC 011.f01 (steady flow) ---

Flow Title=Multiple
Program Version=4.10
Number of Profiles= 7
Profile Names=10-year,25-year,50-year,1pct_min,100-year,1pct_plu,500-year
River Rch & RM=CCLC 011,Reach-1         ,2392
     606     826    1122     502    1517    4581    2862
River Rch & RM=CCLC 011,Reach-1         ,2014
     606     826    1122     502    1517    4581    2862
River Rch & RM=CCLC 011,Reach-1         ,133
    1251    1766    2454    1120    3383   10216    6650
Boundary for River Rch & Prof#=CCLC 011,Reach-1         , 1
Up Type= 0
Dn Type= 3
Dn Slope=0.005
Boundary for River Rch & Prof#=CCLC 011,Reach-1         , 2
Up Type= 0
Dn Type= 3
Dn Slope=0.005
Boundary for River Rch & Prof#=CCLC 011,Reach-1         , 3
Up Type= 0
Dn Type= 3
Dn Slope=0.005
Boundary for River Rch & Prof#=CCLC 011,Reach-1         , 4
Up Type= 0
Dn Type= 3
Dn Slope=0.005
Boundary for River Rch & Prof#=CCLC 011,Reach-1         , 5
Up Type= 0
Dn Type= 3
Dn Slope=0.005
Boundary for River Rch & Prof#=CCLC 011,Reach-1         , 6
Up Type= 0
Dn Type= 3
Dn Slope=0.005
Boundary for River Rch & Prof#=CCLC 011,Reach-1         , 7
Up Type= 0
Dn Type= 3
Dn Slope=0.005
DSS Import GetInterval= 0
DSS Import GetPeak= 0
DSS Import FillOption= 0

--- CCLC 011.f02 (steady flow) ---

Flow Title=Orig_BLE_Flows
Program Version=4.10
Number of Profiles= 7
Profile Names=10-year,25-year,50-year,1pct_min,100-year,1pct_plu,500-year
River Rch & RM=CCLC 011,Reach-1         ,2392
     606     810     976     386    1167    3523    1664
River Rch & RM=CCLC 011,Reach-1         ,2014
     606     810     976     386    1167    3523    1664
River Rch & RM=CCLC 011,Reach-1         ,133
    1251    1731    2134     861    2602    7857    3866
Boundary for River Rch & Prof#=CCLC 011,Reach-1         , 1
Up Type= 0
Dn Type= 3
Dn Slope=0.005
Boundary for River Rch & Prof#=CCLC 011,Reach-1         , 2
Up Type= 0
Dn Type= 3
Dn Slope=0.005
Boundary for River Rch & Prof#=CCLC 011,Reach-1         , 3
Up Type= 0
Dn Type= 3
Dn Slope=0.005
Boundary for River Rch & Prof#=CCLC 011,Reach-1         , 4
Up Type= 0
Dn Type= 3
Dn Slope=0.005
Boundary for River Rch & Prof#=CCLC 011,Reach-1         , 5
Up Type= 0
Dn Type= 3
Dn Slope=0.005
Boundary for River Rch & Prof#=CCLC 011,Reach-1         , 6
Up Type= 0
Dn Type= 3
Dn Slope=0.005
Boundary for River Rch & Prof#=CCLC 011,Reach-1         , 7
Up Type= 0
Dn Type= 3
Dn Slope=0.005
DSS Import GetInterval= 0
DSS Import GetPeak= 0
DSS Import FillOption= 0

--- CCLC 011.g01 (geometry) ---

Geom Title=Existing Conditions
Program Version=4.10

River Reach=CCLC 011        ,Reach-1
Reach XY= 30
      3754996.35     10119013.62       3754883.5     10118862.58
      3754789.75     10118801.81      3754735.93     10118720.21
      3754612.67     10118607.37      3754619.61     10118508.41
      3754579.68     10118454.59      3754524.13     10118442.44
      3754511.97     10118423.34      3754522.39     10118376.46
      3754416.49     10118277.51      3754444.26     10118206.33
      3754432.11     10118183.76      3754350.51     10118129.94
      3754307.11     10118136.88      3754286.28     10118155.98
      3754256.71     10118147.19      3754204.48     10118096.83
      3754160.65     10118092.17      3754114.03     10118108.02
      3754084.18     10118061.39      3753910.73     10117992.38
      3753848.25     10117874.88      3753808.23     10117866.84
      3753778.23     10117836.84      3753738.23     10117756.84
      3753658.23     10117676.84      3753638.23     10117596.84
      3753588.23     10117516.84      3753588.23     10117456.84

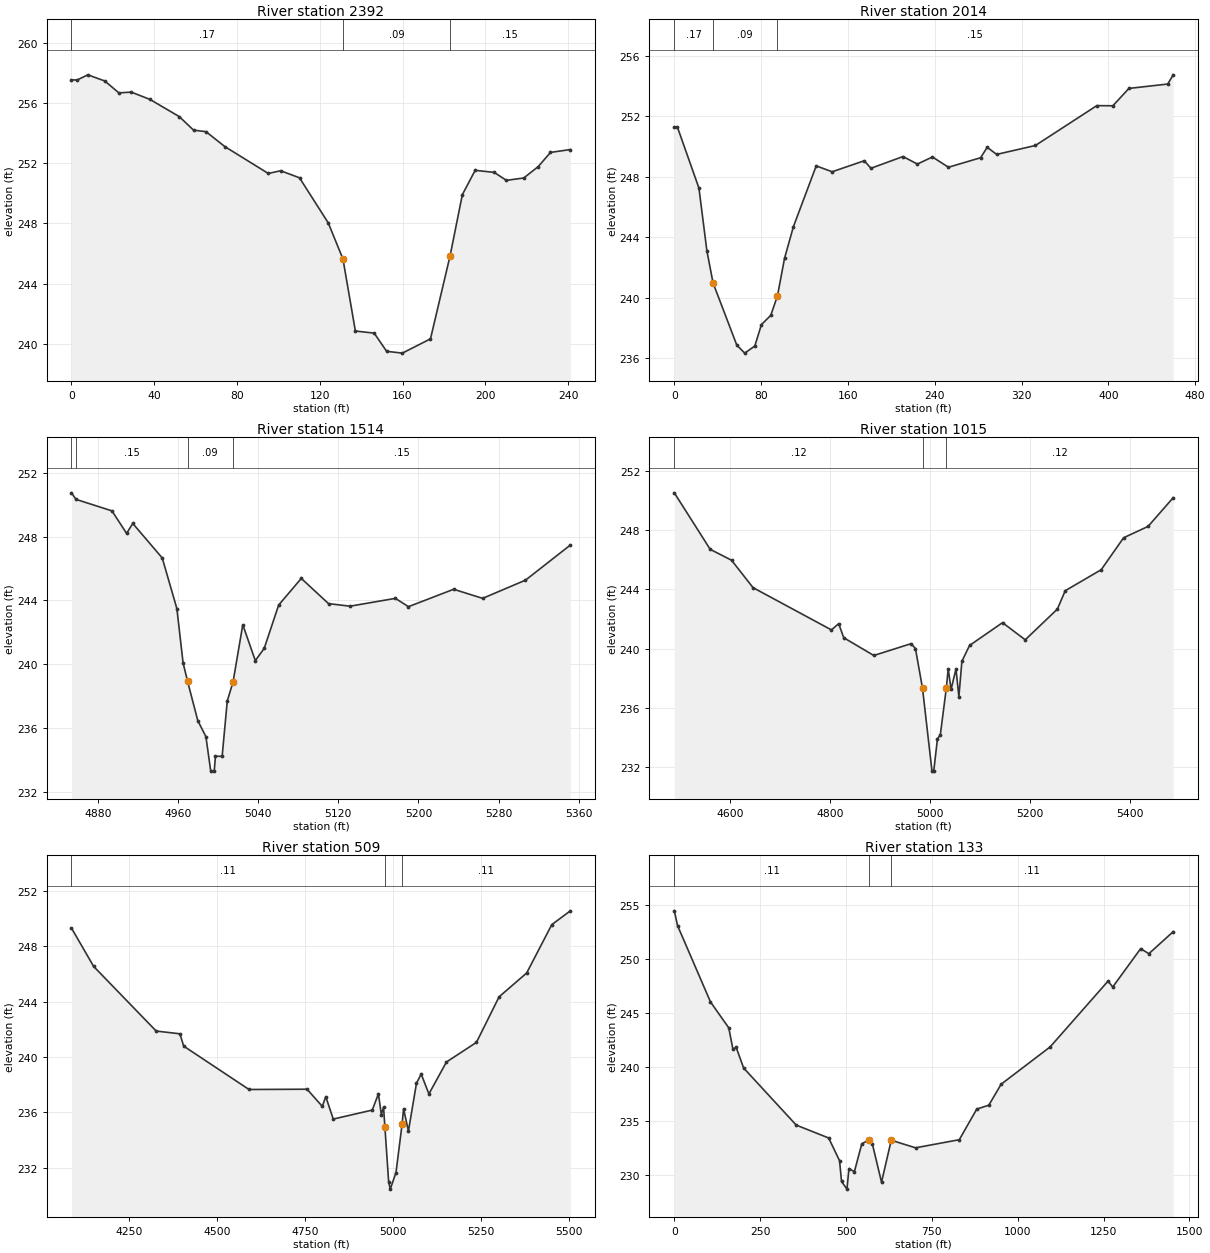
Type RM Length L Ch R = 1 ,2392    ,500,500,500
BEGIN DESCRIPTION:
CCLC 011 3.0
END DESCRIPTION:
XS GIS Cut Line= 3
      3755065.93     10118867.61      3754980.86     10118996.08
      3754902.73     10119123.69
#Sta/Elev= 30
       0  257.54     2.8  257.54     7.9  257.88    16.1  257.47    22.9  256.68
    28.9  256.73      38  256.24    52.1   255.1      59   254.2      65   254.1
    74.1  253.11    95.1  251.32   101.1   251.5   110.2  251.03   124.1  248.03
   131.2  245.63   137.2  240.84   146.3   240.7   152.3  239.49   159.9  239.37
   173.5  240.32     183  245.86   188.9  249.91   195.1  251.53   204.3  251.39
   210.2  250.86   218.6  251.02   225.6  251.78   231.5  252.72   241.1  252.91
#Mann= 3 , 0 , 0
       0     .17       0   131.2     .09       0     183     .15       0
Bank Sta=131.2,183
XS Rating Curve= 0 ,0
Exp/Cntr=0.3,0.1

Type RM Length L Ch R = 1 ,2014    ,500,500,500
BEGIN DESCRIPTION:
CCLC 011 3.0
END DESCRIPTION:
XS GIS Cut Line= 4
      3754767.85     10118661.07      3754735.93     10118720.21
      3754657.91     10118775.46      3754414.65     10118946.58
#Sta/Elev= 30
       0   251.3     2.8   251.3    22.7  247.25      30  243.11    35.7  240.97
    57.6  236.85    64.9  236.32    74.2  236.79    80.3  238.21    88.9  238.82
    95.1  240.12   101.6   242.6   109.8   244.7   130.8  248.72   145.5  248.33
   175.1  249.06   181.2  248.56   210.8  249.34     224  248.84   237.9  249.31
   252.7  248.63   282.3  249.26   288.4  249.95   297.1  249.48   332.8  250.07
   389.4  252.71   404.2   252.7     419  253.85   454.8  254.14   459.8  254.75
#Mann= 3 ,-1 , 0
       0     .17       0    35.7     .09       0    95.1     .15       0
Bank Sta=35.7,95.1
XS Rating Curve= 0 ,0
Exp/Cntr=0.3,0.1

Type RM Length L Ch R = 1 ,1514    ,499,499,499
BEGIN DESCRIPTION:
CCLC 011 2.0
END DESCRIPTION:
XS GIS Cut Line= 3
      3754616.25     10118272.85      3754498.08      10118359.1
      3754317.83      10118661.1
#Sta/Elev= 30
  4853.7  250.74  4858.2  250.33  4894.1  249.61  4908.7   248.2  4914.9  248.82
  4944.3  246.66  4958.9  243.49  4965.1  240.09 4969.56238.9357  4979.8  236.47
  4987.9  235.47  4992.7  233.31  4996.2  233.31  4997.4  234.24  5004.1  234.24
  5009.2   237.7    5015   238.9  5024.7  242.48  5037.2  240.23  5046.1     241
  5060.5  243.71  5083.1  245.38  5110.3   243.8  5131.7  243.64    5177  244.13
  5190.1  243.61  5235.2   244.7  5264.1  244.13  5306.9  245.27  5351.7  247.47
#Mann= 4 ,-1 , 0
  4853.7     .17       0  4858.2     .15       0 4969.56     .09       0
    5015     .15       0
Bank Sta=4969.56,5015
XS Rating Curve= 0 ,0
Exp/Cntr=0.3,0.1

Type RM Length L Ch R = 1 ,1015    ,506,506,506
BEGIN DESCRIPTION:
Mapping XS d2100bbf
END DESCRIPTION:
XS GIS Cut Line= 3
      3754644.87     10118179.09      3754243.85     10118025.46
      3753954.78     10118515.05
#Sta/Elev= 30
    4488  250.53  4559.8  246.71  4602.6  245.97  4645.4  244.12  4802.3  241.26
  4816.8  241.68    4827  240.73  4887.1  239.53  4961.7  240.33  4970.4     240
 4984.51237.3184  5003.5  231.71    5007  231.71  5014.4  233.89  5020.2  234.17
 5032.31237.3638  5035.9  238.63  5041.7  237.24  5051.5  238.62  5057.3  236.74
  5063.3  239.14  5078.7  240.21  5144.6  241.75    5190  240.59  5254.4  242.67
    5270  243.91    5342  245.33  5386.8  247.49  5435.8  248.26    5486   250.2
#Mann= 3 , 0 , 0
    4488     .12       0 4984.51     .07       0 5032.31     .12       0
Bank Sta=4984.51,5032.31
XS Rating Curve= 0 ,0
Exp/Cntr=0.3,0.1

Type RM Length L Ch R = 1 ,509     ,376,376,376
BEGIN DESCRIPTION:
CCLC 011 1.0
END DESCRIPTION:
XS GIS Cut Line= 3
      3754657.89      10118119.2      3753848.58     10117823.99
      3753512.72      10118270.5
#Sta/Elev= 30
  4084.9  249.33  4147.9  246.56    4326  241.88  4393.6  241.68  4404.3  240.79
  4590.3  237.65  4755.5  237.67  4798.9  236.43  4808.8  237.13  4830.1  235.51
  4941.1  236.16  4958.7  237.33    4967  235.84  4973.3  236.36 4977.04234.9708
  4987.8  230.97  4992.4  230.44  5008.7  231.64 5026.04235.1303  5030.3  236.25
  5044.1  234.64    5067   238.1  5080.4  238.77  5102.4  237.33  5152.4  239.64
  5237.7  241.06  5302.3  244.36  5380.7  246.08  5452.2  249.58  5505.1  250.58
#Mann= 3 , 0 , 0
  4084.9     .11       0 4977.04     .06       0 5026.04     .11       0
Bank Sta=4977.04,5026.04
XS Rating Curve= 0 ,0
Exp/Cntr=0.3,0.1

Type RM Length L Ch R = 1 ,133     ,0,0,0
XS GIS Cut Line= 4
      3754136.09     10117274.87      3753635.36     10117560.88
      3753484.28     10117712.63       3753370.5     10118364.44
#Sta/Elev= 30
       0  254.46     9.5  253.09   105.3  246.04   158.6  243.64   170.7  241.66
   180.2  241.83   201.8  239.93     355  234.65   449.4  233.46   481.1  231.36
   486.9  229.44   502.7  228.73   508.5  230.63   524.3  230.34   545.9  232.92
   567.5  233.29   576.6  232.92   603.3  229.37   631.6  233.25   702.3  232.55
   829.8   233.3   880.6  236.13   915.7  236.49   951.6  238.43  1094.3  241.88
  1262.8  247.96  1276.5  247.42  1357.7  250.96  1381.8   250.5  1452.5  252.53
#Mann= 3 , 0 , 0
       0     .11       0   567.5     .06       0   631.6     .11       0
Bank Sta=567.5,631.6
XS Rating Curve= 0 ,0
Exp/Cntr=0.3,0.1

Chan Stop Cuts=-1
Use User Specified Reach Order=0
Composite Channel Slope=5