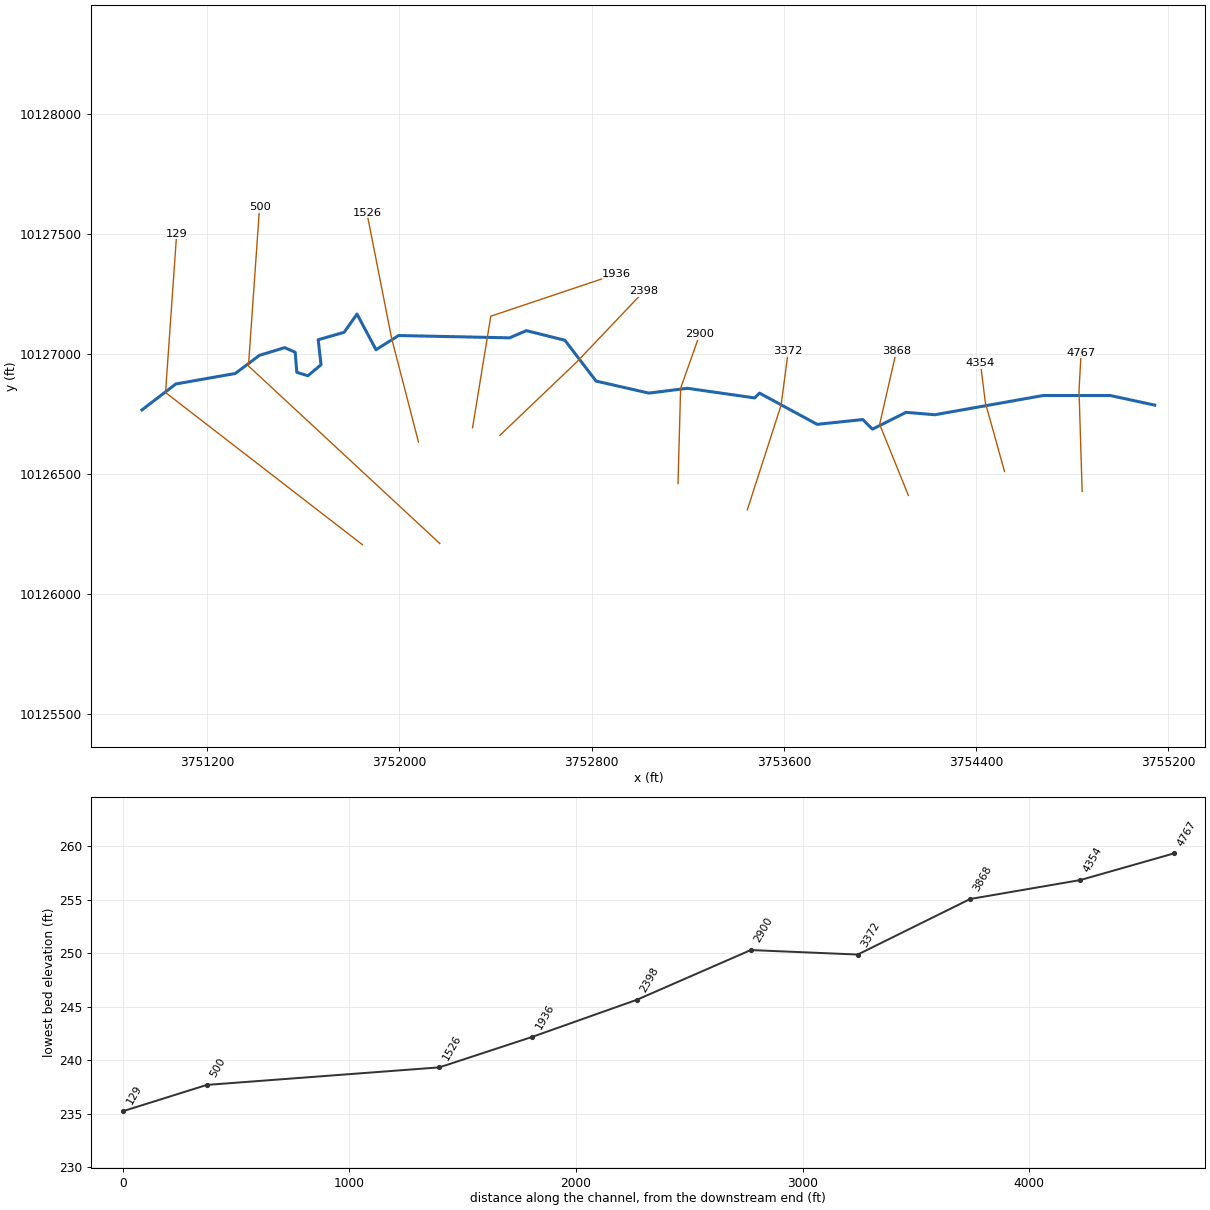
--- CCLC 012.prj (project) ---

Proj Title=CCLC 012 Base Level Engineering
Current Plan=p01
Default Exp/Contr=0.3,0.1
English Units
Geom File=g01
Flow File=f01
Flow File=f02
Plan File=p01
Y Axis Title=Elevation
X Axis Title(PF)=Main Channel Distance
X Axis Title(XS)=Station
BEGIN DESCRIPTION:
CCLC 012
END DESCRIPTION:
DSS Export Rating Curves= 0
DSS Export Rating Curve Sorted= 0
DSS Export Volume Flow Curves= 0
DXF OffsetX= 0
DXF OffsetY= 0
DXF ScaleX= 1
DXF ScaleY= 10

--- CCLC 012.p01 (plan) ---

Plan Title=Multiple Run
Short Identifier=Multiple
Geom File=g01
Flow File=f01
Subcritical Flow
K Sum by GR= 0
Std Step Tol= 0.01
Critical Tol= 0.01
Num of Std Step Trials= 20
Max Error Tol= 0.3
Flow Tol Ratio= 0.001
Split Flow NTrial= 30
Split Flow Tol= 0.02
Split Flow Ratio= 0.02
Log Output Level= 0
Friction Slope Method= 1
Unsteady Friction Slope Method= 2
Unsteady Bridges Friction Slope Method= 1
Parabolic Critical Depth
Global Vel Dist=  1 , 1 , 1
Global Log Level= 0
CheckData=True
Encroach Param= -1, 0, 0, 0
BEGIN DESCRIPTION:
Multiple Run
END DESCRIPTION:

--- CCLC 012.f01 (steady flow) ---

Flow Title=Multiple
Program Version=4.10
Number of Profiles= 7
Profile Names=10-year,25-year,50-year,1pct_min,100-year,1pct_plu,500-year
River Rch & RM=CCLC 012,Reach-1         ,4767
     651     887    1204     538    1624    4904    3056
River Rch & RM=CCLC 012,Reach-1         ,1526
    1195    1691    2354    1077    3253    9824    6426
Boundary for River Rch & Prof#=CCLC 012,Reach-1         , 1
Up Type= 0
Dn Type= 3
Dn Slope=0.005
Boundary for River Rch & Prof#=CCLC 012,Reach-1         , 2
Up Type= 0
Dn Type= 3
Dn Slope=0.005
Boundary for River Rch & Prof#=CCLC 012,Reach-1         , 3
Up Type= 0
Dn Type= 3
Dn Slope=0.005
Boundary for River Rch & Prof#=CCLC 012,Reach-1         , 4
Up Type= 0
Dn Type= 3
Dn Slope=0.005
Boundary for River Rch & Prof#=CCLC 012,Reach-1         , 5
Up Type= 0
Dn Type= 3
Dn Slope=0.005
Boundary for River Rch & Prof#=CCLC 012,Reach-1         , 6
Up Type= 0
Dn Type= 3
Dn Slope=0.005
Boundary for River Rch & Prof#=CCLC 012,Reach-1         , 7
Up Type= 0
Dn Type= 3
Dn Slope=0.005
DSS Import GetInterval= 0
DSS Import GetPeak= 0
DSS Import FillOption= 0

--- CCLC 012.f02 (steady flow) ---

Flow Title=Orig_BLE_Flows
Program Version=4.10
Number of Profiles= 7
Profile Names=10-year,25-year,50-year,1pct_min,100-year,1pct_plu,500-year
River Rch & RM=CCLC 012,Reach-1         ,4767
     651     870    1047     414    1249    3773    1777
River Rch & RM=CCLC 012,Reach-1         ,1526
    1195    1658    2047     829    2502    7556    3736
Boundary for River Rch & Prof#=CCLC 012,Reach-1         , 1
Up Type= 0
Dn Type= 3
Dn Slope=0.005
Boundary for River Rch & Prof#=CCLC 012,Reach-1         , 2
Up Type= 0
Dn Type= 3
Dn Slope=0.005
Boundary for River Rch & Prof#=CCLC 012,Reach-1         , 3
Up Type= 0
Dn Type= 3
Dn Slope=0.005
Boundary for River Rch & Prof#=CCLC 012,Reach-1         , 4
Up Type= 0
Dn Type= 3
Dn Slope=0.005
Boundary for River Rch & Prof#=CCLC 012,Reach-1         , 5
Up Type= 0
Dn Type= 3
Dn Slope=0.005
Boundary for River Rch & Prof#=CCLC 012,Reach-1         , 6
Up Type= 0
Dn Type= 3
Dn Slope=0.005
Boundary for River Rch & Prof#=CCLC 012,Reach-1         , 7
Up Type= 0
Dn Type= 3
Dn Slope=0.005
DSS Import GetInterval= 0
DSS Import GetPeak= 0
DSS Import FillOption= 0

--- CCLC 012.g01 (geometry) ---

Geom Title=Existing Conditions
Program Version=4.10

River Reach=CCLC 012        ,Reach-1
Reach XY= 30
      3755143.23     10126786.84      3754958.23     10126826.84
      3754678.23     10126826.84      3754228.23     10126746.84
      3754108.23     10126756.84      3753968.23     10126686.84
      3753928.23     10126726.84      3753738.23     10126706.84
      3753498.23     10126836.84      3753478.23     10126816.84
      3753198.23     10126856.84      3753038.23     10126836.84
      3752818.23     10126886.84      3752688.23     10127056.84
      3752528.23     10127096.84      3752458.23     10127066.84
      3751996.19     10127076.48      3751902.45     10127017.35
      3751823.34     10127165.67      3751769.74     10127089.91
      3751661.69     10127058.97      3751673.66     10126954.96
      3751618.94     10126909.15      3751572.82     10126923.28
      3751565.98      10127006.9      3751522.61      10127026.1
      3751417.43     10126994.17      3751316.59     10126918.51
      3751069.09     10126874.82      3750928.23     10126766.84

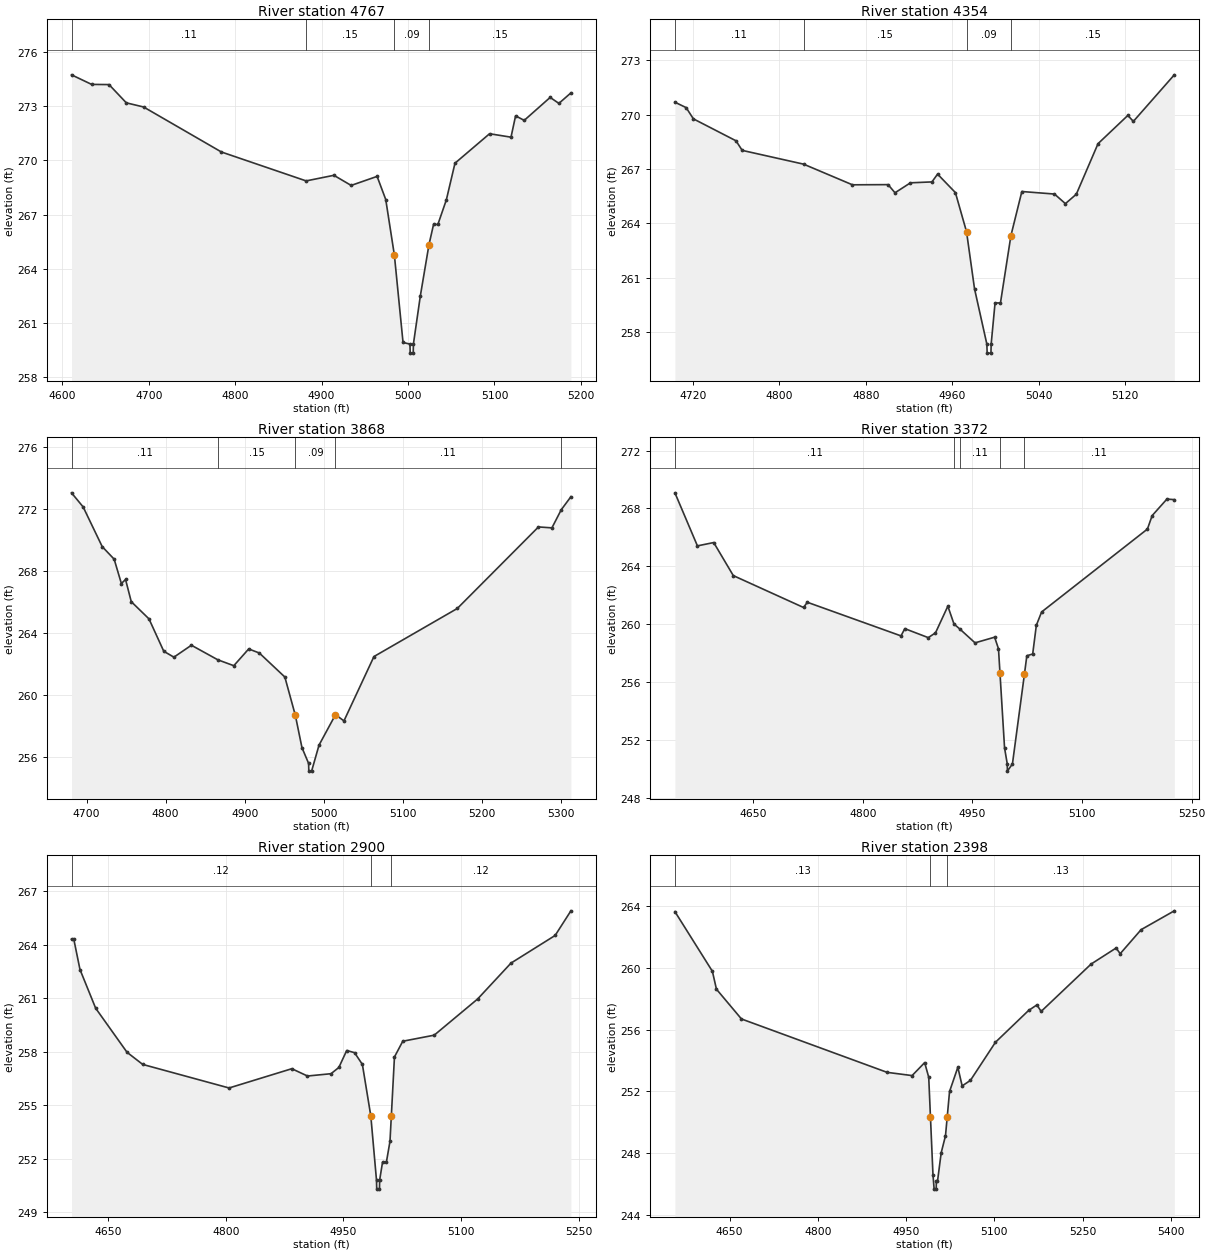
Type RM Length L Ch R = 1 ,4767    ,413,413,413
BEGIN DESCRIPTION:
CCLC 012 9.0
END DESCRIPTION:
XS GIS Cut Line= 3
        3754841.     10126427.73      3754827.98     10126846.55
      3754836.66     10127004.99
#Sta/Elev= 30
  4610.7  274.73    4634   274.2  4654.1  274.19  4674.1  273.18  4694.1  272.95
  4784.1  270.46  4882.1  268.86  4914.2  269.17  4934.2  268.61  4964.2  269.11
  4974.2  267.83  4984.2  264.75  4994.2  259.92  5002.2  259.83  5002.5  259.33
    5006  259.33  5006.2  259.83  5014.2  262.49  5024.2  265.33  5029.5  266.45
  5034.5  266.45  5044.3  267.81  5054.3  269.84  5094.3  271.47  5119.1  271.28
  5124.4  272.46  5134.4  272.21  5164.4  273.48  5174.5  273.15  5188.4  273.73
#Mann= 4 ,-1 , 0
  4610.7     .11       0  4882.1     .15       0  4984.2     .09       0
  5024.2     .15       0
Bank Sta=4984.2,5024.2
XS Rating Curve= 0 ,0
Exp/Cntr=0.3,0.1

Type RM Length L Ch R = 1 ,4354    ,486,486,486
BEGIN DESCRIPTION:
CCLC 012 8.0
END DESCRIPTION:
XS GIS Cut Line= 3
      3754517.86     10126511.03      3754438.23     10126796.84
      3754417.85     10126961.09
#Sta/Elev= 30
  4703.3  270.69  4713.7  270.39  4720.4  269.77  4759.8  268.56  4765.6  268.03
  4822.4  267.27  4867.6  266.13  4900.6  266.14    4907  265.69  4921.3  266.24
  4941.2  266.29  4946.4  266.72  4962.9   265.7  4973.2  263.54  4980.6  260.39
    4992  257.34  4992.3  256.84  4995.8  256.84    4996  257.34  4999.6  259.61
  5004.6  259.61  5014.3  263.33  5024.4  265.76  5054.6  265.62  5064.7  265.09
  5074.8  265.61  5094.9   268.4  5122.5  269.96  5127.6  269.63  5165.5   272.2
#Mann= 4 ,-1 , 0
  4703.3     .11       0  4822.4     .15       0  4973.2     .09       0
  5014.3     .15       0
Bank Sta=4973.2,5014.3
XS Rating Curve= 0 ,0
Exp/Cntr=0.3,0.1

Type RM Length L Ch R = 1 ,3868    ,496,496,496
BEGIN DESCRIPTION:
CCLC 012 7.0
END DESCRIPTION:
XS GIS Cut Line= 3
      3754117.83     10126411.12      3753998.23     10126706.84
      3754067.85     10127011.08
#Sta/Elev= 30
    4681  273.02  4695.7  272.11  4719.8  269.55  4734.9  268.74    4744  267.17
  4749.3  267.43  4756.5     266  4778.9  264.89  4797.6   262.8  4810.4  262.42
  4832.5  263.19  4865.9  262.25  4886.1  261.87  4904.9  262.95  4918.3  262.69
  4950.6  261.14  4963.9  258.66  4972.2  256.59  4980.6  255.57  4980.9  255.07
  4984.4  255.07  4993.8  256.75  5014.6  258.71  5025.3  258.31  5063.2  262.46
  5168.5  265.56  5271.1  270.82  5288.1  270.76  5299.9  271.93  5312.1  272.77
#Mann= 5 ,-1 , 0
    4681     .11       0  4865.9     .15       0  4963.9     .09       0
  5014.6     .11       0  5299.9     .15       0
Bank Sta=4963.9,5014.6
XS Rating Curve= 0 ,0
Exp/Cntr=0.3,0.1

Type RM Length L Ch R = 1 ,3372    ,472,472,472
BEGIN DESCRIPTION:
CCLC 012 6.0
END DESCRIPTION:
XS GIS Cut Line= 3
      3753447.77     10126351.76      3753588.23     10126786.84
      3753617.85      10127011.1
#Sta/Elev= 30
  4542.8  269.08  4573.6  265.42  4595.9  265.65  4622.7  263.37  4718.8  261.17
    4724  261.53  4852.2  259.21  4857.4  259.71  4889.5  259.09  4899.4  259.42
  4916.3  261.26  4924.7  260.03    4933  259.67  4953.5  258.73  4980.3  259.12
  4985.6  258.32 4987.64256.6388  4993.9  251.48  4997.6  250.38  4997.8  249.88
  5004.7  250.38 5021.19 256.601  5024.4  257.84  5032.4  257.96  5037.4  259.94
  5044.6  260.86  5189.4  266.58  5195.9  267.51  5216.1  268.65  5226.2  268.61
#Mann= 5 ,-1 , 0
  4542.8     .11       0  4924.7     .15       0    4933     .11       0
 4987.64     .06       0 5021.19     .11       0
Bank Sta=4987.64,5021.19
XS Rating Curve= 0 ,0
Exp/Cntr=0.3,0.1

Type RM Length L Ch R = 1 ,2900    ,502,502,502
BEGIN DESCRIPTION:
CCLC 012 5.0
END DESCRIPTION:
XS GIS Cut Line= 3
      3753159.14     10126460.29      3753169.99      10126857.4
      3753250.28     10127083.09
#Sta/Elev= 30
  4603.3  264.31  4606.2  264.31  4614.1  262.61  4634.1  260.44  4674.1  257.97
  4694.1  257.29  4804.2  255.97  4884.2  257.05  4904.2  256.64  4934.2  256.77
  4944.2  257.12  4954.2  258.07  4964.2  257.95  4974.2  257.29 4984.93254.4077
  4992.2   250.8  4992.5   250.3    4996   250.3  4996.2   250.8  4999.9  251.81
  5004.8  251.81  5009.4  252.98 5011.13254.4155  5015.1  257.71  5025.7  258.59
  5065.8  258.93  5121.2  260.96  5163.7  262.97    5220  264.52  5240.1   265.9
#Mann= 3 , 0 , 0
  4603.3     .12       0 4984.93     .06       0 5011.13     .12       0
Bank Sta=4984.93,5011.13
XS Rating Curve= 0 ,0
Exp/Cntr=0.3,0.1

Type RM Length L Ch R = 1 ,2398    ,462,462,462
BEGIN DESCRIPTION:
CCLC 012 4.0
END DESCRIPTION:
XS GIS Cut Line= 3
      3752417.83     10126661.06      3752738.23     10126966.84
      3753017.85     10127261.07
#Sta/Elev= 30
  4557.1  263.65  4620.8  259.78  4627.7  258.62  4670.2  256.69  4917.7  253.23
  4960.2  253.02  4981.6  253.86  4988.5  252.91 4991.42250.3511  4995.7   246.6
  4997.7  245.66  5001.2  245.66  5001.4  246.16  5003.4  246.16  5009.7  248.02
    5017  249.12    5020250.3678  5023.9  251.99    5038  253.56  5045.3  252.35
  5059.4  252.71  5101.9  255.18  5158.2  257.24  5172.3   257.6  5179.6  257.18
  5264.5  260.25    5307  261.29  5313.9  260.92  5349.5  262.48  5405.9   263.7
#Mann= 3 , 0 , 0
  4557.1     .13       0 4991.42     .08       0    5020     .13       0
Bank Sta=4991.42,5020
XS Rating Curve= 0 ,0
Exp/Cntr=0.3,0.1

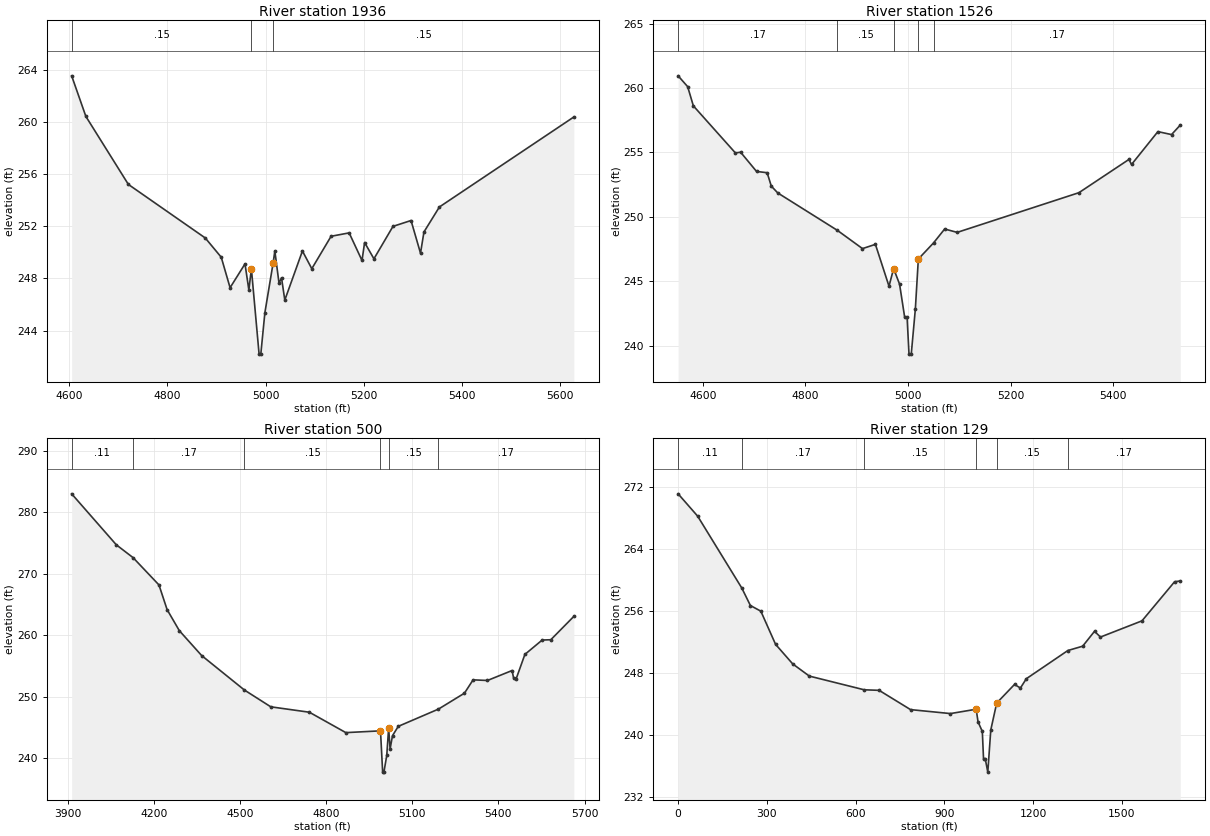
Type RM Length L Ch R = 1 ,1936    ,410,410,410
BEGIN DESCRIPTION:
CCLC 012 3.0
END DESCRIPTION:
XS GIS Cut Line= 3
      3752304.11     10126692.49      3752380.06     10127156.88
      3752903.97     10127332.76
#Sta/Elev= 30
    4605  263.56    4634  260.44  4720.6  255.22  4877.2  251.11  4909.8  249.63
  4927.8  247.29  4958.2  249.12  4966.1  247.11  4971.2  248.75  4986.9  242.19
  4990.4  242.19  4998.7  245.37 5015.52  249.19    5019  250.11  5027.5  247.64
  5032.6  248.05  5039.3  246.34  5075.2  250.11  5094.3  248.75  5133.6  251.24
  5170.4   251.5  5196.6  249.38  5201.9  250.76  5220.9  249.51  5259.7     252
  5296.5  252.45  5315.8  249.94  5322.8  251.57  5354.3  253.49  5628.2   260.4
#Mann= 3 , 0 , 0
    4605     .15       0  4971.2     .09       0 5015.52     .15       0
Bank Sta=4971.2,5015.52
XS Rating Curve= 0 ,0
Exp/Cntr=0.3,0.1

Type RM Length L Ch R = 1 ,1526    ,1026,1026,1026
BEGIN DESCRIPTION:
CCLC 012 2.0
END DESCRIPTION:
XS GIS Cut Line= 3
      3752079.17     10126633.02      3751967.19      10127065.3
      3751864.18      10127587.9
#Sta/Elev= 30
  4551.8  260.94  4570.4   260.1  4581.5  258.61  4663.4  254.96  4673.7  255.01
  4704.7  253.52  4725.4  253.42  4733.5  252.38  4746.1  251.85  4862.2  248.95
  4911.3  247.53  4936.5  247.86    4963  244.61    4972  245.98  4983.6  244.77
  4993.6  242.19  4998.3  242.19    5002  239.34  5006.4  239.34  5014.4  242.85
  5020.2  246.72  5049.8  247.97  5071.5  249.05    5096  248.79  5333.3  251.87
  5430.8  254.45  5435.9  254.06  5487.3  256.61  5513.9  256.38    5531  257.12
#Mann= 5 ,-1 , 0
  4551.8     .17       0  4862.2     .15       0    4972     .09       0
  5020.2     .15       0  5049.8     .17       0
Bank Sta=4972,5020.2
XS Rating Curve= 0 ,0
Exp/Cntr=0.3,0.1

Type RM Length L Ch R = 1 ,500     ,371,371,371
BEGIN DESCRIPTION:
CCLC 012 1.0
END DESCRIPTION:
XS GIS Cut Line= 3
      3752167.83     10126211.09       3751371.5     10126949.94
      3751417.85     10127611.12
#Sta/Elev= 30
  3913.7     283  4069.3   274.7  4127.7  272.61  4217.8  268.17  4246.2  264.15
  4288.7  260.73  4366.4  256.68  4515.2  251.07  4607.3  248.33  4741.7  247.45
  4868.7  244.13  4989.4  244.42  4996.9   237.7  5001.3   237.7  5011.2  240.41
  5017.8  244.88  5022.8  241.47  5031.2  243.63  5051.3  245.15  5191.3  247.96
  5281.8  250.55  5311.9  252.72    5362  252.62  5447.8  254.24  5452.8  253.04
  5462.3  252.94  5492.3  256.86  5552.5   259.2  5582.6  259.25  5662.8  263.05
#Mann= 6 ,-1 , 0
  3913.7     .11       0  4127.7     .17       0  4515.2     .15       0
  4989.4     .09       0  5017.8     .15       0  5191.3     .17       0
Bank Sta=4989.4,5017.8
XS Rating Curve= 0 ,0
Exp/Cntr=0.3,0.1

Type RM Length L Ch R = 1 ,129     ,0,0,0
BEGIN DESCRIPTION:
CCLC 012 0.5
END DESCRIPTION:
XS GIS Cut Line= 3
      3751845.63      10126206.2      3751026.45     10126839.26
       3751072.8     10127500.39
#Sta/Elev= 30
       0  271.17      66  268.29   215.4     259   244.4  256.75   279.7  256.02
   329.5  251.74   387.5  249.21   443.6  247.64   629.1  245.87   679.6   245.8
   785.9  243.31   920.8   242.8  1007.8  243.36  1014.1  241.73  1028.6  240.49
  1032.7  236.92  1038.7  236.92  1047.1  235.24  1057.2  240.69  1077.2  244.16
  1137.4  246.56  1157.4   246.1  1177.4   247.3  1317.8  250.94  1367.9   251.5
  1407.9  253.42  1428.1  252.68  1568.4  254.77  1678.7  259.82    1698  259.92
#Mann= 6 ,-1 , 0
       0     .11       0   215.4     .17       0   629.1     .15       0
  1007.8     .06       0  1077.2     .15       0  1317.8     .17       0
Bank Sta=1007.8,1077.2
XS Rating Curve= 0 ,0
Exp/Cntr=0.3,0.1

Chan Stop Cuts=-1
Use User Specified Reach Order=0
Composite Channel Slope=5