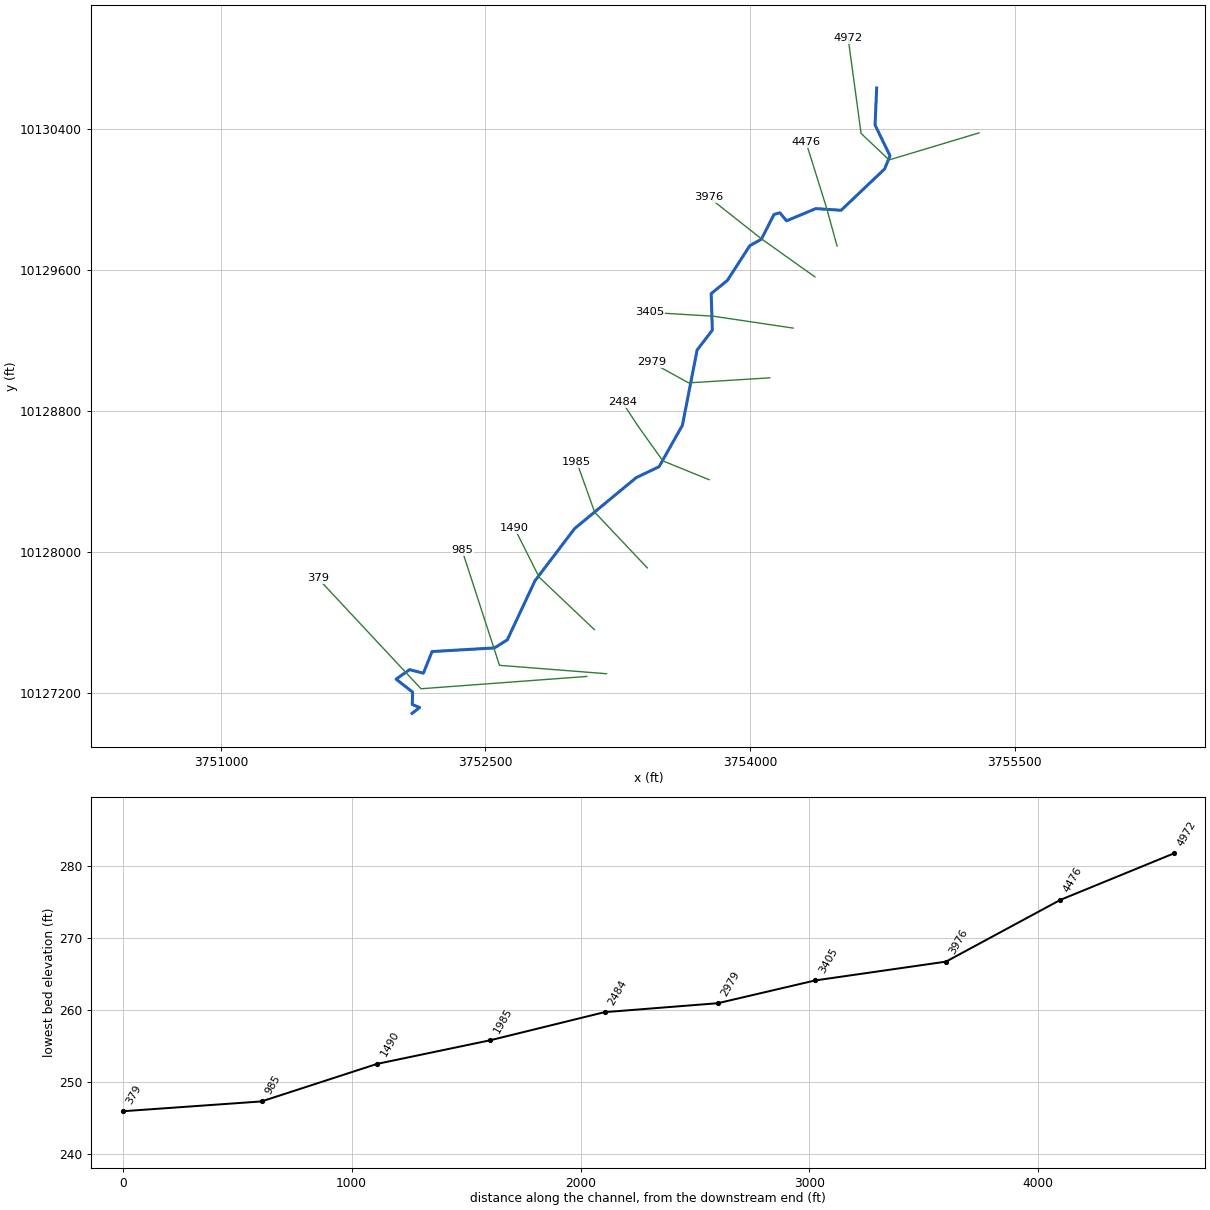
--- CCLC 013.prj (project) ---

Proj Title=CCLC 013 Base Level Engineering
Current Plan=p01
Default Exp/Contr=0.3,0.1
English Units
Geom File=g01
Flow File=f01
Flow File=f02
Plan File=p01
Y Axis Title=Elevation
X Axis Title(PF)=Main Channel Distance
X Axis Title(XS)=Station
BEGIN DESCRIPTION:
CCLC 013
END DESCRIPTION:
DSS Export Rating Curves= 0
DSS Export Rating Curve Sorted= 0
DSS Export Volume Flow Curves= 0
DXF OffsetX= 0
DXF OffsetY= 0
DXF ScaleX= 1
DXF ScaleY= 10

--- CCLC 013.p01 (plan) ---

Plan Title=Multiple Run
Short Identifier=Multiple
Geom File=g01
Flow File=f01
Subcritical Flow
K Sum by GR= 0
Std Step Tol= 0.01
Critical Tol= 0.01
Num of Std Step Trials= 20
Max Error Tol= 0.3
Flow Tol Ratio= 0.001
Split Flow NTrial= 30
Split Flow Tol= 0.02
Split Flow Ratio= 0.02
Log Output Level= 0
Friction Slope Method= 1
Unsteady Friction Slope Method= 2
Unsteady Bridges Friction Slope Method= 1
Parabolic Critical Depth
Global Vel Dist=  1 , 1 , 1
Global Log Level= 0
CheckData=True
Encroach Param= -1, 0, 0, 0
BEGIN DESCRIPTION:
Multiple Run
END DESCRIPTION:

--- CCLC 013.f01 (steady flow) ---

Flow Title=Multiple
Program Version=4.10
Number of Profiles= 7
Profile Names=10-year,25-year,50-year,1pct_min,100-year,1pct_plu,500-year
River Rch & RM=CCLC 013,Reach-1         ,4972
     703     966    1319     593    1790    5406    3409
Boundary for River Rch & Prof#=CCLC 013,Reach-1         , 1
Up Type= 0
Dn Type= 3
Dn Slope=0.005
Boundary for River Rch & Prof#=CCLC 013,Reach-1         , 2
Up Type= 0
Dn Type= 3
Dn Slope=0.005
Boundary for River Rch & Prof#=CCLC 013,Reach-1         , 3
Up Type= 0
Dn Type= 3
Dn Slope=0.005
Boundary for River Rch & Prof#=CCLC 013,Reach-1         , 4
Up Type= 0
Dn Type= 3
Dn Slope=0.005
Boundary for River Rch & Prof#=CCLC 013,Reach-1         , 5
Up Type= 0
Dn Type= 3
Dn Slope=0.005
Boundary for River Rch & Prof#=CCLC 013,Reach-1         , 6
Up Type= 0
Dn Type= 3
Dn Slope=0.005
Boundary for River Rch & Prof#=CCLC 013,Reach-1         , 7
Up Type= 0
Dn Type= 3
Dn Slope=0.005
DSS Import GetInterval= 0
DSS Import GetPeak= 0
DSS Import FillOption= 0

--- CCLC 013.f02 (steady flow) ---

Flow Title=Orig_BLE_Flows
Program Version=4.10
Number of Profiles= 7
Profile Names=10-year,25-year,50-year,1pct_min,100-year,1pct_plu,500-year
River Rch & RM=CCLC 013,Reach-1         ,4972
     703     947    1147     456    1377    4158    1982
Boundary for River Rch & Prof#=CCLC 013,Reach-1         , 1
Up Type= 0
Dn Type= 3
Dn Slope=0.005
Boundary for River Rch & Prof#=CCLC 013,Reach-1         , 2
Up Type= 0
Dn Type= 3
Dn Slope=0.005
Boundary for River Rch & Prof#=CCLC 013,Reach-1         , 3
Up Type= 0
Dn Type= 3
Dn Slope=0.005
Boundary for River Rch & Prof#=CCLC 013,Reach-1         , 4
Up Type= 0
Dn Type= 3
Dn Slope=0.005
Boundary for River Rch & Prof#=CCLC 013,Reach-1         , 5
Up Type= 0
Dn Type= 3
Dn Slope=0.005
Boundary for River Rch & Prof#=CCLC 013,Reach-1         , 6
Up Type= 0
Dn Type= 3
Dn Slope=0.005
Boundary for River Rch & Prof#=CCLC 013,Reach-1         , 7
Up Type= 0
Dn Type= 3
Dn Slope=0.005
DSS Import GetInterval= 0
DSS Import GetPeak= 0
DSS Import FillOption= 0

--- CCLC 013.g01 (geometry) ---

Geom Title=Existing Conditions
Program Version=4.10

River Reach=CCLC 013        ,Reach-1
Reach XY= 30
      3754718.23     10130631.84      3754709.11     10130422.06
      3754793.72     10130247.36      3754763.44     10130172.96
       3754516.6     10129938.49      3754373.09     10129947.97
      3754207.47     10129878.79      3754168.97     10129924.52
      3754135.84     10129914.74      3754064.66     10129774.73
      3753998.62     10129737.45       3753872.3      10129541.4
      3753779.96     10129466.02      3753786.43     10129258.54
      3753700.15     10129146.05      3753616.82     10128719.31
      3753484.54     10128484.85      3753354.31      10128422.2
      3753005.76     10128134.09      3752780.81     10127837.69
      3752624.02     10127503.12      3752551.21     10127457.24
      3752197.33     10127436.65       3752148.3     10127314.07
      3752070.16     10127333.99      3751993.54     10127280.36
      3752087.01     10127206.82      3752085.48     10127136.33
      3752126.85     10127119.48      3752084.12     10127086.18

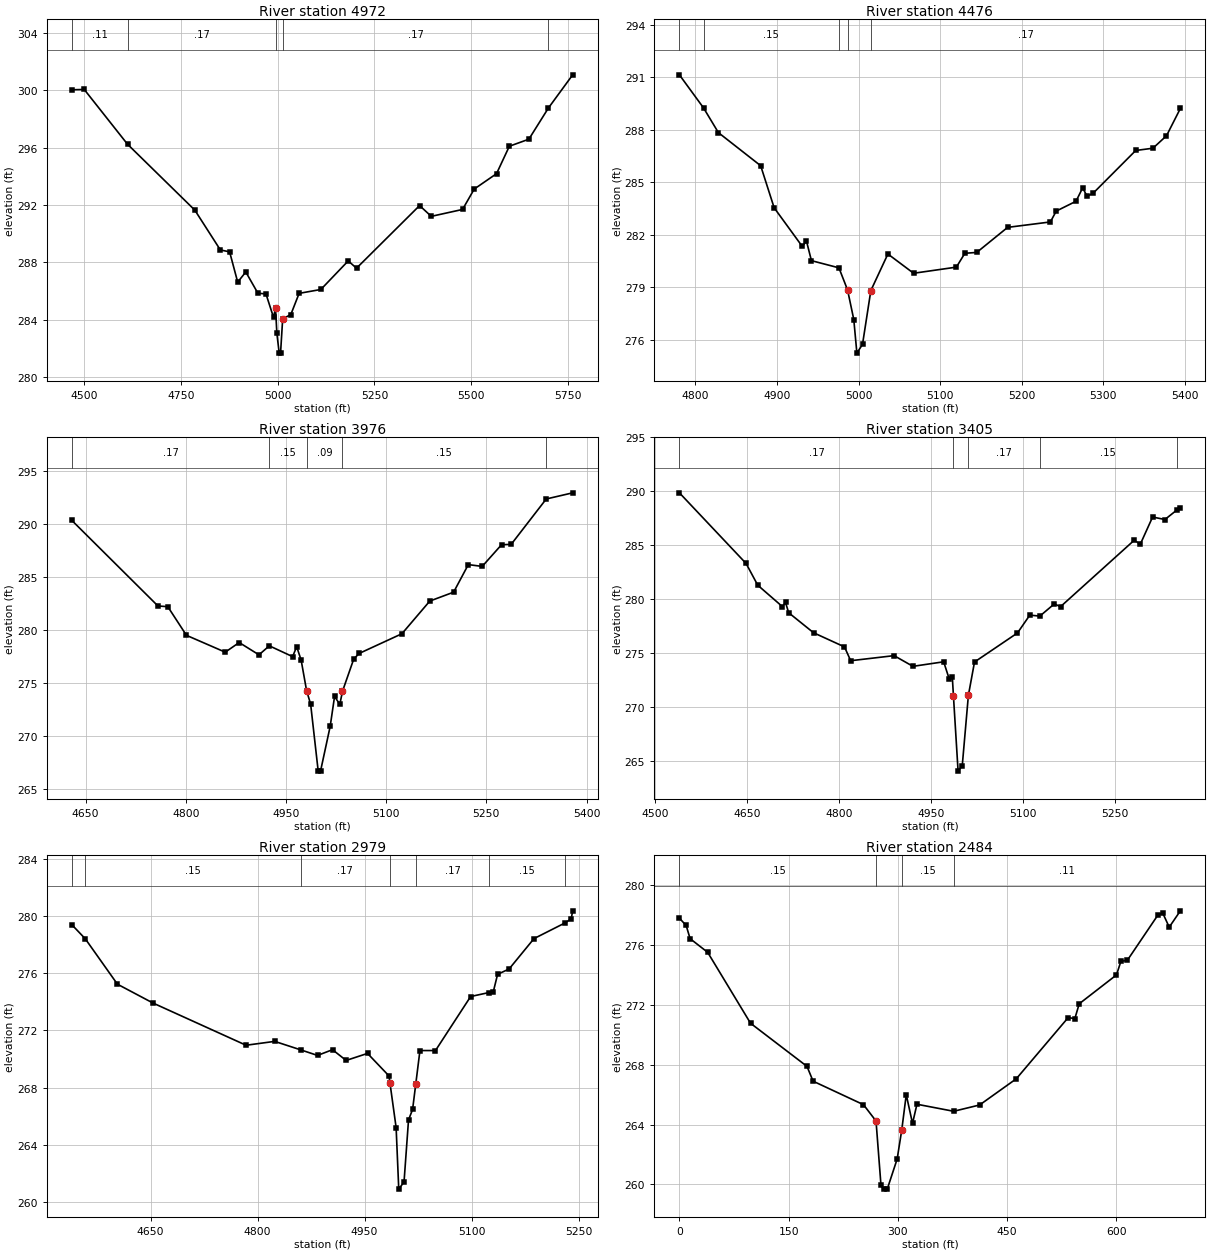
Type RM Length L Ch R = 1 ,4972    ,496,496,496
BEGIN DESCRIPTION:
CCLC 013 9.0
END DESCRIPTION:
XS GIS Cut Line= 4
      3755298.88     10130377.36      3754788.72     10130224.05
      3754629.72     10130374.38      3754556.72     10130913.34
#Sta/Elev= 30
  4467.3  300.02  4499.7  300.04  4611.6  296.23  4785.7  291.64  4851.7  288.87
  4875.6  288.74  4896.5  286.63  4917.4  287.34  4948.7  285.86  4969.6  285.81
  4989.1  284.18  4994.3  284.82  4997.8  283.06  5003.8  281.69  5007.3  281.69
  5012.8  284.08  5033.8  284.37  5055.3  285.85  5111.5  286.12  5182.3  288.11
  5203.7   287.6  5366.8  291.96  5397.1  291.21  5477.9  291.69  5508.1  293.11
  5565.8  294.18  5598.9  296.09  5649.4  296.58  5699.9  298.75  5762.7  301.06
#Mann= 5 ,-1 , 0
  4467.3     .11       0  4611.6     .17       0  4994.3     .09       0
  5012.8     .17       0  5699.9     .11       0
Bank Sta=4994.3,5012.8
XS Rating Curve= 0 ,0
Exp/Cntr=0.3,0.1

Type RM Length L Ch R = 1 ,4476    ,500,500,500
BEGIN DESCRIPTION:
CCLC 013 8.0
END DESCRIPTION:
XS GIS Cut Line= 3
      3754493.78     10129734.99      3754435.73     10129946.78
        3754318.     10130323.09
#Sta/Elev= 30
  4780.4  291.14    4810  289.25  4828.2  287.84    4880  285.95  4896.5  283.55
    4931  281.34  4936.1  281.65  4942.2  280.53  4975.9  280.12 4986.47278.8574
  4994.1  277.17  4997.9  275.25  5004.8  275.75    5015  278.82  5035.9  280.91
  5067.4  279.81  5119.8  280.16  5130.2  280.95  5144.8     281  5182.6  282.43
    5235  282.74  5242.2  283.36  5266.4  283.92  5274.6  284.69  5279.9  284.21
  5287.4  284.38  5339.6  286.82  5360.7  286.95  5377.3  287.66  5394.3  289.22
#Mann= 5 ,-1 , 0
  4780.4     .17       0    4810     .15       0  4975.9     .17       0
 4986.47     .09       0    5015     .17       0
Bank Sta=4986.47,5015
XS Rating Curve= 0 ,0
Exp/Cntr=0.3,0.1

Type RM Length L Ch R = 1 ,3976    ,571,571,571
BEGIN DESCRIPTION:
CCLC 013 7.0
END DESCRIPTION:
XS GIS Cut Line= 3
      3754367.84     10129561.08      3754065.64     10129776.12
      3753767.87     10130011.06
#Sta/Elev= 30
  4629.1  290.35  4758.2  282.27    4773   282.2  4800.9   279.5    4859  277.91
  4879.9  278.82  4909.5  277.66    4925  278.51  4959.9  277.49    4966  278.43
  4972.7  277.15  4980.8  274.29  4986.9     273  4998.2  266.69  5001.7  266.69
  5016.2  270.93  5022.7  273.73  5030.6  272.99 5034.57274.2181  5051.4  277.26
  5059.5  277.79  5123.6  279.65  5165.3  282.73    5201  283.57    5223  286.17
  5243.8     286  5272.7  288.04  5287.2  288.08  5339.7  292.36  5379.3  292.94
#Mann= 5 ,-1 , 0
  4629.1     .17       0    4925     .15       0  4980.8     .09       0
 5034.57     .15       0  5339.7     .11       0
Bank Sta=4980.8,5034.57
XS Rating Curve= 0 ,0
Exp/Cntr=0.3,0.1

Type RM Length L Ch R = 1 ,3405    ,426,426,426
BEGIN DESCRIPTION:
CCLC 013 6.0
END DESCRIPTION:
XS GIS Cut Line= 3
      3754244.23     10129270.59      3753792.82     10129337.87
      3753432.67     10129359.57
#Sta/Elev= 30
  4539.3  289.85  4648.1  283.31  4667.1   281.3  4707.3  279.32  4712.4   279.7
  4717.6  278.75  4758.1   276.9  4808.6  275.59  4818.7  274.31  4889.5  274.78
  4920.3  273.79  4970.4  274.21  4979.5  272.61  4984.5  272.81 4986.34271.0396
  4993.9  264.09  5000.7  264.59  5010.7   271.1  5020.7  274.19  5090.8  276.88
  5110.9  278.53  5127.3  278.44  5150.9  279.57    5161  279.31  5281.2  285.46
  5291.2   285.1  5311.2  287.61  5331.3  287.38  5350.6  288.25  5356.5  288.48
#Mann= 5 ,-1 , 0
  4539.3     .17       0 4986.34     .09       0  5010.7     .17       0
  5127.3     .15       0  5350.6     .11       0
Bank Sta=4986.34,5010.7
XS Rating Curve= 0 ,0
Exp/Cntr=0.3,0.1

Type RM Length L Ch R = 1 ,2979    ,495,495,495
BEGIN DESCRIPTION:
CCLC 013 5.0
END DESCRIPTION:
XS GIS Cut Line= 3
      3754111.87     10128988.48      3753652.06     10128959.93
      3753440.35     10129076.76
#Sta/Elev= 30
  4539.3  279.39  4558.3   278.4  4603.4  275.23  4653.5  273.91  4783.8  270.97
  4823.9  271.24  4860.3  270.65    4884  270.26    4905  270.66  4924.1  269.91
  4954.1   270.4  4984.2  268.83 4985.54268.3477  4994.2  265.23  4997.9  260.93
  5005.3  261.43  5011.6  265.76  5017.3  266.49 5021.79268.2817  5027.6   270.6
  5049.4   270.6  5098.7  274.37  5124.6  274.65  5130.4  274.69  5136.5  275.92
  5152.6  276.29  5187.5  278.41  5231.2  279.51  5239.7  279.79  5241.8  280.35
#Mann= 7 ,-1 , 0
  4539.3     .17       0  4558.3     .15       0  4860.3     .17       0
 4985.54     .09       0 5021.79     .17       0  5124.6     .15       0
  5231.2     .11       0
Bank Sta=4985.54,5021.79
XS Rating Curve= 0 ,0
Exp/Cntr=0.3,0.1

Type RM Length L Ch R = 1 ,2484    ,499,499,499
BEGIN DESCRIPTION:
CCLC 013 4.0
END DESCRIPTION:
XS GIS Cut Line= 4
      3753767.85     10128411.07      3753506.14     10128517.71
      3753367.85     10128711.07      3753275.99     10128851.26
#Sta/Elev= 30
       0  277.79     9.3   277.3    14.7  276.42    38.8  275.51    97.7  270.77
   175.2  267.89   183.6   266.9   252.8  265.33     270  264.24   276.8  259.95
   280.4  259.69   285.4  259.69     299   261.7   305.3  263.63   311.5     266
   320.1  264.08   326.2  265.36   376.6  264.89   412.2  265.31   462.6  267.06
   533.9  271.15     543  271.08     549  272.07   600.2     274   606.2   274.9
   615.3  274.99   657.5  278.03   663.8  278.12   672.6  277.19   687.9  278.28
#Mann= 4 ,-1 , 0
       0     .15       0     270     .09       0   305.3     .15       0
   376.6     .11       0
Bank Sta=270,305.3
XS Rating Curve= 0 ,0
Exp/Cntr=0.3,0.1

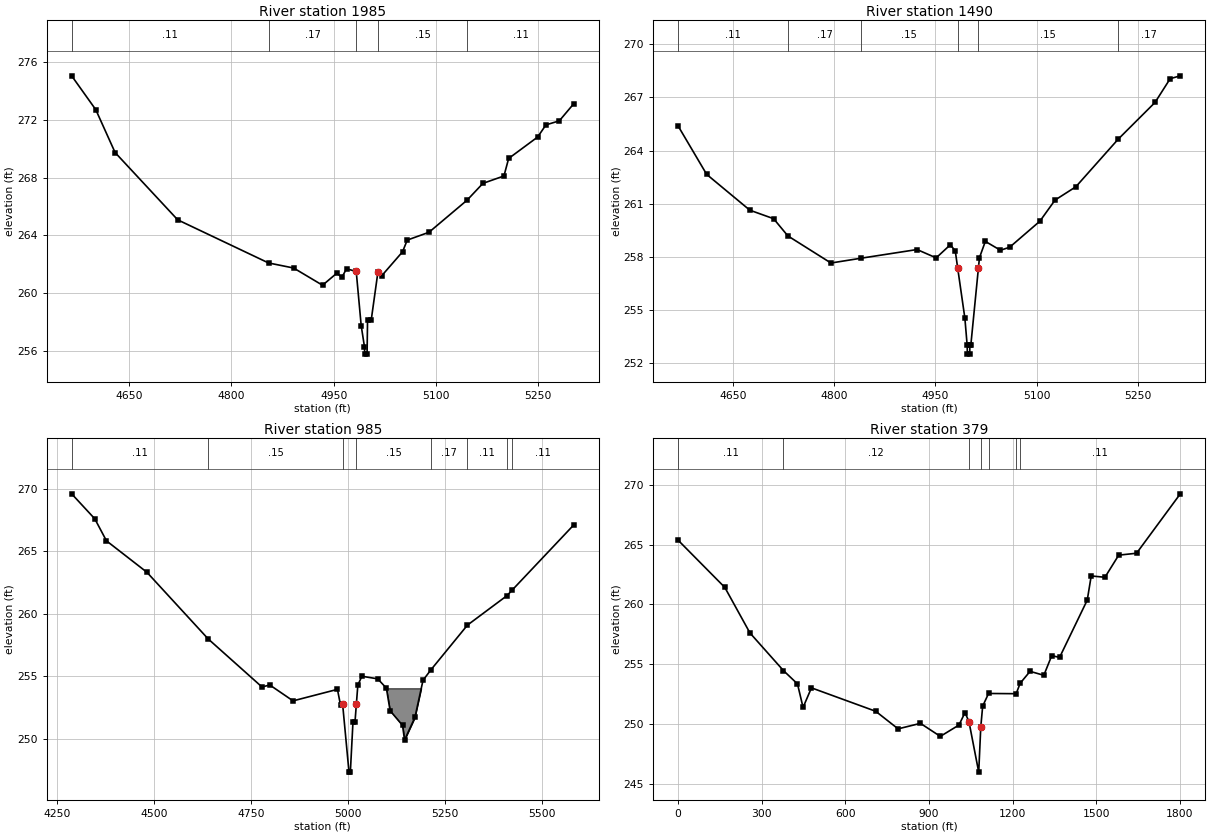
Type RM Length L Ch R = 1 ,1985    ,495,495,495
BEGIN DESCRIPTION:
CCLC 013 3.0
END DESCRIPTION:
XS GIS Cut Line= 3
      3753417.85     10127911.07      3753119.45     10128226.62
      3753017.84     10128511.12
#Sta/Elev= 30
  4565.7  275.03  4601.1  272.69  4629.4  269.73  4721.2  265.08  4854.4   262.1
  4891.2  261.75  4933.6  260.56  4954.7   261.4  4961.9   261.1  4968.8   261.7
    4983  261.51  4990.3  257.76  4995.1   256.3  4995.4   255.8  4998.9   255.8
  4999.6  258.16    5005  258.16  5014.8  261.47  5020.1   261.2  5050.9  262.87
  5057.8  263.68  5089.7  264.22  5145.6  266.44  5168.8   267.6  5199.6  268.11
  5206.5  269.32    5249   270.8  5261.2  271.64  5280.8  271.92  5302.1  273.11
#Mann= 5 ,-1 , 0
  4565.7     .11       0  4854.4     .17       0    4983     .09       0
  5014.8     .15       0  5145.6     .11       0
Bank Sta=4983,5014.8
XS Rating Curve= 0 ,0
Exp/Cntr=0.3,0.1

Type RM Length L Ch R = 1 ,1490    ,505,505,505
BEGIN DESCRIPTION:
CCLC 013 2.0
END DESCRIPTION:
XS GIS Cut Line= 3
      3753117.86     10127561.06      3752804.94     10127857.58
      3752664.79      10128136.9
#Sta/Elev= 30
  4568.9  265.39  4611.2  262.66  4675.1  260.64  4710.3  260.16  4731.4  259.19
  4795.2  257.66  4839.6  257.93  4922.7  258.42    4951  257.95    4972  258.69
  4979.3  258.34 4982.79257.3941  4993.5  254.55  4996.9  253.02  4997.2  252.52
  5000.7  252.52  5000.9  253.02  5002.3  253.02 5013.63257.4031  5015.1  257.96
  5023.8  258.88  5046.2  258.38  5059.8  258.55  5104.6  260.02    5127  261.21
  5157.8  261.96  5220.6  264.65  5275.1  266.72  5297.5  268.06  5312.5  268.22
#Mann= 6 ,-1 , 0
  4568.9     .11       0  4731.4     .17       0  4839.6     .15       0
 4982.79     .09       0 5013.63     .15       0  5220.6     .17       0
Bank Sta=4982.79,5013.63
XS Rating Curve= 0 ,0
Exp/Cntr=0.3,0.1

Type RM Length L Ch R = 1 ,985     ,606,606,606
BEGIN DESCRIPTION:
CCLC 013 1.0
END DESCRIPTION:
XS GIS Cut Line= 3
      3753187.38     10127310.96      3752579.71      10127358.7
      3752367.87     10128011.03
#Sta/Elev= 30
  4287.2  269.58  4346.9  267.58    4377  265.82  4481.2  263.31  4639.5  257.97
  4778.2  254.13  4798.3  254.29  4858.3  253.02  4972.8  253.94  4980.9  252.66
  4986.2  252.75  5002.6  247.32  5006.1  247.32  5012.9  251.34  5018.1  251.34
  5021.7252.7899  5025.4  254.28  5035.9  254.99  5076.8  254.78    5099  254.04
  5108.7  252.23  5140.7  251.06  5145.9  249.89  5172.6  251.69  5193.6  254.67
  5214.1  255.51  5308.2  259.08  5410.3  261.44  5423.2  261.87  5582.6   267.1
#Mann= 8 ,-1 , 0
  4287.2     .11       0  4639.5     .15       0  4986.2     .09       0
  5021.7     .15       0  5214.1     .17       0  5308.2     .11       0
  5410.3     .17       0  5423.2     .11       0
#Block Obstruct= 1 ,-1
 5098.99 5191.94  254.02
Bank Sta=4986.2,5021.7
XS Rating Curve= 0 ,0
Exp/Cntr=0.3,0.1

Type RM Length L Ch R = 1 ,379     ,0,0,0
BEGIN DESCRIPTION:
CCLC 013 0.5
END DESCRIPTION:
XS GIS Cut Line= 3
      3753074.95     10127295.61      3752134.96     10127225.81
      3751548.64     10127854.02
#Sta/Elev= 30
       0  265.36   167.6  261.41   257.8   257.6   378.1  254.45   428.3  253.34
   448.3  251.37   478.4  253.01     709  251.05   789.3  249.58   869.5  250.04
   940.8  248.95  1007.8   249.9  1029.3  250.94  1043.5  250.19  1078.6  245.96
    1086  249.75  1092.8  251.48  1113.9  252.54    1213  252.52  1227.2  253.39
  1262.8  254.39  1312.2  254.06  1340.5   255.7  1368.8  255.56    1468  260.35
  1482.2  262.37  1531.5  262.26  1580.9  264.11  1644.9  264.27  1801.9  269.24
#Mann= 7 ,-1 , 0
       0     .11       0   378.1     .12       0  1043.5     .06       0
    1086     .15       0  1113.9     .09       0    1213     .15       0
  1227.2     .11       0
Bank Sta=1043.5,1086
XS Rating Curve= 0 ,0
Exp/Cntr=0.3,0.1

Chan Stop Cuts=-1
Use User Specified Reach Order=0
Composite Channel Slope=5