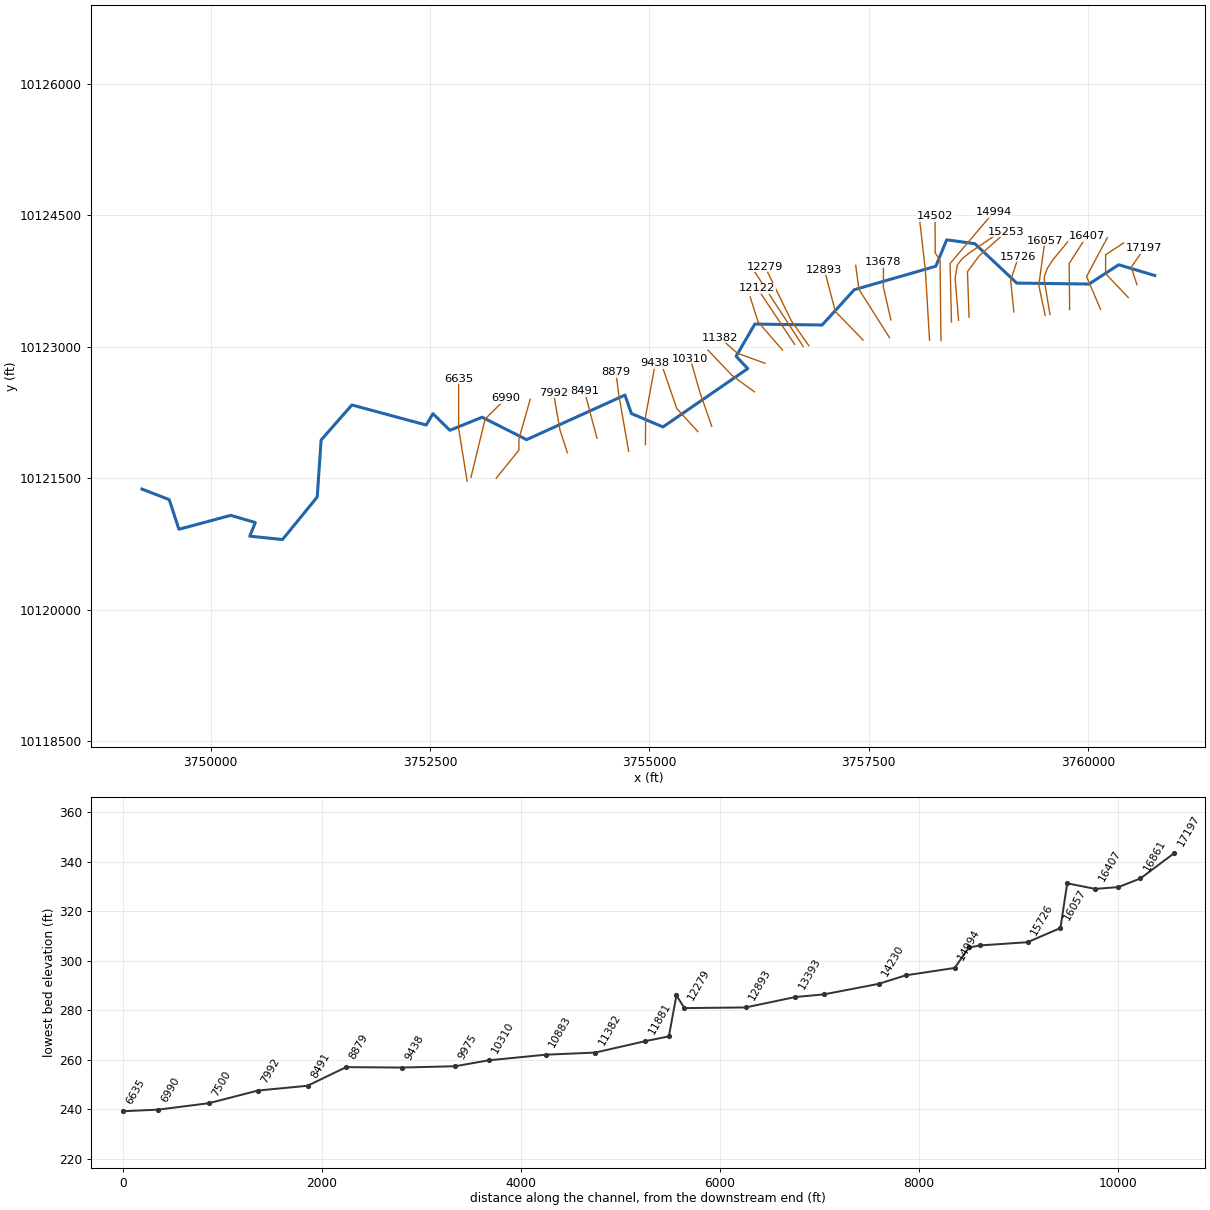
--- CCLC 015.prj (project) ---

Proj Title=CCLC 015 Base Level Engineering
Current Plan=p01
Default Exp/Contr=0.3,0.1
English Units
Geom File=g01
Flow File=f01
Flow File=f02
Plan File=p01
Y Axis Title=Elevation
X Axis Title(PF)=Main Channel Distance
X Axis Title(XS)=Station
BEGIN DESCRIPTION:
CCLC 015
END DESCRIPTION:
DSS Export Rating Curves= 0
DSS Export Rating Curve Sorted= 0
DSS Export Volume Flow Curves= 0
DXF OffsetX= 0
DXF OffsetY= 0
DXF ScaleX= 1
DXF ScaleY= 10

--- CCLC 015.p01 (plan) ---

Plan Title=Multiple Run
Short Identifier=Multiple
Geom File=g01
Flow File=f01
Subcritical Flow
K Sum by GR= 0
Std Step Tol= 0.01
Critical Tol= 0.01
Num of Std Step Trials= 20
Max Error Tol= 0.3
Flow Tol Ratio= 0.001
Split Flow NTrial= 30
Split Flow Tol= 0.02
Split Flow Ratio= 0.02
Log Output Level= 0
Friction Slope Method= 1
Unsteady Friction Slope Method= 2
Unsteady Bridges Friction Slope Method= 1
Parabolic Critical Depth
Global Vel Dist=  1 , 1 , 1
Global Log Level= 0
CheckData=True
Encroach Param= -1, 0, 0, 0
BEGIN DESCRIPTION:
Multiple Run
END DESCRIPTION:

--- CCLC 015.f01 (steady flow) ---

Flow Title=Multiple
Program Version=4.10
Number of Profiles= 7
Profile Names=10-year,25-year,50-year,1pct_min,100-year,1pct_plu,500-year
River Rch & RM=CCLC 015,Reach-1         ,17197
      94     111     137      56     170     513     270
River Rch & RM=CCLC 015,Reach-1         ,16057
     197     248     321     137     415    1253     712
River Rch & RM=CCLC 015,Reach-1         ,14994
     426     567     759     335    1013    3059    1859
River Rch & RM=CCLC 015,Reach-1         ,12122
     650     884    1199     535    1616    4880    3034
River Rch & RM=CCLC 015,Reach-1         ,5493
     902    1246    1709     769    2323    7015    4444
Boundary for River Rch & Prof#=CCLC 015,Reach-1         , 1
Up Type= 0
Dn Type= 3
Dn Slope=0.005
Boundary for River Rch & Prof#=CCLC 015,Reach-1         , 2
Up Type= 0
Dn Type= 3
Dn Slope=0.005
Boundary for River Rch & Prof#=CCLC 015,Reach-1         , 3
Up Type= 0
Dn Type= 3
Dn Slope=0.005
Boundary for River Rch & Prof#=CCLC 015,Reach-1         , 4
Up Type= 0
Dn Type= 3
Dn Slope=0.005
Boundary for River Rch & Prof#=CCLC 015,Reach-1         , 5
Up Type= 0
Dn Type= 3
Dn Slope=0.005
Boundary for River Rch & Prof#=CCLC 015,Reach-1         , 6
Up Type= 0
Dn Type= 3
Dn Slope=0.005
Boundary for River Rch & Prof#=CCLC 015,Reach-1         , 7
Up Type= 0
Dn Type= 3
Dn Slope=0.005
DSS Import GetInterval= 0
DSS Import GetPeak= 0
DSS Import FillOption= 0

--- CCLC 015.f02 (steady flow) ---

Flow Title=Orig_BLE_Flows
Program Version=4.10
Number of Profiles= 7
Profile Names=10-year,25-year,50-year,1pct_min,100-year,1pct_plu,500-year
River Rch & RM=CCLC 015,Reach-1         ,17197
      94     109     119      43     131     396     157
River Rch & RM=CCLC 015,Reach-1         ,16057
     197     243     279     106     319     963     414
River Rch & RM=CCLC 015,Reach-1         ,14994
     426     556     660     258     779    2352    1081
River Rch & RM=CCLC 015,Reach-1         ,12122
     650     867    1043     412    1243    3755    1764
River Rch & RM=CCLC 015,Reach-1         ,5493
     902    1222    1486     592    1787    5397    2584
Boundary for River Rch & Prof#=CCLC 015,Reach-1         , 1
Up Type= 0
Dn Type= 3
Dn Slope=0.005
Boundary for River Rch & Prof#=CCLC 015,Reach-1         , 2
Up Type= 0
Dn Type= 3
Dn Slope=0.005
Boundary for River Rch & Prof#=CCLC 015,Reach-1         , 3
Up Type= 0
Dn Type= 3
Dn Slope=0.005
Boundary for River Rch & Prof#=CCLC 015,Reach-1         , 4
Up Type= 0
Dn Type= 3
Dn Slope=0.005
Boundary for River Rch & Prof#=CCLC 015,Reach-1         , 5
Up Type= 0
Dn Type= 3
Dn Slope=0.005
Boundary for River Rch & Prof#=CCLC 015,Reach-1         , 6
Up Type= 0
Dn Type= 3
Dn Slope=0.005
Boundary for River Rch & Prof#=CCLC 015,Reach-1         , 7
Up Type= 0
Dn Type= 3
Dn Slope=0.005
DSS Import GetInterval= 0
DSS Import GetPeak= 0
DSS Import FillOption= 0

--- CCLC 015.g01 (geometry) ---

Geom Title=Existing Conditions
Program Version=4.10

River Reach=CCLC 015        ,Reach-1
Reach XY= 30
       3760759.3     10123811.65      3760347.84     10123934.04
      3760009.91     10123714.26      3759186.69     10123725.11
      3758709.12     10124174.39      3758388.31     10124218.45
      3758264.04     10123917.17      3757335.74     10123649.79
      3756968.56     10123246.84      3756202.19     10123258.13
      3755988.57     10122890.65      3756121.44     10122749.97
      3755155.26     10122085.05      3754795.61     10122237.57
      3754722.18     10122448.46      3753601.81     10121940.06
      3753094.83     10122195.91      3752727.09     10122046.83
      3752534.01     10122236.35      3752457.36     10122106.66
      3751610.56     10122335.77      3751259.98     10121935.87
      3751215.62      10121286.1      3750820.13      10120801.4
      3750446.55     10120839.67      3750510.23     10120995.25
      3750229.51     10121076.82      3749639.74     10120918.29
      3749529.57     10121255.89      3749218.23     10121376.84

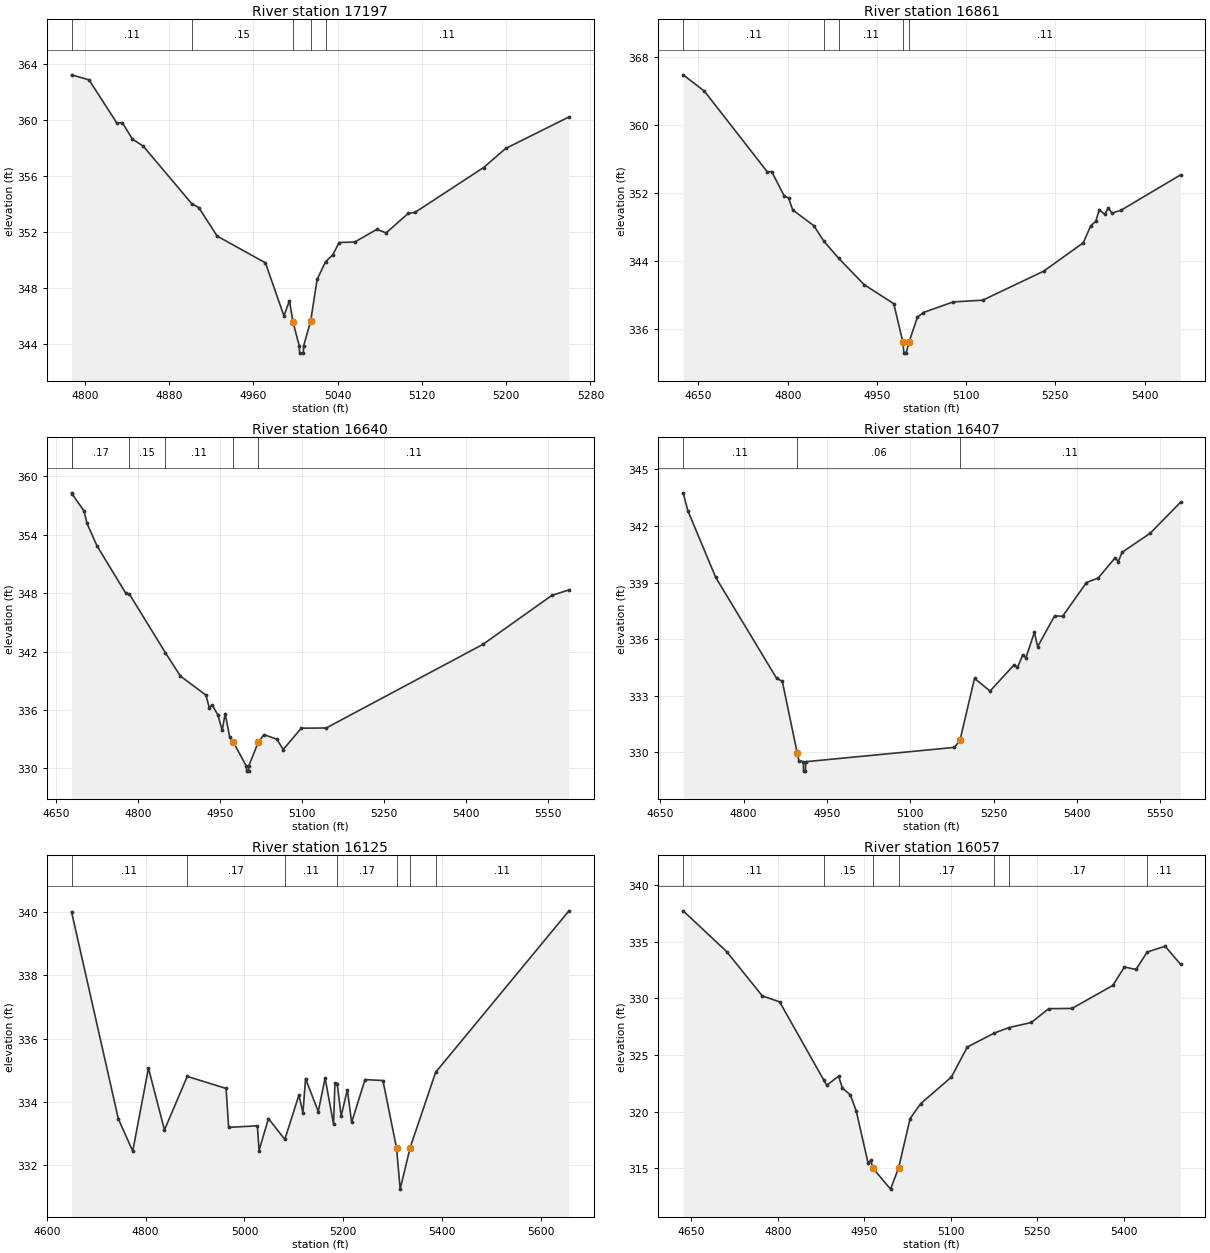
Type RM Length L Ch R = 1 ,17197   ,336,336,336
BEGIN DESCRIPTION:
CCLC 015 30.0
END DESCRIPTION:
XS GIS Cut Line= 3
      3760556.71     10123706.24      3760490.73     10123905.92
      3760640.04     10124121.21
#Sta/Elev= 30
  4787.3  363.21  4803.9  362.85  4830.4  359.76  4835.6  359.79    4845  358.63
  4855.6   358.1  4901.4  354.01  4908.2  353.72  4925.6  351.69  4971.4  349.78
    4989  345.99  4994.2  347.08  4997.6  345.55  5003.6  343.83  5003.9  343.33
  5007.4  343.33  5007.6  343.83  5014.4  345.63  5020.5   348.6  5028.5  349.86
  5035.4  350.36  5041.4  351.23  5056.3  351.27  5077.2  352.17    5086  351.92
    5107  353.31  5113.4  353.38  5178.6  356.59  5199.5  357.95  5259.6   360.2
#Mann= 5 ,-1 , 0
  4787.3     .11       0  4901.4     .15       0  4997.6     .09       0
  5014.4     .15       0  5028.5     .11       0
Bank Sta=4997.6,5014.4
XS Rating Curve= 0 ,0
Exp/Cntr=0.3,0.1

Type RM Length L Ch R = 1 ,16861   ,221,221,221
BEGIN DESCRIPTION:
Mapping XS 11dd6ecb
END DESCRIPTION:
XS GIS Cut Line= 4
      3760457.74     10123560.43      3760199.06       10123833.
      3760199.06     10124048.28      3760404.25     10124182.77
#Sta/Elev= 30
  4624.2   365.9    4660  363.98  4765.9  354.49  4773.2  354.53  4794.3  351.65
  4801.5  351.44  4808.4  350.04    4844  348.18    4861  346.35  4885.7  344.36
  4928.6  341.26  4978.3  339.03 4993.63  334.54  4995.5  333.22    4999  333.22
 5003.96 334.512  5018.1  337.43  5028.1  337.99  5078.1  339.23  5128.1  339.44
  5230.6  342.85    5297  346.18  5309.5  348.17  5318.1   348.7    5324  350.07
  5333.2  349.51  5339.1  350.27  5345.3  349.67  5360.2  349.99  5460.6  354.15
#Mann= 5 ,-1 , 0
  4624.2     .11       0    4861     .15       0  4885.7     .11       0
 4993.63     .07       0 5003.96     .11       0
Bank Sta=4993.63,5003.96
XS Rating Curve= 0 ,0
Exp/Cntr=0.3,0.1

Type RM Length L Ch R = 1 ,16640   ,233,233,233
BEGIN DESCRIPTION:
Mapping XS 94903d9f
END DESCRIPTION:
XS GIS Cut Line= 3
      3760141.78       10123425.      3759982.05     10123800.01
      3760218.18     10124242.76
#Sta/Elev= 30
  4678.5   358.3  4679.1  358.21  4701.3  356.44  4706.8  355.16    4725  352.86
  4777.7  347.99  4784.3   347.9  4849.9   341.9  4877.6  339.48  4924.2  337.53
  4930.3  336.25  4935.7  336.49    4946  335.51  4953.9   333.9  4959.4  335.63
  4967.7  333.21 4974.18332.7102  4998.3  330.22  4998.6  329.72  5002.1  329.72
  5002.3  330.22 5019.77332.6718  5030.3  333.47  5053.9     333  5065.5  331.94
  5098.6  334.13    5144  334.15  5430.4  342.73  5556.5  347.76  5587.9  348.33
#Mann= 6 ,-1 , 0
  4678.5     .11       0  4679.1     .17       0  4784.3     .15       0
  4849.9     .11       0 4974.18     .06       0 5019.77     .11       0
Bank Sta=4974.18,5019.77
XS Rating Curve= 0 ,0
Exp/Cntr=0.3,0.1

Type RM Length L Ch R = 1 ,16407   ,282,282,282
BEGIN DESCRIPTION:
Mapping XS 1c4350fe
END DESCRIPTION:
XS GIS Cut Line= 3
      3759789.08     10123422.53      3759783.87     10123948.55
      3759983.61     10124259.83
#Sta/Elev= 30
    4691  343.76  4699.5  342.81  4749.5  339.28  4859.5  333.91  4869.6  333.76
 4896.37329.9634  4899.6  329.55  4907.6  329.49  4907.8  328.99  4911.3  328.99
  4911.6  329.49  5179.6  330.25  5189.6  330.63  5215.8  333.91  5243.8  333.24
  5287.3  334.64  5293.2  334.49  5302.5  335.15  5308.4  335.01  5323.6  336.35
  5329.6   335.6    5360  337.23  5374.5  337.21  5417.5     339  5438.6  339.24
    5469  340.31  5474.9  340.11  5481.4   340.6  5532.4  341.62  5586.9  343.26
#Mann= 3 , 0 , 0
    4691     .11       0 4896.37     .06       0  5189.6     .11       0
Bank Sta=4896.37,5189.6
XS Rating Curve= 0 ,0
Exp/Cntr=0.3,0.1

Type RM Length L Ch R = 1 ,16125   ,68,68,68
BEGIN DESCRIPTION:
Mapping XS d882fb5f
END DESCRIPTION:
XS GIS Cut Line= 6
      3759565.11     10123367.87      3759502.62     10123742.82
      3759500.02      10123794.9      3759533.87     10123891.26
      3759596.37     10123987.61      3759822.88     10124263.58
#Sta/Elev= 30
  4650.1  340.01  4744.8  333.47  4773.9  332.45  4805.7  335.07  4838.1  333.12
  4884.2  334.81  4962.8  334.43  4967.9   333.2  5026.1  333.25  5029.5  332.47
  5048.5  333.48  5081.6  332.82  5110.1  334.22  5118.3  333.66  5123.6  334.74
  5149.3   333.7  5163.1  334.76  5180.2   333.3    5183  334.61  5187.6  334.58
  5195.6  333.56  5208.1  334.39  5216.8  333.36  5243.9  334.71  5280.1  334.68
 5307.73332.5408    5315  331.25 5335.04332.5557  5386.7  334.94  5656.4  340.04
#Mann= 7 ,-1 , 0
  4650.1     .11       0  4884.2     .17       0  5081.6     .11       0
  5187.6     .17       0 5307.73     .09       0 5335.04     .17       0
  5386.7     .11       0
Bank Sta=5307.73,5335.04
XS Rating Curve= 0 ,0
Exp/Cntr=0.3,0.1

Type RM Length L Ch R = 1 ,16057   ,331,331,331
BEGIN DESCRIPTION:
Mapping XS 059a9fce
END DESCRIPTION:
XS GIS Cut Line= 3
      3759510.44     10123357.37      3759437.52     10123701.15
      3759507.62     10124207.49
#Sta/Elev= 30
  4635.7  337.73    4711  334.14  4773.1  330.22    4803   329.7  4879.6   322.8
  4884.8  322.35  4905.3  323.14  4911.8   322.1  4925.7  321.49  4935.9  320.07
  4956.3   315.5  4961.4  315.72 4964.23315.0615  4995.4  313.18 5009.38315.0689
  5029.3   319.4  5047.6  320.72    5101  323.07  5128.4  325.71    5175  326.94
  5200.5  327.43  5239.4  327.88  5269.7   329.1  5310.1  329.12  5380.8  331.15
    5401  332.77  5421.1  332.56  5440.5   334.1  5471.6  334.61  5498.3  333.01
#Mann= 7 ,-1 , 0
  4635.7     .11       0  4879.6     .15       0 4964.23     .09       0
 5009.38     .17       0    5175     .11       0  5200.5     .17       0
  5440.5     .11       0
Bank Sta=4964.23,5009.38
XS Rating Curve= 0 ,0
Exp/Cntr=0.3,0.1

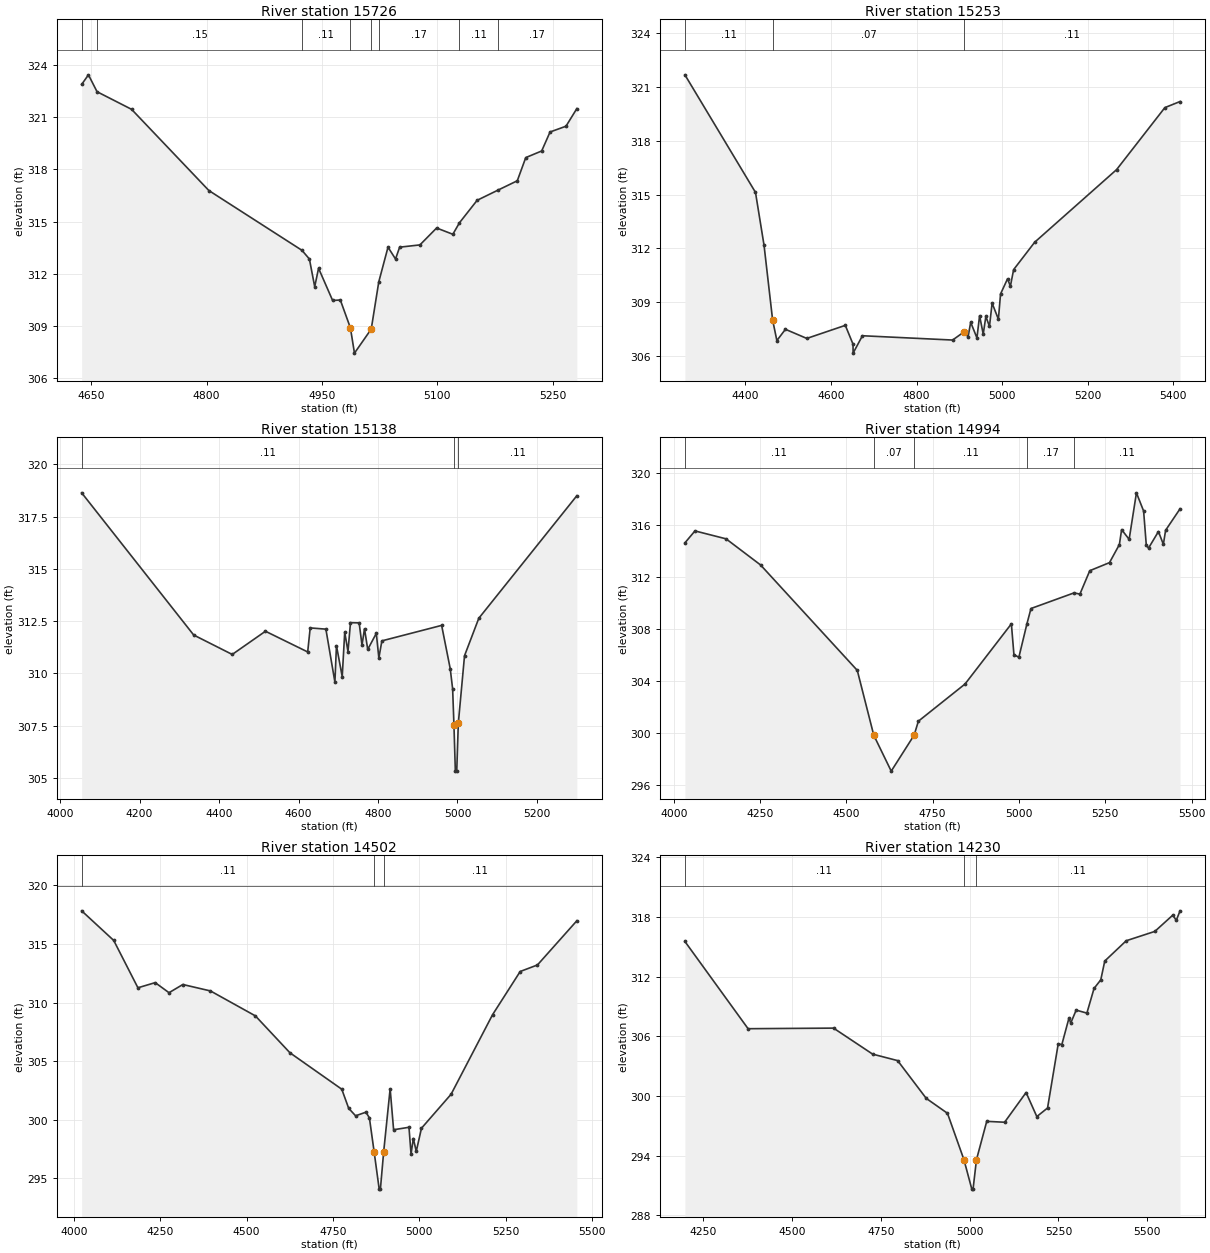
Type RM Length L Ch R = 1 ,15726   ,473,473,473
BEGIN DESCRIPTION:
CCLC 015 29.0
END DESCRIPTION:
XS GIS Cut Line= 3
      3759153.66     10123396.48      3759117.02     10123757.12
      3759205.74     10124024.06
#Sta/Elev= 30
  4637.5  322.87  4646.3  323.42  4657.5  322.45  4702.4  321.44  4802.9  316.78
  4923.9  313.35  4933.6  312.85  4940.5  311.26  4945.5  312.32  4963.8  310.47
  4973.8   310.5 4986.91308.8981  4992.2  307.45    5014  308.83  5023.8  311.54
  5035.8  313.53  5045.6  312.85  5050.9  313.53  5077.3  313.66    5099  314.63
  5120.1  314.27  5128.7  314.93  5151.7  316.22  5178.6   316.8  5203.9  317.34
  5214.9  318.67  5235.6  319.05  5246.5  320.14  5267.2  320.47  5281.3  321.48
#Mann= 8 ,-1 , 0
  4637.5     .17       0  4657.5     .15       0  4923.9     .11       0
 4986.91     .06       0    5014     .11       0  5023.8     .17       0
  5128.7     .11       0  5178.6     .17       0
Bank Sta=4986.91,5014
XS Rating Curve= 0 ,0
Exp/Cntr=0.3,0.1

Type RM Length L Ch R = 1 ,15253   ,115,115,115
BEGIN DESCRIPTION:
CCLC 015 28.0
END DESCRIPTION:
XS GIS Cut Line= 4
      3758642.85     10123336.12      3758625.02      10123854.8
      3758756.97     10124034.21      3759067.86     10124311.08
#Sta/Elev= 30
  4258.3  321.69  4423.4  315.13  4443.4  312.18  4463.4  308.02  4473.4  306.86
  4493.4  307.49  4543.4  306.98  4633.5  307.71  4651.5  306.66  4651.7  306.16
  4673.5  307.13  4884.4  306.89    4912  307.36  4920.5  307.06  4926.7  307.88
  4941.3  307.01  4947.5  308.25    4956  307.22  4962.2  308.21  4970.6  307.65
  4976.8  308.95  4991.5  308.05  4996.5  309.46  5012.9  310.31  5019.5  309.89
  5027.1  310.82  5076.4  312.35  5267.9   316.4  5380.8  319.86  5416.3   320.2
#Mann= 3 ,-1 , 0
  4258.3     .11       0  4463.4     .07       0    4912     .11       0
Bank Sta=4463.4,4912
XS Rating Curve= 0 ,0
Exp/Cntr=0.3,0.1

Type RM Length L Ch R = 1 ,15138   ,144,144,144
BEGIN DESCRIPTION:
Mapping XS c6715533
END DESCRIPTION:
XS GIS Cut Line= 6
      3758523.45     10123300.11      3758484.39     10123784.48
      3758510.43     10123932.92      3758565.12     10124003.23
      3758658.87     10124078.76      3758989.57     10124302.69
#Sta/Elev= 30
  4054.3  318.64  4336.2  311.84  4433.2  310.91  4516.8  312.02  4623.1  311.03
  4629.4  312.18  4668.9  312.12  4691.6  309.59  4695.5  311.33    4710  309.85
  4716.3  311.98  4724.5  311.05  4730.8  312.43  4752.6  312.42  4759.8  311.36
  4766.1  312.14  4774.2  311.15  4795.8  311.92  4802.2  310.74  4809.8  311.56
  4960.2   312.3  4981.8  310.23  4987.9  309.26 4991.17307.5344  4994.7  305.33
  4998.2  305.33  5002.2307.6266  5017.8  310.85  5053.7  312.64  5300.4   318.5
#Mann= 3 ,-1 , 0
  4054.3     .11       0 4991.17     .07       0  5002.2     .11       0
Bank Sta=4991.17,5002.2
XS Rating Curve= 0 ,0
Exp/Cntr=0.3,0.1

Type RM Length L Ch R = 1 ,14994   ,492,492,492
BEGIN DESCRIPTION:
CCLC 015 27.0
END DESCRIPTION:
XS GIS Cut Line= 3
      3758442.72      10123281.9       3758427.1     10123948.55
      3758923.64     10124533.48
#Sta/Elev= 30
  4032.4  314.61  4061.6  315.53  4151.6  314.92  4251.6  312.91  4531.7   304.8
 4579.42299.8124    4630  297.05 4696.44299.8235  4708.6  300.89  4843.7  303.75
    4978  308.38  4985.4  306.01  4999.7  305.81  5023.1  308.39  5034.8  309.56
  5159.3  310.76  5176.5  310.67  5205.1  312.47  5262.2  313.09  5290.8  314.48
  5297.3  315.63  5319.1  314.88  5340.2  318.46    5361  317.06  5368.8  314.42
  5375.3  314.21  5403.9  315.48  5418.2   314.5  5424.7  315.58  5466.5  317.23
#Mann= 5 ,-1 , 0
  4032.4     .11       0 4579.42     .07       0 4696.44     .11       0
  5023.1     .17       0  5159.3     .11       0
Bank Sta=4579.42,4696.44
XS Rating Curve= 0 ,0
Exp/Cntr=0.3,0.1

Type RM Length L Ch R = 1 ,14502   ,272,272,272
BEGIN DESCRIPTION:
Mapping XS c5008eea
END DESCRIPTION:
XS GIS Cut Line= 4
      3758322.93     10123068.29      3758312.52     10123985.01
      3758257.83     10124068.34      3758255.22     10124484.99
#Sta/Elev= 30
  4022.5  317.83  4115.3   315.3  4185.3  311.26  4235.3   311.7  4275.3  310.84
  4315.3  311.54  4395.3  310.99  4525.3  308.86  4625.3  305.71  4775.3   302.6
  4795.3  300.97  4815.3  300.33  4845.3  300.64  4855.3  300.15 4869.03297.2416
  4883.6  294.07  4887.1  294.07 4896.55297.2483  4915.3  302.64  4925.3  299.14
  4969.8  299.35  4975.8  297.07  4982.4  298.39  4990.9   297.3    5006  299.27
  5091.7  302.17  5211.7  308.96  5291.7  312.65  5341.7  313.21  5455.6  316.98
#Mann= 3 ,-1 , 0
  4022.5     .11       0 4869.03     .06       0 4896.55     .11       0
Bank Sta=4869.03,4896.55
XS Rating Curve= 0 ,0
Exp/Cntr=0.3,0.1

Type RM Length L Ch R = 1 ,14230   ,552,552,552
BEGIN DESCRIPTION:
CCLC 015 26.0
END DESCRIPTION:
XS GIS Cut Line= 3
      3758192.72     10123073.56      3758145.85     10123865.21
      3758078.14     10124461.54
#Sta/Elev= 30
  4198.9  315.54  4376.7  306.76  4617.1  306.82  4727.3   304.2  4797.5  303.55
    4878  299.75  4937.7  298.25 4984.01293.5862  5006.2  290.62  5009.7  290.62
 5019.34293.5845  5048.2  297.44  5098.5  297.35  5158.9  300.34  5189.1  297.92
  5219.3  298.78  5249.4  305.25  5259.5  305.16  5279.5  307.82  5284.6  307.33
  5299.8  308.63    5330  308.33  5350.1  310.81  5369.1  311.68  5380.3  313.57
  5440.7  315.61  5521.2  316.55  5571.5  318.18  5581.6  317.67  5592.1  318.62
#Mann= 3 ,-1 , 0
  4198.9     .11       0 4984.01     .06       0 5019.34     .11       0
Bank Sta=4984.01,5019.34
XS Rating Curve= 0 ,0
Exp/Cntr=0.3,0.1

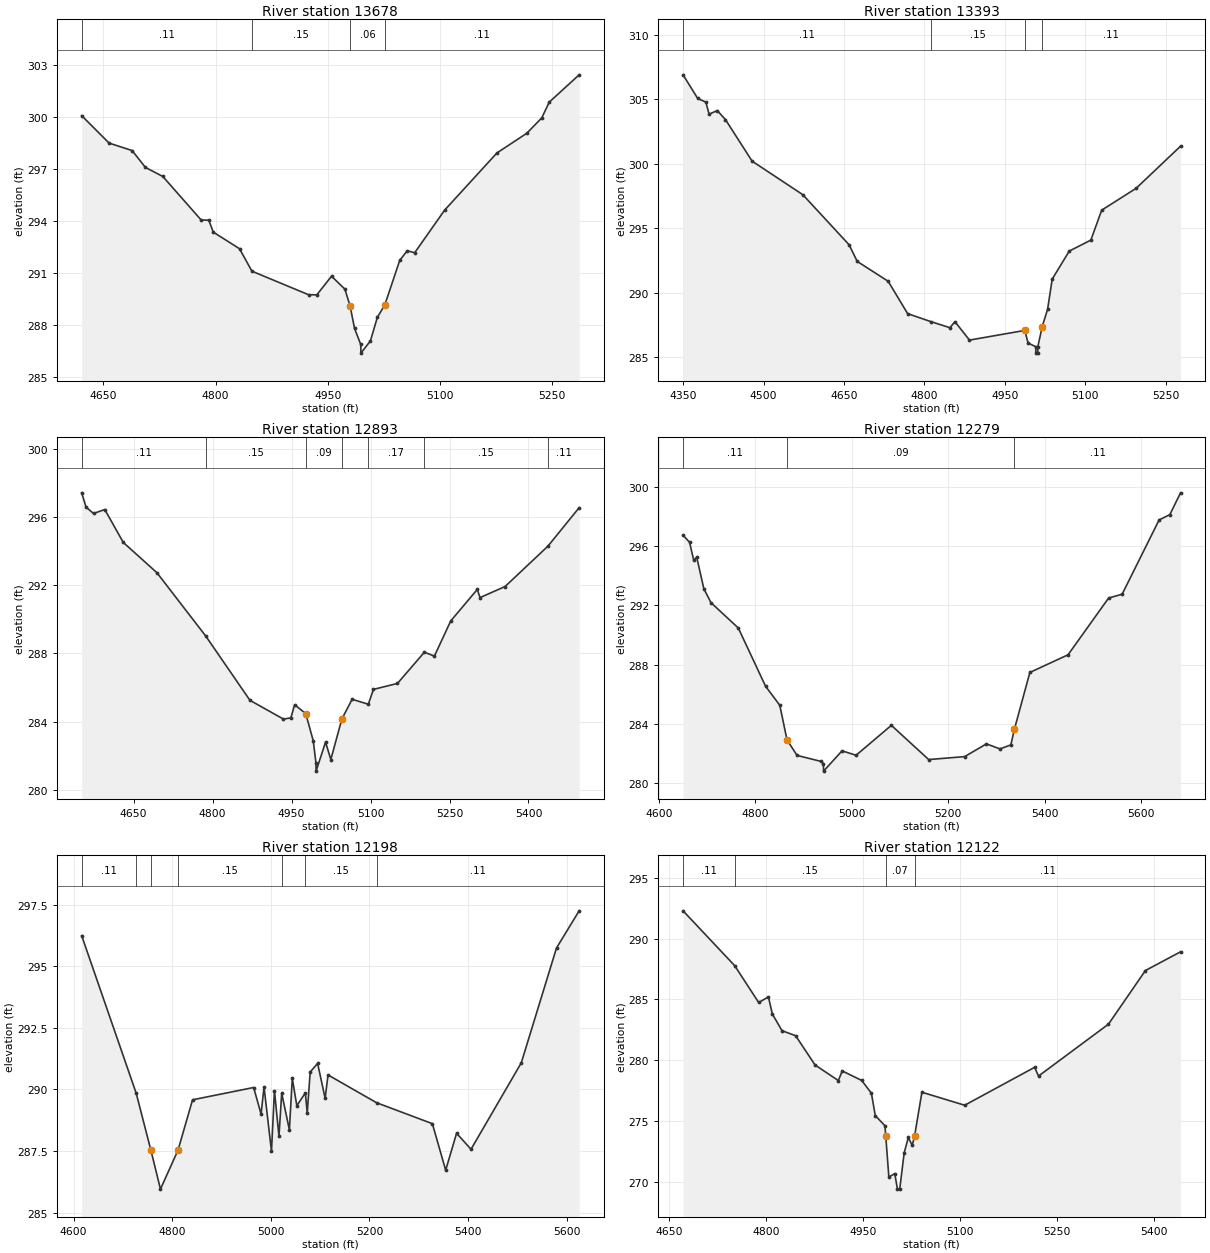
Type RM Length L Ch R = 1 ,13678   ,285,285,285
BEGIN DESCRIPTION:
CCLC 015 25.0
END DESCRIPTION:
XS GIS Cut Line= 3
      3757752.62      10123305.3      3757666.68     10123677.71
      3757667.85     10123961.11
#Sta/Elev= 30
  4620.9   300.1  4657.6  298.51  4688.4  298.08  4706.3   297.1  4729.5  296.58
  4780.8  294.06    4791  294.05    4797  293.36  4832.1   292.4  4848.7   291.1
  4924.4  289.74  4935.5  289.73  4955.2  290.81  4973.1  290.06 4980.08289.0816
    4986  287.79  4994.3  286.86  4994.5  286.36  5007.3  287.07  5016.5  288.43
  5026.5  289.15  5046.5  291.73  5056.5  292.28  5066.5  292.17  5106.5  294.63
  5176.5  297.94  5216.5  299.08  5236.5  299.97  5246.5  300.88  5286.5  302.46
#Mann= 4 ,-1 , 0
  4620.9     .11       0  4848.7     .15       0 4980.08     .06       0
  5026.5     .11       0
Bank Sta=4980.08,5026.5
XS Rating Curve= 0 ,0
Exp/Cntr=0.3,0.1

Type RM Length L Ch R = 1 ,13393   ,500,500,500
BEGIN DESCRIPTION:
CCLC 015 24.0
END DESCRIPTION:
XS GIS Cut Line= 3
      3757736.97     10123102.22      3757388.04     10123654.28
      3757351.69     10123926.88
#Sta/Elev= 30
  4349.8  306.88  4377.1  305.05  4392.4  304.76  4398.3  303.83  4413.6  304.11
  4428.9  303.41  4478.6  300.19  4573.2  297.59  4659.5  293.71  4674.7  292.42
  4732.4  290.88  4768.8  288.37  4811.5  287.76  4847.7  287.28    4857  287.75
  4884.1  286.32  4987.3  287.07  4993.5  286.09  5007.7  285.81    5008  285.31
  5011.5  285.31  5011.7  285.81  5019.8  287.36  5029.9  288.71  5038.5  291.05
  5070.3  293.22  5110.6  294.07  5130.8  296.39  5194.9  298.08  5277.9  301.35
#Mann= 4 ,-1 , 0
  4349.8     .11       0  4811.5     .15       0  4987.3     .09       0
  5019.8     .11       0
Bank Sta=4987.3,5019.8
XS Rating Curve= 0 ,0
Exp/Cntr=0.3,0.1

Type RM Length L Ch R = 1 ,12893   ,614,614,614
BEGIN DESCRIPTION:
CCLC 015 23.0
END DESCRIPTION:
XS GIS Cut Line= 3
      3757434.91     10123076.16      3757118.84     10123402.44
       3756995.1     10123877.11
#Sta/Elev= 30
  4551.4  297.41  4559.8  296.57  4573.9   296.2  4595.3  296.43  4630.5   294.5
  4694.3  292.73  4787.2  289.01    4871  285.25  4934.6  284.15  4948.7  284.22
  4955.9  284.99    4977  284.47  4991.2  282.88  4996.3   281.6  4996.6   281.1
  5014.6   282.8  5024.6  281.78  5045.6  284.16  5065.1  285.31  5095.8  285.02
  5105.6  285.89  5151.2  286.24  5202.3  288.07  5221.3  287.84  5252.3   289.9
  5302.8  291.75    5308  291.27  5355.6  291.92  5436.8  294.28  5496.2  296.54
#Mann= 7 ,-1 , 0
  4551.4     .11       0  4787.2     .15       0    4977     .09       0
  5045.6     .15       0  5095.8     .17       0  5202.3     .15       0
  5436.8     .11       0
Bank Sta=4977,5045.6
XS Rating Curve= 0 ,0
Exp/Cntr=0.3,0.1

Type RM Length L Ch R = 1 ,12279   ,81,81,81
BEGIN DESCRIPTION:
CCLC 015 22.0
END DESCRIPTION:
XS GIS Cut Line= 3
      3756817.85     10123011.07      3756616.44     10123297.68
      3756317.86     10123911.06
#Sta/Elev= 30
  4649.7  296.74  4663.2  296.26  4671.9  295.04    4678  295.26  4692.8  293.13
  4707.6  292.19  4764.3  290.48  4820.9  286.55  4850.5  285.26  4865.4  282.93
  4886.3  281.88  4936.8  281.47    4941  281.32  4941.3  280.82  4979.7  282.19
  5008.8  281.89    5082  283.91  5159.5   281.6  5234.2   281.8  5279.3  282.66
  5307.4  282.32    5330  282.59  5337.4  283.65  5369.5  287.48  5448.7  288.67
  5532.9   292.5    5561  292.76  5637.7  297.77    5660  298.13  5682.2   299.6
#Mann= 3 , 0 , 0
  4649.7     .11       0  4865.4     .09       0  5337.4     .11       0
Bank Sta=4865.4,5337.4
XS Rating Curve= 0 ,0
Exp/Cntr=0.3,0.1

Type RM Length L Ch R = 1 ,12198   ,76,76,76
BEGIN DESCRIPTION:
Mapping XS bffc8574
END DESCRIPTION:
XS GIS Cut Line= 2
       3756752.6     10123003.26      3756203.17     10123849.55
#Sta/Elev= 30
  4616.4  296.25  4727.1  289.84 4756.74287.5366  4776.2  285.95  4811.9287.5375
  4841.3  289.58  4965.2  290.08  4980.3     289  4986.3   290.1  5001.4  287.49
  5007.4  289.95  5016.6   288.1  5022.1  289.85  5037.7  288.36  5043.6  290.45
  5052.8  289.34  5070.1  289.86  5073.9  289.04  5079.9  290.71    5095  291.06
  5110.2  289.64  5116.1  290.59  5214.7  289.46  5327.7  288.61  5354.7  286.72
  5376.8  288.22  5406.1  287.57    5508  291.08  5579.5  295.75  5625.4  297.26
#Mann= 7 ,-1 , 0
  4616.4     .11       0  4727.1     .15       0 4756.74     .09       0
  4811.9     .15       0  5022.1     .11       0  5070.1     .15       0
  5214.7     .11       0
Bank Sta=4756.74,4811.9
XS Rating Curve= 0 ,0
Exp/Cntr=0.3,0.1

Type RM Length L Ch R = 1 ,12122   ,241,241,241
BEGIN DESCRIPTION:
Mapping XS 11785450
END DESCRIPTION:
XS GIS Cut Line= 2
      3756656.29     10123026.63      3756229.62     10123666.65
#Sta/Elev= 30
    4672  292.29  4751.8  287.78  4788.9  284.75    4804  285.21    4810  283.81
    4825  282.43    4846  282.02  4876.1  279.61  4912.1  278.33  4918.1  279.12
  4948.2  278.34  4963.2  277.29  4969.2  275.45  4984.2  274.61 4985.43273.7449
  4990.2  270.39  4999.3  270.68  5003.5   269.4    5007   269.4  5013.9  272.39
  5020.3  273.65  5026.3     273 5029.91273.7461  5041.3  277.37  5107.4   276.3
  5215.6  279.42  5221.6   278.7  5329.8  282.97  5386.9  287.38  5441.2  288.92
#Mann= 4 ,-1 , 0
    4672     .11       0  4751.8     .15       0 4985.43     .07       0
 5029.91     .11       0
Bank Sta=4985.43,5029.91
XS Rating Curve= 0 ,0
Exp/Cntr=0.3,0.1

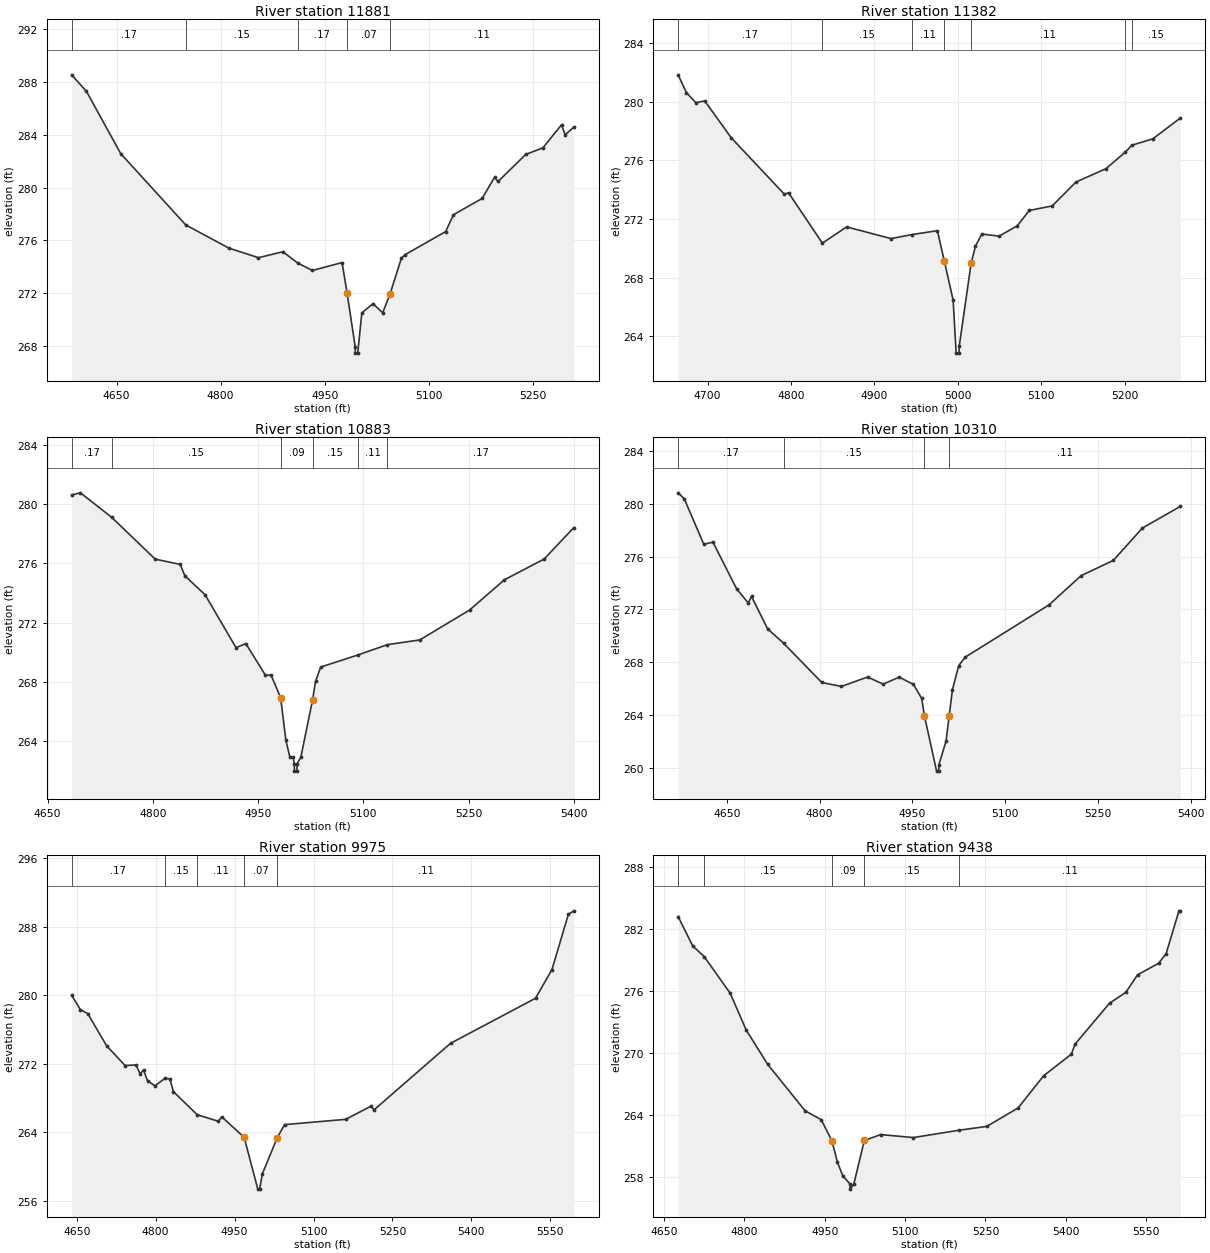
Type RM Length L Ch R = 1 ,11881   ,499,499,499
BEGIN DESCRIPTION:
CCLC 015 21.0
END DESCRIPTION:
XS GIS Cut Line= 3
      3756517.88     10122961.04       3756239.6     10123281.88
      3756148.82     10123567.18
#Sta/Elev= 30
  4585.2  288.55  4606.6  287.29    4656  282.57  4749.6  277.17  4811.7  275.41
  4854.5  274.68  4889.7  275.13    4911  274.28  4932.3  273.71  4975.1  274.31
  4982.4  271.98    4994  267.94  4994.2  267.44  4997.7  267.44  5003.6  270.49
  5019.6  271.19  5033.7   270.5 5044.44271.9504  5060.7  274.65    5066  274.91
  5124.5  276.66  5135.7  277.94    5177  279.17  5194.9  280.77  5200.1  280.46
  5239.9  282.51  5264.6  283.01  5291.6  284.76  5296.8     284  5309.3  284.59
#Mann= 5 ,-1 , 0
  4585.2     .17       0  4749.6     .15       0    4911     .17       0
  4982.4     .07       0 5044.44     .11       0
Bank Sta=4982.4,5044.44
XS Rating Curve= 0 ,0
Exp/Cntr=0.3,0.1

Type RM Length L Ch R = 1 ,11382   ,499,499,499
BEGIN DESCRIPTION:
CCLC 015 20.0
END DESCRIPTION:
XS GIS Cut Line= 3
      3756317.88     10122811.06      3756002.66     10122925.37
      3755802.46     10123101.88
#Sta/Elev= 30
  4664.7  281.84  4674.7  280.62    4686  279.94  4696.6  280.06  4728.5  277.54
  4791.9  273.71  4797.2  273.79  4837.7  270.36  4866.8  271.47    4920  270.67
  4945.5  270.95  4975.6  271.21  4983.8  269.17  4994.5  266.47  4998.1  262.86
  5001.6  262.86  5001.9  263.36 5016.13269.0179  5021.3  270.16  5028.9  270.98
  5049.7  270.84  5071.5  271.55  5085.8  272.59  5113.3   272.9  5141.8  274.53
  5177.8  275.44  5200.9  276.57  5208.8  277.04  5233.8  277.47  5266.9  278.89
#Mann= 7 ,-1 , 0
  4664.7     .17       0  4837.7     .15       0  4945.5     .11       0
  4983.8     .07       0 5016.13     .11       0  5200.9     .17       0
  5208.8     .15       0
Bank Sta=4983.8,5016.13
XS Rating Curve= 0 ,0
Exp/Cntr=0.3,0.1

Type RM Length L Ch R = 1 ,10883   ,573,573,573
BEGIN DESCRIPTION:
CCLC 015 19.0
END DESCRIPTION:
XS GIS Cut Line= 3
      3756197.96     10122484.98      3755943.45     10122671.59
      3755667.84     10122961.08
#Sta/Elev= 30
  4684.4  280.61  4696.9  280.75  4741.4   279.1  4803.5  276.28    4839  275.93
  4845.7  275.16  4874.5  273.88  4918.5  270.32  4932.5  270.59  4960.2  268.48
  4968.6  268.45  4982.1  266.94  4989.5  264.09  4995.3  262.93    5000  262.93
  5001.5   262.5  5001.8     262  5005.3     262  5005.5   262.5  5010.8  262.92
 5027.57266.8016  5031.8  268.04  5039.1  269.01  5091.7  269.82  5134.1  270.52
  5180.3  270.84  5251.1  272.85  5300.8  274.89  5357.4  276.29  5399.7  278.41
#Mann= 6 ,-1 , 0
  4684.4     .17       0  4741.4     .15       0  4982.1     .09       0
 5027.57     .15       0  5091.7     .11       0  5134.1     .17       0
Bank Sta=4982.1,5027.57
XS Rating Curve= 0 ,0
Exp/Cntr=0.3,0.1

Type RM Length L Ch R = 1 ,10310   ,335,335,335
BEGIN DESCRIPTION:
CCLC 015 18.0
END DESCRIPTION:
XS GIS Cut Line= 3
      3755710.94     10122091.82      3755572.93     10122490.21
      3755466.17     10122865.19
#Sta/Elev= 30
  4571.4  280.84  4581.2   280.4  4612.9  276.94  4627.7   277.1  4665.9  273.56
  4684.7  272.49    4690  272.98  4715.9  270.53  4741.9  269.43  4803.4  266.46
  4835.2  266.15  4877.5  266.87  4902.8  266.33  4928.7  266.86  4951.6  266.31
  4965.1  265.24 4969.31263.9442  4989.1  259.73  4992.6  259.73  4992.8  260.23
  5004.3  261.99 5009.38263.9047  5014.7  265.91  5024.9  267.74  5035.5  268.38
  5170.7  272.34  5222.7  274.56  5274.6  275.71  5321.7  278.17  5382.9  279.81
#Mann= 4 ,-1 , 0
  4571.4     .17       0  4741.9     .15       0 4969.31     .07       0
 5009.38     .11       0
Bank Sta=4969.31,5009.38
XS Rating Curve= 0 ,0
Exp/Cntr=0.3,0.1

Type RM Length L Ch R = 1 ,9975    ,537,537,537
BEGIN DESCRIPTION:
CCLC 015 17.0
END DESCRIPTION:
XS GIS Cut Line= 3
       3755552.1     10122031.88      3755312.52      10122294.9
      3755117.85     10122861.09
#Sta/Elev= 30
  4640.3  280.01  4656.8  278.34    4671  277.85  4706.8   274.1  4741.9  271.79
  4762.8  271.86  4770.3  270.82    4777  271.26  4784.5  270.02  4798.6  269.41
  4817.3  270.28    4827  270.23  4833.8  268.73    4879  266.04  4918.9  265.28
  4925.7  265.79  4968.2  263.39  4994.1  257.34  4997.6  257.34  5002.6   259.1
  5030.9263.3348  5044.9  264.88  5161.2   265.5  5209.6  267.05  5214.9   266.6
  5360.5  274.39    5522  279.66  5553.2  283.01  5584.4  289.47  5594.8  289.88
#Mann= 5 ,-1 , 0
  4640.3     .17       0  4817.3     .15       0    4879     .11       0
  4968.2     .07       0  5030.9     .11       0
Bank Sta=4968.2,5030.9
XS Rating Curve= 0 ,0
Exp/Cntr=0.3,0.1

Type RM Length L Ch R = 1 ,9438    ,559,559,559
BEGIN DESCRIPTION:
CCLC 015 16.0
END DESCRIPTION:
XS GIS Cut Line= 3
       3754955.4     10121883.95      3754957.55     10122207.44
      3755067.85     10122811.04
#Sta/Elev= 30
  4676.5  283.24  4703.6   280.4  4725.3  279.34  4773.6  275.81  4803.6  272.23
  4843.6  268.91  4913.6   264.4  4943.6  263.54  4963.6  261.48  4973.6  259.45
  4983.6  258.12  4997.3  257.31  4997.6  256.81  5004.4  257.31    5024  261.53
  5054.5   262.1  5115.5  261.81  5200.8  262.52  5252.4  262.89  5310.7  264.67
  5358.8  267.81  5410.3  269.89  5417.2  270.87  5481.5  274.83    5512  275.89
  5533.8  277.59    5573   278.7    5587  279.62  5611.1  283.79  5613.6  283.79
#Mann= 5 ,-1 , 0
  4676.5     .17       0  4725.3     .15       0  4963.6     .09       0
    5024     .15       0  5200.8     .11       0
Bank Sta=4963.6,5024
XS Rating Curve= 0 ,0
Exp/Cntr=0.3,0.1

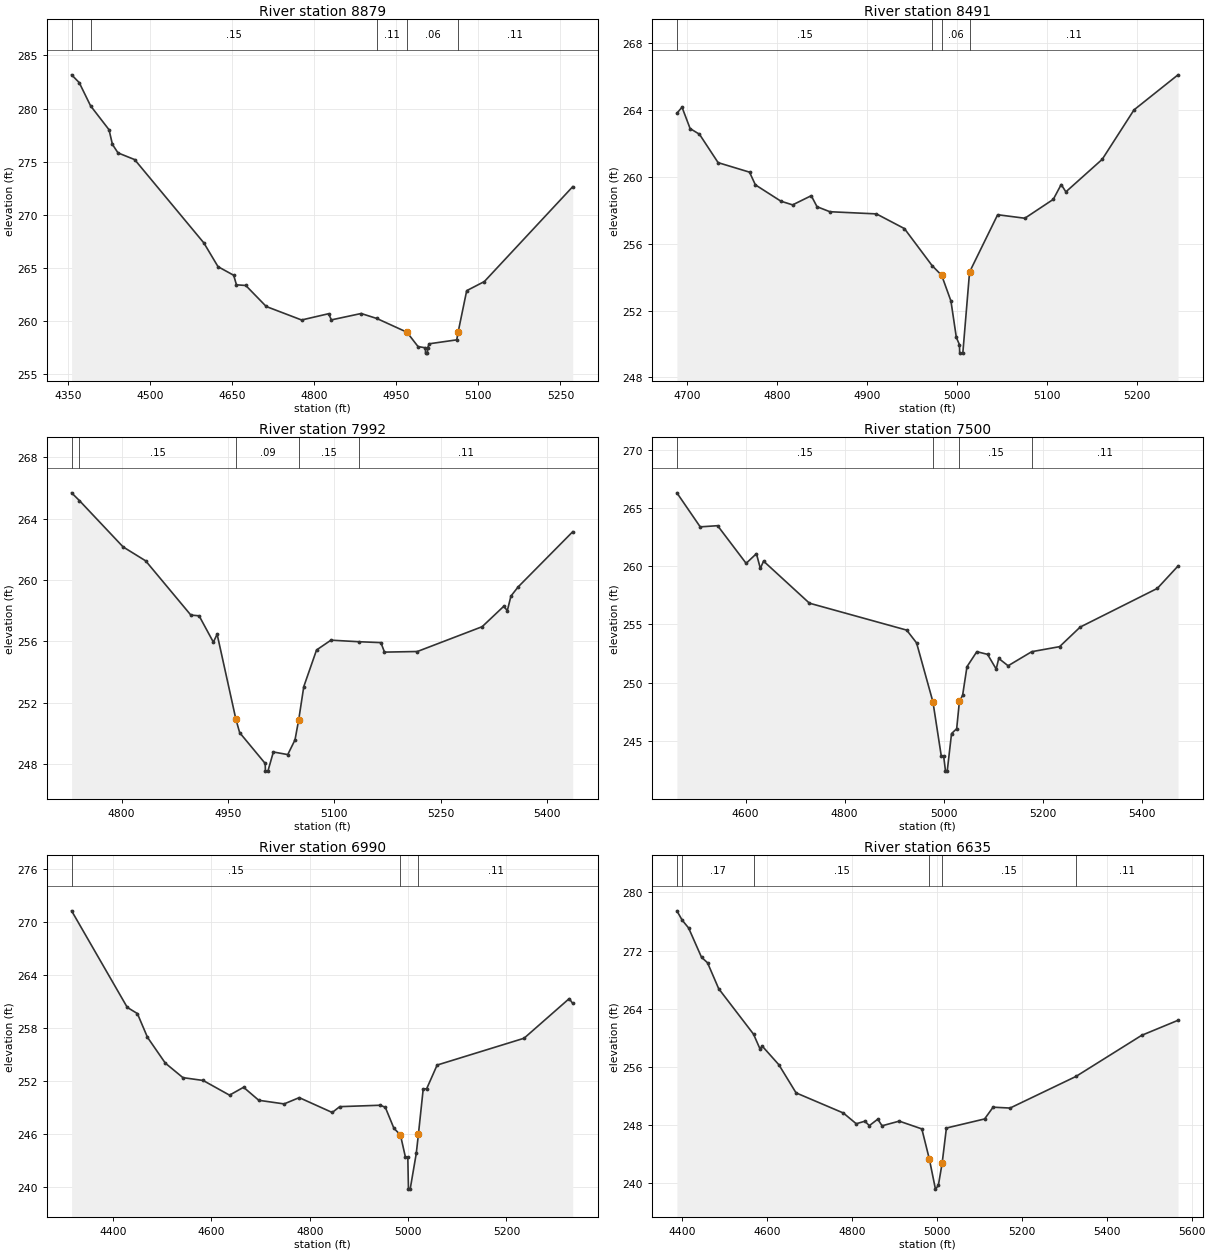
Type RM Length L Ch R = 1 ,8879    ,388,388,388
BEGIN DESCRIPTION:
CCLC 015 15.0
END DESCRIPTION:
XS GIS Cut Line= 3
      3754764.42     10121807.58      3754653.31     10122442.99
      3754617.85     10122711.11
#Sta/Elev= 30
    4357  283.18  4370.9  282.45  4391.7  280.26  4425.4  278.01  4431.6  276.63
  4441.8  275.83  4472.2   275.2  4598.7  267.35  4624.5  265.12  4653.1  264.31
  4658.2  263.41  4675.2  263.35  4712.6  261.37  4777.2   260.1  4826.5  260.69
  4831.6  260.11    4886  260.71  4914.7  260.24  4969.6  258.95  4989.9   257.6
  5003.4  257.48  5003.6  256.98  5007.1  256.98  5007.4  257.48  5010.4  257.86
  5060.6  258.23 5063.06258.9339  5078.8  262.86  5111.1  263.72  5272.5  272.65
#Mann= 5 ,-1 , 0
    4357     .17       0  4391.7     .15       0  4914.7     .11       0
  4969.6     .06       0 5063.06     .11       0
Bank Sta=4969.6,5063.06
XS Rating Curve= 0 ,0
Exp/Cntr=0.3,0.1

Type RM Length L Ch R = 1 ,8491    ,499,499,499
BEGIN DESCRIPTION:
CCLC 015 14.0
END DESCRIPTION:
XS GIS Cut Line= 3
      3754403.33     10121956.84      3754323.01      10122257.6
      3754260.94     10122495.12
#Sta/Elev= 30
  4688.7  263.82  4694.4  264.18  4703.4   262.9  4713.8  262.56  4734.5  260.86
  4769.4  260.29  4775.9  259.53  4804.3  258.55  4817.3  258.33    4838  258.88
  4844.4  258.22  4858.7  257.92  4910.4  257.79  4941.5  256.91  4972.3  254.69
  4982.9  254.11  4993.2  252.57  4999.2  250.39  5002.7  249.95  5002.9  249.45
  5006.4  249.45  5013.9  254.31  5045.1  257.74  5075.3  257.53  5106.9  258.66
  5115.7  259.55  5120.9  259.11  5161.3  261.06  5196.6  264.02  5245.5  266.12
#Mann= 4 ,-1 , 0
  4688.7     .15       0  4972.3     .11       0  4982.9     .06       0
  5013.9     .11       0
Bank Sta=4982.9,5013.9
XS Rating Curve= 0 ,0
Exp/Cntr=0.3,0.1

Type RM Length L Ch R = 1 ,7992    ,492,492,492
BEGIN DESCRIPTION:
CCLC 015 13.0
END DESCRIPTION:
XS GIS Cut Line= 3
      3754066.49     10121790.26      3753982.17     10122047.39
      3753906.94     10122476.85
#Sta/Elev= 30
  4729.4  265.69  4740.5  265.18    4802  262.16  4833.8  261.25  4897.5  257.71
  4909.2  257.66  4929.3  255.94  4934.6  256.46  4961.1   250.9  4966.4  250.03
  5002.4  248.02  5002.7  247.52  5006.2  247.52  5013.9  248.77  5034.2   248.6
  5044.4  249.56 5049.64250.8736  5056.8  253.04  5074.8  255.43  5095.1  256.07
    5134  255.97  5165.5  255.91  5170.6  255.29  5216.9  255.33  5308.3  256.95
  5338.7  258.28  5343.8     258  5348.9  258.95  5359.1  259.55    5436  263.15
#Mann= 5 ,-1 , 0
  4729.4     .17       0  4740.5     .15       0  4961.1     .09       0
 5049.64     .15       0    5134     .11       0
Bank Sta=4961.1,5049.64
XS Rating Curve= 0 ,0
Exp/Cntr=0.3,0.1

Type RM Length L Ch R = 1 ,7500    ,510,510,510
BEGIN DESCRIPTION:
CCLC 015 12.0
END DESCRIPTION:
XS GIS Cut Line= 4
        3753254.     10121498.54      3753514.11     10121821.44
      3753513.32     10121945.71      3753642.87     10122401.24
#Sta/Elev= 30
  4461.1  266.29  4508.2  263.37  4543.4  263.47    4601  260.24  4621.8  261.07
  4629.7   259.8  4636.2  260.43  4728.9  256.82  4925.4  254.51  4945.4  253.41
 4978.47248.3445  4995.2  243.73    5000  243.73  5003.8  242.41  5007.3  242.41
    5016  245.63  5026.4  246.05 5031.91248.3918  5038.4  248.92  5047.2  251.37
  5067.1  252.66  5088.8  252.43  5106.2  251.17  5111.4  252.08  5130.3  251.45
  5178.1  252.66  5234.3  253.09  5275.9  254.77  5431.8  258.09  5473.6  260.01
#Mann= 4 ,-1 , 0
  4461.1     .15       0 4978.47     .09       0 5031.91     .15       0
  5178.1     .11       0
Bank Sta=4978.47,5031.91
XS Rating Curve= 0 ,0
Exp/Cntr=0.3,0.1

Type RM Length L Ch R = 1 ,6990    ,355,355,355
BEGIN DESCRIPTION:
CCLC 015 11.0
END DESCRIPTION:
XS GIS Cut Line= 3
      3752967.86     10121511.09      3753129.01     10122175.63
      3753367.86     10122411.08
#Sta/Elev= 30
  4315.5  271.25  4428.7  260.34  4449.3  259.64  4469.8  256.96  4506.1  254.04
  4541.9   252.4    4583  252.08  4636.7  250.42  4665.3  251.31  4696.2  249.84
  4747.7  249.43  4778.5  250.14  4845.6  248.46  4860.8  249.12  4943.2  249.28
  4953.5  249.05    4971  246.68  4984.3  245.92  4994.4  243.43  4999.3  243.43
  5000.6   239.8  5004.1   239.8  5016.5  243.83 5020.95246.0488  5030.6   251.1
  5037.7  251.15  5058.9  253.82  5235.7  256.85  5327.6  261.33  5334.7  260.78
#Mann= 3 , 0 , 0
  4315.5     .15       0  4984.3     .09       0 5020.95     .11       0
Bank Sta=4984.3,5020.95
XS Rating Curve= 0 ,0
Exp/Cntr=0.3,0.1

Type RM Length L Ch R = 1 ,6635    ,710,710,710
BEGIN DESCRIPTION:
CCLC 015 10.0
END DESCRIPTION:
XS GIS Cut Line= 3
      3752924.15      10121463.8      3752826.93     10122067.99
      3752826.93     10122636.73
#Sta/Elev= 30
  4387.2  277.47  4399.6  276.19  4414.8  275.11  4445.2  271.08  4459.4  270.32
  4485.7  266.75  4567.8  260.49  4583.1  258.45  4588.1  258.86  4627.5  256.28
    4668  252.41  4779.4  249.64  4809.8  248.16  4830.1  248.51  4840.6   247.9
  4860.5  248.79  4870.6  247.88  4911.1  248.52  4964.3  247.45    4982   243.3
  4996.4  239.16  5003.2  239.66  5012.2  242.75  5022.2  247.57  5112.2  248.82
  5132.2  250.44  5172.2  250.32  5327.4  254.67  5482.2  260.33  5567.9   262.4
#Mann= 6 ,-1 , 0
  4387.2     .15       0  4399.6     .17       0  4567.8     .15       0
    4982     .09       0  5012.2     .15       0  5327.4     .11       0
Bank Sta=4982,5012.2
XS Rating Curve= 0 ,0
Exp/Cntr=0.3,0.1