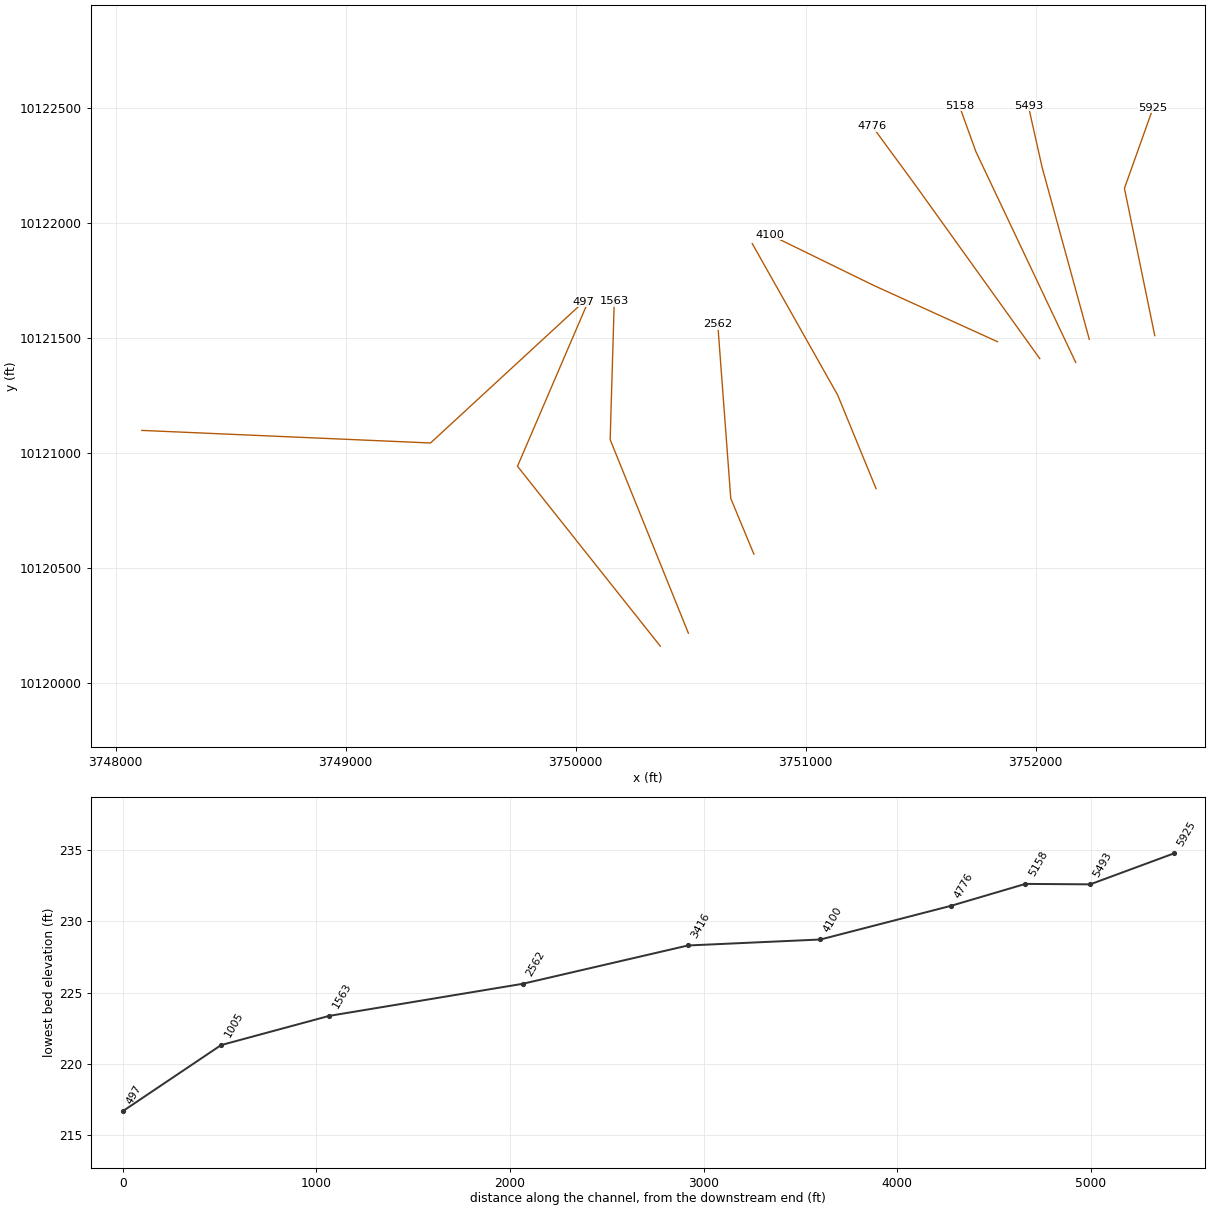
HEC-RAS study CCLC 015.prj: CCLC 015 Base Level Engineering

--- CCLC 015.g01 (geometry) --- (continued)

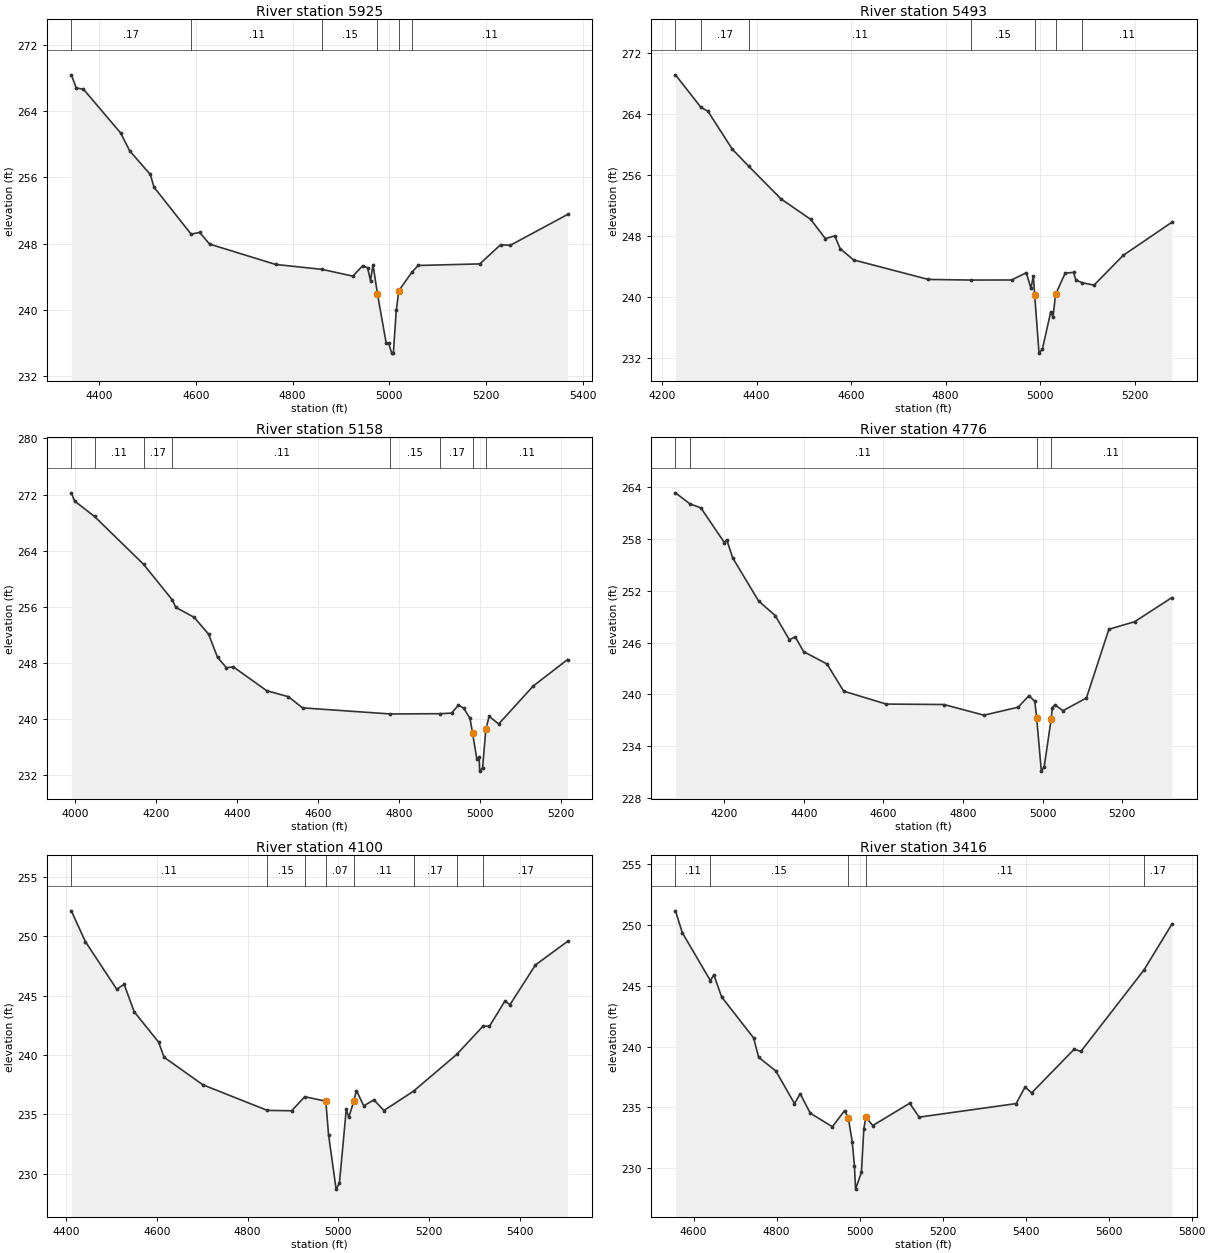
Type RM Length L Ch R = 1 ,5925    ,432,432,432
BEGIN DESCRIPTION:
CCLC 015 9.0
END DESCRIPTION:
XS GIS Cut Line= 3
      3752517.85     10121511.09      3752385.95     10122151.32
      3752510.96     10122502.03
#Sta/Elev= 30
  4342.4  268.38  4352.6  266.79  4367.5  266.64  4444.5  261.34    4463   259.2
  4505.7  256.34  4513.3  254.81  4589.9  249.14  4607.8  249.34  4628.3  247.93
  4764.9  245.47  4860.7  244.88  4924.4  244.06  4944.8  245.32    4955  245.07
    4961  243.51  4966.1  245.45  4975.4  241.89  4993.4  235.96  4998.6  235.96
  5004.7  234.76  5008.2  234.76  5014.2  239.92  5019.5  242.31  5046.5  244.53
  5059.5  245.35  5186.9  245.54  5229.9  247.85  5250.1  247.79  5368.4  251.51
#Mann= 6 ,-1 , 0
  4342.4     .17       0  4589.9     .11       0  4860.7     .15       0
  4975.4     .09       0  5019.5     .15       0  5046.5     .11       0
Bank Sta=4975.4,5019.5
XS Rating Curve= 0 ,0
Exp/Cntr=0.3,0.1

Type RM Length L Ch R = 1 ,5493    ,335,335,335
BEGIN DESCRIPTION:
CCLC 015 8.0
END DESCRIPTION:
XS GIS Cut Line= 3
      3752233.19     10121495.04      3752028.31      10122241.6
      3751967.86     10122511.04
#Sta/Elev= 30
  4228.2  269.15  4282.3  264.86  4296.7  264.38  4348.5  259.38  4383.2  257.14
  4451.6  252.85  4514.4  250.16  4545.5  247.63  4565.3     248  4576.7  246.32
    4605  244.84  4763.5  242.27  4853.9  242.19  4939.6   242.2  4970.7  243.15
  4980.6  241.11  4985.7  242.75  4988.5  240.21  4997.7  232.59  5004.7  233.09
  5022.3  237.96  5027.4  237.35  5032.6   240.3  5053.1  243.11  5070.7  243.19
  5075.8  242.19  5088.6  241.85  5114.1  241.52    5176  245.44  5278.5  249.77
#Mann= 7 ,-1 , 0
  4228.2     .11       0  4282.3     .17       0  4383.2     .11       0
  4853.9     .15       0  4988.5     .09       0  5032.6     .17       0
  5088.6     .11       0
Bank Sta=4988.5,5032.6
XS Rating Curve= 0 ,0
Exp/Cntr=0.3,0.1

Type RM Length L Ch R = 1 ,5158    ,382,382,382
BEGIN DESCRIPTION:
CCLC 015 7.0
END DESCRIPTION:
XS GIS Cut Line= 3
      3752174.13     10121394.42      3751740.12     10122311.05
      3751667.84     10122511.11
#Sta/Elev= 30
  3990.4  272.25  3998.3  271.09  4047.8  268.88  4169.2  262.06  4240.3  256.98
  4248.6  255.94  4294.1  254.52  4329.7  252.13  4351.8  248.83  4373.9  247.34
  4390.6  247.48  4473.5  244.07  4527.1  243.22    4562  241.63  4779.4  240.76
  4902.4   240.8  4930.4  240.88  4947.6  242.03  4960.3   241.6  4975.9  240.16
  4982.5  238.04  4993.1  234.31  4998.6  234.57    5000  232.62  5007.3  233.12
  5015.2  238.56  5023.3  240.41  5047.1  239.34  5132.2  244.73  5217.3  248.51
#Mann= 8 ,-1 , 0
  3990.4     .17       0  4047.8     .11       0  4169.2     .17       0
  4240.3     .11       0  4779.4     .15       0  4902.4     .17       0
  4982.5     .09       0  5015.2     .11       0
Bank Sta=4982.5,5015.2
XS Rating Curve= 0 ,0
Exp/Cntr=0.3,0.1

Type RM Length L Ch R = 1 ,4776    ,676,676,676
BEGIN DESCRIPTION:
CCLC 015 6.0
END DESCRIPTION:
XS GIS Cut Line= 3
      3752017.84     10121411.09       3751479.7     10122161.74
       3751288.7      10122422.2
#Sta/Elev= 30
  4077.9  263.38  4113.9  262.11  4141.8  261.63  4200.7  257.61  4206.8  257.92
  4221.6  255.84  4286.7  250.83  4328.4  249.14  4364.1  246.33  4378.8  246.67
  4399.7  244.96  4458.6  243.52  4500.4  240.37  4607.2  238.87  4752.1  238.82
  4852.8  237.58  4938.8  238.51  4965.9  239.85  4980.6  239.18 4985.42237.2211
    4997  231.09  5004.2  231.59 5021.69237.1174  5024.7  238.41  5030.9  238.78
  5051.7  238.11  5110.3  239.58  5166.7  247.55  5231.5  248.43  5324.5  251.21
#Mann= 4 ,-1 , 0
  4077.9     .17       0  4113.9     .11       0 4985.42     .07       0
 5021.69     .11       0
Bank Sta=4985.42,5021.69
XS Rating Curve= 0 ,0
Exp/Cntr=0.3,0.1

Type RM Length L Ch R = 1 ,4100    ,684,684,684
BEGIN DESCRIPTION:
CCLC 015 5.0
END DESCRIPTION:
XS GIS Cut Line= 3
      3751833.84     10121484.67      3751299.15     10121727.71
      3750844.27     10121949.94
#Sta/Elev= 30
  4411.6  252.12  4442.4  249.54  4511.6  245.53    4528  245.94    4550  243.64
  4603.9  241.08  4615.9  239.81  4701.6  237.49  4843.5  235.34  4897.2  235.31
  4925.9  236.49 4972.42236.1152  4978.4   233.3  4995.1  228.72  5002.4  229.22
  5017.5  235.43  5023.1  234.75  5033.8  236.11    5040  237.01    5056  235.72
  5078.3  236.23  5100.5  235.33  5165.8  236.96  5260.7  240.04  5319.3  242.44
  5332.8   242.4  5367.7  244.57  5377.9  244.21  5434.4  247.57  5505.2  249.55
#Mann= 8 ,-1 , 0
  4411.6     .11       0  4843.5     .15       0  4925.9     .11       0
 4972.42     .07       0  5033.8     .11       0  5165.8     .17       0
  5260.7     .11       0  5319.3     .17       0
Bank Sta=4972.42,5033.8
XS Rating Curve= 0 ,0
Exp/Cntr=0.3,0.1

Type RM Length L Ch R = 1 ,3416    ,854,854,854
BEGIN DESCRIPTION:
CCLC 015 4.0
END DESCRIPTION:
XS GIS Cut Line= 3
      3751306.08      10120845.8      3751139.43     10121252.02
      3750767.83     10121911.11
#Sta/Elev= 30
  4556.2  251.14  4572.7  249.34  4640.2  245.42  4648.8  245.89  4667.3  244.08
  4744.7   240.7  4756.5  239.12  4798.1     238  4842.9  235.32  4856.8  236.13
  4880.8  234.54  4934.2  233.42  4963.6  234.74  4972.6  234.15  4982.1   232.2
  4987.5  230.17  4990.1   228.3  5004.3  229.69    5010  233.24 5014.94234.1932
  5031.7  233.52  5120.5  235.35  5143.4  234.21    5377  235.32  5398.6  236.68
  5414.5   236.2  5517.1  239.79    5533   239.6    5685  246.28  5751.9  250.02
#Mann= 5 ,-1 , 0
  4556.2     .11       0  4640.2     .15       0  4972.6     .06       0
 5014.94     .11       0    5685     .17       0
Bank Sta=4972.6,5014.94
XS Rating Curve= 0 ,0
Exp/Cntr=0.3,0.1

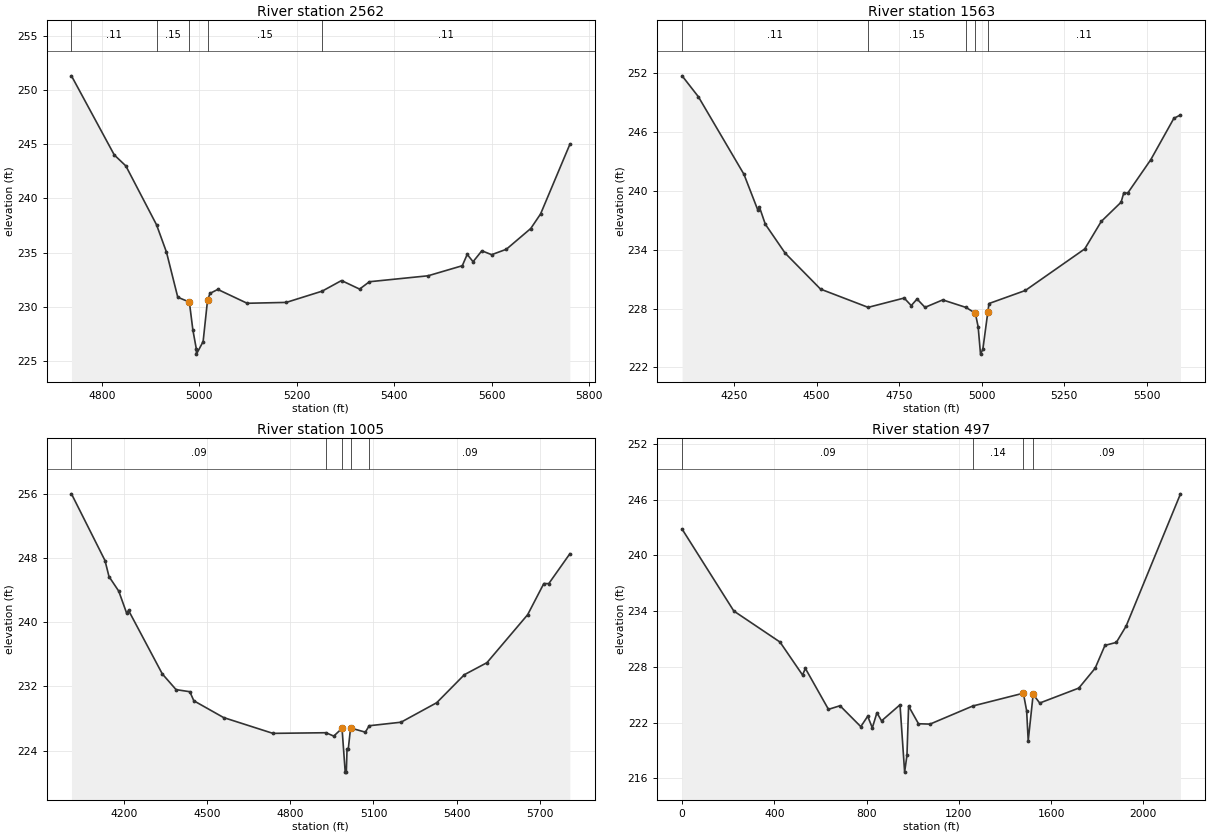
Type RM Length L Ch R = 1 ,2562    ,999,999,999
BEGIN DESCRIPTION:
CCLC 015 3.0
END DESCRIPTION:
XS GIS Cut Line= 3
      3750774.84     10120561.05       3750674.4     10120803.14
      3750617.85     10121561.04
#Sta/Elev= 30
  4737.9  251.33  4825.7  244.02  4849.5     243  4912.4  237.56  4932.8  235.03
  4955.9  230.87  4979.7  230.42  4986.9  227.84  4993.9  226.11  4994.2  225.61
  5007.9  226.77  5016.9  230.57  5021.9  231.22    5038  231.59  5098.2  230.31
  5178.4  230.39    5252  231.43  5291.7  232.41  5328.8  231.62  5348.9   232.3
  5469.2  232.85  5539.4  233.78  5549.5  234.83  5561.5  234.15  5579.5  235.16
  5599.6   234.8  5629.7   235.3  5679.8  237.22  5699.9  238.56    5760     245
#Mann= 5 ,-1 , 0
  4737.9     .11       0  4912.4     .15       0  4979.7     .09       0
  5016.9     .15       0    5252     .11       0
Bank Sta=4979.7,5016.9
XS Rating Curve= 0 ,0
Exp/Cntr=0.3,0.1

Type RM Length L Ch R = 1 ,1563    ,558,558,558
BEGIN DESCRIPTION:
CCLC 015 2.0
END DESCRIPTION:
XS GIS Cut Line= 3
      3750490.11     10120217.33      3750149.99      10121058.9
      3750167.85     10121661.03
#Sta/Elev= 30
  4092.3  251.74  4141.6  249.61  4279.7   241.7  4321.3  238.09  4326.7  238.35
  4344.4  236.61  4404.5  233.66  4511.8  229.99    4656  228.13  4765.1  229.08
  4786.6  228.31  4804.2  228.98  4828.3  228.13    4882  228.89  4952.7  228.12
  4980.8  227.53  4989.3  226.15  4996.5  223.36  5003.6  223.86 5018.58227.6403
  5022.2  228.52  5132.2  229.85  5312.3  234.09  5362.3  236.89  5422.4  238.85
  5430.6  239.81  5442.4  239.78  5512.4  243.19  5582.4  247.41  5602.4  247.75
#Mann= 5 ,-1 , 0
  4092.3     .11       0    4656     .15       0  4952.7     .11       0
  4980.8     .06       0 5018.58     .11       0
Bank Sta=4980.8,5018.58
XS Rating Curve= 0 ,0
Exp/Cntr=0.3,0.1

Type RM Length L Ch R = 1 ,1005    ,508,508,508
BEGIN DESCRIPTION:
CCLC 015 1.0
END DESCRIPTION:
XS GIS Cut Line= 3
      3750367.84     10120161.09      3749747.06     10120942.99
      3750062.28     10121677.34
#Sta/Elev= 30
  4010.9  255.99  4131.8  247.68  4146.3  245.68  4181.5  243.86  4210.3  241.08
  4216.7  241.47  4338.5  233.55  4388.2  231.59  4437.8  231.33  4452.3   230.2
  4559.6  228.11  4737.5  226.14  4928.8  226.22  4956.9   225.8 4986.74226.7669
  4998.2  221.31  5002.2  221.31  5004.8  224.21  5009.3  224.21  5017.5226.8098
  5070.8  226.29  5084.7  227.09  5199.5  227.53  5328.2  229.96  5427.9  233.45
  5509.4  234.95  5656.2  240.93  5714.5  244.81  5732.3   244.8  5808.4  248.52
#Mann= 5 ,-1 , 0
  4010.9     .09       0  4928.8     .14       0 4986.74     .06       0
  5017.5     .14       0  5084.7     .09       0
Bank Sta=4986.74,5017.5
XS Rating Curve= 0 ,0
Exp/Cntr=0.3,0.1

Type RM Length L Ch R = 1 ,497     ,0,0,0
BEGIN DESCRIPTION:
CCLC 015 0.5
END DESCRIPTION:
XS GIS Cut Line= 3
      3748113.73     10121098.92      3749368.93     10121044.23
       3750035.6     10121658.82
#Sta/Elev= 30
       0  242.84   224.3  234.02   424.5  230.68   522.3  227.13   534.6  227.84
   634.7  223.43   684.8  223.82   774.9  221.57   804.9  222.69   824.9  221.44
   844.9  223.07   864.9  222.19     945  223.92     965  216.67   975.1  218.48
   982.2  223.78  1025.1  221.88  1075.1  221.84  1260.4  223.79  1479.9  225.17
  1494.1  223.28  1500.9  220.05  1522.4  225.04  1550.8  224.11  1720.3  225.72
  1791.2  227.86  1833.7  230.32  1883.1  230.64  1925.6   232.4  2161.3  246.64
#Mann= 4 ,-1 , 0
       0     .09       0  1260.4     .14       0  1479.9     .06       0
  1522.4     .09       0
Bank Sta=1479.9,1522.4
XS Rating Curve= 0 ,0
Exp/Cntr=0.3,0.1

Chan Stop Cuts=-1
Use User Specified Reach Order=0
Composite Channel Slope=5