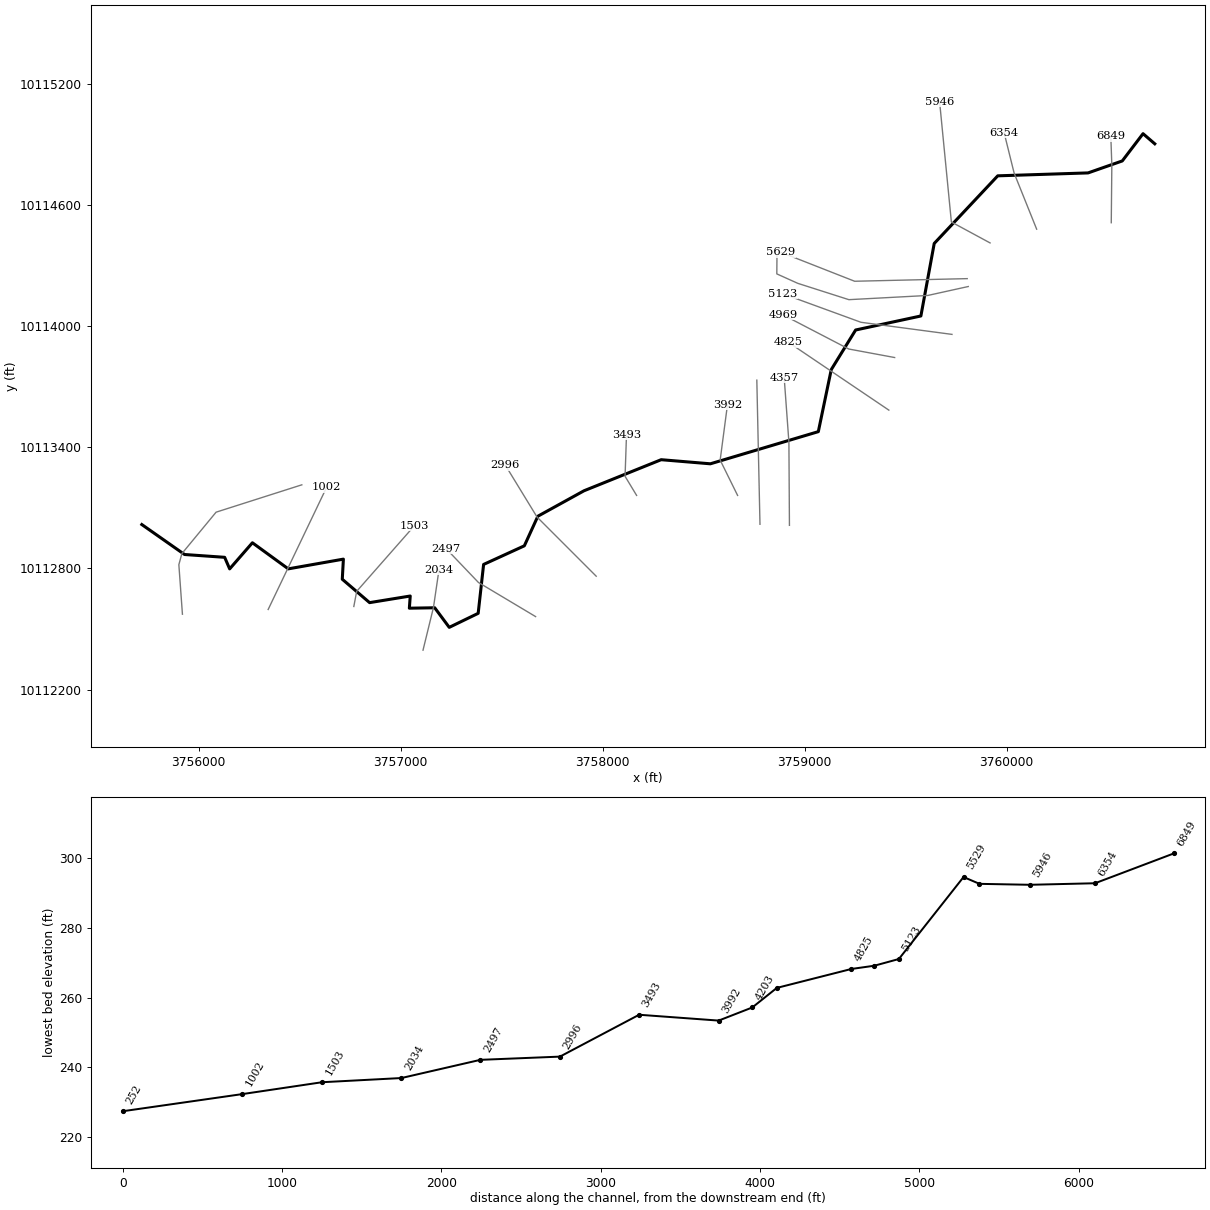
--- CCLC 016.prj (project) ---

Proj Title=CCLC 016 Base Level Engineering
Current Plan=p01
Default Exp/Contr=0.3,0.1
English Units
Geom File=g01
Flow File=f01
Flow File=f02
Plan File=p01
Y Axis Title=Elevation
X Axis Title(PF)=Main Channel Distance
X Axis Title(XS)=Station
BEGIN DESCRIPTION:
CCLC 016
END DESCRIPTION:
DSS Export Rating Curves= 0
DSS Export Rating Curve Sorted= 0
DSS Export Volume Flow Curves= 0
DXF OffsetX= 0
DXF OffsetY= 0
DXF ScaleX= 1
DXF ScaleY= 10

--- CCLC 016.p01 (plan) ---

Plan Title=Multiple Run
Short Identifier=Multiple
Geom File=g01
Flow File=f01
Subcritical Flow
K Sum by GR= 0
Std Step Tol= 0.01
Critical Tol= 0.01
Num of Std Step Trials= 20
Max Error Tol= 0.3
Flow Tol Ratio= 0.001
Split Flow NTrial= 30
Split Flow Tol= 0.02
Split Flow Ratio= 0.02
Log Output Level= 0
Friction Slope Method= 1
Unsteady Friction Slope Method= 2
Unsteady Bridges Friction Slope Method= 1
Parabolic Critical Depth
Global Vel Dist=  1 , 1 , 1
Global Log Level= 0
CheckData=True
Encroach Param= -1, 0, 0, 0
BEGIN DESCRIPTION:
Multiple Run
END DESCRIPTION:

--- CCLC 016.f01 (steady flow) ---

Flow Title=Multiple
Program Version=4.10
Number of Profiles= 7
Profile Names=10-year,25-year,50-year,1pct_min,100-year,1pct_plu,500-year
River Rch & RM=CCLC 016,Reach-1         ,6849
     638     873    1188     533    1609    4859    3050
Boundary for River Rch & Prof#=CCLC 016,Reach-1         , 1
Up Type= 0
Dn Type= 3
Dn Slope=0.005
Boundary for River Rch & Prof#=CCLC 016,Reach-1         , 2
Up Type= 0
Dn Type= 3
Dn Slope=0.005
Boundary for River Rch & Prof#=CCLC 016,Reach-1         , 3
Up Type= 0
Dn Type= 3
Dn Slope=0.005
Boundary for River Rch & Prof#=CCLC 016,Reach-1         , 4
Up Type= 0
Dn Type= 3
Dn Slope=0.005
Boundary for River Rch & Prof#=CCLC 016,Reach-1         , 5
Up Type= 0
Dn Type= 3
Dn Slope=0.005
Boundary for River Rch & Prof#=CCLC 016,Reach-1         , 6
Up Type= 0
Dn Type= 3
Dn Slope=0.005
Boundary for River Rch & Prof#=CCLC 016,Reach-1         , 7
Up Type= 0
Dn Type= 3
Dn Slope=0.005
DSS Import GetInterval= 0
DSS Import GetPeak= 0
DSS Import FillOption= 0

--- CCLC 016.f02 (steady flow) ---

Flow Title=Orig_BLE_Flows
Program Version=4.10
Number of Profiles= 7
Profile Names=10-year,25-year,50-year,1pct_min,100-year,1pct_plu,500-year
River Rch & RM=CCLC 016,Reach-1         ,6849
     638     856    1033     410    1238    3738    1773
Boundary for River Rch & Prof#=CCLC 016,Reach-1         , 1
Up Type= 0
Dn Type= 3
Dn Slope=0.005
Boundary for River Rch & Prof#=CCLC 016,Reach-1         , 2
Up Type= 0
Dn Type= 3
Dn Slope=0.005
Boundary for River Rch & Prof#=CCLC 016,Reach-1         , 3
Up Type= 0
Dn Type= 3
Dn Slope=0.005
Boundary for River Rch & Prof#=CCLC 016,Reach-1         , 4
Up Type= 0
Dn Type= 3
Dn Slope=0.005
Boundary for River Rch & Prof#=CCLC 016,Reach-1         , 5
Up Type= 0
Dn Type= 3
Dn Slope=0.005
Boundary for River Rch & Prof#=CCLC 016,Reach-1         , 6
Up Type= 0
Dn Type= 3
Dn Slope=0.005
Boundary for River Rch & Prof#=CCLC 016,Reach-1         , 7
Up Type= 0
Dn Type= 3
Dn Slope=0.005
DSS Import GetInterval= 0
DSS Import GetPeak= 0
DSS Import FillOption= 0

--- CCLC 016.g01 (geometry) ---

Geom Title=Existing Conditions
Program Version=4.10

River Reach=CCLC 016        ,Reach-1
Reach XY= 30
      3760733.23     10114901.84      3760675.11     10114951.97
      3760572.37     10114816.98      3760403.04     10114757.72
      3759955.84     10114743.29      3759641.33     10114408.43
      3759575.32     10114049.42      3759252.29     10113980.03
      3759131.54     10113783.85      3759067.52     10113476.77
      3758532.98     10113317.57      3758289.53     10113337.88
      3757907.49     10113184.03      3757679.01     10113058.05
       3757612.1     10112911.55      3757410.41     10112819.31
       3757383.5     10112577.25      3757240.27      10112507.8
      3757168.34     10112604.79      3757042.82     10112602.72
      3757047.13     10112662.97      3756845.95     10112630.22
      3756710.72     10112746.04       3756716.2     10112845.58
      3756443.38     10112797.46      3756265.72     10112926.63
      3756153.16      10112797.3      3756128.35      10112854.6
      3755929.93     10112868.49      3755718.23     10113016.84

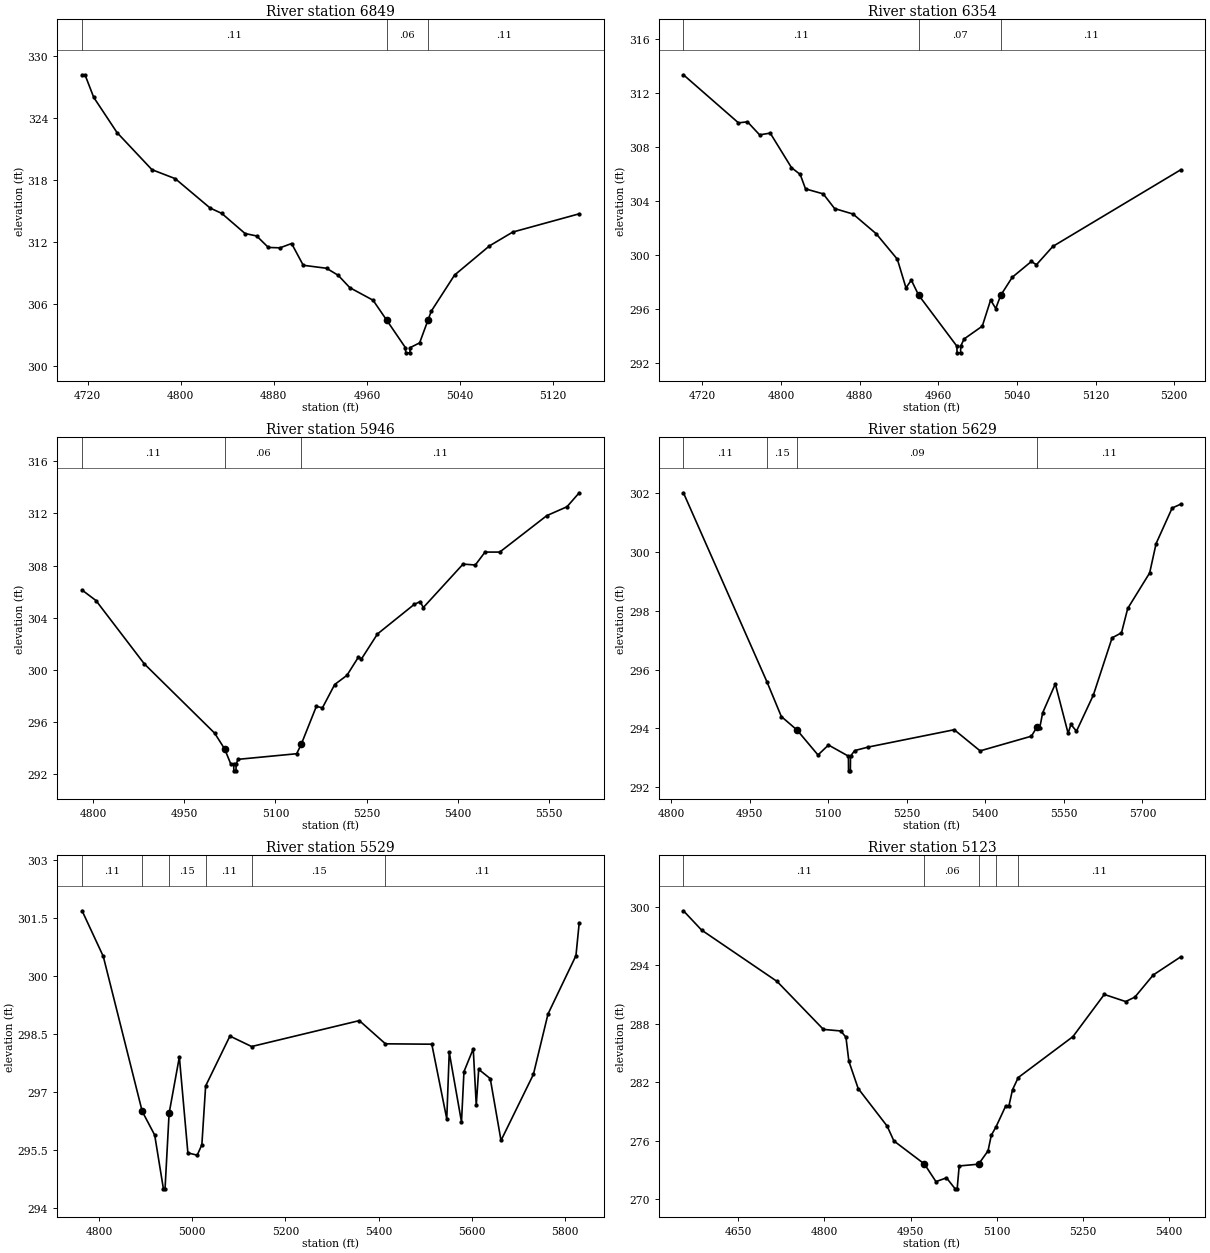
Type RM Length L Ch R = 1 ,6849    ,495,495,495
BEGIN DESCRIPTION:
CCLC 016 13.0
END DESCRIPTION:
XS GIS Cut Line= 3
      3760517.85     10114511.11      3760520.66      10114795.8
      3760515.73     10114938.11
#Sta/Elev= 30
  4715.3  328.22  4717.8  328.22  4725.3  326.03  4745.3  322.62  4775.3  319.02
  4795.3  318.15  4825.3   315.3  4835.3  314.78  4855.3  312.83  4865.3  312.59
  4875.3  311.48  4885.3  311.44  4895.3  311.86  4905.3  309.75  4925.3  309.46
  4935.3  308.78  4945.3  307.58  4965.3  306.36 4976.84304.4543  4993.1  301.76
  4993.4  301.26  4996.9  301.26  4997.1  301.76  5005.3  302.23  5012.6304.4712
  5015.3   305.3  5035.3   308.8  5065.3  311.63  5085.3  312.97  5142.4  314.74
#Mann= 3 , 0 , 0
  4715.3     .11       0 4976.84     .06       0  5012.6     .11       0
Bank Sta=4976.84,5012.6
XS Rating Curve= 0 ,0
Exp/Cntr=0.3,0.1

Type RM Length L Ch R = 1 ,6354    ,408,408,408
BEGIN DESCRIPTION:
CCLC 016 12.0
END DESCRIPTION:
XS GIS Cut Line= 3
      3760148.47     10114479.13      3760036.92     10114756.86
      3759987.29      10114957.2
#Sta/Elev= 30
  4700.7  313.36  4756.7  309.79  4765.8  309.87  4778.2   308.9    4789  309.03
  4810.6  306.47  4819.5  305.96  4824.9  304.89  4842.9  304.52  4854.5  303.43
  4873.3  303.02  4896.8  301.56  4918.3  299.67  4927.1  297.54  4932.5  298.12
  4939.9  297.01  4978.8  293.22  4979.1  292.72  4982.6  292.72  4982.8  293.22
  4986.2  293.75  5004.7   294.7  5013.2  296.64  5018.4  296.01 5023.46296.9909
  5035.2  298.33  5054.6   299.5  5059.8  299.26  5076.5  300.62  5206.4   306.3
#Mann= 3 , 0 , 0
  4700.7     .11       0  4939.9     .07       0 5023.46     .11       0
Bank Sta=4939.9,5023.46
XS Rating Curve= 0 ,0
Exp/Cntr=0.3,0.1

Type RM Length L Ch R = 1 ,5946    ,317,317,317
BEGIN DESCRIPTION:
CCLC 016 11.0
END DESCRIPTION:
XS GIS Cut Line= 3
      3759917.87     10114411.06      3759726.28     10114514.64
      3759667.85     10115111.09
#Sta/Elev= 30
  4782.2  306.12    4805  305.32  4884.5  300.47    5000  295.17  5016.5  293.96
  5026.6   292.8  5031.4  292.78  5031.6  292.28  5035.1  292.28  5035.4  292.78
  5038.4  293.16  5134.9  293.59 5142.47294.3198  5167.2  297.21  5177.3  297.11
  5197.4  298.89  5217.5  299.59  5236.4  300.99  5241.4  300.85  5267.7  302.76
    5328  305.02  5337.9  305.24    5343  304.78  5408.4  308.11  5428.5  308.04
  5444.5  309.03  5468.7  309.03    5546  311.82  5579.2   312.5  5599.3  313.57
#Mann= 3 , 0 , 0
  4782.2     .11       0  5016.5     .06       0 5142.47     .11       0
Bank Sta=5016.5,5142.47
XS Rating Curve= 0 ,0
Exp/Cntr=0.3,0.1

Type RM Length L Ch R = 1 ,5629    ,100,100,100
BEGIN DESCRIPTION:
Mapping XS e599cc53
END DESCRIPTION:
XS GIS Cut Line= 3
      3759804.72     10114234.33      3759247.43     10114221.31
      3758882.89     10114364.52
#Sta/Elev= 30
  4823.7  302.02  4983.2  295.58  5010.6   294.4  5040.6  293.94  5080.6  293.09
  5100.6  293.43  5138.7  293.05  5138.9  292.55  5142.4  292.55  5142.7  293.05
  5150.7  293.24  5176.5  293.36  5340.7  293.95  5390.1  293.23  5488.1  293.73
  5498.5  294.04  5503.9  294.01  5509.6  294.53  5533.7  295.51  5558.1  293.83
  5563.5  294.13  5574.1   293.9  5606.3  295.13  5642.1  297.08    5660  297.25
  5671.9  298.08  5713.8  299.29  5726.1  300.29  5756.7   301.5  5772.8  301.63
#Mann= 4 ,-1 , 0
  4823.7     .11       0  4983.2     .15       0  5040.6     .09       0
  5498.5     .11       0
Bank Sta=5040.6,5498.5
XS Rating Curve= 0 ,0
Exp/Cntr=0.3,0.1

Type RM Length L Ch R = 1 ,5529    ,406,406,406
BEGIN DESCRIPTION:
Mapping XS 8e8d93e5
END DESCRIPTION:
XS GIS Cut Line= 6
      3759809.95     10114195.27      3759609.41       10114151.
      3759218.79     10114130.17      3758966.18      10114210.9
      3758862.02     10114257.77      3758862.82     10114348.07
#Sta/Elev= 30
  4763.6  301.69  4809.1  300.51 4892.58296.5045  4919.4  295.89  4938.1   294.5
  4941.6   294.5  4950.3  296.45  4972.3  297.91  4990.6  295.43  5010.6  295.37
  5020.6  295.64  5028.7  297.16  5080.8  298.45  5127.4  298.18  5358.5  298.85
  5414.5  298.25    5514  298.24  5546.1  296.31  5551.4  298.03  5577.7  296.23
    5583  297.53  5602.9  298.12  5609.4  296.66  5614.6  297.59  5639.4  297.35
  5662.5  295.75    5732  297.46  5763.3  299.02  5823.3  300.53  5830.3  301.38
#Mann= 6 ,-1 , 0
  4763.6     .11       0 4892.58     .09       0  4950.3     .15       0
  5028.7     .11       0  5127.4     .15       0  5414.5     .11       0
Bank Sta=4892.58,4950.3
XS Rating Curve= 0 ,0
Exp/Cntr=0.3,0.1

Type RM Length L Ch R = 1 ,5123    ,154,154,154
BEGIN DESCRIPTION:
CCLC 016 10.0
END DESCRIPTION:
XS GIS Cut Line= 3
       3759729.2     10113958.29      3759278.68     10114018.19
      3758893.22     10114158.83
#Sta/Elev= 30
  4554.9  299.59  4586.5  297.61  4717.7  292.34  4798.4  287.41  4828.6  287.25
  4837.6  286.61  4842.7  284.14  4858.9  281.34  4909.3  277.48    4921  275.96
 4974.15273.5871  4994.2  271.78  5012.5  272.17  5027.6  271.04  5031.1  271.04
  5034.6  273.39 5068.29273.5718  5084.8  274.94  5090.4  276.53  5098.9  277.43
  5115.7  279.57    5121  279.53  5127.4  281.22  5137.4  282.47  5232.5  286.67
    5287     291  5324.2  290.27  5340.3  290.73  5372.2     293  5419.7  294.85
#Mann= 5 ,-1 , 0
  4554.9     .11       0 4974.15     .06       0 5068.29     .11       0
  5098.9     .15       0  5137.4     .11       0
Bank Sta=4974.15,5068.29
XS Rating Curve= 0 ,0
Exp/Cntr=0.3,0.1

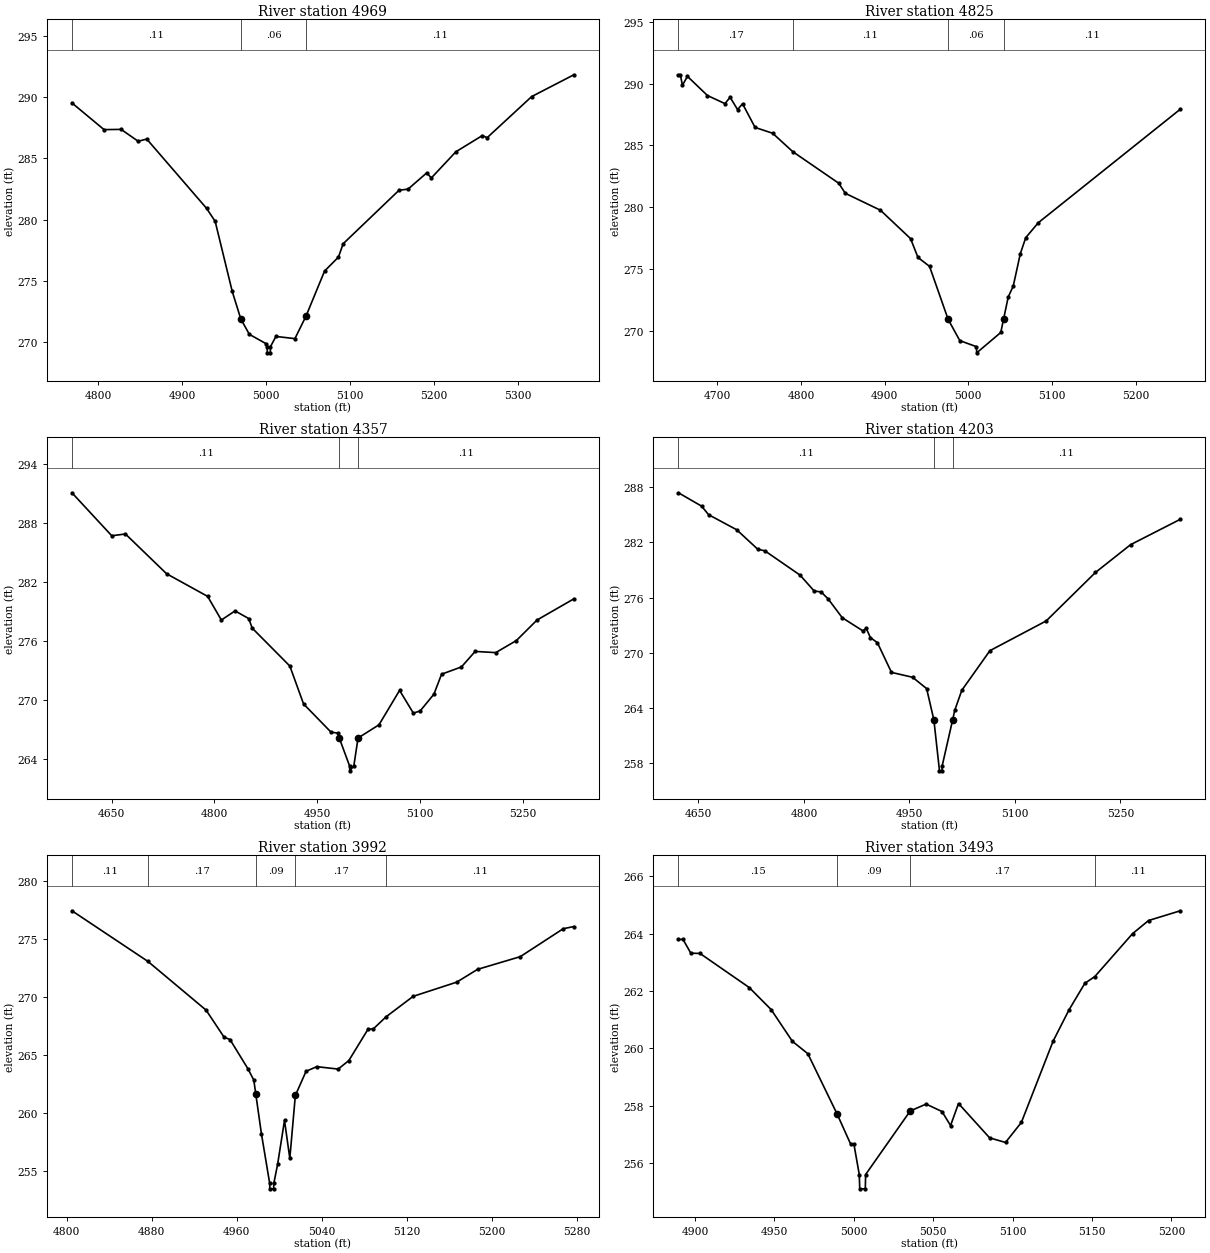
Type RM Length L Ch R = 1 ,4969    ,144,144,144
BEGIN DESCRIPTION:
CCLC 016 9.0
END DESCRIPTION:
XS GIS Cut Line= 3
      3759445.37      10113843.7      3759218.35     10113885.84
      3758893.26     10114054.65
#Sta/Elev= 30
  4769.1  289.53  4807.3  287.35  4827.6  287.37  4847.9   286.4  4858.1  286.58
  4929.3  280.92  4939.5  279.86  4959.8  274.14    4970  271.89  4980.2  270.63
    5000  269.87  5001.3  269.62  5001.6  269.12  5005.1  269.12  5005.3  269.62
  5011.8  270.46  5034.4  270.28  5047.6  272.12  5069.7   275.8  5086.2  276.94
  5091.8  278.03  5158.3   282.4    5169  282.49  5191.1  283.81  5196.8  283.41
  5225.9  285.54  5257.5  286.87  5263.1  286.69  5316.1  290.05  5366.3  291.83
#Mann= 3 , 0 , 0
  4769.1     .11       0    4970     .06       0  5047.6     .11       0
Bank Sta=4970,5047.6
XS Rating Curve= 0 ,0
Exp/Cntr=0.3,0.1

Type RM Length L Ch R = 1 ,4825    ,468,468,468
BEGIN DESCRIPTION:
Mapping XS 4f8630c7
END DESCRIPTION:
XS GIS Cut Line= 2
      3759416.69      10113583.3       3758919.3     10113919.23
#Sta/Elev= 30
  4653.3  290.73  4655.6  290.73  4658.1  289.88  4664.1   290.6    4688  289.05
    4709  288.39  4715.1  288.91    4724  287.91    4730  288.38    4745  286.46
    4766  285.99    4790   284.5    4845  281.94  4852.9  281.12  4894.9  279.75
  4930.9  277.45  4939.8  275.92  4953.6   275.2  4975.8  270.91  4989.8  269.18
  5009.7  268.69    5010  268.19  5038.8  269.84 5042.25270.9564  5047.7  272.72
  5053.7   273.6  5062.2  276.24  5068.7  277.53  5083.7  278.74  5253.5  287.94
#Mann= 4 ,-1 , 0
  4653.3     .17       0    4790     .11       0  4975.8     .06       0
 5042.25     .11       0
Bank Sta=4975.8,5042.25
XS Rating Curve= 0 ,0
Exp/Cntr=0.3,0.1

Type RM Length L Ch R = 1 ,4357    ,154,154,154
BEGIN DESCRIPTION:
CCLC 016 8.0
END DESCRIPTION:
XS GIS Cut Line= 3
      3758924.52     10113012.94      3758921.91     10113424.44
      3758898.47     10113744.78
#Sta/Elev= 30
    4592  291.11  4650.1  286.73  4670.1  286.91  4730.1  282.86  4790.1  280.55
  4810.1  278.14  4830.1  279.07  4850.1  278.29  4855.1  277.32  4910.1  273.45
  4930.1  269.59  4970.1  266.72  4980.1  266.61 4982.23266.1201  4997.3  263.27
  4997.6  262.77  5003.5  263.27 5009.65266.1154  5040.2  267.46  5070.3  270.97
  5090.4  268.65  5100.4  268.88  5120.4  270.58  5131.6  272.62  5160.6  273.36
  5180.6  274.94  5210.7  274.82  5240.8  276.05  5270.9  278.14  5324.7   280.3
#Mann= 3 ,-1 , 0
    4592     .11       0 4982.23     .07       0 5009.65     .11       0
Bank Sta=4982.23,5009.65
XS Rating Curve= 0 ,0
Exp/Cntr=0.3,0.1

Type RM Length L Ch R = 1 ,4203    ,211,211,211
BEGIN DESCRIPTION:
Mapping XS 192577fa
END DESCRIPTION:
XS GIS Cut Line= 2
      3758778.68     10113018.15      3758763.06     10113731.78
#Sta/Elev= 30
  4621.5  287.39  4654.4  285.94  4664.4  285.01  4704.4  283.37  4734.4  281.25
  4744.5  281.08  4794.5  278.44  4814.5  276.72  4824.5  276.61  4834.5  275.85
  4854.5  273.81  4883.7  272.39  4888.7  272.65  4894.5  271.65  4904.5   271.1
  4924.5  267.87  4954.5  267.34  4974.5  266.11 4984.82262.7005  4992.8  257.17
  4996.3  257.17  4996.5  257.67 5011.39 262.674  5014.5  263.75  5024.5  265.92
  5064.5  270.23  5144.5  273.46  5214.6  278.73  5264.6  281.75  5335.3  284.51
#Mann= 3 ,-1 , 0
  4621.5     .11       0 4984.82     .07       0 5011.39     .11       0
Bank Sta=4984.82,5011.39
XS Rating Curve= 0 ,0
Exp/Cntr=0.3,0.1

Type RM Length L Ch R = 1 ,3992    ,499,499,499
BEGIN DESCRIPTION:
CCLC 016 7.0
END DESCRIPTION:
XS GIS Cut Line= 3
      3758667.86     10113161.05      3758581.55     10113336.01
      3758617.85     10113611.03
#Sta/Elev= 30
  4804.9  277.43  4876.4  273.06  4931.2  268.85  4948.1  266.52  4953.7  266.31
  4970.5   263.8  4976.1  262.81 4977.95261.6151  4983.3  258.16    4991  253.92
  4991.2  253.42  4994.7  253.42    4995  253.92  4998.5  255.53    5005  259.33
    5010  256.05  5015.2  261.48  5025.3  263.57  5035.4  263.97  5055.5  263.76
  5065.6   264.5  5083.6   267.2  5088.6  267.23  5100.7  268.28  5126.1  270.04
  5167.2  271.27  5186.7  272.37    5227  273.47  5267.4  275.88  5277.4  276.07
#Mann= 5 ,-1 , 0
  4804.9     .11       0  4876.4     .17       0 4977.95     .09       0
  5015.2     .17       0  5100.7     .11       0
Bank Sta=4977.95,5015.2
XS Rating Curve= 0 ,0
Exp/Cntr=0.3,0.1

Type RM Length L Ch R = 1 ,3493    ,497,497,497
BEGIN DESCRIPTION:
CCLC 016 6.0
END DESCRIPTION:
XS GIS Cut Line= 3
      3758167.87     10113161.05      3758110.73     10113255.63
      3758117.85      10113461.1
#Sta/Elev= 30
  4889.5   263.8  4892.4   263.8  4897.3  263.32  4903.1  263.31  4934.1  262.12
  4947.9  261.35  4961.3  260.24    4971  259.81 4989.58 257.687  4997.9  256.66
    5000  256.66  5003.4  255.59  5003.7  255.09  5007.2  255.09  5007.4  255.59
  5035.5  257.81  5045.5  258.05  5055.5  257.79  5060.9   257.3  5065.9  258.07
  5085.5  256.87  5095.5  256.71  5105.5  257.41  5125.5  260.25  5135.5  261.34
  5145.5  262.27  5151.7   262.5  5175.5     264  5185.6  264.46  5205.6   264.8
#Mann= 4 ,-1 , 0
  4889.5     .15       0 4989.58     .09       0  5035.5     .17       0
  5151.7     .11       0
Bank Sta=4989.58,5035.5
XS Rating Curve= 0 ,0
Exp/Cntr=0.3,0.1

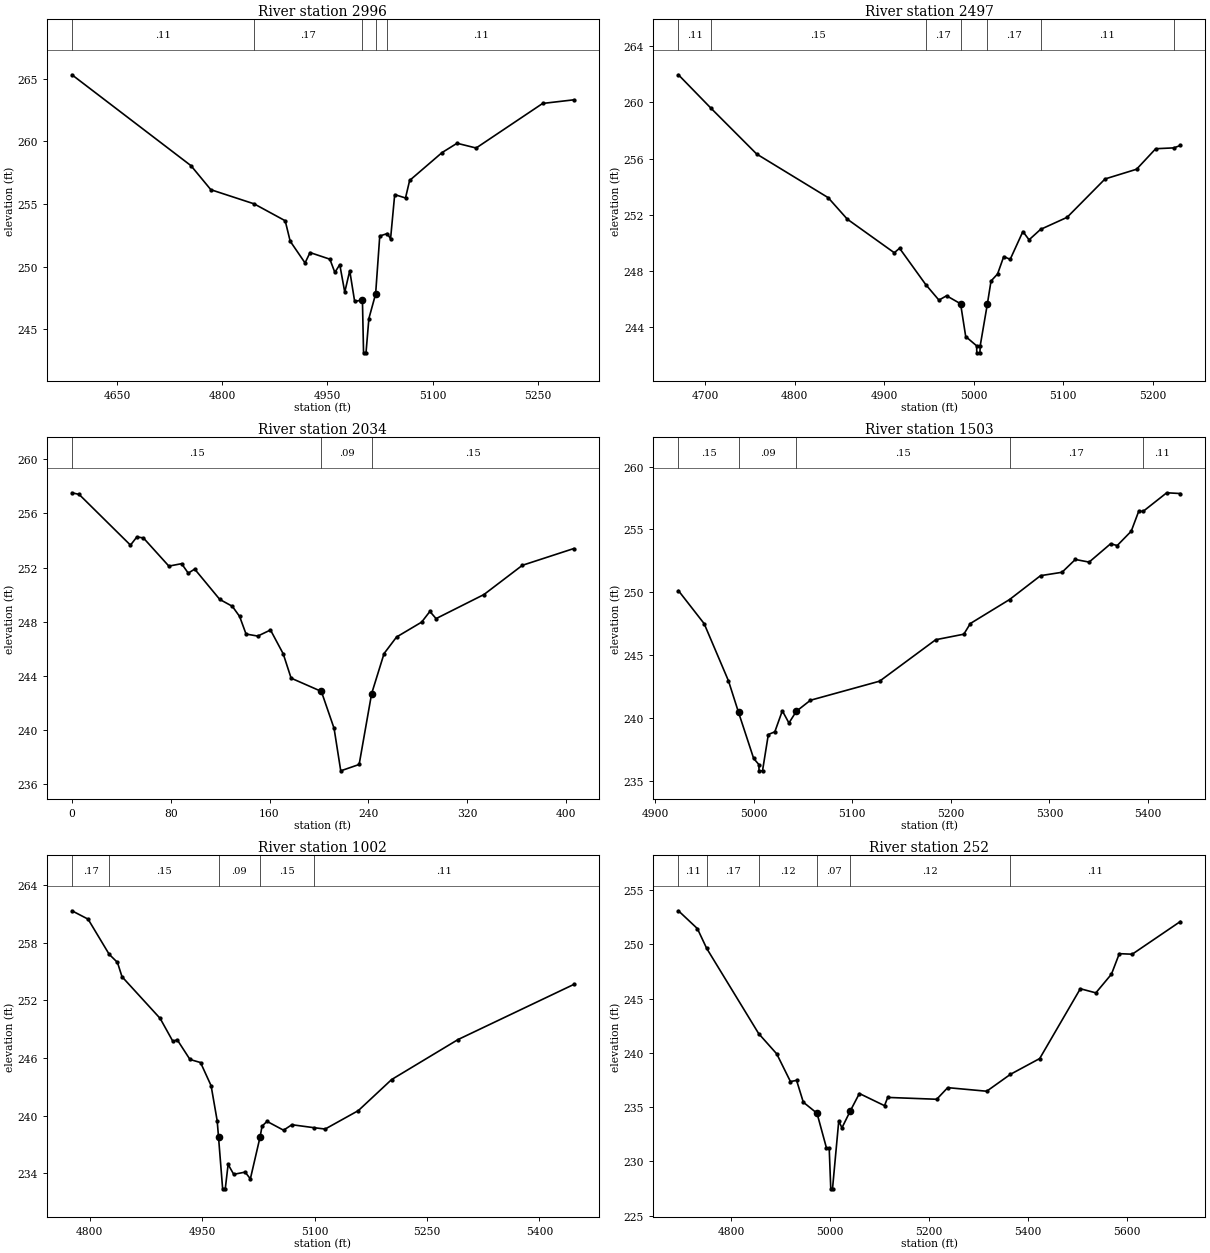
Type RM Length L Ch R = 1 ,2996    ,499,499,499
BEGIN DESCRIPTION:
CCLC 016 5.0
END DESCRIPTION:
XS GIS Cut Line= 3
      3757967.84     10112761.08      3757675.02     10113053.89
      3757517.86     10113311.06
#Sta/Elev= 30
  4585.9  265.32  4755.6  258.06  4783.9  256.14  4845.6  255.01  4889.9  253.66
    4897  252.03  4918.2  250.29  4925.3  251.12  4953.6  250.59  4960.7  249.53
  4967.7  250.16  4974.8  247.96  4981.9  249.67  4988.9  247.22    5000  247.33
  5001.6  243.11  5005.1  243.11  5009.2  245.85  5018.8  247.81  5024.7  252.44
  5035.5  252.64  5040.1  252.21    5046  255.75  5061.4  255.48  5067.3  256.88
  5113.6  259.11  5134.9  259.85  5162.1  259.47  5256.9  263.03  5301.4  263.32
#Mann= 5 ,-1 , 0
  4585.9     .11       0  4845.6     .17       0    5000     .09       0
  5018.8     .17       0  5035.5     .11       0
Bank Sta=5000,5018.8
XS Rating Curve= 0 ,0
Exp/Cntr=0.3,0.1

Type RM Length L Ch R = 1 ,2497    ,496,496,496
BEGIN DESCRIPTION:
CCLC 016 4.0
END DESCRIPTION:
XS GIS Cut Line= 3
      3757667.82     10112561.09      3757384.58     10112730.24
      3757225.11     10112897.23
#Sta/Elev= 30
  4670.1  261.97  4706.2  259.61  4757.6  256.33  4837.4  253.23  4858.8   251.7
  4911.3  249.31  4917.2  249.63  4946.4  247.05  4961.2  245.94  4969.7  246.25
 4985.38245.6814  4991.1  243.35  5003.3  242.69  5003.5  242.19    5007  242.19
  5007.3  242.69 5015.27 245.654  5019.4   247.3  5026.7   247.8  5033.6  249.04
  5040.8  248.84    5055  250.82  5061.9  250.23  5074.7  250.97  5104.4  251.83
  5146.8  254.56    5182  255.25  5203.4  256.71  5223.6  256.77  5230.9  256.94
#Mann= 7 ,-1 , 0
  4670.1     .11       0  4706.2     .15       0  4946.4     .17       0
 4985.38     .09       0 5015.27     .17       0  5074.7     .11       0
  5223.6     .17       0
Bank Sta=4985.38,5015.27
XS Rating Curve= 0 ,0
Exp/Cntr=0.3,0.1

Type RM Length L Ch R = 1 ,2034    ,498,498,498
BEGIN DESCRIPTION:
CCLC 016 3.0
END DESCRIPTION:
XS GIS Cut Line= 3
      3757110.39     10112394.85      3757162.21     10112606.62
      3757189.51     10112793.16
#Sta/Elev= 30
       0  257.53     5.8  257.41    47.4  253.66    52.6  254.27    57.9  254.19
    78.5  252.11    88.8  252.29    94.2  251.59    99.4  251.89   119.7  249.65
   129.9  249.14   135.8  248.39     141  247.09   150.5  246.94   160.8  247.39
   171.1  245.63   177.5  243.83     202  242.85   212.3  240.12   217.7  236.98
   232.6  237.45   242.7  242.68   252.8  245.65   262.9  246.87   283.2  247.97
   289.9  248.76   294.9  248.23   333.7  250.01   364.8  252.17   406.5  253.41
#Mann= 3 ,-1 , 0
       0     .15       0     202     .09       0   242.7     .15       0
Bank Sta=202,242.7
XS Rating Curve= 0 ,0
Exp/Cntr=0.3,0.1

Type RM Length L Ch R = 1 ,1503    ,501,501,501
BEGIN DESCRIPTION:
CCLC 016 2.0
END DESCRIPTION:
XS GIS Cut Line= 3
      3756767.86     10112611.11      3756782.05     10112686.19
      3757067.85     10113011.07
#Sta/Elev= 30
  4923.6  250.13  4949.7   247.5  4974.4  242.94  4984.6  240.43  4999.9  236.77
  5005.2  236.28  5005.4  235.78  5008.9  235.78  5014.8  238.67  5021.4  238.89
    5029  240.56  5035.7  239.59  5043.2  240.52  5057.5   241.4  5127.7  242.92
  5184.6  246.22  5213.1  246.66  5219.7  247.51  5259.5  249.42  5290.9  251.32
  5312.7  251.59  5326.2  252.61  5340.2   252.4    5362  253.86  5368.7  253.72
  5382.9  254.86  5390.5  256.45    5395  256.44  5418.9  257.92  5432.7  257.86
#Mann= 5 ,-1 , 0
  4923.6     .15       0  4984.6     .09       0  5043.2     .15       0
  5259.5     .17       0    5395     .11       0
Bank Sta=4984.6,5043.2
XS Rating Curve= 0 ,0
Exp/Cntr=0.3,0.1

Type RM Length L Ch R = 1 ,1002    ,750,750,750
BEGIN DESCRIPTION:
Mapping XS 0cfbfb68
END DESCRIPTION:
XS GIS Cut Line= 2
      3756343.77     10112596.28      3756632.85     10113200.49
#Sta/Elev= 30
  4776.1  261.31  4797.6  260.44  4825.8  256.78  4836.8  255.94  4842.9  254.45
  4893.8  250.11  4910.9  247.71  4916.5   247.9  4933.6  245.84  4947.7  245.52
  4961.8  243.11  4969.9  239.47 4971.68 237.794  4977.2  232.38  4980.7  232.38
  4984.5  234.92    4992  233.89  5007.2  234.12  5014.2  233.42 5027.18237.7855
  5029.8   238.9  5036.4   239.4  5058.5  238.48  5069.6  239.05  5099.3  238.74
    5114   238.6  5158.3  240.52  5202.7  243.75  5291.3  247.91  5445.9  253.65
#Mann= 5 ,-1 , 0
  4776.1     .17       0  4825.8     .15       0 4971.68     .09       0
 5027.18     .15       0  5099.3     .11       0
Bank Sta=4971.68,5027.18
XS Rating Curve= 0 ,0
Exp/Cntr=0.3,0.1

Type RM Length L Ch R = 1 ,252     ,0,0,0
BEGIN DESCRIPTION:
CCLC 016 1.0
END DESCRIPTION:
XS GIS Cut Line= 5
      3755919.31     10112572.85      3755901.63     10112818.23
      3755916.56     10112872.89      3756085.97     10113078.08
      3756510.43     10113213.49
#Sta/Elev= 30
  4693.4  253.09  4731.7  251.45  4750.6  249.62  4855.7  241.77  4892.1  239.91
  4919.8  237.36  4932.2  237.47  4945.8  235.46  4973.5  234.44  4992.5  231.26
  4998.1  231.26  5001.3  227.48  5004.8  227.48  5017.4  233.72  5023.9   233.1
 5040.66234.6487  5059.1  236.26  5109.9  235.14  5116.4   235.9  5215.4  235.73
  5237.6   236.8  5316.4  236.47  5364.5  238.03  5423.5  239.48  5505.6  245.91
    5537  245.53  5568.5  247.25  5584.4  249.14  5610.5  249.09  5707.7   252.1
#Mann= 6 ,-1 , 0
  4693.4     .11       0  4750.6     .17       0  4855.7     .12       0
  4973.5     .07       0 5040.66     .12       0  5364.5     .11       0
Bank Sta=4973.5,5040.66
XS Rating Curve= 0 ,0
Exp/Cntr=0.3,0.1

Chan Stop Cuts=-1
Use User Specified Reach Order=0
Composite Channel Slope=5