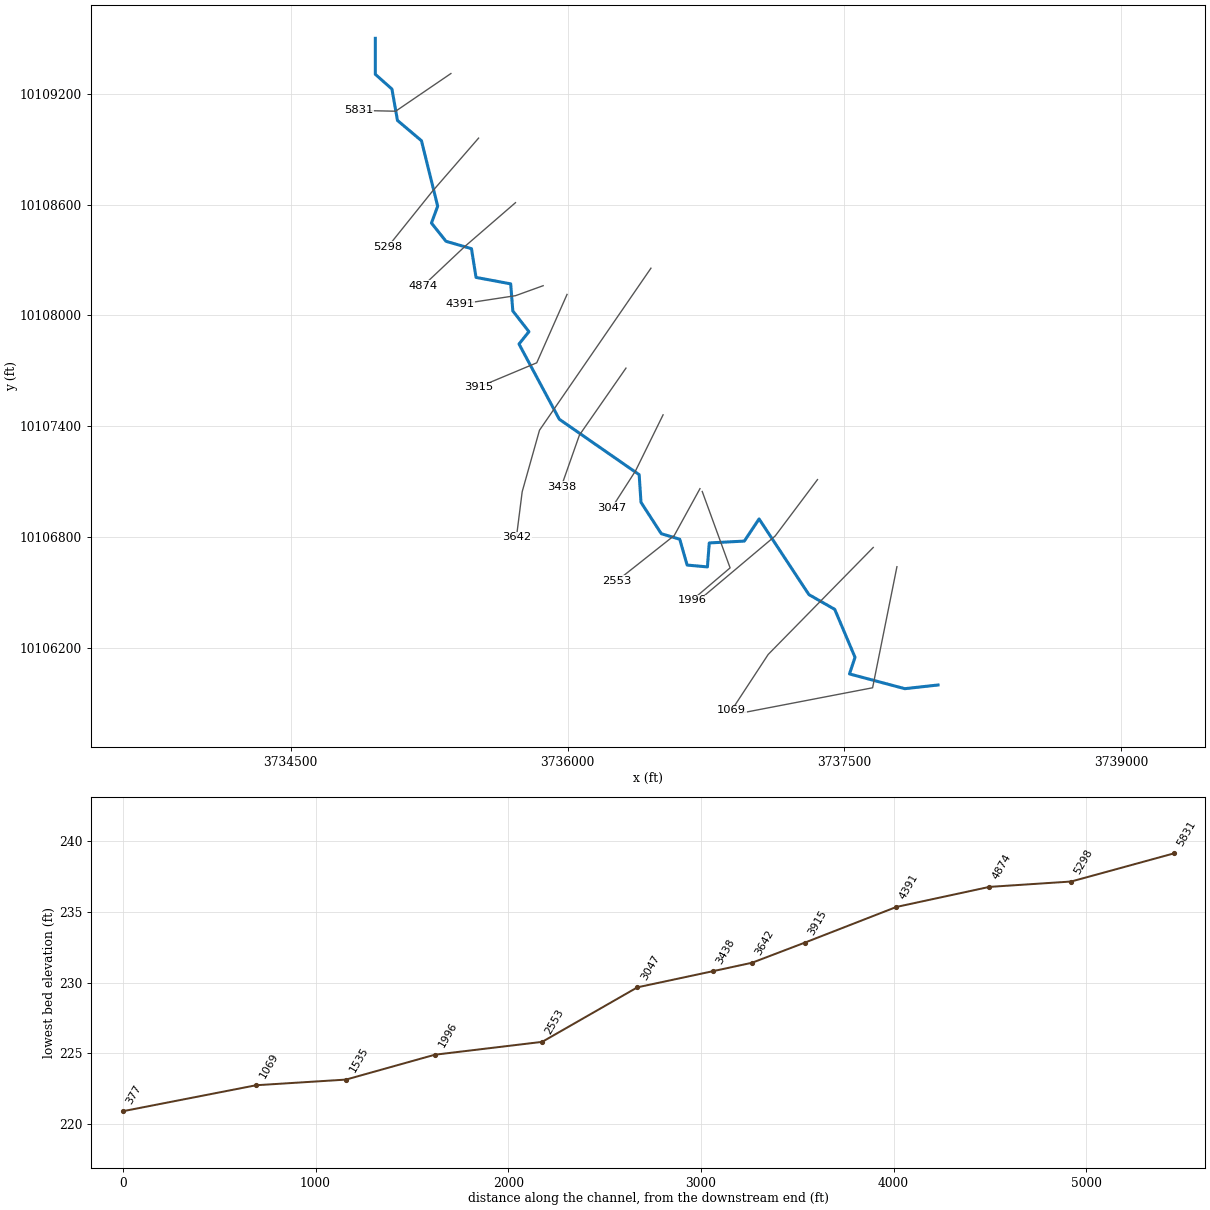
--- CCLC 020.prj (project) ---

Proj Title=CCLC 020 Base Level Engineering
Current Plan=p01
Default Exp/Contr=0.3,0.1
English Units
Geom File=g01
Flow File=f01
Flow File=f02
Plan File=p01
Y Axis Title=Elevation
X Axis Title(PF)=Main Channel Distance
X Axis Title(XS)=Station
BEGIN DESCRIPTION:
CCLC 020
END DESCRIPTION:
DSS Export Rating Curves= 0
DSS Export Rating Curve Sorted= 0
DSS Export Volume Flow Curves= 0
DXF OffsetX= 0
DXF OffsetY= 0
DXF ScaleX= 1
DXF ScaleY= 10

--- CCLC 020.p01 (plan) ---

Plan Title=Multiple Run
Short Identifier=Multiple
Geom File=g01
Flow File=f01
Subcritical Flow
K Sum by GR= 0
Std Step Tol= 0.01
Critical Tol= 0.01
Num of Std Step Trials= 20
Max Error Tol= 0.3
Flow Tol Ratio= 0.001
Split Flow NTrial= 30
Split Flow Tol= 0.02
Split Flow Ratio= 0.02
Log Output Level= 0
Friction Slope Method= 1
Unsteady Friction Slope Method= 2
Unsteady Bridges Friction Slope Method= 1
Parabolic Critical Depth
Global Vel Dist=  1 , 1 , 1
Global Log Level= 0
CheckData=True
Encroach Param= -1, 0, 0, 0
BEGIN DESCRIPTION:
Multiple Run
END DESCRIPTION:

--- CCLC 020.f01 (steady flow) ---

Flow Title=Multiple
Program Version=4.10
Number of Profiles= 7
Profile Names=10-year,25-year,50-year,1pct_min,100-year,1pct_plu,500-year
River Rch & RM=CCLC 020,Reach-1         ,5831
     617     842    1143     512    1546    4669    2921
River Rch & RM=CCLC 020,Reach-1         ,4874
     761    1037    1409     629    1899    5735    3569
Boundary for River Rch & Prof#=CCLC 020,Reach-1         , 1
Up Type= 0
Dn Type= 3
Dn Slope=0.005
Boundary for River Rch & Prof#=CCLC 020,Reach-1         , 2
Up Type= 0
Dn Type= 3
Dn Slope=0.005
Boundary for River Rch & Prof#=CCLC 020,Reach-1         , 3
Up Type= 0
Dn Type= 3
Dn Slope=0.005
Boundary for River Rch & Prof#=CCLC 020,Reach-1         , 4
Up Type= 0
Dn Type= 3
Dn Slope=0.005
Boundary for River Rch & Prof#=CCLC 020,Reach-1         , 5
Up Type= 0
Dn Type= 3
Dn Slope=0.005
Boundary for River Rch & Prof#=CCLC 020,Reach-1         , 6
Up Type= 0
Dn Type= 3
Dn Slope=0.005
Boundary for River Rch & Prof#=CCLC 020,Reach-1         , 7
Up Type= 0
Dn Type= 3
Dn Slope=0.005
DSS Import GetInterval= 0
DSS Import GetPeak= 0
DSS Import FillOption= 0

--- CCLC 020.f02 (steady flow) ---

Flow Title=Orig_BLE_Flows
Program Version=4.10
Number of Profiles= 7
Profile Names=10-year,25-year,50-year,1pct_min,100-year,1pct_plu,500-year
River Rch & RM=CCLC 020,Reach-1         ,5831
     617     825     994     394    1189    3591    1698
River Rch & RM=CCLC 020,Reach-1         ,4874
     761    1017    1225     484    1461    4411    2075
Boundary for River Rch & Prof#=CCLC 020,Reach-1         , 1
Up Type= 0
Dn Type= 3
Dn Slope=0.005
Boundary for River Rch & Prof#=CCLC 020,Reach-1         , 2
Up Type= 0
Dn Type= 3
Dn Slope=0.005
Boundary for River Rch & Prof#=CCLC 020,Reach-1         , 3
Up Type= 0
Dn Type= 3
Dn Slope=0.005
Boundary for River Rch & Prof#=CCLC 020,Reach-1         , 4
Up Type= 0
Dn Type= 3
Dn Slope=0.005
Boundary for River Rch & Prof#=CCLC 020,Reach-1         , 5
Up Type= 0
Dn Type= 3
Dn Slope=0.005
Boundary for River Rch & Prof#=CCLC 020,Reach-1         , 6
Up Type= 0
Dn Type= 3
Dn Slope=0.005
Boundary for River Rch & Prof#=CCLC 020,Reach-1         , 7
Up Type= 0
Dn Type= 3
Dn Slope=0.005
DSS Import GetInterval= 0
DSS Import GetPeak= 0
DSS Import FillOption= 0

--- CCLC 020.g01 (geometry) ---

Geom Title=Existing Conditions
Program Version=4.10

River Reach=CCLC 020        ,Reach-1
Reach XY= 30
      3734958.23     10109501.84      3734958.23     10109306.84
      3735048.23     10109226.84      3735078.23     10109056.84
      3735208.23     10108946.84      3735296.14     10108592.22
       3735262.4     10108500.52      3735341.12     10108401.89
      3735479.29     10108361.75      3735504.04     10108205.99
      3735691.83     10108171.06      3735703.47     10108024.03
      3735790.81     10107911.94      3735736.95     10107844.98
      3735955.31     10107437.38      3736388.23     10107136.84
      3736398.23     10106986.84      3736508.23     10106816.84
      3736608.23     10106786.84      3736648.23     10106646.84
      3736758.23     10106636.84      3736768.23     10106766.84
      3736958.23     10106776.84      3737038.23     10106896.84
      3737308.23     10106486.84      3737448.23     10106406.84
      3737558.23     10106146.84      3737528.23     10106056.84
      3737828.23     10105976.84      3738008.23     10105996.84

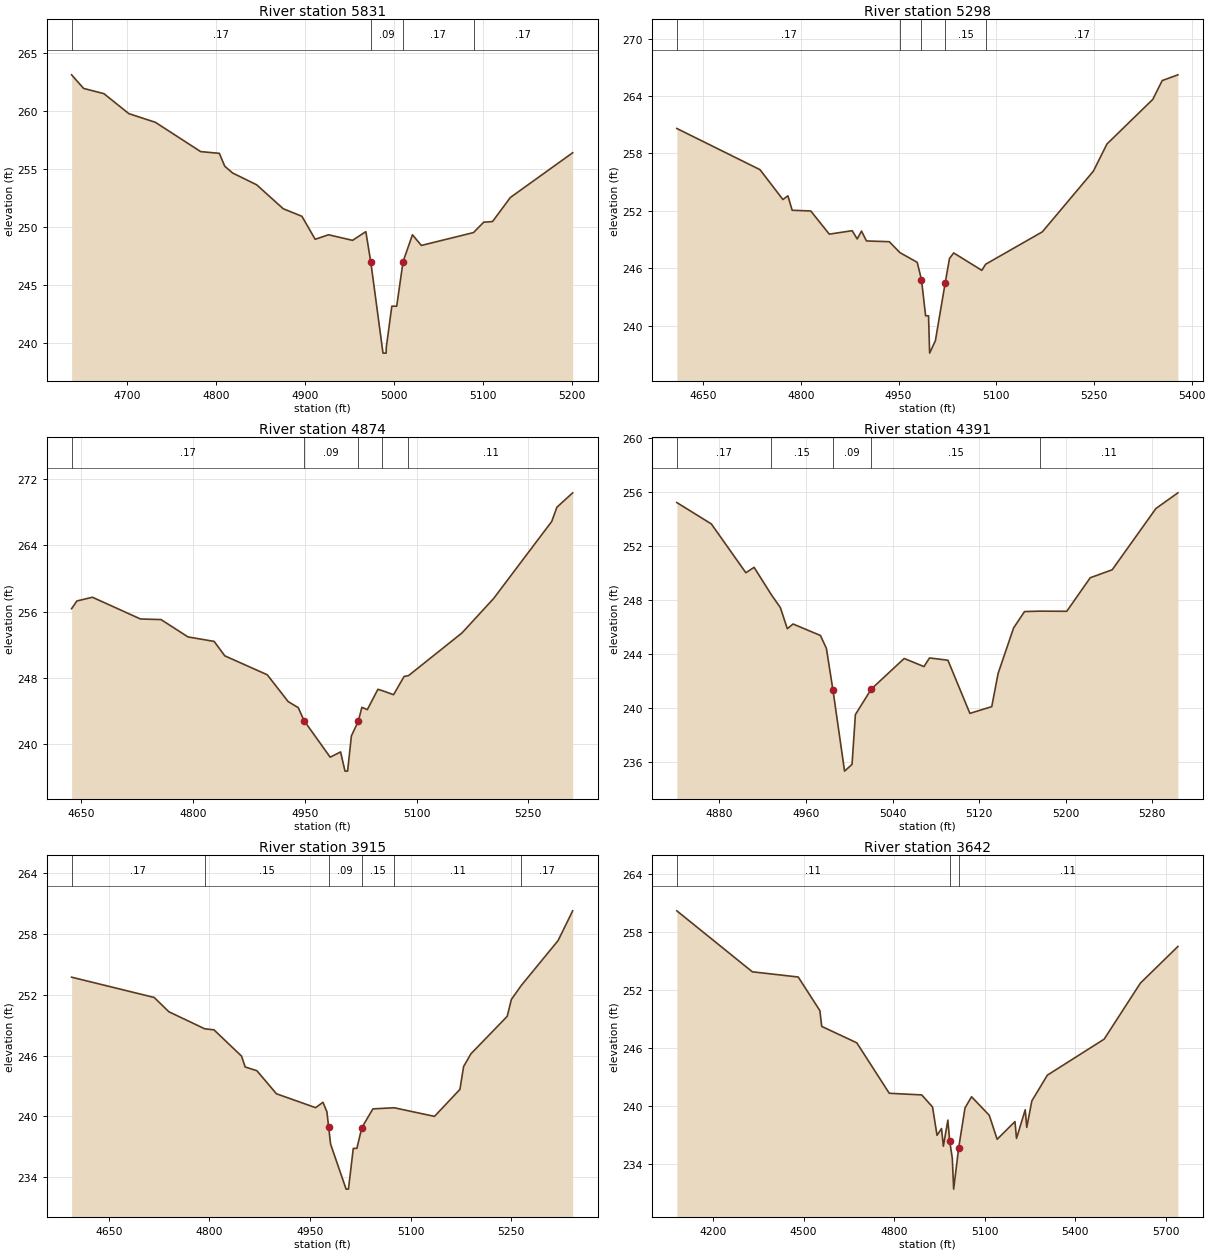
Type RM Length L Ch R = 1 ,5831    ,533,533,533
BEGIN DESCRIPTION:
CCLC 020 10.0
END DESCRIPTION:
XS GIS Cut Line= 3
      3735367.85     10109311.07      3735068.23     10109106.84
      3734867.87     10109111.07
#Sta/Elev= 30
  4637.4  263.11  4650.9  261.94  4673.7  261.49  4701.7  259.77  4731.6  259.02
  4782.4   256.5  4803.4  256.35  4809.5  255.24  4818.3  254.66  4845.4  253.64
  4875.2  251.58  4896.2  250.93  4911.1  248.95  4926.1  249.34  4953.1  248.86
    4968  249.61 4973.65246.9552  4987.3  239.15  4990.8  239.15    4991  239.65
  4997.2  243.19  5002.7  243.19 5009.89247.0372  5020.4  249.34  5030.4  248.42
    5089  249.53  5100.4  250.42  5110.4  250.48  5130.4  252.55  5200.4   256.4
#Mann= 4 ,-1 , 0
  4637.4     .17       0 4973.65     .09       0 5009.89     .17       0
    5089     .17       0
Bank Sta=4973.65,5009.89
XS Rating Curve= 0 ,0
Exp/Cntr=0.3,0.1

Type RM Length L Ch R = 1 ,5298    ,424,424,424
BEGIN DESCRIPTION:
CCLC 020 9.0
END DESCRIPTION:
XS GIS Cut Line= 3
      3735517.86     10108961.08      3735264.61     10108669.25
      3735025.05     10108370.67
#Sta/Elev= 30
  4609.7  260.61  4737.4  256.31  4772.6  253.19  4780.2  253.58  4786.8  252.07
  4815.3     252  4843.8  249.58  4878.9  249.94  4886.6  249.08  4893.2   249.9
  4900.8  248.87  4935.9  248.79  4952.2  247.65  4978.7  246.64  4985.3  244.82
  4991.6  241.06  4996.1  241.06  4997.8  237.16  5006.6  238.45 5021.76244.5221
  5028.3  247.04  5034.7  247.62  5077.9   245.8  5083.8  246.44  5170.8  249.82
  5249.2  256.16    5270  258.99  5340.4  263.65  5354.8  265.61  5378.9  266.21
#Mann= 5 ,-1 , 0
  4609.7     .17       0  4952.2     .15       0  4985.3     .09       0
 5021.76     .15       0  5083.8     .17       0
Bank Sta=4985.3,5021.76
XS Rating Curve= 0 ,0
Exp/Cntr=0.3,0.1

Type RM Length L Ch R = 1 ,4874    ,483,483,483
BEGIN DESCRIPTION:
CCLC 020 8.0
END DESCRIPTION:
XS GIS Cut Line= 3
      3735717.86     10108611.08      3735443.12     10108373.52
      3735217.88      10108161.1
#Sta/Elev= 30
  4636.8  256.35  4643.9  257.28  4664.8  257.73  4729.3  255.11  4756.9  255.04
  4793.1  252.95  4828.2  252.41  4842.5  250.67  4899.5  248.39  4927.6  245.16
  4941.2  244.42  4948.9  242.87    4984  238.46    4998  239.09  5003.9  236.78
  5007.4  236.78  5012.5  241.02 5021.74242.7906  5026.6  244.47  5033.9  244.19
  5048.1  246.64  5054.2  246.47  5069.1  245.99  5083.3  248.19  5089.1  248.28
    5161  253.43  5203.4  257.57  5281.5  266.86  5288.4  268.57  5309.6  270.31
#Mann= 5 ,-1 , 0
  4636.8     .17       0  4948.9     .09       0 5021.74     .17       0
  5054.2     .15       0  5089.1     .11       0
Bank Sta=4948.9,5021.74
XS Rating Curve= 0 ,0
Exp/Cntr=0.3,0.1

Type RM Length L Ch R = 1 ,4391    ,476,476,476
BEGIN DESCRIPTION:
CCLC 020 7.0
END DESCRIPTION:
XS GIS Cut Line= 3
      3735867.87     10108161.08      3735718.03       10108107.
      3735417.82     10108061.07
#Sta/Elev= 30
  4840.7  255.22  4872.6  253.64  4904.5  250.03  4912.1  250.43    4928  248.41
  4936.4  247.45  4942.8  245.89  4948.1  246.24  4973.4  245.39  4978.9  244.44
 4984.94241.3749  4995.7  235.36  5002.6  235.86  5005.7  239.54  5020.4  241.43
  5050.8  243.69  5069.1  243.09  5074.2  243.73  5091.2  243.56  5111.5  239.63
  5131.7  240.13  5137.6  242.59  5151.9  245.95    5162  247.16  5176.1  247.19
    5201  247.18  5222.7  249.66    5243  250.25  5283.4  254.78  5303.7  255.94
#Mann= 5 ,-1 , 0
  4840.7     .17       0    4928     .15       0 4984.94     .09       0
  5020.4     .15       0  5176.1     .11       0
Bank Sta=4984.94,5020.4
XS Rating Curve= 0 ,0
Exp/Cntr=0.3,0.1

Type RM Length L Ch R = 1 ,3915    ,273,273,273
BEGIN DESCRIPTION:
CCLC 020 6.0
END DESCRIPTION:
XS GIS Cut Line= 3
      3735997.26     10108113.72      3735833.03     10107743.08
      3735517.86     10107611.07
#Sta/Elev= 30
  4594.6  253.72  4717.8  251.72  4739.7  250.31  4793.2  248.63  4806.9  248.53
    4848  245.94  4853.4  244.87  4870.9   244.5    4900  242.23  4958.4  240.86
  4969.4  241.39  4975.3  240.45 4977.84238.9768  4980.8  237.26  5003.9  232.83
  5007.4  232.83  5014.6  236.84    5020  236.85  5027.3  238.88  5043.8  240.74
  5075.6  240.85  5135.7     240  5173.6  242.66  5179.1  244.91  5189.9  246.16
  5244.1  249.86  5250.3  251.52  5264.8  252.88    5320  257.33  5341.7  260.26
#Mann= 6 ,-1 , 0
  4594.6     .17       0  4793.2     .15       0 4977.84     .09       0
  5027.3     .15       0  5075.6     .11       0  5264.8     .17       0
Bank Sta=4977.84,5027.3
XS Rating Curve= 0 ,0
Exp/Cntr=0.3,0.1

Type RM Length L Ch R = 1 ,3642    ,204,204,204
BEGIN DESCRIPTION:
Mapping XS 2da122bb
END DESCRIPTION:
XS GIS Cut Line= 4
      3736452.09     10108256.02      3735847.94     10107377.58
      3735754.19     10107044.25      3735722.94     10106797.72
#Sta/Elev= 30
  4080.1  260.21  4330.4   253.9  4482.6  253.36  4554.3  249.88  4560.4  248.25
  4676.7  246.55  4784.3  241.33  4891.9  241.16  4927.7  239.91  4942.6  236.98
  4957.5  237.68  4963.6  235.85  4978.5  238.55  4984.5  236.41  4993.3  234.59
  4997.7  231.41  5014.3  235.67  5035.3  239.81    5057  240.97  5115.8  239.05
  5141.9  236.57  5200.9   238.4  5206.1  236.66  5234.9  239.62  5240.1   237.8
  5256.9  240.54  5308.2   243.2  5496.6  246.93  5616.7  252.73    5741  256.52
#Mann= 3 , 0 , 0
  4080.1     .11       0  4984.5     .06       0  5014.3     .11       0
Bank Sta=4984.5,5014.3
XS Rating Curve= 0 ,0
Exp/Cntr=0.3,0.1

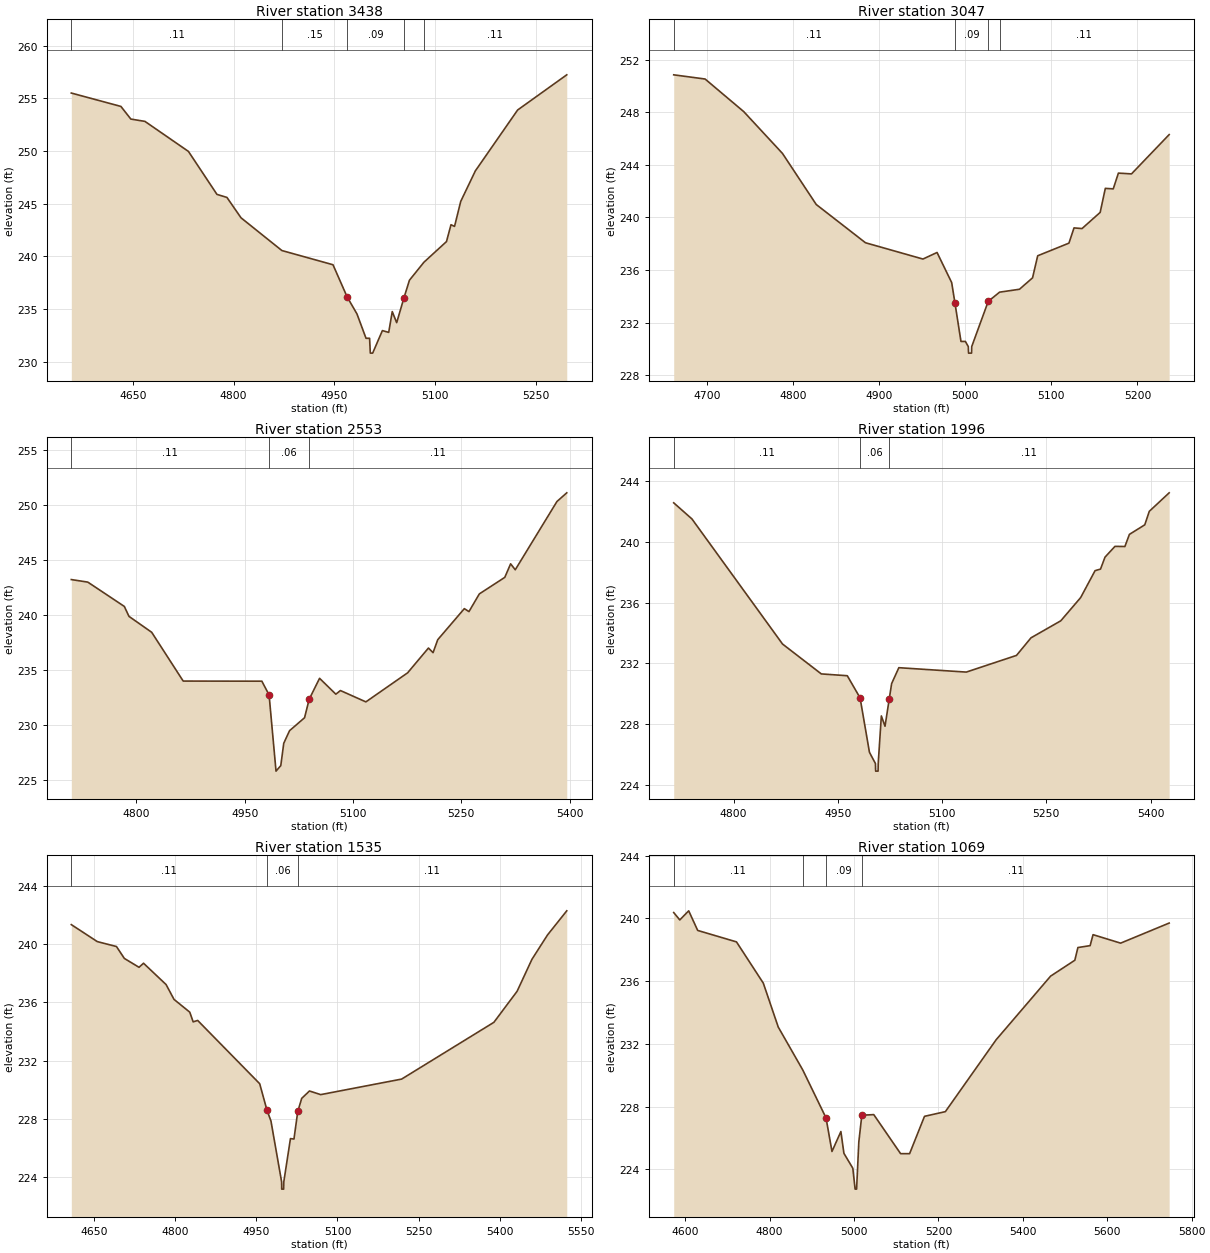
Type RM Length L Ch R = 1 ,3438    ,391,391,391
BEGIN DESCRIPTION:
CCLC 020 5.0
END DESCRIPTION:
XS GIS Cut Line= 3
      3736316.68     10107714.36      3736064.49     10107351.49
        3735966.     10107072.04
#Sta/Elev= 30
  4558.1   255.5    4632  254.23  4646.8  253.03  4667.8  252.81  4732.6  249.96
  4775.1  245.88    4790  245.59  4810.9  243.66  4871.8  240.55    4948   239.2
  4968.9  236.17  4983.8  234.52  4997.2  232.22  5002.5  232.22  5003.6  230.81
  5007.1  230.81  5021.6  232.95    5031  232.78  5036.3  234.75  5042.9   233.7
  5053.5  236.01  5061.9  237.73  5083.5  239.44  5117.1   241.4  5123.8     243
  5129.1  242.84  5138.3  245.21  5160.1  248.11  5223.1  253.89  5296.3  257.23
#Mann= 5 ,-1 , 0
  4558.1     .11       0  4871.8     .15       0  4968.9     .09       0
  5053.5     .15       0  5083.5     .11       0
Bank Sta=4968.9,5053.5
XS Rating Curve= 0 ,0
Exp/Cntr=0.3,0.1

Type RM Length L Ch R = 1 ,3047    ,494,494,494
BEGIN DESCRIPTION:
CCLC 020 4.0
END DESCRIPTION:
XS GIS Cut Line= 3
      3736517.84     10107461.05      3736368.23     10107156.84
      3736240.31     10106957.45
#Sta/Elev= 30
    4661  250.85  4697.5  250.53  4742.4  248.05  4787.4  244.87  4826.7  240.98
  4883.9  238.07  4950.7  236.83  4967.1  237.33  4984.1  235.04 4987.88233.4937
  4994.9  230.56    5000  230.56  5003.4  230.17  5003.7  229.67  5007.2  229.67
  5007.4  230.17  5026.6  233.61  5039.8  234.31  5062.9  234.53  5078.1   235.4
  5084.1  237.08  5120.4  238.04  5126.3   239.2  5135.6  239.15  5156.7  240.38
  5162.7  242.21  5171.9  242.17  5177.9  243.37  5193.1  243.31  5236.9   246.3
#Mann= 4 ,-1 , 0
    4661     .11       0 4987.88     .09       0  5026.6     .15       0
  5039.8     .11       0
Bank Sta=4987.88,5026.6
XS Rating Curve= 0 ,0
Exp/Cntr=0.3,0.1

Type RM Length L Ch R = 1 ,2553    ,557,557,557
BEGIN DESCRIPTION:
CCLC 020 3.0
END DESCRIPTION:
XS GIS Cut Line= 3
      3736717.83     10107061.03      3736578.23     10106806.84
      3736267.85     10106561.07
#Sta/Elev= 30
    4710  243.21  4732.8  242.98  4783.4  240.77  4789.8  239.87  4821.3  238.42
  4864.9  233.99  4973.8  233.98  4983.8  232.73  4993.4  225.81    5000  226.31
  5004.1  228.34  5012.1  229.48  5032.9  230.66  5039.3  232.34  5053.7  234.24
  5076.2   232.8  5082.6  233.13  5117.8   232.1  5175.6  234.74  5204.4  236.99
  5210.8  236.57  5217.3  237.75  5254.1  240.57  5260.5   240.3  5274.9  241.91
  5310.1  243.41  5318.2  244.64  5324.6   244.1  5382.3   250.3  5395.9  251.09
#Mann= 3 , 0 , 0
    4710     .11       0  4983.8     .06       0  5039.3     .11       0
Bank Sta=4983.8,5039.3
XS Rating Curve= 0 ,0
Exp/Cntr=0.3,0.1

Type RM Length L Ch R = 1 ,1996    ,461,461,461
BEGIN DESCRIPTION:
Mapping XS aa714e99
END DESCRIPTION:
XS GIS Cut Line= 3
      3736730.08     10107045.71      3736881.12     10106631.64
       3736673.7     10106455.33
#Sta/Elev= 30
  4713.8  242.59    4740  241.53  4870.4  233.28  4926.2  231.31  4963.6  231.19
    4982  229.73  4995.5  226.14  5004.1   225.4  5004.4   224.9  5007.9   224.9
  5008.1   225.4  5012.6  228.54  5017.9  227.86 5023.88229.6288  5027.4  230.67
  5037.8  231.72  5134.8  231.43  5207.1  232.53    5228  233.69  5270.8  234.81
  5299.4  236.34  5320.2  238.12    5328  238.22  5334.5  239.01  5348.8  239.72
  5363.1  239.71  5369.6  240.51  5391.7  241.14  5398.2  242.03  5426.8  243.25
#Mann= 3 , 0 , 0
  4713.8     .11       0    4982     .06       0 5023.88     .11       0
Bank Sta=4982,5023.88
XS Rating Curve= 0 ,0
Exp/Cntr=0.3,0.1

Type RM Length L Ch R = 1 ,1535    ,466,466,466
BEGIN DESCRIPTION:
CCLC 020 2.0
END DESCRIPTION:
XS GIS Cut Line= 3
      3737354.86     10107110.19      3737125.72     10106804.67
      3736717.86     10106461.08
#Sta/Elev= 30
  4608.3  241.36  4656.3  240.19  4691.7  239.85  4706.3  239.03  4733.4  238.42
  4741.7   238.7  4783.4  237.23    4798  236.21  4827.1  235.33  4833.4  234.66
  4841.7  234.76  4956.3   230.4  4969.7  228.58  4977.1  227.83  4996.8  223.64
    4997  223.14  5000.5  223.14  5000.8  223.64  5013.1  226.62  5019.6  226.59
  5026.6  228.49  5033.9  229.39  5048.2   229.9    5069  229.65  5218.5  230.72
  5388.9  234.63  5431.8  236.77  5459.2  238.97  5487.8  240.64  5523.5  242.31
#Mann= 3 ,-1 , 0
  4608.3     .11       0  4969.7     .06       0  5026.6     .11       0
Bank Sta=4969.7,5026.6
XS Rating Curve= 0 ,0
Exp/Cntr=0.3,0.1

Type RM Length L Ch R = 1 ,1069    ,692,692,692
BEGIN DESCRIPTION:
Mapping XS 35e2d455
END DESCRIPTION:
XS GIS Cut Line= 3
        3737657.      10106742.2      3737087.53     10106162.31
      3736889.61     10105860.23
#Sta/Elev= 30
  4572.8  240.37  4587.2   239.9  4608.3  240.48  4629.6  239.23  4721.5   238.5
  4785.1  235.87  4820.5  233.07  4878.7  230.33  4933.7  227.28  4947.8  225.14
  4968.9  226.41  4976.1  225.02  4997.2  224.07  5002.6  222.74  5006.1  222.74
  5011.4  225.75  5018.5  227.45  5046.8  227.49  5110.4     225  5131.7     225
    5167  227.38  5216.5  227.68  5336.7  232.26  5465.9  236.32  5523.2  237.33
  5530.5  238.14  5559.4  238.26  5566.4  238.96  5631.7  238.42  5746.7   239.7
#Mann= 4 ,-1 , 0
  4572.8     .11       0  4878.7     .15       0  4933.7     .09       0
  5018.5     .11       0
Bank Sta=4933.7,5018.5
XS Rating Curve= 0 ,0
Exp/Cntr=0.3,0.1

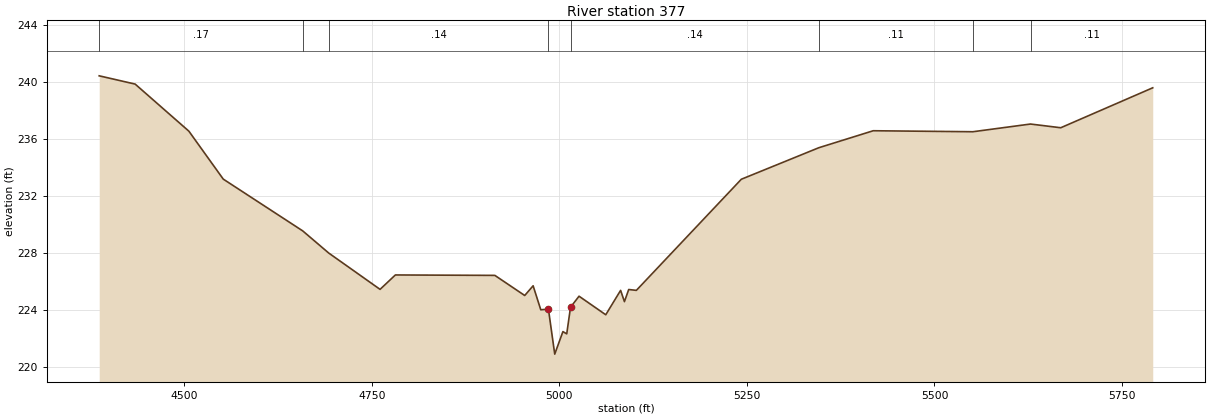
Type RM Length L Ch R = 1 ,377     ,0,0,0
BEGIN DESCRIPTION:
CCLC 020 1.0
END DESCRIPTION:
XS GIS Cut Line= 3
      3737785.45     10106638.01       3737653.5     10105981.75
      3736932.02       10105843.
#Sta/Elev= 30
  4386.8  240.41  4434.7  239.83  4506.3  236.53  4552.1  233.17    4658  229.54
  4692.6  227.99  4761.1  225.44  4781.5  226.45  4914.1  226.42  4953.9  225.01
  4965.1  225.69  4975.3  224.01  4985.5  224.05  4993.9   220.9  5004.8  222.48
  5009.9  222.32 5014.93 224.186  5026.3  224.96  5061.9  223.66  5081.7  225.37
  5086.8  224.58  5092.5  225.43  5102.7  225.37  5242.6  233.16  5345.9  235.37
  5418.4  236.56  5551.2  236.49    5628  237.03  5668.3  236.77  5790.9  239.57
#Mann= 8 ,-1 , 0
  4386.8     .17       0    4658     .11       0  4692.6     .14       0
  4985.5     .07       0 5014.93     .14       0  5345.9     .11       0
  5551.2     .17       0    5628     .11       0
Bank Sta=4985.5,5014.93
XS Rating Curve= 0 ,0
Exp/Cntr=0.3,0.1

Chan Stop Cuts=-1
Use User Specified Reach Order=0
Composite Channel Slope=5