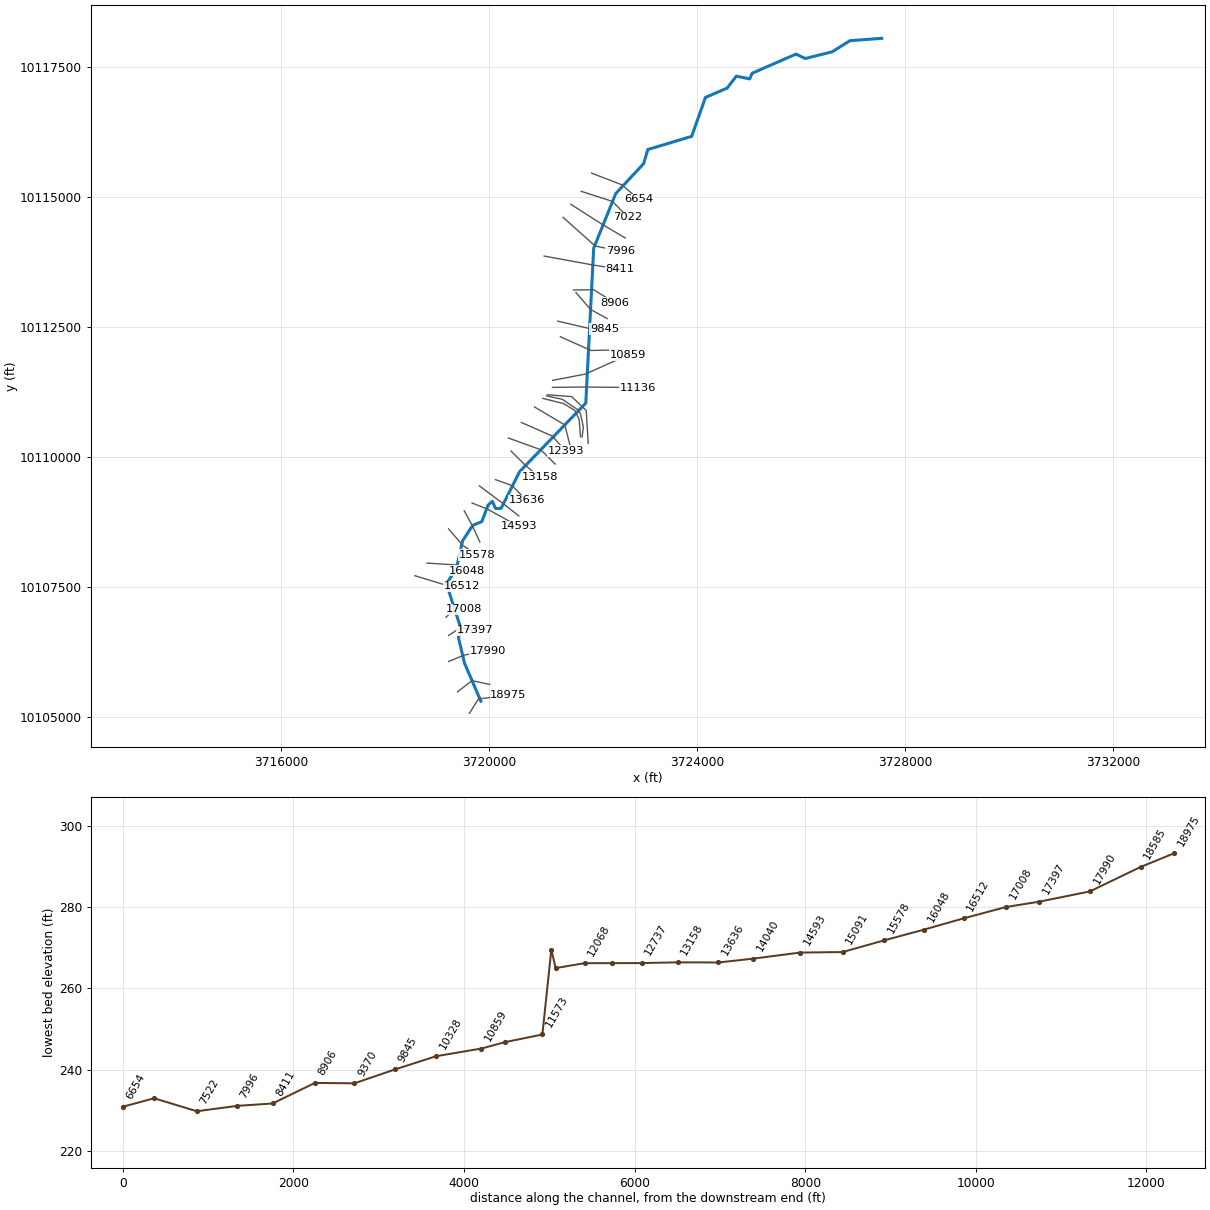
--- CCLC 022.prj (project) ---

Proj Title=CCLC 022 Base Level Engineering
Current Plan=p01
Default Exp/Contr=0.3,0.1
English Units
Geom File=g01
Flow File=f01
Flow File=f02
Plan File=p01
Y Axis Title=Elevation
X Axis Title(PF)=Main Channel Distance
X Axis Title(XS)=Station
BEGIN DESCRIPTION:
CCLC 022
END DESCRIPTION:
DSS File=dss
DSS Export Rating Curves= 0
DSS Export Rating Curve Sorted= 0
DSS Export Volume Flow Curves= 0
DXF OffsetX= 0
DXF OffsetY= 0
DXF ScaleX= 1
DXF ScaleY= 10

--- CCLC 022.p01 (plan) ---

Plan Title=Multiple Run
Program Version=4.10
Short Identifier=Multiple Run
Geom File=g01
Flow File=f01
Subcritical Flow
K Sum by GR= 0
Std Step Tol= 0.01
Critical Tol= 0.01
Num of Std Step Trials= 20
Max Error Tol= 0.3
Flow Tol Ratio= 0.001
Split Flow NTrial= 30
Split Flow Tol= 0.02
Split Flow Ratio= 0.02
Log Output Level= 0
Friction Slope Method= 1
Unsteady Friction Slope Method= 2
Unsteady Bridges Friction Slope Method= 1
Parabolic Critical Depth
Global Vel Dist= 1 , 1 , 1
Global Log Level= 0
CheckData=True
Encroach Param=-1 ,0,0, 0
BEGIN DESCRIPTION:
Multiple Run
END DESCRIPTION:
Computation Interval=1HOUR
Output Interval=1HOUR
Run HTab= 0
Run UNet= 0
Run PostProcess= 0
Run WQNet= 0
UNET Theta= 1
UNET Theta Warmup= 1
UNET ZTol= 0.02
UNET ZSATol= 0.05
UNET MxIter= 20
UNET MaxInSteps= 0
UNET DtIC= 0
UNET DtMin= 0
UNET MaxCRTS= 20
UNET WFStab= 2
UNET SFStab= 1
UNET WFX= 1
UNET SFX= 1
UNET DSS MLevel= 4
UNET DZMax Abort= 100
UNET Convert EG Bridges= 0
UNET Use Existing IB Tables=-1
UNET Froude Reduction=False
UNET Froude Limit= 1
UNET Froude Power= 10
UNET Time Slicing=0,0, 5
UNET Junction Losses=0
Instantaneous Interval=1HOUR
DSS File=dss
Write IC File= 0
Write IC File at Sim End=0
Echo Input=False
Echo Parameters=False
Echo Output=False
Write Detailed= 0
WQ AD Non Conservative
WQ ULTIMATE=-1
WQ Max Comp Step=1HOUR
WQ Output Interval=15MIN
WQ Output Selected Increments= 0
WQ Output face flow=0
WQ Output face velocity=0
WQ Output face area=0
WQ Output face dispersion=0
WQ Output cell volume=0
WQ Output cell surface area=0
WQ Output cell continuity=0
WQ Output cumulative cell continuity=0
WQ Output face conc=0
WQ Output face dconc_dx=0
WQ Output face courant=0
WQ Output face peclet=0
WQ Output face adv mass=0
WQ Output face disp mass=0
WQ Output cell mass=0
WQ Output cell source sink temp=0
WQ Output cell source sink nsm=0
WQ Output MaxMinRange=-1
WQ Daily Max Min Mean=-1
WQ Daily Range=0
WQ Daily Time=0
WQ Create Restart=0
WQ Fixed Restart=0
WQ System Summary=0
WQ Use Fixed Temperature=0
Sorting and Armoring Iterations= 10
XS Update Threshold= 0.02
Hydraulics Update Threshold= 0.02
Energy Slope Method= 1
Volume Change Method= 0
XS Weighting Method= 0
Number of US Weighted Cross Sections= 1
Number of DS Weighted Cross Sections= 1
Upstream XS Weight=0.25
Main XS Weight=0.5
Downstream XS Weight=0.25
Number of DS XS's Weighted with US Boundary= 1
Upstream Boundary Weight= 1
Weight of XSs Associated with US Boundary= 0
Number of US XS's Weighted with DS Boundary= 1
Downstream Boundary Weight= 0.5
Weight of XSs Associated with DS Boundary= 0.5
Sediment Output Level= 4
Mass or Volume Output= 0
Output Increment Type= 1
Profile and TS Output Increment= 10
XS Output Flag= 0
XS Output Increment= 10
Disregard all LS=0
Disregard all Conn=0
Disregard all Breaches=0
Disregard all Pumps=0

--- CCLC 022.f01 (steady flow) ---

Flow Title=Multiple
Program Version=4.10
Number of Profiles= 7
Profile Names=10-year,25-year,50-year,1pct_min,100-year,1pct_plu,500-year
River Rch & RM=CCLC 022,Reach-1         ,18975
     592     798    1073     475    1435    4334    2652
River Rch & RM=CCLC 022,Reach-1         ,11136
    1164    1618    2224    1003    3030    9150    5819
River Rch & RM=CCLC 022,Reach-1         ,5798
    1355    1899    2625    1190    3593   10851    6971
River Rch & RM=CCLC 022,Reach-1         ,2281
    4122    5900    8273    3798   11470   34639   22840
Boundary for River Rch & Prof#=CCLC 022,Reach-1         , 1
Up Type= 0
Dn Type= 3
Dn Slope=0.003
Boundary for River Rch & Prof#=CCLC 022,Reach-1         , 2
Up Type= 0
Dn Type= 3
Dn Slope=0.003
Boundary for River Rch & Prof#=CCLC 022,Reach-1         , 3
Up Type= 0
Dn Type= 3
Dn Slope=0.003
Boundary for River Rch & Prof#=CCLC 022,Reach-1         , 4
Up Type= 0
Dn Type= 3
Dn Slope=0.003
Boundary for River Rch & Prof#=CCLC 022,Reach-1         , 5
Up Type= 0
Dn Type= 3
Dn Slope=0.003
Boundary for River Rch & Prof#=CCLC 022,Reach-1         , 6
Up Type= 0
Dn Type= 3
Dn Slope=0.003
Boundary for River Rch & Prof#=CCLC 022,Reach-1         , 7
Up Type= 0
Dn Type= 3
Dn Slope=0.003
DSS Import GetInterval= 0
DSS Import GetPeak= 0
DSS Import FillOption= 0

--- CCLC 022.f02 (steady flow) ---

Flow Title=Orig_BLE_Flows
Program Version=4.10
Number of Profiles= 7
Profile Names=10-year,25-year,50-year,1pct_min,100-year,1pct_plu,500-year
River Rch & RM=CCLC 022,Reach-1         ,18975
     592     782     933     365    1104    3333    1542
River Rch & RM=CCLC 022,Reach-1         ,11136
    1164    1586    1934     772    2331    7039    3383
River Rch & RM=CCLC 022,Reach-1         ,5798
    1355    1862    2283     915    2764    8348    4053
River Rch & RM=CCLC 022,Reach-1         ,2281
    4122    5784    7194    2921    8823   26647   13279
Boundary for River Rch & Prof#=CCLC 022,Reach-1         , 1
Up Type= 0
Dn Type= 3
Dn Slope=0.003
Boundary for River Rch & Prof#=CCLC 022,Reach-1         , 2
Up Type= 0
Dn Type= 3
Dn Slope=0.003
Boundary for River Rch & Prof#=CCLC 022,Reach-1         , 3
Up Type= 0
Dn Type= 3
Dn Slope=0.003
Boundary for River Rch & Prof#=CCLC 022,Reach-1         , 4
Up Type= 0
Dn Type= 3
Dn Slope=0.003
Boundary for River Rch & Prof#=CCLC 022,Reach-1         , 5
Up Type= 0
Dn Type= 3
Dn Slope=0.003
Boundary for River Rch & Prof#=CCLC 022,Reach-1         , 6
Up Type= 0
Dn Type= 3
Dn Slope=0.003
Boundary for River Rch & Prof#=CCLC 022,Reach-1         , 7
Up Type= 0
Dn Type= 3
Dn Slope=0.003
DSS Import GetInterval= 0
DSS Import GetPeak= 0
DSS Import FillOption= 0

--- CCLC 022.g01 (geometry) ---

Geom Title=Existing Conditions
Program Version=4.10

River Reach=CCLC 022        ,Reach-1
Reach XY= 30
      3719837.97     10105294.71      3719521.82     10106032.33
      3719405.16     10106525.04      3719461.41     10106670.87
      3719174.95     10107554.73       3719368.7     10107851.08
      3719485.89     10108383.89      3719680.16     10108679.21
      3719856.69     10108753.43       3719975.4     10109070.27
      3720059.23     10109142.25      3720121.73     10109004.23
      3720228.51     10109009.44      3720580.74      10109711.2
       3721856.1     10111033.41      3722008.23     10114016.84
      3722432.98     10115068.19      3722968.09     10115642.25
      3723048.89     10115915.06      3723892.69     10116168.66
      3724157.82     10116917.94      3724575.12     10117097.77
      3724752.64     10117328.32      3725008.55     10117275.29
      3725059.27     10117385.96      3725900.77     10117752.53
      3726075.99     10117667.22      3726594.72     10117796.33
      3726938.24     10118010.74      3727549.16     10118055.92

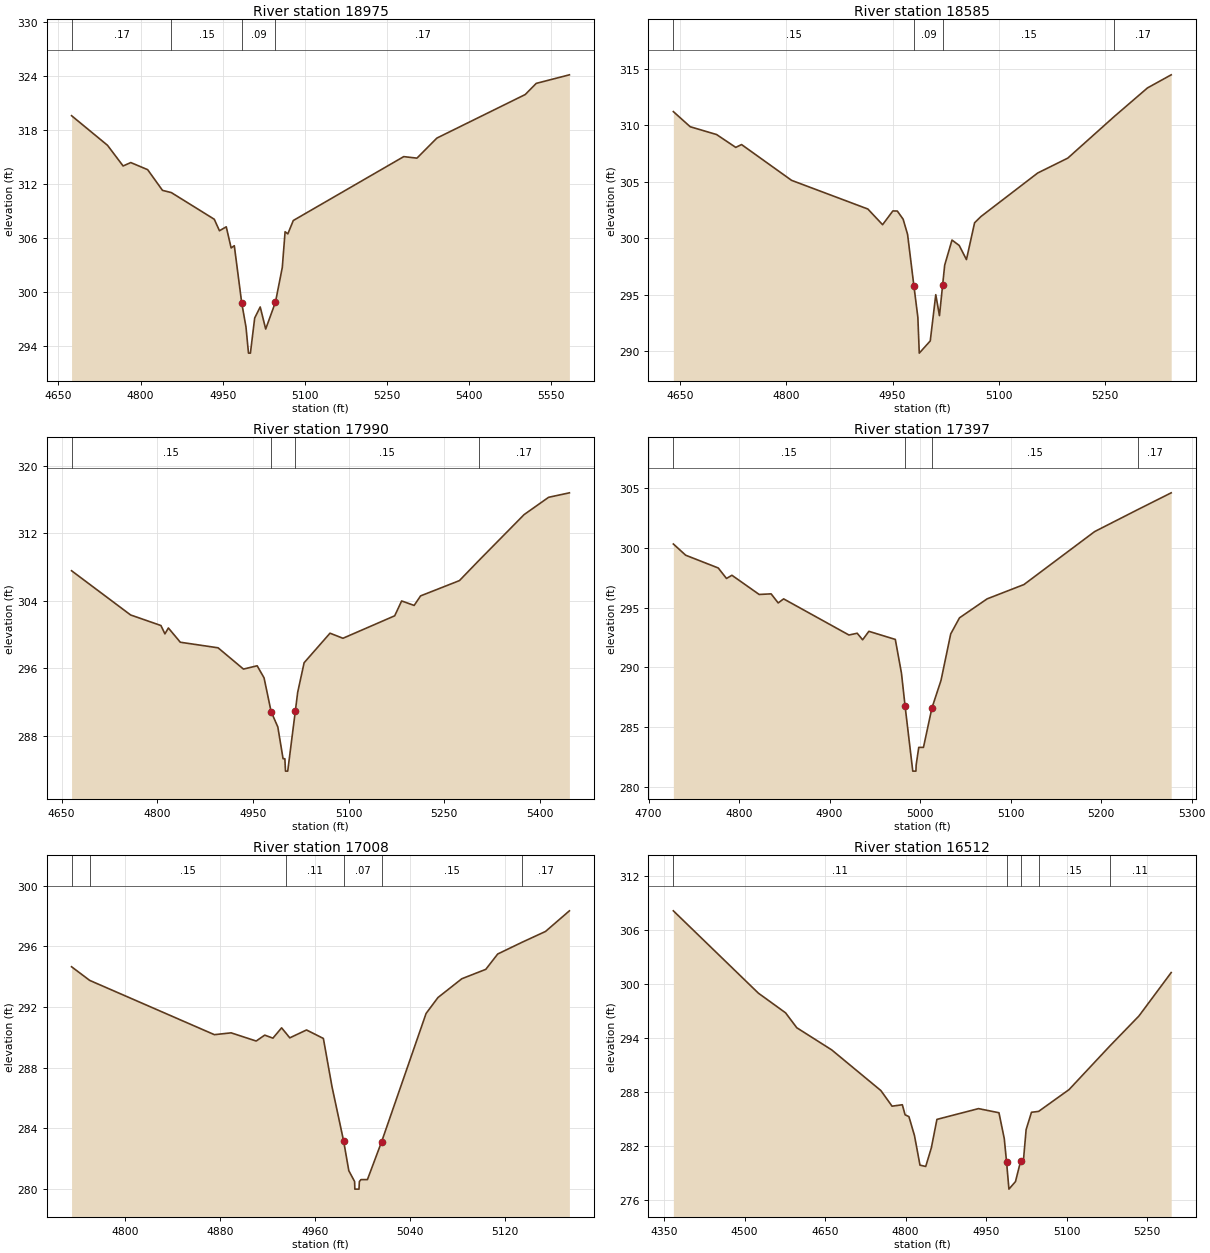
Type RM Length L Ch R = 1 ,18975   ,390,390,390
BEGIN DESCRIPTION:
CCLC 022 34.0
END DESCRIPTION:
XS GIS Cut Line= 3
      3719617.84     10105061.05      3719789.53     10105338.06
      3720367.84     10105411.07
#Sta/Elev= 30
  4674.1  319.56  4739.7  316.27  4768.2  313.97  4782.2  314.35    4813  313.56
  4840.1  311.26  4856.3  311.01  4934.6  308.05  4944.1  306.77  4956.5  307.21
  4965.4  304.86  4971.2  305.11 4984.72298.7554  4992.5  296.08  4997.1  293.17
  5000.6  293.17  5008.4  297.07  5018.5   298.3  5028.5  295.85  5046.3  298.83
  5058.8  302.69  5063.9  306.66  5068.9  306.42  5078.9  307.91  5280.5  315.01
  5304.6  314.84    5341  317.07  5502.3  321.91  5522.4  323.15  5582.9   324.1
#Mann= 4 ,-1 , 0
  4674.1     .17       0  4856.3     .15       0 4984.72     .09       0
  5046.3     .17       0
Bank Sta=4984.72,5046.3
XS Rating Curve= 0 ,0
Exp/Cntr=0.3,0.1

Type RM Length L Ch R = 1 ,18585   ,595,595,595
BEGIN DESCRIPTION:
CCLC 022 33.0
END DESCRIPTION:
XS GIS Cut Line= 3
      3719389.07     10105475.31      3719666.87      10105690.6
      3720010.66     10105617.68
#Sta/Elev= 30
  4640.6  311.23  4664.4  309.89  4701.6   309.2  4728.7  308.06  4736.9  308.31
  4807.5  305.14  4915.2   302.6    4936  301.21  4950.5  302.43  4956.8  302.42
    4965   301.7  4971.3  300.35 4980.31295.7375  4985.8  293.01  4987.8  289.83
  5003.3  290.91  5011.1  295.01  5016.3  293.15 5020.85295.9046  5023.7  297.63
    5034  299.85  5044.2  299.37  5054.4  298.12  5065.9  301.38  5074.8  301.93
    5155  305.79  5197.5  307.11    5263  310.79    5310  313.33  5343.5  314.49
#Mann= 4 ,-1 , 0
  4640.6     .15       0 4980.31     .09       0 5020.85     .15       0
    5263     .17       0
Bank Sta=4980.31,5020.85
XS Rating Curve= 0 ,0
Exp/Cntr=0.3,0.1

Type RM Length L Ch R = 1 ,17990   ,593,593,593
BEGIN DESCRIPTION:
CCLC 022 32.0
END DESCRIPTION:
XS GIS Cut Line= 3
      3719217.87     10106061.08      3719528.07     10106185.98
      3719967.81     10106261.06
#Sta/Elev= 30
  4665.6  307.56  4758.2  302.32  4805.7  301.07    4812  300.08  4817.4  300.78
  4836.1  299.09  4895.3  298.43  4935.1  295.91  4956.6   296.3  4967.4  294.87
  4978.5  290.86    4989  289.05  4997.2  285.29    5000  285.29    5001  283.82
  5004.5  283.82 5016.48290.9567  5020.1  293.15  5030.2  296.66  5070.8  300.16
  5091.1  299.56  5172.2  302.22  5183.1  303.98  5202.7  303.45  5212.8  304.58
  5273.7  306.39    5304  308.76  5375.1  314.21  5413.5  316.26  5446.1  316.79
#Mann= 4 ,-1 , 0
  4665.6     .15       0  4978.5     .09       0 5016.48     .15       0
    5304     .17       0
Bank Sta=4978.5,5016.48
XS Rating Curve= 0 ,0
Exp/Cntr=0.3,0.1

Type RM Length L Ch R = 1 ,17397   ,389,389,389
BEGIN DESCRIPTION:
CCLC 022 31.0
END DESCRIPTION:
XS GIS Cut Line= 3
      3719217.83     10106561.06      3719444.64     10106711.44
       3719717.9     10106661.06
#Sta/Elev= 30
  4727.4  300.33    4741  299.39    4777  298.32  4786.1  297.44  4792.1  297.71
  4822.2   296.1  4835.4  296.15  4843.2  295.39  4849.2  295.73  4921.4   292.7
  4930.5  292.85  4936.5   292.3  4943.4  293.01  4972.6  292.33  4979.4   289.5
 4983.43286.7231  4991.9  281.29  4995.4  281.29  4995.6  281.79  4998.5  283.28
  5003.7  283.28    5013  286.57  5023.1   288.9  5033.8  292.79  5043.5  294.14
    5074  295.73  5114.7  296.93  5192.8  301.37  5240.9  303.23  5277.4  304.62
#Mann= 4 ,-1 , 0
  4727.4     .15       0 4983.43     .09       0    5013     .15       0
  5240.9     .17       0
Bank Sta=4983.43,5013
XS Rating Curve= 0 ,0
Exp/Cntr=0.3,0.1

Type RM Length L Ch R = 1 ,17008   ,496,496,496
BEGIN DESCRIPTION:
CCLC 022 30.0
END DESCRIPTION:
XS GIS Cut Line= 3
      3719167.87     10106911.09      3719344.74     10107080.77
      3719517.82     10107061.07
#Sta/Elev= 30
  4754.9  294.66  4770.2  293.76  4875.2  290.18  4889.3   290.3  4910.4  289.76
  4917.6  290.15  4924.5  289.95  4931.8  290.63  4935.7  290.26  4938.7  289.97
  4952.8  290.49    4967  289.93  4974.2  286.77 4984.07283.1556  4988.4  281.21
  4993.3  280.49  4993.5  279.99    4997  279.99  4997.3  280.49  4998.7  280.62
  5004.1  280.62  5016.1  283.13  5053.5  291.58  5063.5  292.63  5083.6  293.87
  5103.8  294.49  5113.8   295.5  5133.9  296.26  5154.1  296.99  5174.2  298.35
#Mann= 6 ,-1 , 0
  4754.9     .17       0  4770.2     .15       0  4935.7     .11       0
 4984.07     .07       0  5016.1     .15       0  5133.9     .17       0
Bank Sta=4984.07,5016.1
XS Rating Curve= 0 ,0
Exp/Cntr=0.3,0.1

Type RM Length L Ch R = 1 ,16512   ,464,464,464
BEGIN DESCRIPTION:
CCLC 022 29.0
END DESCRIPTION:
XS GIS Cut Line= 3
      3718567.81     10107711.08      3719173.39     10107527.12
      3719467.85     10107511.07
#Sta/Elev= 30
  4367.1  308.17  4525.5  299.01  4576.2  296.82  4597.1  295.16  4662.3  292.69
  4753.8  288.17  4774.7  286.43  4793.8  286.59    4799  285.47  4806.1  285.27
  4816.5  283.15  4826.7  279.87  4837.4  279.72  4847.9   281.8  4858.3  284.96
  4935.8  286.16  4973.9   285.7  4983.8  282.82    4988  280.26  4992.5   277.2
  5004.7  278.04  5014.4  280.35  5019.4  280.32  5024.5  283.82  5034.5  285.75
  5047.8  285.85  5104.6  288.28  5180.1   293.1  5234.8  296.47  5294.9   301.3
#Mann= 5 ,-1 , 0
  4367.1     .11       0    4988     .07       0  5014.4     .11       0
  5047.8     .15       0  5180.1     .11       0
Bank Sta=4988,5014.4
XS Rating Curve= 0 ,0
Exp/Cntr=0.3,0.1

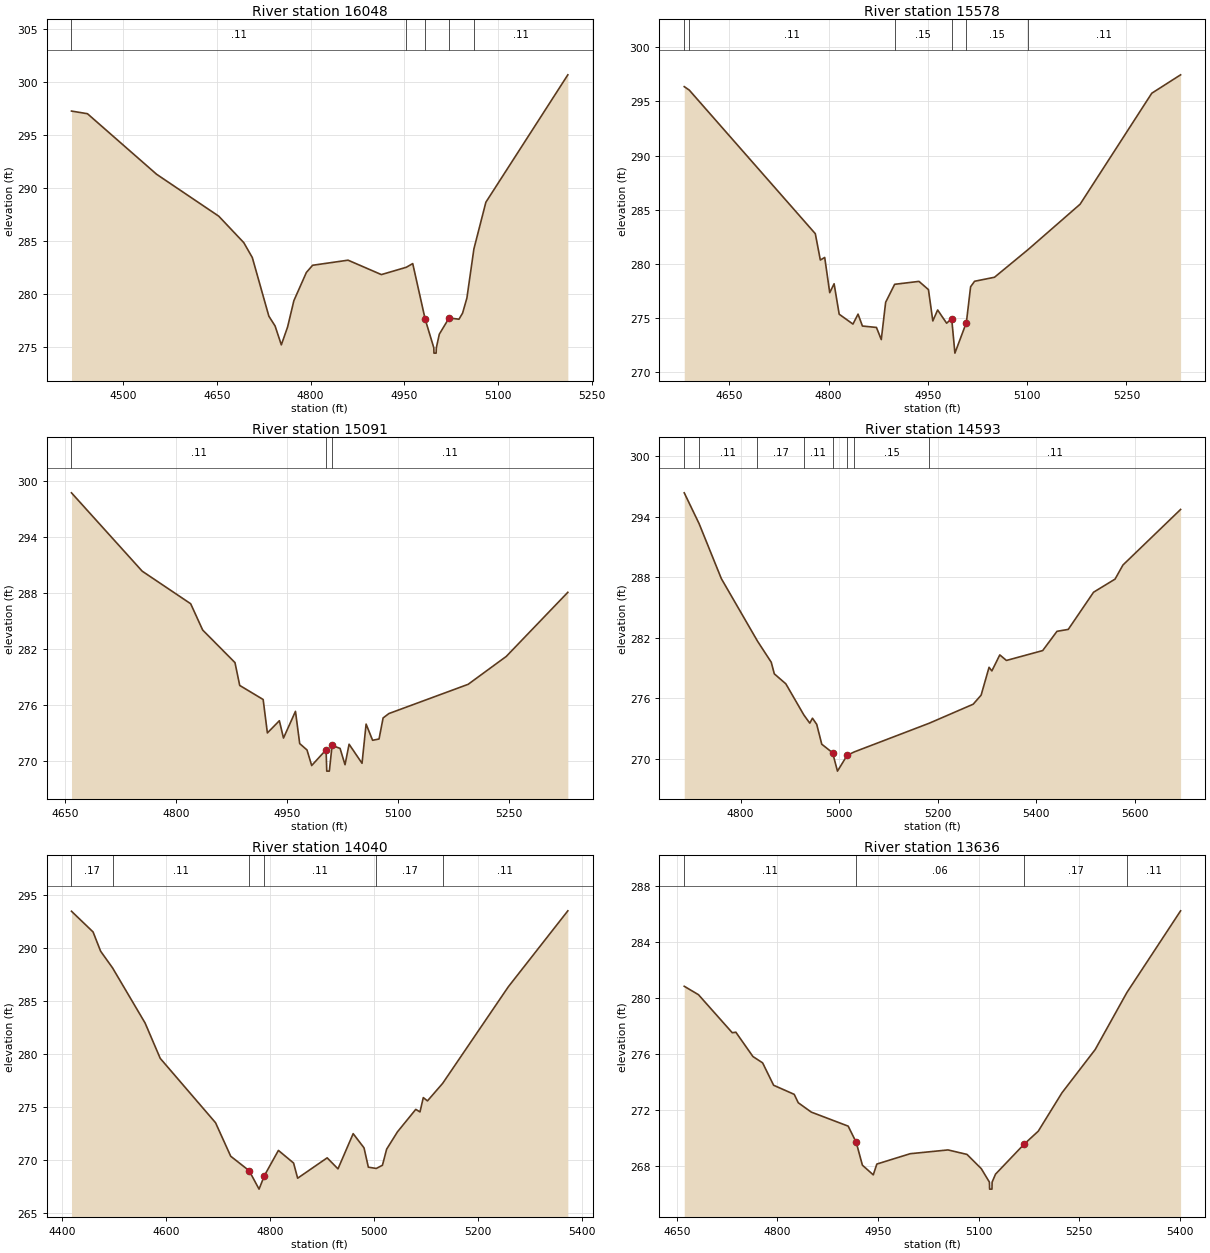
Type RM Length L Ch R = 1 ,16048   ,470,470,470
BEGIN DESCRIPTION:
CCLC 022 28.0
END DESCRIPTION:
XS GIS Cut Line= 3
      3718802.32     10107954.49      3719384.32     10107917.23
      3719567.84     10107811.08
#Sta/Elev= 30
  4416.8  297.27  4442.4  297.02  4553.1  291.31  4652.8  287.35  4692.9  284.85
  4706.5  283.45    4733  277.92    4743  276.99    4753  275.21    4763  276.89
  4773.1  279.38  4793.1  282.04  4803.1  282.72  4859.9   283.2  4913.3  281.84
  4953.2  282.53  4963.5  282.88  4983.5  277.62  4997.3  274.93  4997.5  274.43
    5001  274.43  5001.3  274.93  5006.1  276.22  5021.8  277.75  5037.6  277.63
  5043.4  278.21  5050.3  279.63  5061.5  284.26  5080.7  288.67    5212  300.69
#Mann= 5 ,-1 , 0
  4416.8     .11       0  4953.2     .15       0  4983.5     .09       0
  5021.8     .15       0  5061.5     .11       0
Bank Sta=4983.5,5021.8
XS Rating Curve= 0 ,0
Exp/Cntr=0.3,0.1

Type RM Length L Ch R = 1 ,15578   ,487,487,487
BEGIN DESCRIPTION:
CCLC 022 27.0
END DESCRIPTION:
XS GIS Cut Line= 3
      3719217.87     10108611.05       3719491.1     10108294.31
      3719767.84     10108111.08
#Sta/Elev= 30
  4581.7  296.36  4589.3  296.04  4779.8  282.79  4787.4  280.36    4794   280.6
  4801.6  277.35  4808.2  278.17  4815.9  275.36  4836.7  274.45  4844.4  275.37
    4851  274.27  4872.2  274.14  4879.5  273.02  4886.1  276.46  4899.7  278.12
  4936.5  278.39  4950.8  277.63  4957.4  274.74  4964.7  275.75  4978.3  274.53
  4985.9  274.96  4990.8  271.77  5008.1  274.59  5014.5  277.89  5020.5   278.4
  5050.6  278.77  5101.3  281.32    5180  285.51  5288.3  295.75  5331.9  297.45
#Mann= 6 ,-1 , 0
  4581.7     .17       0  4589.3     .11       0  4899.7     .15       0
  4985.9     .09       0  5008.1     .15       0  5101.3     .11       0
Bank Sta=4985.9,5008.1
XS Rating Curve= 0 ,0
Exp/Cntr=0.3,0.1

Type RM Length L Ch R = 1 ,15091   ,498,498,498
BEGIN DESCRIPTION:
CCLC 022 26.0
END DESCRIPTION:
XS GIS Cut Line= 3
      3719517.84     10108961.09      3719680.68     10108660.46
      3719817.85     10108361.08
#Sta/Elev= 30
  4658.1  298.78  4753.7  290.37  4819.3  286.87  4835.5  284.05  4879.2  280.55
  4885.6   278.1  4917.3  276.59    4923     273  4939.2  274.31  4944.8  272.45
    4961  275.32  4966.7  271.86  4976.6  271.17  4982.9   269.5  5002.4  271.19
  5003.3   268.9  5006.8   268.9  5010.5  271.66  5021.3  271.34    5028  269.59
  5033.5  271.79    5051  269.74  5056.5  273.95  5065.3  272.21    5074  272.35
  5079.5  274.61  5087.3  275.08  5194.5  278.22  5246.1  281.22  5329.3   288.1
#Mann= 3 ,-1 , 0
  4658.1     .11       0  5002.4     .06       0  5010.5     .11       0
Bank Sta=5002.4,5010.5
XS Rating Curve= 0 ,0
Exp/Cntr=0.3,0.1

Type RM Length L Ch R = 1 ,14593   ,553,553,553
BEGIN DESCRIPTION:
CCLC 022 25.0
END DESCRIPTION:
XS GIS Cut Line= 3
      3719667.89     10109111.05      3719960.21     10108994.75
      3720567.82     10108661.09
#Sta/Elev= 30
  4685.4  296.38  4715.5  293.33  4760.7  287.87  4834.1  281.67  4862.1  279.57
  4868.3  278.42  4891.7  277.43  4928.3  274.34  4940.3  273.53  4945.7  274.02
  4954.4  273.41  4964.6  271.44  4986.7  270.59  4996.5  268.77  5016.2  270.34
  5030.8  270.68  5182.7  273.52  5272.1  275.41  5288.2  276.31  5304.3  279.07
    5310  278.71  5326.1   280.3  5339.6  279.75  5413.2  280.73  5442.2  282.64
  5465.1  282.83  5516.5  286.52  5560.1  287.82  5576.2  289.22  5693.2  294.73
#Mann= 8 ,-1 , 0
  4685.4     .17       0  4715.5     .11       0  4834.1     .17       0
  4928.3     .11       0  4986.7     .06       0  5016.2     .11       0
  5030.8     .15       0  5182.7     .11       0
Bank Sta=4986.7,5016.2
XS Rating Curve= 0 ,0
Exp/Cntr=0.3,0.1

Type RM Length L Ch R = 1 ,14040   ,404,404,404
BEGIN DESCRIPTION:
CCLC 022 24.0
END DESCRIPTION:
XS GIS Cut Line= 3
      3719809.23      10109440.6      3720274.51     10109093.38
      3720567.82      10108861.1
#Sta/Elev= 30
  4417.8  293.47  4459.3  291.52  4473.9   289.7  4496.8  288.13  4559.4  282.93
  4588.5   279.6  4694.9  273.53  4724.1  270.37  4759.5  269.01  4778.6  267.27
  4788.7  268.53  4815.8  270.92    4845  269.73  4852.8   268.3  4909.6  270.22
  4930.4  269.18  4959.6   272.5  4980.5  271.16  4988.8  269.34    5004  269.22
  5015.9  269.52    5024  271.04  5044.8  272.67    5080  274.79  5088.1  274.55
  5094.5   275.9  5102.5  275.59  5131.7  277.24  5257.9  286.34  5372.5  293.51
#Mann= 6 ,-1 , 0
  4417.8     .17       0  4496.8     .11       0  4759.5     .06       0
  4788.7     .11       0    5004     .17       0  5131.7     .11       0
Bank Sta=4759.5,4788.7
XS Rating Curve= 0 ,0
Exp/Cntr=0.3,0.1

Type RM Length L Ch R = 1 ,13636   ,478,478,478
BEGIN DESCRIPTION:
CCLC 022 23.0
END DESCRIPTION:
XS GIS Cut Line= 3
      3720117.84     10109561.07      3720436.84     10109446.94
      3720717.88     10109161.04
#Sta/Elev= 30
  4661.2  280.83  4682.4  280.23  4732.8  277.51  4738.1  277.55  4763.6  275.81
    4778  275.36  4794.4  273.76  4825.1  273.11  4831.1  272.51  4850.6  271.84
  4905.5  270.84  4917.5  269.68  4926.7  268.05  4942.9  267.36  4948.2  268.13
  4997.9  268.87  5054.3  269.14  5082.6  268.82  5103.9   267.8    5116  266.84
  5116.3  266.34  5119.8  266.34    5120  266.84  5125.1  267.41  5167.5  269.54
  5188.8  270.48  5224.1  273.22  5273.6  276.31  5320.8  280.38  5400.9  286.22
#Mann= 4 ,-1 , 0
  4661.2     .11       0  4917.5     .06       0  5167.5     .17       0
  5320.8     .11       0
Bank Sta=4917.5,5167.5
XS Rating Curve= 0 ,0
Exp/Cntr=0.3,0.1

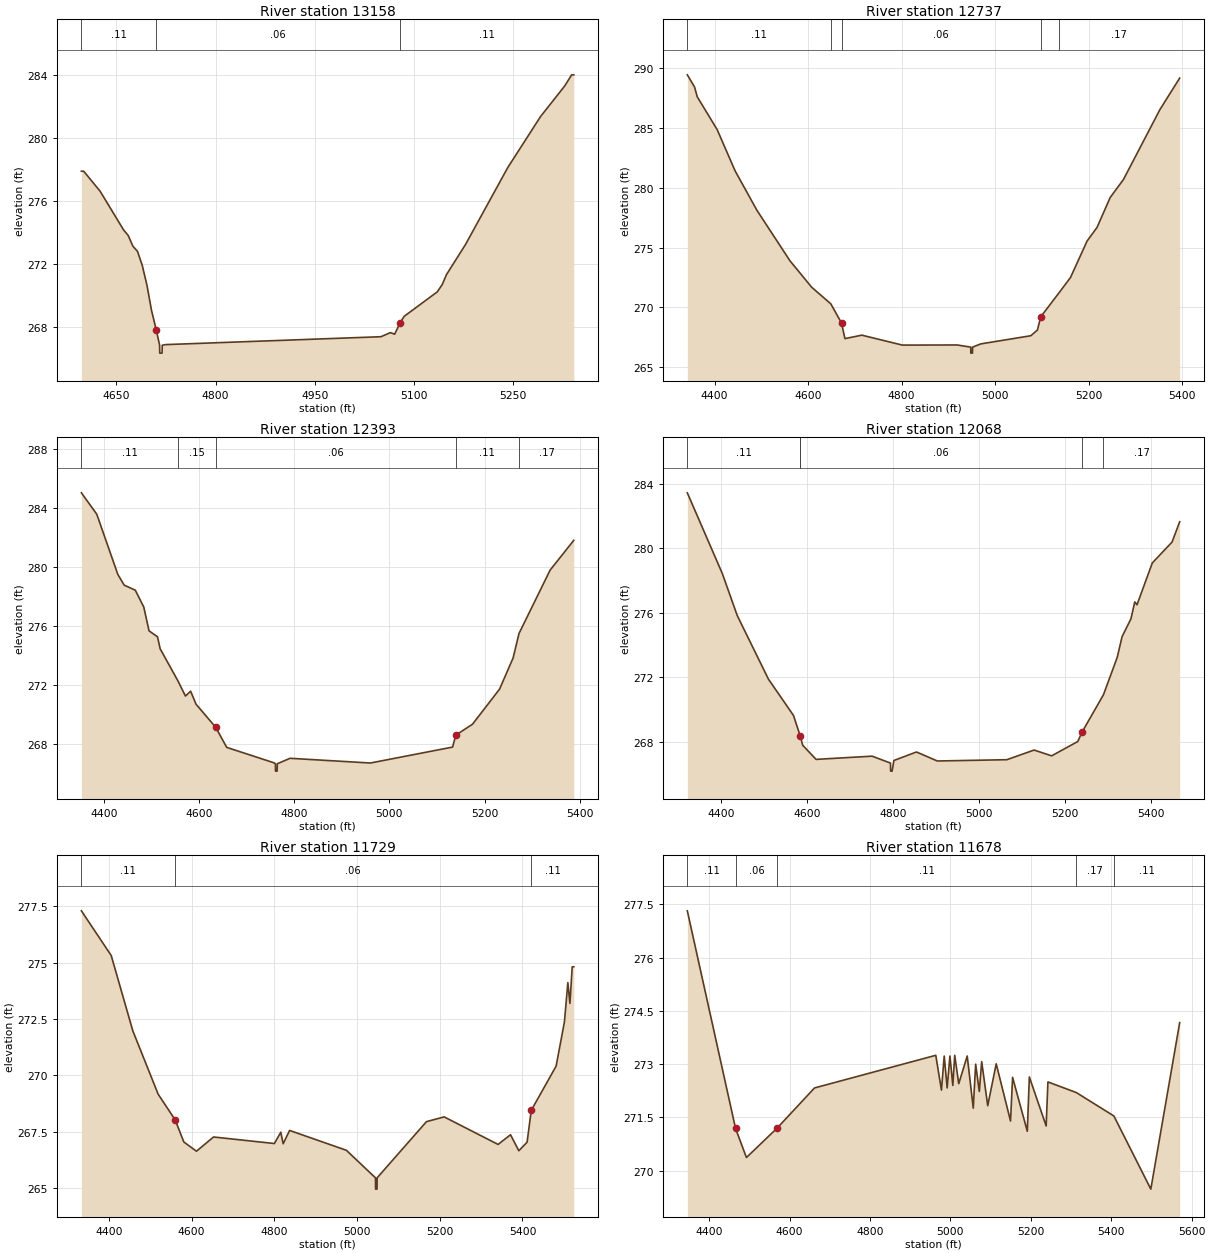
Type RM Length L Ch R = 1 ,13158   ,421,421,421
BEGIN DESCRIPTION:
CCLC 022 22.0
END DESCRIPTION:
XS GIS Cut Line= 3
      3720417.86     10110111.06      3720703.13     10109826.82
      3720967.85     10109611.07
#Sta/Elev= 30
  4597.3   277.9  4600.8   277.9  4625.6  276.63  4660.9  274.19    4668  273.83
  4675.1  273.15  4682.1  272.82  4689.2  271.94  4696.3  270.69  4703.3  269.07
  4710.4  267.85  4715.5  266.87  4715.7  266.37  4719.2  266.37  4719.5  266.87
  4724.5  266.91    5050  267.41  5064.3  267.67  5070.8  267.57  5078.7  268.27
  5085.1   268.7  5135.1  270.25  5142.6  270.71    5149  271.34  5177.8  273.25
  5241.7  278.13  5291.2  281.36  5327.9  283.31  5338.3  284.01  5341.5  284.01
#Mann= 3 , 0 , 0
  4597.3     .11       0  4710.4     .06       0  5078.7     .11       0
Bank Sta=4710.4,5078.7
XS Rating Curve= 0 ,0
Exp/Cntr=0.3,0.1

Type RM Length L Ch R = 1 ,12737   ,344,344,344
BEGIN DESCRIPTION:
CCLC 022 21.0
END DESCRIPTION:
XS GIS Cut Line= 3
      3720367.83     10110361.08      3720986.99     10110137.76
      3721267.88     10109861.05
#Sta/Elev= 30
  4341.8  289.41  4357.2   288.4  4363.1  287.57  4405.6  284.84  4443.9   281.4
  4490.7   278.1  4561.3  273.89  4607.6  271.69  4648.6   270.3  4671.4   268.7
  4678.7   267.4  4714.7  267.69  4801.5  266.86  4918.9  266.87  4947.6  266.69
  4947.8  266.19  4951.3  266.19  4951.6  266.69    4969  266.96    5076  267.64
  5090.2  268.12  5097.3  269.22  5135.9   271.2  5160.9   272.5  5196.3  275.54
  5217.5  276.67  5245.8  279.18    5274  280.67  5351.9   286.5  5394.3  289.14
#Mann= 5 ,-1 , 0
  4341.8     .11       0  4648.6     .15       0  4671.4     .06       0
  5097.3     .11       0  5135.9     .17       0
Bank Sta=4671.4,5097.3
XS Rating Curve= 0 ,0
Exp/Cntr=0.3,0.1

Type RM Length L Ch R = 1 ,12393   ,325,325,325
BEGIN DESCRIPTION:
CCLC 022 20.0
END DESCRIPTION:
XS GIS Cut Line= 3
      3720617.81     10110661.09       3721209.9     10110400.26
      3721467.84     10110111.08
#Sta/Elev= 30
    4353  285.04  4385.3  283.59  4429.5  279.51  4442.9  278.78  4466.2  278.44
  4484.1  277.29  4495.1  275.68  4512.9  275.28  4518.4  274.47  4555.3  272.32
  4571.6  271.26  4582.5  271.59  4593.8  270.71    4635  269.15  4658.3  267.78
  4757.1  266.74  4760.6  266.67  4760.8  266.17  4764.3  266.17  4764.6  266.67
  4791.4  267.04  4960.1  266.72  5132.9   267.8  5139.6  268.61  5174.7  269.35
  5231.6  271.73    5260  273.84  5272.4   275.5  5337.8   279.8  5387.5  281.82
#Mann= 5 ,-1 , 0
    4353     .11       0  4555.3     .15       0    4635     .06       0
  5139.6     .11       0  5272.4     .17       0
Bank Sta=4635,5139.6
XS Rating Curve= 0 ,0
Exp/Cntr=0.3,0.1

Type RM Length L Ch R = 1 ,12068   ,339,339,339
BEGIN DESCRIPTION:
CCLC 022 19.0
END DESCRIPTION:
XS GIS Cut Line= 3
      3720867.89     10110961.05      3721452.02     10110613.71
      3721567.85     10110161.09
#Sta/Elev= 30
  4320.4  283.46  4401.8  278.45  4436.7  275.83  4509.3  271.88  4567.7  269.62
    4582  268.46  4583.3  268.37  4589.1  267.77  4620.3  266.89  4750.8  267.09
  4793.6  266.66  4793.9  266.16  4797.4  266.16  4801.5  266.82  4854.1  267.35
  4902.7  266.79  5064.7  266.87  5128.1  267.47  5168.9  267.11  5229.8     268
  5240.1   268.6  5289.7  270.91  5321.8  273.24    5333  274.52  5353.7  275.63
  5362.6  276.68  5367.8   276.5  5403.4   279.1  5449.4   280.4  5467.2  281.66
#Mann= 5 ,-1 , 0
  4320.4     .11       0    4582     .15       0  4583.3     .06       0
  5240.1     .11       0  5289.7     .17       0
Bank Sta=4583.3,5240.1
XS Rating Curve= 0 ,0
Exp/Cntr=0.3,0.1

Type RM Length L Ch R = 1 ,11729   ,51,51,51
BEGIN DESCRIPTION:
CCLC 022 18.0
END DESCRIPTION:
XS GIS Cut Line= 5
      3721027.97     10111125.39      3721430.76     10111023.94
      3721645.16     10110892.79      3721729.37     10110714.91
      3721753.67     10110388.52
#Sta/Elev= 30
  4333.3  277.29  4405.4  275.31  4457.7  271.97  4518.8  269.17    4560  268.03
    4581  267.05  4611.6  266.64  4652.9  267.27    4800  266.98  4815.5  267.48
  4821.3  266.97  4836.8  267.56  4974.2  266.68  5044.5  265.46  5044.8  264.96
  5048.3  264.96  5048.5  265.46  5167.9  267.95  5210.7  268.16    5341  266.94
  5371.1  267.37  5391.2  266.66  5411.2  267.04  5421.3  268.45  5481.4  270.41
  5501.5  272.37  5509.8  274.11  5514.8  273.19  5520.3  274.81  5524.1  274.81
#Mann= 3 , 0 , 0
  4333.3     .11       0    4560     .06       0  5421.3     .11       0
Bank Sta=4560,5421.3
XS Rating Curve= 0 ,0
Exp/Cntr=0.3,0.1

Type RM Length L Ch R = 1 ,11678   ,105,105,105
BEGIN DESCRIPTION:
Mapping XS b27a9c99
END DESCRIPTION:
XS GIS Cut Line= 6
      3721100.92     10111173.24      3721402.98     10111107.27
      3721698.12     10110909.35      3721753.67     10110826.02
      3721809.23     10110576.02      3721784.92     10110378.11
#Sta/Elev= 30
  4345.8  277.32 4465.76271.1897  4492.8  270.37 4569.53 271.204  4662.1  272.33
  4963.7  273.25  4977.8  272.27  4984.7  273.23    4992  272.33  4998.9  273.23
  5006.1   272.4  5010.8  273.25  5020.8  272.45  5041.9  273.23  5056.9  271.76
  5062.9     273  5071.9  272.23  5077.9  273.07  5092.9  271.83    5114  273.01
  5149.6   271.4  5154.7  272.63  5191.3  271.11  5196.4  272.64  5238.2  271.26
  5242.6   272.5  5313.3   272.2  5406.7  271.54  5498.5  269.48  5570.3  274.17
#Mann= 5 ,-1 , 0
  4345.8     .11       0 4465.76     .06       0 4569.53     .11       0
  5313.3     .17       0  5406.7     .11       0
Bank Sta=4465.76,4569.53
XS Rating Curve= 0 ,0
Exp/Cntr=0.3,0.1

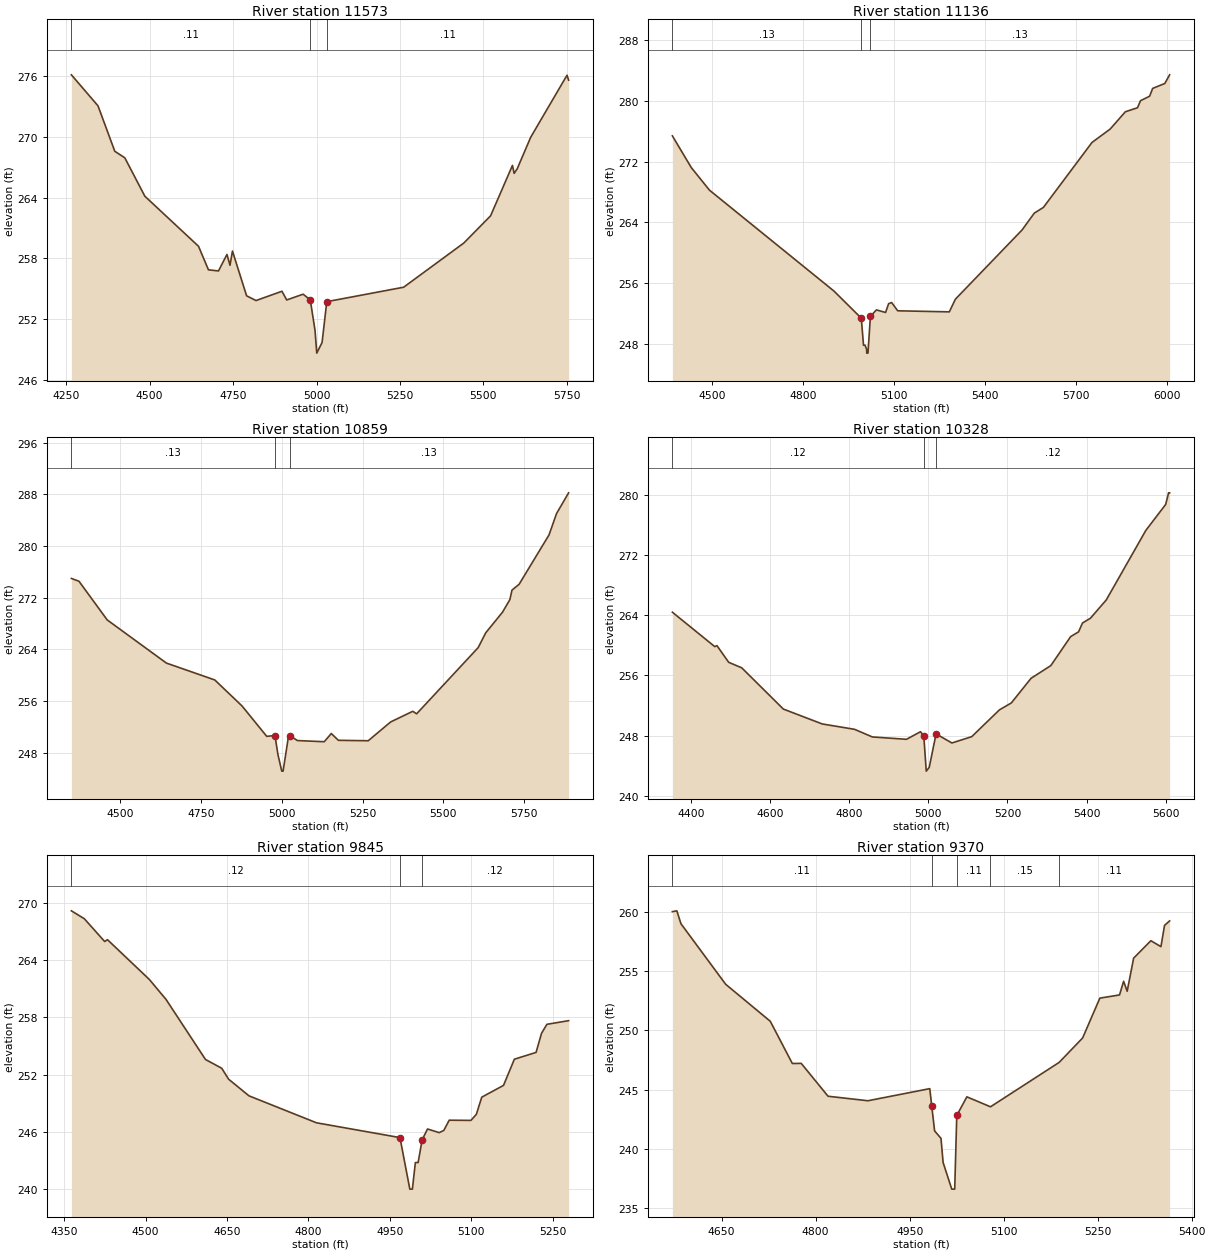
Type RM Length L Ch R = 1 ,11573   ,437,437,437
BEGIN DESCRIPTION:
Mapping XS 0987f22e
END DESCRIPTION:
XS GIS Cut Line= 4
      3721118.24     10111194.08      3721583.53     10111159.35
      3721864.78     10110891.99      3721902.92     10110257.58
#Sta/Elev= 30
  4265.4  276.15  4345.2  273.08  4395.4  268.59  4425.5  267.94  4485.6  264.14
  4646.4  259.19  4676.2  256.86  4706.2  256.75  4731.6  258.38  4740.8  257.31
  4748.1  258.72  4790.5  254.29  4818.8  253.82  4896.5  254.74  4910.7  253.88
    4960  254.45  4981.4  253.88  4995.6  250.87  5000.8  248.62  5016.7  249.67
  5030.8  253.71  5261.2  255.14  5441.5  259.51  5521.7   262.2  5587.3  267.19
  5592.3   266.4  5601.8  266.87  5641.9  269.97  5750.8  276.11  5755.6  275.62
#Mann= 3 , 0 , 0
  4265.4     .11       0  4981.4     .07       0  5030.8     .11       0
Bank Sta=4981.4,5030.8
XS Rating Curve= 0 ,0
Exp/Cntr=0.3,0.1

Type RM Length L Ch R = 1 ,11136   ,277,277,277
BEGIN DESCRIPTION:
CCLC 022 17.0
END DESCRIPTION:
XS GIS Cut Line= 3
      3721215.52     10111336.44      3721847.42     10111343.38
      3722853.62     10111332.97
#Sta/Elev= 30
  4370.5  275.38  4432.8   271.2  4492.8  268.22  4902.9  254.92  4992.9  251.35
  5000.2  247.78  5005.2  247.78  5010.5  247.24  5010.8  246.74  5014.9  246.74
  5022.9   251.6  5042.9  252.44  5072.9   252.1  5082.9  253.26  5092.9  253.41
  5112.9  252.32  5282.9  252.18  5302.9  253.85  5522.9  262.99  5562.9   265.2
  5592.9  265.95  5752.9  274.51  5812.9  276.28  5862.9  278.56  5902.9  279.09
  5912.9  280.02  5942.9  280.61  5952.9  281.64  5992.9  282.29  6008.7  283.43
#Mann= 3 , 0 , 0
  4370.5     .13       0  4992.9     .09       0  5022.9     .13       0
Bank Sta=4992.9,5022.9
XS Rating Curve= 0 ,0
Exp/Cntr=0.3,0.1

Type RM Length L Ch R = 1 ,10859   ,531,531,531
BEGIN DESCRIPTION:
CCLC 022 16.0
END DESCRIPTION:
XS GIS Cut Line= 3
      3721218.92     10111471.85      3721850.89     10111593.38
      3722667.81     10111961.05
#Sta/Elev= 30
  4348.4  274.99  4371.8  274.56  4459.3  268.57  4642.6  261.89  4792.3  259.28
  4876.8  255.25  4953.2  250.55  4978.7  250.68  4987.9  247.72  4999.7  245.17
  5003.8  245.17  5019.5  250.22  5024.9  250.66  5048.1   249.9  5131.2  249.72
  5153.1  250.99    5175  249.94  5267.4  249.87  5336.8  252.78  5405.3  254.43
  5417.3  254.04  5607.9  264.29  5631.1  266.57  5682.9  269.75    5706  271.72
  5712.4  273.18  5734.6  274.09  5827.2  281.73  5850.4  285.03  5887.8  288.24
#Mann= 3 , 0 , 0
  4348.4     .13       0  4978.7     .09       0  5024.9     .13       0
Bank Sta=4978.7,5024.9
XS Rating Curve= 0 ,0
Exp/Cntr=0.3,0.1

Type RM Length L Ch R = 1 ,10328   ,483,483,483
BEGIN DESCRIPTION:
CCLC 022 15.0
END DESCRIPTION:
XS GIS Cut Line= 3
      3721367.86     10112311.07      3721958.23     10112046.84
      3722567.86     10112061.07
#Sta/Elev= 30
  4353.2   264.4  4460.3  259.83  4465.8  259.96  4495.6  257.74  4528.5  257.01
  4633.6  251.53  4731.9  249.55  4813.3  248.84  4858.8  247.82  4944.8  247.51
  4980.3  248.52  4988.6  247.91  4994.8  243.28  5002.3  243.78  5019.6  248.23
  5059.6  247.02  5109.7  247.86  5179.7  251.42  5209.7  252.34  5259.7  255.62
  5309.7  257.31  5359.7  261.16  5379.7  261.79  5389.7  262.97  5409.7   263.6
  5449.7  266.03  5549.8  275.28  5599.8  278.72  5607.3  280.27  5609.8  280.27
#Mann= 3 , 0 , 0
  4353.2     .12       0  4988.6     .08       0  5019.6     .12       0
Bank Sta=4988.6,5019.6
XS Rating Curve= 0 ,0
Exp/Cntr=0.3,0.1

Type RM Length L Ch R = 1 ,9845    ,475,475,475
BEGIN DESCRIPTION:
CCLC 022 14.0
END DESCRIPTION:
XS GIS Cut Line= 3
      3721317.87     10112611.07      3721938.23     10112466.84
      3722217.87     10112461.07
#Sta/Elev= 30
  4363.1  269.13    4387   268.3  4424.4  265.92  4429.6  266.11  4506.8  261.95
  4537.6  259.86  4610.3  253.58  4640.3  252.66  4652.9  251.52  4690.4  249.78
  4814.8  246.96  4968.8  245.41    4987  240.02  4991.7  240.02  4997.2   242.8
  5002.3   242.8  5009.6  245.16  5019.6  246.31  5041.1  245.93  5049.6  246.16
  5059.6  247.23  5099.6  247.21  5109.6  247.84  5119.6  249.64  5159.7  250.87
  5179.7  253.61  5219.7  254.32  5229.7  256.31  5239.7  257.26  5279.7  257.64
#Mann= 3 , 0 , 0
  4363.1     .12       0  4968.8     .08       0  5009.6     .12       0
Bank Sta=4968.8,5009.6
XS Rating Curve= 0 ,0
Exp/Cntr=0.3,0.1

Type RM Length L Ch R = 1 ,9370    ,464,464,464
BEGIN DESCRIPTION:
CCLC 022 13.0
END DESCRIPTION:
XS GIS Cut Line= 3
      3721667.88     10113161.04      3721948.23     10112836.84
      3722267.88     10112661.06
#Sta/Elev= 30
  4571.4     260  4578.5  260.07  4585.1  258.98  4656.4  253.88  4727.6  250.76
  4762.8   247.2    4777  247.21  4819.8  244.44  4883.4  244.06  4982.1  245.08
 4985.22243.6374  4989.8  241.52    5000  240.89  5003.4  238.85  5017.2  236.61
  5021.9  236.61  5025.2  242.82  5041.3  244.39    5079  243.55  5188.5  247.29
    5226  249.35  5253.5  252.71  5284.9  252.98  5291.4  254.13  5297.1  253.29
  5307.4  256.08  5334.9  257.55    5351  257.05  5356.7  258.84  5364.8  259.22
#Mann= 5 ,-1 , 0
  4571.4     .11       0 4985.22     .06       0  5025.2     .11       0
    5079     .15       0  5188.5     .11       0
Bank Sta=4985.22,5025.2
XS Rating Curve= 0 ,0
Exp/Cntr=0.3,0.1

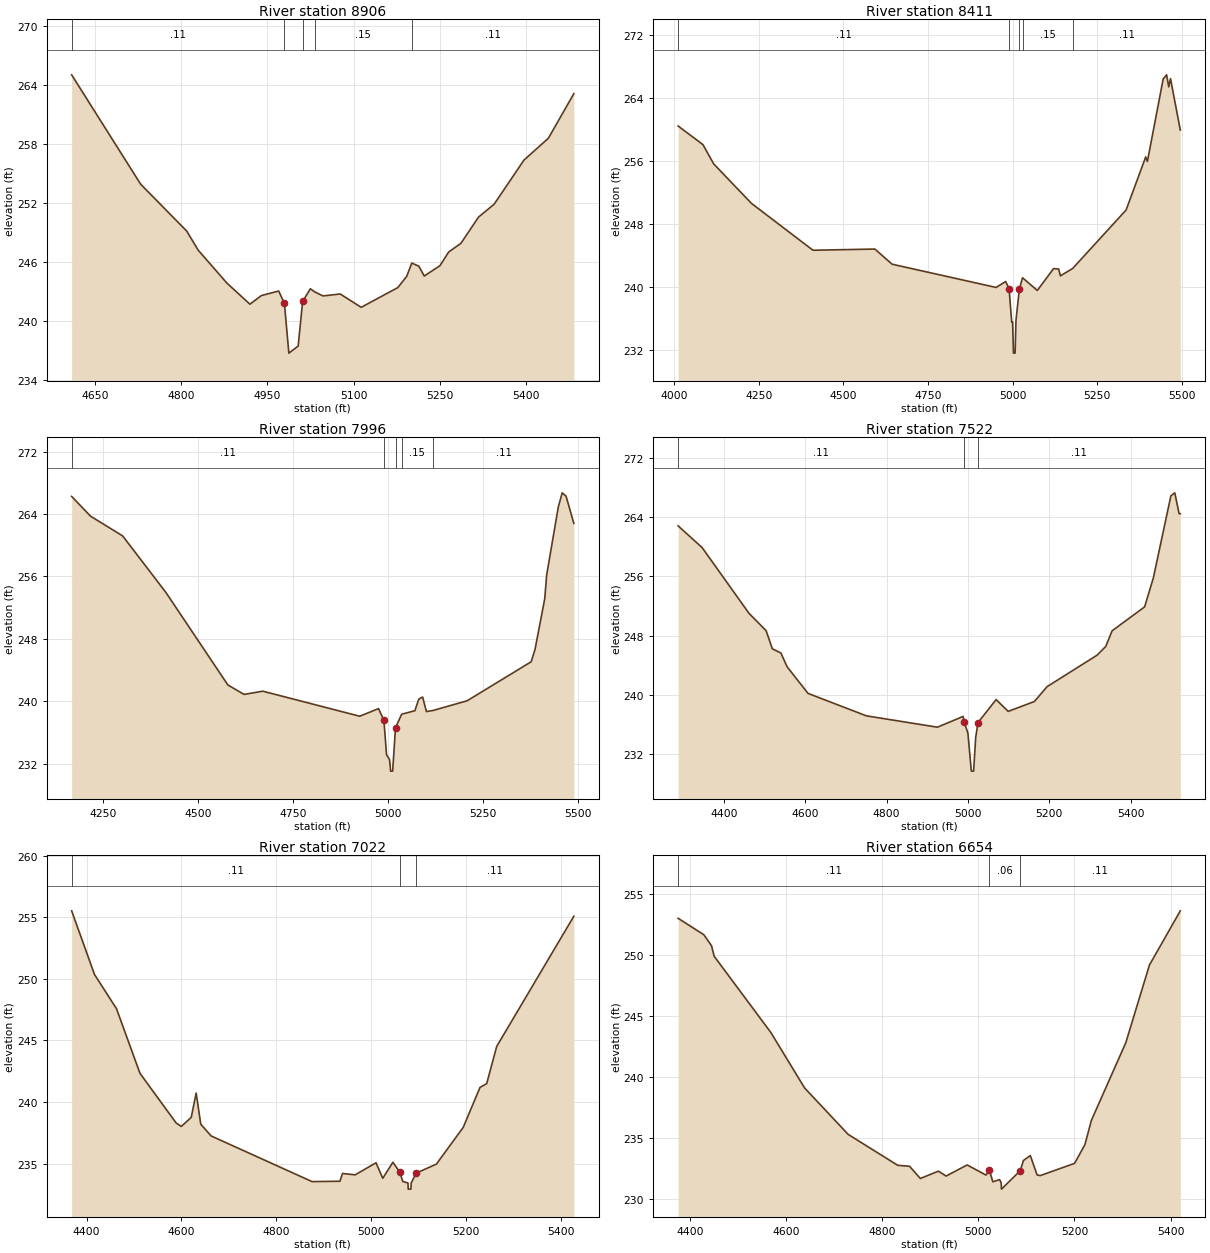
Type RM Length L Ch R = 1 ,8906    ,495,495,495
BEGIN DESCRIPTION:
CCLC 022 12.0
END DESCRIPTION:
XS GIS Cut Line= 3
      3721617.87     10113211.07      3722008.23     10113216.84
      3722417.84     10112961.08
#Sta/Elev= 30
  4609.6  265.07  4729.6  253.92  4809.6  249.15  4829.6   247.2  4879.6  243.84
  4919.6  241.69  4939.6  242.57  4969.6  243.03  4979.6  241.78  4987.3   236.7
  5003.5  237.42  5011.3  241.97  5024.7  243.26  5032.1  242.95  5046.7  242.53
  5076.6  242.73  5113.1  241.37  5176.8  243.38  5192.2  244.52  5201.1  245.88
  5213.4  245.56  5222.8  244.56    5250  245.61  5265.3  247.01  5286.5  247.89
  5317.2  250.57  5344.3  251.88  5396.2  256.38  5438.7  258.61  5482.9  263.15
#Mann= 5 ,-1 , 0
  4609.6     .11       0  4979.6     .06       0  5011.3     .11       0
  5032.1     .15       0  5201.1     .11       0
Bank Sta=4979.6,5011.3
XS Rating Curve= 0 ,0
Exp/Cntr=0.3,0.1

Type RM Length L Ch R = 1 ,8411    ,415,415,415
BEGIN DESCRIPTION:
CCLC 022 11.0
END DESCRIPTION:
XS GIS Cut Line= 3
      3721055.77     10113864.21      3722028.23     10113686.84
       3722517.9     10113611.06
#Sta/Elev= 30
  4011.5  260.46  4084.8   258.1  4116.5  255.66  4228.1  250.65    4410   244.7
    4593  244.85  4643.8  242.93  4951.2  239.98  4979.3  240.73  4989.5  239.84
  4997.3  235.59    5000  235.59  5002.5  231.65  5007.3  231.65  5009.9  235.81
  5019.9  239.76  5029.3  241.21    5073   239.6    5121  242.37    5136  242.32
  5141.3  241.45  5177.4  242.39  5335.3   249.8  5393.3  256.54  5398.3  255.96
  5444.9  266.42    5455  266.95  5461.4  265.42  5466.5  266.47  5495.5  259.95
#Mann= 5 ,-1 , 0
  4011.5     .11       0  4989.5     .06       0  5019.9     .11       0
  5029.3     .15       0  5177.4     .11       0
Bank Sta=4989.5,5019.9
XS Rating Curve= 0 ,0
Exp/Cntr=0.3,0.1

Type RM Length L Ch R = 1 ,7996    ,474,474,474
BEGIN DESCRIPTION:
CCLC 022 10.0
END DESCRIPTION:
XS GIS Cut Line= 3
      3721417.84     10114611.08      3722038.23     10114056.84
      3722517.86     10113961.07
#Sta/Elev= 30
  4168.1  266.25  4217.8  263.72  4302.3  261.19    4416  253.95    4579   242.1
  4621.6  240.89    4671   241.3  4925.9  238.09  4975.3  239.07  4989.5  237.56
  4996.4  233.16  5004.3  232.54  5007.2  231.06  5012.5  231.06    5020  236.62
  5036.2  238.35    5071   238.8  5081.2  240.28  5091.4  240.55  5101.3  238.69
  5118.8  238.83  5208.4  240.07  5376.9  245.07  5387.1  246.67  5412.6  253.16
  5417.7  256.21  5448.3  264.91  5458.5  266.71  5468.7  266.28  5489.1   262.8
#Mann= 5 ,-1 , 0
  4168.1     .11       0  4989.5     .06       0    5020     .11       0
  5036.2     .15       0  5118.8     .11       0
Bank Sta=4989.5,5020
XS Rating Curve= 0 ,0
Exp/Cntr=0.3,0.1

Type RM Length L Ch R = 1 ,7522    ,500,500,500
BEGIN DESCRIPTION:
CCLC 022 9.0
END DESCRIPTION:
XS GIS Cut Line= 3
      3721567.85     10114861.07      3722168.23     10114476.84
      3722617.85     10114211.07
#Sta/Elev= 30
  4287.2  262.79  4346.4  259.85  4461.4  251.01  4503.7  248.66  4518.9  246.23
  4540.1  245.65  4555.3   243.8  4606.8  240.21  4750.2  237.19  4924.8  235.66
  4988.2  237.11 4991.24236.3075    5000  234.84  5008.3  229.74    5014  229.74
  5019.1  234.29  5024.9  236.29  5069.3  239.38    5099  237.79  5163.4  239.12
  5194.6  241.12  5317.5  245.36  5338.9  246.54  5354.6  248.65  5434.5  251.87
    5456  255.77  5499.1  266.83  5508.7  267.24  5519.4  264.43  5522.3  264.43
#Mann= 3 , 0 , 0
  4287.2     .11       0 4991.24     .06       0  5024.9     .11       0
Bank Sta=4991.24,5024.9
XS Rating Curve= 0 ,0
Exp/Cntr=0.3,0.1

Type RM Length L Ch R = 1 ,7022    ,368,368,368
BEGIN DESCRIPTION:
CCLC 022 8.0
END DESCRIPTION:
XS GIS Cut Line= 3
      3721767.83     10115111.08      3722368.91     10114917.12
      3722667.84     10114611.08
#Sta/Elev= 30
  4368.4  255.53  4416.5  250.37    4463  247.58  4512.6  242.33  4589.1  238.29
  4599.6  238.02  4620.6  238.75  4631.1  240.73  4640.8   238.2  4662.6  237.25
  4875.6  233.54  4934.4  233.57  4939.7   234.2  4966.5  234.09  5010.5  235.07
  5024.7  233.81    5046  235.11  5060.1  234.35  5067.1  233.55  5077.9  233.43
  5078.4  232.93  5084.2  232.93  5084.7  233.43  5095.4  234.23  5137.8  234.96
  5194.4  237.94  5229.9  241.19    5244   241.5  5265.1  244.52  5427.8  255.09
#Mann= 3 , 0 , 0
  4368.4     .11       0  5060.1     .06       0  5095.4     .11       0
Bank Sta=5060.1,5095.4
XS Rating Curve= 0 ,0
Exp/Cntr=0.3,0.1

Type RM Length L Ch R = 1 ,6654    ,314,314,314
BEGIN DESCRIPTION:
CCLC 022 7.0
END DESCRIPTION:
XS GIS Cut Line= 3
      3721967.87     10115461.06      3722550.16     10115236.19
      3722867.88     10114961.05
#Sta/Elev= 30
  4375.8  253.01  4429.4  251.66  4445.3  250.76  4450.8   249.9  4568.7  243.66
  4638.9  239.12  4729.5  235.32  4832.6  232.79  4857.2  232.71  4879.6  231.71
  4917.1  232.31  4933.2  231.91    4977  232.82  5016.1  231.99  5023.4  232.37
  5030.4  231.44  5044.6  231.62  5047.8  231.34  5048.3  230.84  5087.4  232.35
    5094  233.18  5108.3  233.59  5122.5     232  5129.2  231.95  5200.4  232.95
  5221.8  234.47  5235.5  236.48  5306.8  242.81  5356.1  249.18  5420.3  253.62
#Mann= 3 , 0 , 0
  4375.8     .11       0  5023.4     .06       0  5087.4     .11       0
Bank Sta=5023.4,5087.4
XS Rating Curve= 0 ,0
Exp/Cntr=0.3,0.1