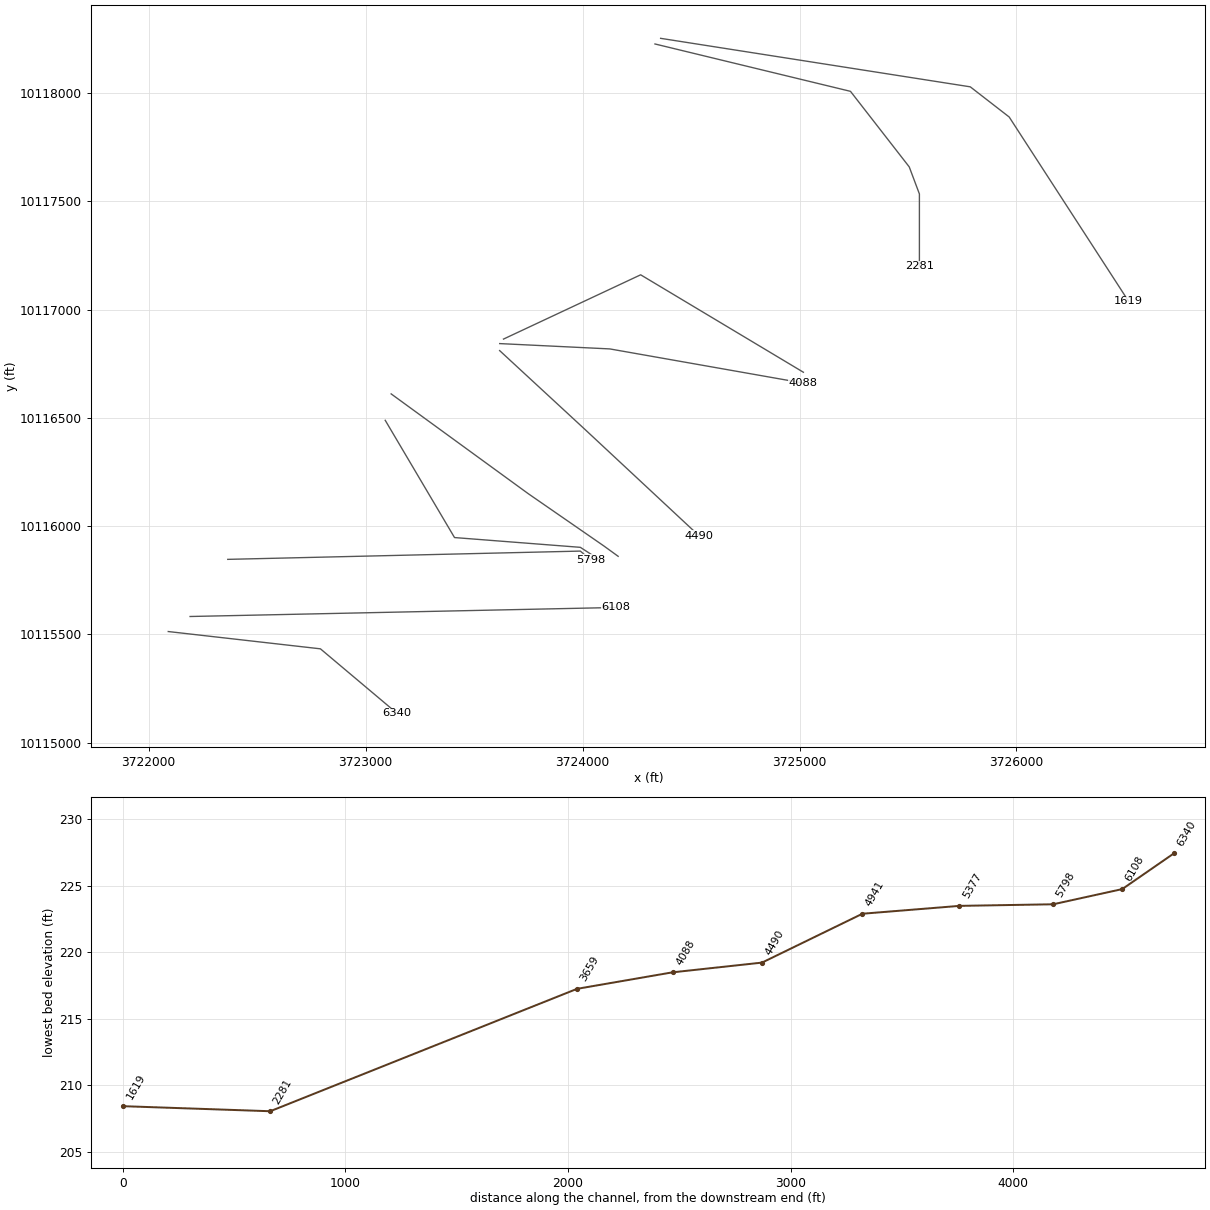
HEC-RAS study CCLC 022.prj: CCLC 022 Base Level Engineering

--- CCLC 022.g01 (geometry) --- (continued)

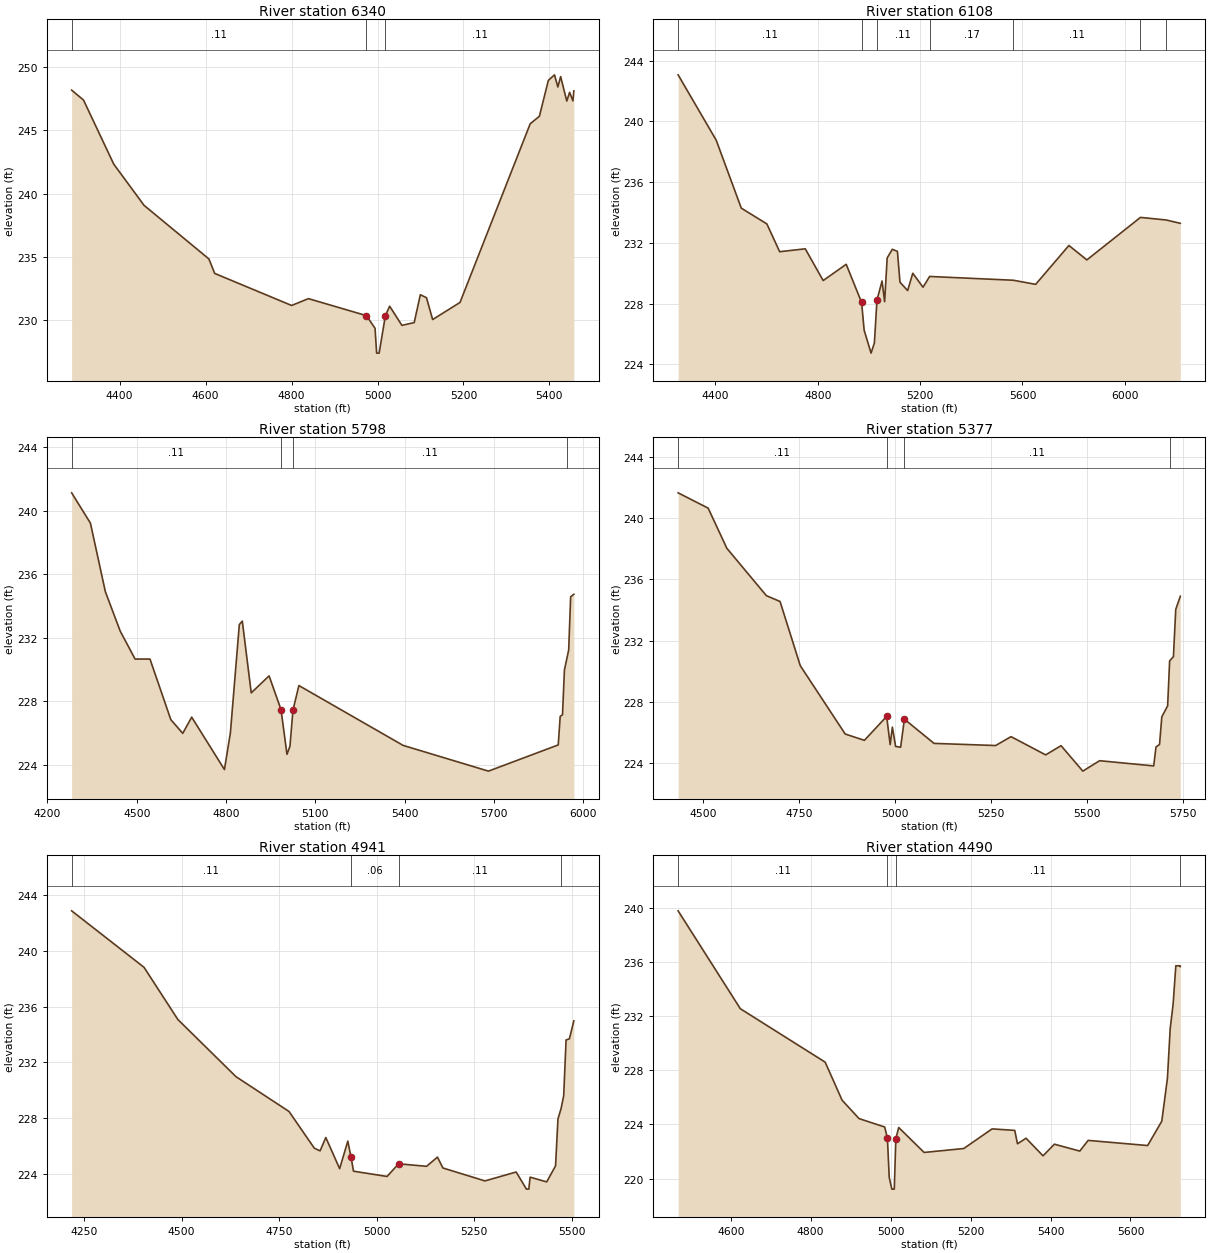
Type RM Length L Ch R = 1 ,6340    ,232,232,232
BEGIN DESCRIPTION:
CCLC 022 6.0
END DESCRIPTION:
XS GIS Cut Line= 3
      3722090.47     10115513.52      3722791.87     10115433.66
      3723145.43     10115135.55
#Sta/Elev= 30
  4288.4  248.17    4316  247.39  4386.4  242.33  4456.9  239.08  4607.8  234.85
  4621.2  233.71  4800.2  231.18  4839.3  231.72  4974.1  230.38  4994.3  229.38
    4998  227.42  5003.8  227.42 5018.42230.3882  5028.3  231.12  5056.8  229.61
  5085.4  229.83  5099.7  232.03    5114  231.79  5128.3  230.07    5192  231.42
  5355.3  245.52  5376.7  246.11  5397.5  248.94  5411.8  249.38  5419.6  248.42
  5426.1  249.24  5440.4  247.31    5447     248  5454.7  247.32  5456.8  248.11
#Mann= 3 , 0 , 0
  4288.4     .11       0  4974.1     .06       0 5018.42     .11       0
Bank Sta=4974.1,5018.42
XS Rating Curve= 0 ,0
Exp/Cntr=0.3,0.1

Type RM Length L Ch R = 1 ,6108    ,310,310,310
BEGIN DESCRIPTION:
Mapping XS e94229c4
END DESCRIPTION:
XS GIS Cut Line= 2
      3722191.15     10115582.97      3724152.91     10115624.63
#Sta/Elev= 30
  4254.5  243.07  4403.5  238.76  4501.3  234.29  4601.3  233.25  4651.3  231.42
  4751.3  231.61  4821.3  229.52  4911.3  230.59  4971.4  228.08  4981.4  226.25
  5008.4  224.74  5021.4  225.41  5031.4  228.23  5051.4  229.49  5061.4  228.13
  5071.4  231.01  5091.4  231.58  5111.4  231.44  5121.4  229.41  5151.4  228.86
  5171.4     230  5211.4  229.08  5237.3  229.79  5564.5  229.54  5651.5  229.27
  5781.5  231.83  5851.6  230.88  6061.1  233.68  6161.2  233.51  6216.7  233.29
#Mann= 7 ,-1 , 0
  4254.5     .11       0  4971.4     .06       0  5031.4     .11       0
  5237.3     .17       0  5564.5     .11       0  6061.1     .15       0
  6161.2     .11       0
Bank Sta=4971.4,5031.4
XS Rating Curve= 0 ,0
Exp/Cntr=0.3,0.1

Type RM Length L Ch R = 1 ,5798    ,421,421,421
BEGIN DESCRIPTION:
Mapping XS 428280cd
END DESCRIPTION:
XS GIS Cut Line= 3
      3722364.79     10115846.85      3723989.78     10115885.05
      3724036.65     10115845.46
#Sta/Elev= 30
  4281.5  241.13  4344.6  239.22  4394.6  234.91  4444.6  232.42  4494.6  230.66
  4544.6  230.66  4614.7  226.84  4654.7  225.98  4684.7     227  4794.7   223.7
  4814.7  226.01  4844.7  232.83  4854.7  233.05  4884.7  228.53  4944.7   229.6
  4984.8  227.47  5004.8  224.66  5014.8  225.17  5024.8  227.43  5044.8  228.99
  5394.9  225.22  5681.5   223.6  5915.9  225.25  5922.5  227.05  5930.2  227.15
  5936.7  229.97  5945.2  230.72    5951  231.23  5957.6  234.58  5968.3  234.74
#Mann= 4 ,-1 , 0
  4281.5     .11       0  4984.8     .06       0  5024.8     .11       0
  5945.2     .15       0
Bank Sta=4984.8,5024.8
XS Rating Curve= 0 ,0
Exp/Cntr=0.3,0.1

Type RM Length L Ch R = 1 ,5377    ,436,436,436
BEGIN DESCRIPTION:
CCLC 022 5.0
END DESCRIPTION:
XS GIS Cut Line= 4
       3723090.5     10116489.18      3723409.92     10115947.55
      3723989.78     10115902.41      3724072.14     10115849.15
#Sta/Elev= 30
  4434.7  241.64    4513  240.64  4561.7  238.02  4664.7  234.93  4700.3  234.55
    4753  230.36  4870.1   225.9  4920.1  225.49  4978.1  227.05  4987.2  225.21
    4993  226.35  5001.4  225.09  5014.5  225.04  5024.3  226.87  5101.5  225.29
    5262  225.15  5302.2  225.73  5392.4  224.54  5432.5  225.14  5489.2  223.48
  5532.9  224.16  5673.9  223.82  5679.9  225.06  5689.1  225.22    5695  227.02
  5710.2  227.74  5715.4  230.67  5725.3  230.95  5731.3  234.03  5743.2  234.89
#Mann= 4 ,-1 , 0
  4434.7     .11       0  4978.1     .06       0  5024.3     .11       0
  5715.4     .15       0
Bank Sta=4978.1,5024.3
XS Rating Curve= 0 ,0
Exp/Cntr=0.3,0.1

Type RM Length L Ch R = 1 ,4941    ,451,451,451
BEGIN DESCRIPTION:
CCLC 022 4.0
END DESCRIPTION:
XS GIS Cut Line= 4
      3723117.86     10116611.07      3723749.75     10116150.22
      3724097.42     10115909.35      3724164.16     10115860.94
#Sta/Elev= 30
  4217.9  242.89  4403.5  238.83  4490.2  235.08  4639.3  230.97  4775.2  228.47
  4840.1  225.83  4854.8  225.64  4869.5   226.6    4905  224.36  4925.9  226.34
  4934.4  225.17  4940.5  224.18  5026.5   223.8  5056.2  224.71  5127.8  224.53
  5155.8  225.19  5169.7  224.41  5277.5  223.48  5357.5  224.12  5383.9  222.89
    5390  222.89  5393.3  223.75  5435.8  223.41  5458.5  224.56  5464.7  227.93
  5472.7  228.68  5479.4  229.61  5485.5  233.61    5494  233.69  5505.4  234.98
#Mann= 4 ,-1 , 0
  4217.9     .11       0  4934.4     .06       0  5056.2     .11       0
  5472.7     .15       0
Bank Sta=4934.4,5056.2
XS Rating Curve= 0 ,0
Exp/Cntr=0.3,0.1

Type RM Length L Ch R = 1 ,4490    ,402,402,402
BEGIN DESCRIPTION:
CCLC 022 3.0
END DESCRIPTION:
XS GIS Cut Line= 3
      3723617.86     10116811.06      3724007.97     10116449.93
      3724537.58     10115955.25
#Sta/Elev= 30
  4468.4  239.78    4624  232.55  4836.3   228.6  4878.6  225.79  4921.1  224.43
  4985.2  223.81    4992  222.99  4996.5  220.09  5003.1  219.22  5009.2  219.22
 5013.03222.9359  5020.3  223.77  5083.8  221.93    5183  222.22  5253.8  223.67
  5310.5  223.56  5317.4  222.57  5338.8  222.98  5381.3  221.68  5409.7  222.54
  5473.2  222.03  5494.2  222.82    5643  222.44  5678.4  224.24  5692.5  227.41
  5699.4  231.07  5706.7  232.88  5713.5  235.72  5724.1  235.72  5724.7  235.66
#Mann= 4 ,-1 , 0
  4468.4     .11       0    4992     .06       0 5013.03     .11       0
  5724.1     .17       0
Bank Sta=4992,5013.03
XS Rating Curve= 0 ,0
Exp/Cntr=0.3,0.1

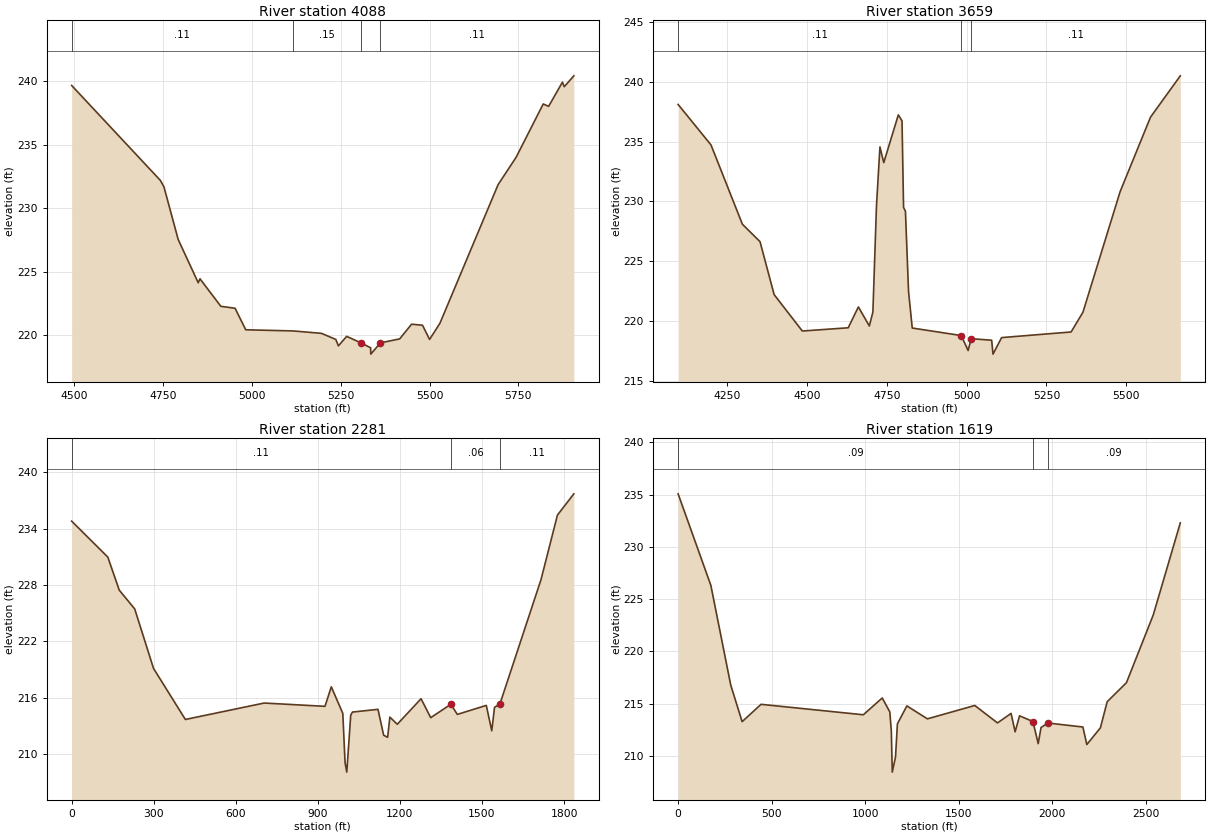
Type RM Length L Ch R = 1 ,4088    ,429,429,429
BEGIN DESCRIPTION:
CCLC 022 2.0
END DESCRIPTION:
XS GIS Cut Line= 3
      3723618.24     10116843.38      3724125.55     10116818.81
      3725017.81     10116661.08
#Sta/Elev= 30
  4492.1  239.68    4742  232.19    4752  231.68  4792.1  227.53  4848.5  224.12
  4853.5  224.43  4912.2  222.26  4952.2  222.11  4982.3  220.41  5115.3  220.32
  5195.3  220.13  5235.9  219.65  5243.2  219.14  5266.4  219.89  5307.5  219.37
  5333.9  218.99  5334.4  218.49  5361.6  219.38  5415.7  219.69  5449.2  220.85
    5480  220.77  5499.9  219.65    5529  220.92  5692.9  231.86  5743.7  234.02
  5819.9  238.22  5835.1  238.03    5874  239.94  5879.1  239.58  5906.1  240.44
#Mann= 4 ,-1 , 0
  4492.1     .11       0  5115.3     .15       0  5307.5     .06       0
  5361.6     .11       0
Bank Sta=5307.5,5361.6
XS Rating Curve= 0 ,0
Exp/Cntr=0.3,0.1

Type RM Length L Ch R = 1 ,3659    ,1378,1378,1378
BEGIN DESCRIPTION:
CCLC 022 1.0
END DESCRIPTION:
XS GIS Cut Line= 3
      3723635.61     10116864.21      3724267.85     10117161.07
      3725017.85     10116711.07
#Sta/Elev= 30
  4096.1   238.1  4199.1  234.72  4297.4   228.1  4352.7  226.64  4396.9  222.22
  4485.2  219.18  4628.9  219.45  4660.8  221.19  4695.1   219.6  4706.2  220.76
  4717.5  229.65  4728.3  234.55  4740.3  233.24  4785.9  237.23  4797.5  236.73
  4802.3   229.5  4808.2  229.18  4817.9   222.5  4829.5  219.43  4983.1   218.8
  5004.5  217.55  5014.2  218.54  5078.3  218.41  5082.5  217.25  5109.4  218.63
  5327.1   219.1  5364.1  220.74  5480.7  230.82  5575.9  237.04  5669.2  240.49
#Mann= 3 , 0 , 0
  4096.1     .11       0  4983.1     .06       0  5014.2     .11       0
Bank Sta=4983.1,5014.2
XS Rating Curve= 0 ,0
Exp/Cntr=0.3,0.1

Type RM Length L Ch R = 1 ,2281    ,662,662,662
XS GIS Cut Line= 5
      3724333.88     10118227.16      3725234.93     10118008.41
      3725505.76     10117659.45      3725552.63     10117534.45
      3725552.63     10117201.12
#Sta/Elev= 30
       0   234.8   132.2  230.97     174  227.45   230.5  225.45   299.3  219.11
   415.7  213.67   703.8  215.42   926.1  215.07   949.2  217.15   991.3  214.31
   999.4  209.08  1005.8  208.06  1020.2  214.13  1026.6  214.46  1119.8  214.75
  1140.6  211.99  1155.1  211.77  1163.3  213.92  1190.4  213.16  1277.3  215.88
  1312.6  213.86  1386.2  215.29  1409.9  214.21  1515.8  215.17  1535.8  212.46
  1545.8  214.96  1565.8  215.34  1715.8  228.57  1775.8  235.44  1835.8  237.71
#Mann= 3 , 0 , 0
       0     .11       0  1386.2     .06       0  1565.8     .11       0
Bank Sta=1386.2,1565.8
XS Rating Curve= 0 ,0
Exp/Cntr=0.3,0.1

Type RM Length L Ch R = 1 ,1619    ,0,0,0
XS GIS Cut Line= 4
      3724359.93      10118253.2      3725787.01     10118029.25
      3725966.38     10117889.92      3726516.18     10117039.66
#Sta/Elev= 30
       0  235.08     175  226.32   281.3  216.77   342.1  213.27   443.3  214.93
   989.9  213.93  1091.1  215.54  1131.6   214.2  1139.6  212.37  1144.7  208.44
    1162   209.9  1172.1  213.06  1222.7  214.78  1332.5  213.54  1585.7  214.82
    1707  213.15  1779.6  214.06  1801.3   212.3    1825  213.83  1896.6  213.28
  1924.7  211.17  1939.8  212.71  1976.1  213.14  2163.5  212.76  2184.6  211.08
  2257.1  212.68  2293.4  215.18  2396.3     217  2539.6  223.48  2684.2   232.3
#Mann= 3 , 0 , 0
       0     .09       0  1896.6     .06       0  1976.1     .09       0
Bank Sta=1896.6,1976.1
XS Rating Curve= 0 ,0
Exp/Cntr=0.3,0.1

Chan Stop Cuts=-1
Use User Specified Reach Order=0
Composite Channel Slope=5