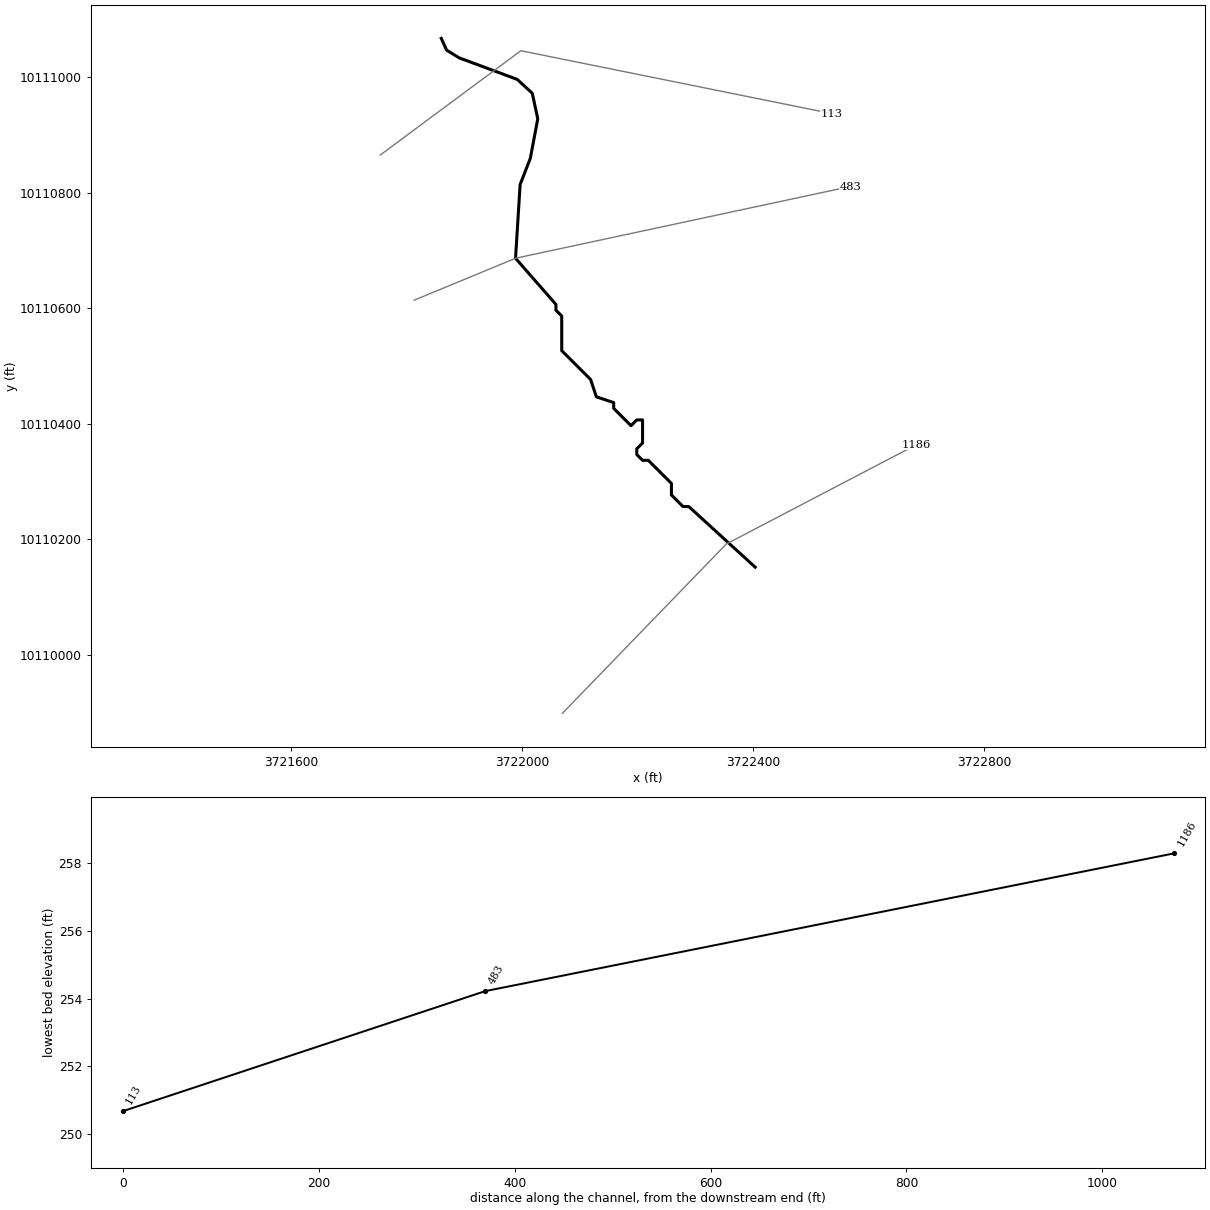
--- CCLC 023.prj (project) ---

Proj Title=CCLC 023 Base Level Engineering
Current Plan=p01
Default Exp/Contr=0.3,0.1
English Units
Geom File=g01
Flow File=f01
Flow File=f02
Plan File=p01
Y Axis Title=Elevation
X Axis Title(PF)=Main Channel Distance
X Axis Title(XS)=Station
BEGIN DESCRIPTION:
CCLC 023
END DESCRIPTION:
DSS Export Rating Curves= 0
DSS Export Rating Curve Sorted= 0
DSS Export Volume Flow Curves= 0
DXF OffsetX= 0
DXF OffsetY= 0
DXF ScaleX= 1
DXF ScaleY= 10

--- CCLC 023.p01 (plan) ---

Plan Title=Multiple Run
Short Identifier=Multiple
Geom File=g01
Flow File=f01
Subcritical Flow
K Sum by GR= 0
Std Step Tol= 0.01
Critical Tol= 0.01
Num of Std Step Trials= 20
Max Error Tol= 0.3
Flow Tol Ratio= 0.001
Split Flow NTrial= 30
Split Flow Tol= 0.02
Split Flow Ratio= 0.02
Log Output Level= 0
Friction Slope Method= 1
Unsteady Friction Slope Method= 2
Unsteady Bridges Friction Slope Method= 1
Parabolic Critical Depth
Global Vel Dist=  1 , 1 , 1
Global Log Level= 0
CheckData=True
Encroach Param= -1, 0, 0, 0
BEGIN DESCRIPTION:
Multiple Run
END DESCRIPTION:

--- CCLC 023.f01 (steady flow) ---

Flow Title=Multiple
Program Version=4.10
Number of Profiles= 7
Profile Names=10-year,25-year,50-year,1pct_min,100-year,1pct_plu,500-year
River Rch & RM=CCLC 023,Reach-1         ,1186
     521     703     948     421    1271    3838    2363
Boundary for River Rch & Prof#=CCLC 023,Reach-1         , 1
Up Type= 0
Dn Type= 3
Dn Slope=0.009
Boundary for River Rch & Prof#=CCLC 023,Reach-1         , 2
Up Type= 0
Dn Type= 3
Dn Slope=0.009
Boundary for River Rch & Prof#=CCLC 023,Reach-1         , 3
Up Type= 0
Dn Type= 3
Dn Slope=0.009
Boundary for River Rch & Prof#=CCLC 023,Reach-1         , 4
Up Type= 0
Dn Type= 3
Dn Slope=0.009
Boundary for River Rch & Prof#=CCLC 023,Reach-1         , 5
Up Type= 0
Dn Type= 3
Dn Slope=0.009
Boundary for River Rch & Prof#=CCLC 023,Reach-1         , 6
Up Type= 0
Dn Type= 3
Dn Slope=0.009
Boundary for River Rch & Prof#=CCLC 023,Reach-1         , 7
Up Type= 0
Dn Type= 3
Dn Slope=0.009
DSS Import GetInterval= 0
DSS Import GetPeak= 0
DSS Import FillOption= 0

--- CCLC 023.f02 (steady flow) ---

Flow Title=Orig_BLE_Flows
Program Version=4.10
Number of Profiles= 7
Profile Names=10-year,25-year,50-year,1pct_min,100-year,1pct_plu,500-year
River Rch & RM=CCLC 023,Reach-1         ,1186
     521     689     824     324     978    2952    1374
Boundary for River Rch & Prof#=CCLC 023,Reach-1         , 1
Up Type= 0
Dn Type= 3
Dn Slope=0.009
Boundary for River Rch & Prof#=CCLC 023,Reach-1         , 2
Up Type= 0
Dn Type= 3
Dn Slope=0.009
Boundary for River Rch & Prof#=CCLC 023,Reach-1         , 3
Up Type= 0
Dn Type= 3
Dn Slope=0.009
Boundary for River Rch & Prof#=CCLC 023,Reach-1         , 4
Up Type= 0
Dn Type= 3
Dn Slope=0.009
Boundary for River Rch & Prof#=CCLC 023,Reach-1         , 5
Up Type= 0
Dn Type= 3
Dn Slope=0.009
Boundary for River Rch & Prof#=CCLC 023,Reach-1         , 6
Up Type= 0
Dn Type= 3
Dn Slope=0.009
Boundary for River Rch & Prof#=CCLC 023,Reach-1         , 7
Up Type= 0
Dn Type= 3
Dn Slope=0.009
DSS Import GetInterval= 0
DSS Import GetPeak= 0
DSS Import FillOption= 0

--- CCLC 023.g01 (geometry) ---

Geom Title=Existing Conditions
Program Version=4.10

River Reach=CCLC 023        ,Reach-1
Reach XY= 30
      3722403.23     10110151.84      3722288.23     10110256.84
      3722278.23     10110256.84      3722258.23     10110276.84
      3722258.23     10110296.84      3722218.23     10110336.84
      3722208.23     10110336.84      3722198.23     10110346.84
      3722198.23     10110356.84      3722208.23     10110366.84
      3722208.23     10110406.84      3722198.23     10110406.84
      3722188.23     10110396.84      3722158.23     10110426.84
      3722158.23     10110436.84      3722128.23     10110446.84
      3722118.23     10110476.84      3722068.23     10110526.84
      3722068.23     10110586.84      3722058.23     10110596.84
      3722058.23     10110606.84      3721988.23     10110686.84
      3721996.17     10110814.42      3722013.83     10110859.82
      3722026.72     10110928.28      3722017.25     10110972.62
      3721991.09     10110996.64      3721890.67     10111033.87
       3721868.8     10111047.33      3721859.58     10111067.71

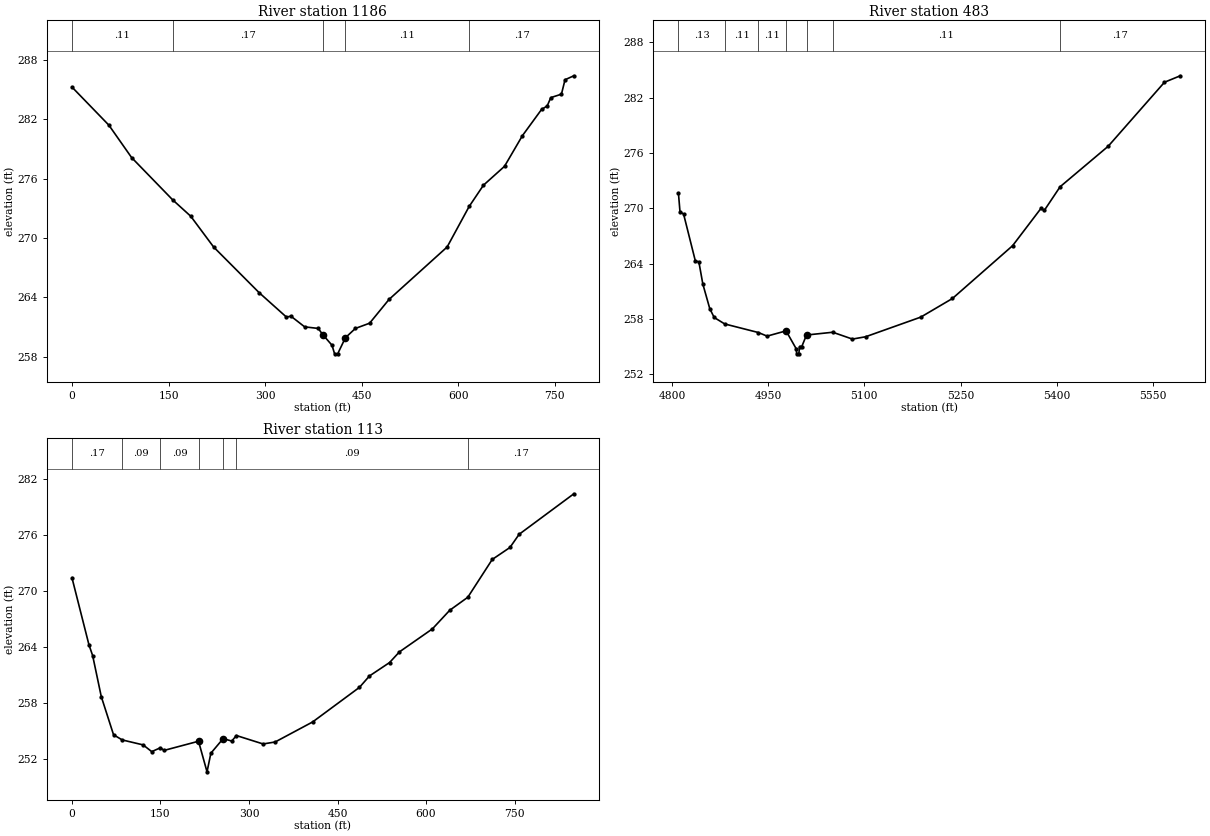
Type RM Length L Ch R = 1 ,1186    ,703,703,703
BEGIN DESCRIPTION:
CCLC 023 2.0
END DESCRIPTION:
XS GIS Cut Line= 3
      3722069.32     10109898.59      3722353.19     10110191.89
      3722682.28     10110363.81
#Sta/Elev= 30
       0  285.27    57.4  281.41    92.6  278.14   156.4  273.86   184.5   272.2
     220  269.09   290.7  264.47   333.1     262   340.1  262.09   361.4  261.01
   382.5  260.85   389.7  260.21   403.9  259.15   407.9  258.28   412.7  258.28
   424.7  259.91   440.2  260.85   462.3  261.38   492.4  263.78   582.7  269.09
   616.9  273.19   639.1  275.34   671.8  277.25   699.6  280.35   729.3     283
   738.1  283.36   743.7   284.2   760.2  284.55   765.8  286.01   779.5  286.41
#Mann= 5 ,-1 , 0
       0     .11       0   156.4     .17       0   389.7     .09       0
   424.7     .11       0   616.9     .17       0
Bank Sta=389.7,424.7
XS Rating Curve= 0 ,0
Exp/Cntr=0.3,0.1

Type RM Length L Ch R = 1 ,483     ,370,370,370
BEGIN DESCRIPTION:
CCLC 023 1.0
END DESCRIPTION:
XS GIS Cut Line= 3
      3721812.67      10110614.2      3721988.23     10110686.84
      3722567.87     10110811.07
#Sta/Elev= 30
    4810  271.67  4812.5  269.59    4818  269.39  4836.4  264.29  4841.9  264.19
  4848.1  261.78  4858.9  259.12  4865.8  258.16  4882.2  257.46  4934.7  256.53
  4948.3  256.14  4977.9  256.71  4994.1  254.72  4994.3  254.22  4997.8  254.22
    4999  255.01  5002.4  255.01  5009.8  256.26  5050.7  256.56  5081.4  255.82
  5101.9  256.07    5188   258.2  5237.4  260.22  5331.2  265.94  5375.5  269.99
  5380.6  269.76  5405.3  272.33  5480.3  276.72  5568.1  283.66  5592.8  284.36
#Mann= 7 ,-1 , 0
    4810     .13       0  4882.2     .11       0  4934.7     .11       0
  4977.9     .06       0  5009.8     .11       0  5050.7     .11       0
  5405.3     .17       0
Bank Sta=4977.9,5009.8
XS Rating Curve= 0 ,0
Exp/Cntr=0.3,0.1

Type RM Length L Ch R = 1 ,113     ,0,0,0
BEGIN DESCRIPTION:
CCLC 023 0.5
END DESCRIPTION:
XS GIS Cut Line= 3
      3721754.03     10110865.66      3721997.49     10111046.27
      3722535.17     10110937.53
#Sta/Elev= 30
       0  271.43    28.8  264.26    35.1   263.1    49.7  258.72    70.5  254.64
    85.2  254.09   120.6  253.56   135.2  252.84   149.8  253.25   156.1  252.97
   214.5  253.95   228.9  250.68   235.4  252.67   256.2  254.23   270.8  253.97
   278.7  254.56   323.9  253.66   344.3  253.87   407.8  256.01   487.2  259.71
   504.2  260.93   538.2  262.36   554.9   263.5   610.8  265.96   640.2  267.95
   670.8  269.34   712.2  273.38   742.2  274.66   757.8  276.07   850.5   280.4
#Mann= 7 ,-1 , 0
       0     .17       0    85.2     .09       0   149.8     .09       0
   214.5     .06       0   256.2     .09       0   278.7     .09       0
   670.8     .17       0
Bank Sta=214.5,256.2
XS Rating Curve= 0 ,0
Exp/Cntr=0.3,0.1

Chan Stop Cuts=-1
Use User Specified Reach Order=0
Composite Channel Slope=5