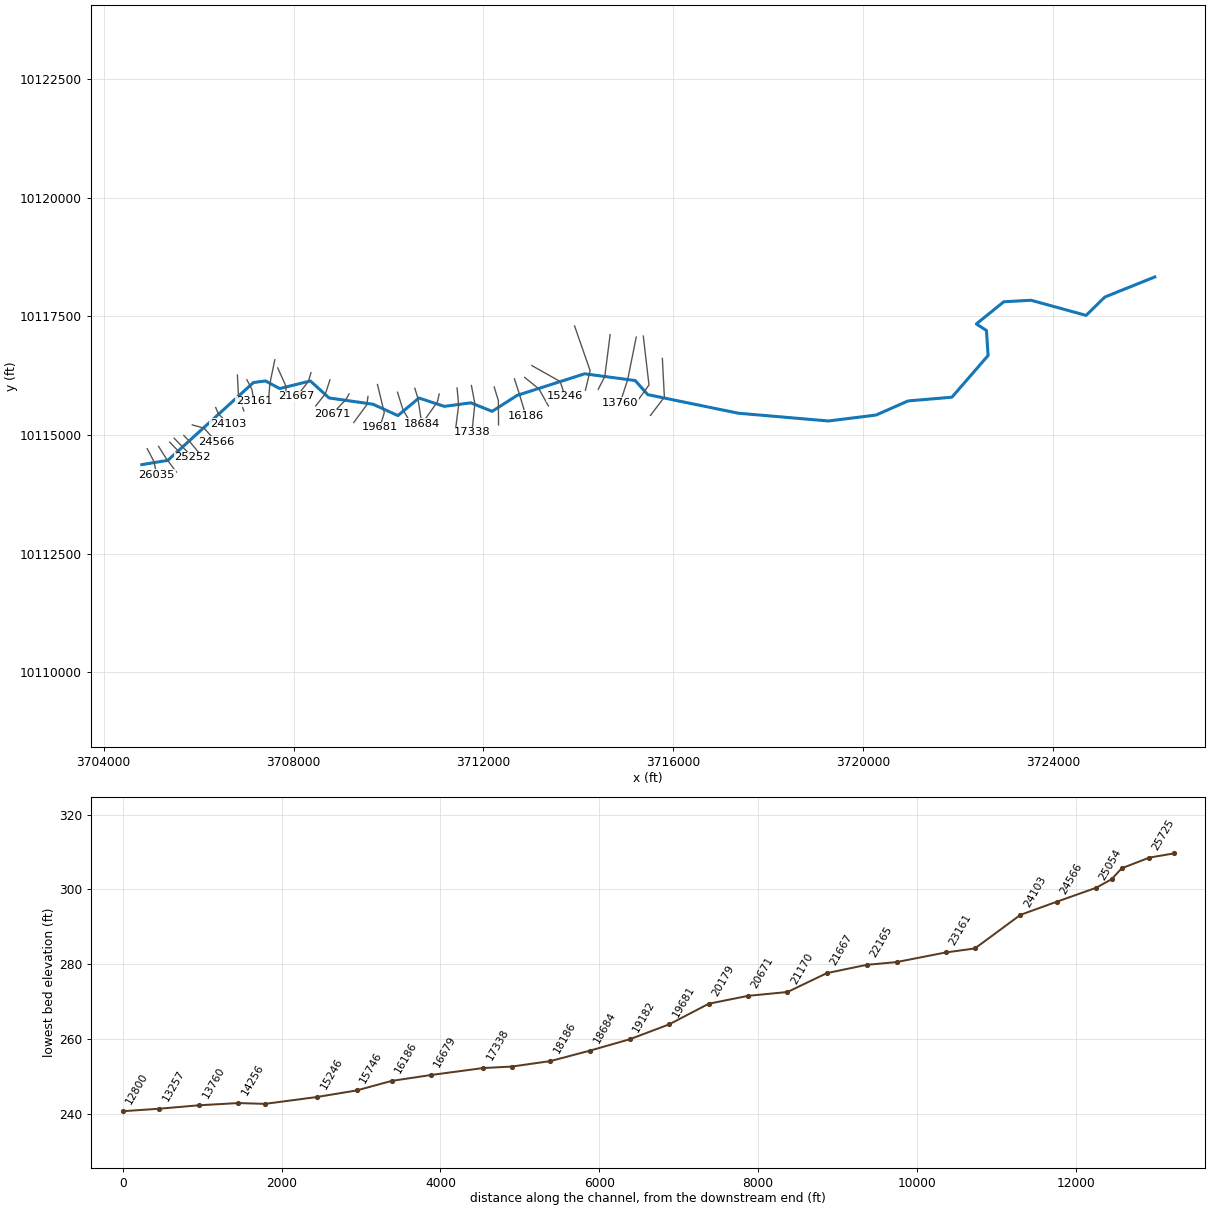
--- CCLC 024.prj (project) ---

Proj Title=CCLC 024 Base Level Engineering
Current Plan=p01
Default Exp/Contr=0.3,0.1
English Units
Geom File=g01
Flow File=f01
Flow File=f02
Plan File=p01
Y Axis Title=Elevation
X Axis Title(PF)=Main Channel Distance
X Axis Title(XS)=Station
BEGIN DESCRIPTION:
CCLC 024
END DESCRIPTION:
DSS Export Rating Curves= 0
DSS Export Rating Curve Sorted= 0
DSS Export Volume Flow Curves= 0
DXF OffsetX= 0
DXF OffsetY= 0
DXF ScaleX= 1
DXF ScaleY= 10

--- CCLC 024.p01 (plan) ---

Plan Title=Multiple Run
Program Version=4.10
Short Identifier=Multiple
Geom File=g01
Flow File=f01
Subcritical Flow
K Sum by GR= 0
Std Step Tol= 0.01
Critical Tol= 0.01
Num of Std Step Trials= 20
Max Error Tol= 0.3
Flow Tol Ratio= 0.001
Split Flow NTrial= 30
Split Flow Tol= 0.02
Split Flow Ratio= 0.02
Log Output Level= 0
Friction Slope Method= 1
Unsteady Friction Slope Method= 2
Unsteady Bridges Friction Slope Method= 1
Parabolic Critical Depth
Global Vel Dist= 1 , 1 , 1
Global Log Level= 0
CheckData=True
Encroach Param=-1 ,0,0, 0
BEGIN DESCRIPTION:
Multiple Run
END DESCRIPTION:
Computation Interval=1HOUR
Output Interval=1HOUR
Run HTab= 0
Run UNet= 0
Run PostProcess= 0
Run WQNet= 0
UNET Theta= 1
UNET Theta Warmup= 1
UNET ZTol= 0.02
UNET ZSATol= 0.05
UNET MxIter= 20
UNET MaxInSteps= 0
UNET DtIC= 0
UNET DtMin= 0
UNET MaxCRTS= 20
UNET WFStab= 2
UNET SFStab= 1
UNET WFX= 1
UNET SFX= 1
UNET DSS MLevel= 4
UNET DZMax Abort= 100
UNET Convert EG Bridges= 0
UNET Use Existing IB Tables=-1
UNET Froude Reduction=False
UNET Froude Limit= 1
UNET Froude Power= 10
UNET Time Slicing=0,0, 5
UNET Junction Losses=0
Instantaneous Interval=1HOUR
Write IC File= 0
Write IC File at Sim End=0
Echo Input=False
Echo Parameters=False
Echo Output=False
Write Detailed= 0
WQ AD Non Conservative
WQ ULTIMATE=-1
WQ Max Comp Step=1HOUR
WQ Output Interval=15MIN
WQ Output Selected Increments= 0
WQ Output face flow=0
WQ Output face velocity=0
WQ Output face area=0
WQ Output face dispersion=0
WQ Output cell volume=0
WQ Output cell surface area=0
WQ Output cell continuity=0
WQ Output cumulative cell continuity=0
WQ Output face conc=0
WQ Output face dconc_dx=0
WQ Output face courant=0
WQ Output face peclet=0
WQ Output face adv mass=0
WQ Output face disp mass=0
WQ Output cell mass=0
WQ Output cell source sink temp=0
WQ Output cell source sink nsm=0
WQ Output MaxMinRange=-1
WQ Daily Max Min Mean=-1
WQ Daily Range=0
WQ Daily Time=0
WQ Create Restart=0
WQ Fixed Restart=0
WQ System Summary=0
WQ Use Fixed Temperature=0
Sorting and Armoring Iterations= 10
XS Update Threshold= 0.02
Hydraulics Update Threshold= 0.02
Energy Slope Method= 1
Volume Change Method= 0
XS Weighting Method= 0
Number of US Weighted Cross Sections= 1
Number of DS Weighted Cross Sections= 1
Upstream XS Weight=0.25
Main XS Weight=0.5
Downstream XS Weight=0.25
Number of DS XS's Weighted with US Boundary= 1
Upstream Boundary Weight= 1
Weight of XSs Associated with US Boundary= 0
Number of US XS's Weighted with DS Boundary= 1
Downstream Boundary Weight= 0.5
Weight of XSs Associated with DS Boundary= 0.5
Sediment Output Level= 4
Mass or Volume Output= 0
Output Increment Type= 1
Profile and TS Output Increment= 10
XS Output Flag= 0
XS Output Increment= 10
Disregard all LS=0
Disregard all Conn=0
Disregard all Breaches=0
Disregard all Pumps=0

--- CCLC 024.f01 (steady flow) ---

Flow Title=Multiple
Program Version=4.10
Number of Profiles= 7
Profile Names=10-year,25-year,50-year,1pct_min,100-year,1pct_plu,500-year
River Rch & RM=CCLC 024,Reach-1         ,26035
     811    1125    1547     700    2113    6381    4075
River Rch & RM=CCLC 024,Reach-1         ,23530
    1261    1782    2477    1131    3415   10313    6720
River Rch & RM=CCLC 024,Reach-1         ,14591
    1580    2239    3118    1424    4299   12983    8461
River Rch & RM=CCLC 024,Reach-1         ,10304
    2480    3578    5044    2328    7029   21227   14135
River Rch & RM=CCLC 024,Reach-1         ,4035
    2767    4000    5648    2608    7877   23788   15869
River Rch & RM=CCLC 024,Reach-1         ,1585
    4122    5900    8273    3798   11470   34639   22840
Boundary for River Rch & Prof#=CCLC 024,Reach-1         , 1
Up Type= 0
Dn Type= 3
Dn Slope=0.006
Boundary for River Rch & Prof#=CCLC 024,Reach-1         , 2
Up Type= 0
Dn Type= 3
Dn Slope=0.006
Boundary for River Rch & Prof#=CCLC 024,Reach-1         , 3
Up Type= 0
Dn Type= 3
Dn Slope=0.006
Boundary for River Rch & Prof#=CCLC 024,Reach-1         , 4
Up Type= 0
Dn Type= 3
Dn Slope=0.006
Boundary for River Rch & Prof#=CCLC 024,Reach-1         , 5
Up Type= 0
Dn Type= 3
Dn Slope=0.006
Boundary for River Rch & Prof#=CCLC 024,Reach-1         , 6
Up Type= 0
Dn Type= 3
Dn Slope=0.006
Boundary for River Rch & Prof#=CCLC 024,Reach-1         , 7
Up Type= 0
Dn Type= 3
Dn Slope=0.006
DSS Import GetInterval= 0
DSS Import GetPeak= 0
DSS Import FillOption= 0

--- CCLC 024.f02 (steady flow) ---

Flow Title=Orig_BLE_Flows
Program Version=4.10
Number of Profiles= 7
Profile Names=10-year,25-year,50-year,1pct_min,100-year,1pct_plu,500-year
River Rch & RM=CCLC 024,Reach-1         ,26035
     811    1103    1345     538    1625    4907    2369
River Rch & RM=CCLC 024,Reach-1         ,23530
    1261    1747    2154     870    2627    7935    3907
River Rch & RM=CCLC 024,Reach-1         ,14591
    1580    2195    2711    1095    3307    9986    4919
River Rch & RM=CCLC 024,Reach-1         ,10304
    2480    3508    4386    1790    5407   16328    8218
River Rch & RM=CCLC 024,Reach-1         ,4035
    2767    3922    4911    2006    6059   18299    9226
River Rch & RM=CCLC 024,Reach-1         ,1585
    4122    5784    7194    2921    8823   26647   13279
Boundary for River Rch & Prof#=CCLC 024,Reach-1         , 1
Up Type= 0
Dn Type= 3
Dn Slope=0.006
Boundary for River Rch & Prof#=CCLC 024,Reach-1         , 2
Up Type= 0
Dn Type= 3
Dn Slope=0.006
Boundary for River Rch & Prof#=CCLC 024,Reach-1         , 3
Up Type= 0
Dn Type= 3
Dn Slope=0.006
Boundary for River Rch & Prof#=CCLC 024,Reach-1         , 4
Up Type= 0
Dn Type= 3
Dn Slope=0.006
Boundary for River Rch & Prof#=CCLC 024,Reach-1         , 5
Up Type= 0
Dn Type= 3
Dn Slope=0.006
Boundary for River Rch & Prof#=CCLC 024,Reach-1         , 6
Up Type= 0
Dn Type= 3
Dn Slope=0.006
Boundary for River Rch & Prof#=CCLC 024,Reach-1         , 7
Up Type= 0
Dn Type= 3
Dn Slope=0.006
DSS Import GetInterval= 0
DSS Import GetPeak= 0
DSS Import FillOption= 0

--- CCLC 024.g01 (geometry) ---

Geom Title=Existing Conditions
Program Version=4.10

River Reach=CCLC 024        ,Reach-1
Reach XY= 30
      3704804.81     10114374.16      3705351.69     10114464.01
      3707155.24     10116102.98      3707408.69     10116137.01
      3707708.73     10115976.47      3708354.12     10116136.23
      3708748.85     10115778.68      3709675.02     10115645.83
      3710198.61     10115406.54      3710640.96       10115777.
        3711177.     10115601.24      3711732.99     10115676.08
       3712182.9     10115496.93      3712710.43     10115833.04
      3714129.18       10116287.      3715195.69     10116145.34
      3715460.74     10115848.32      3717366.29     10115457.26
      3719267.39     10115293.31      3720269.82     10115418.67
      3720942.48     10115715.97       3721865.4     10115794.05
      3722627.63     10116671.67      3722593.42     10117199.34
      3722380.75     10117337.22      3722958.31     10117804.38
       3723532.1     10117836.21      3724692.08     10117517.46
      3725086.62     10117903.76      3726138.23     10118326.84

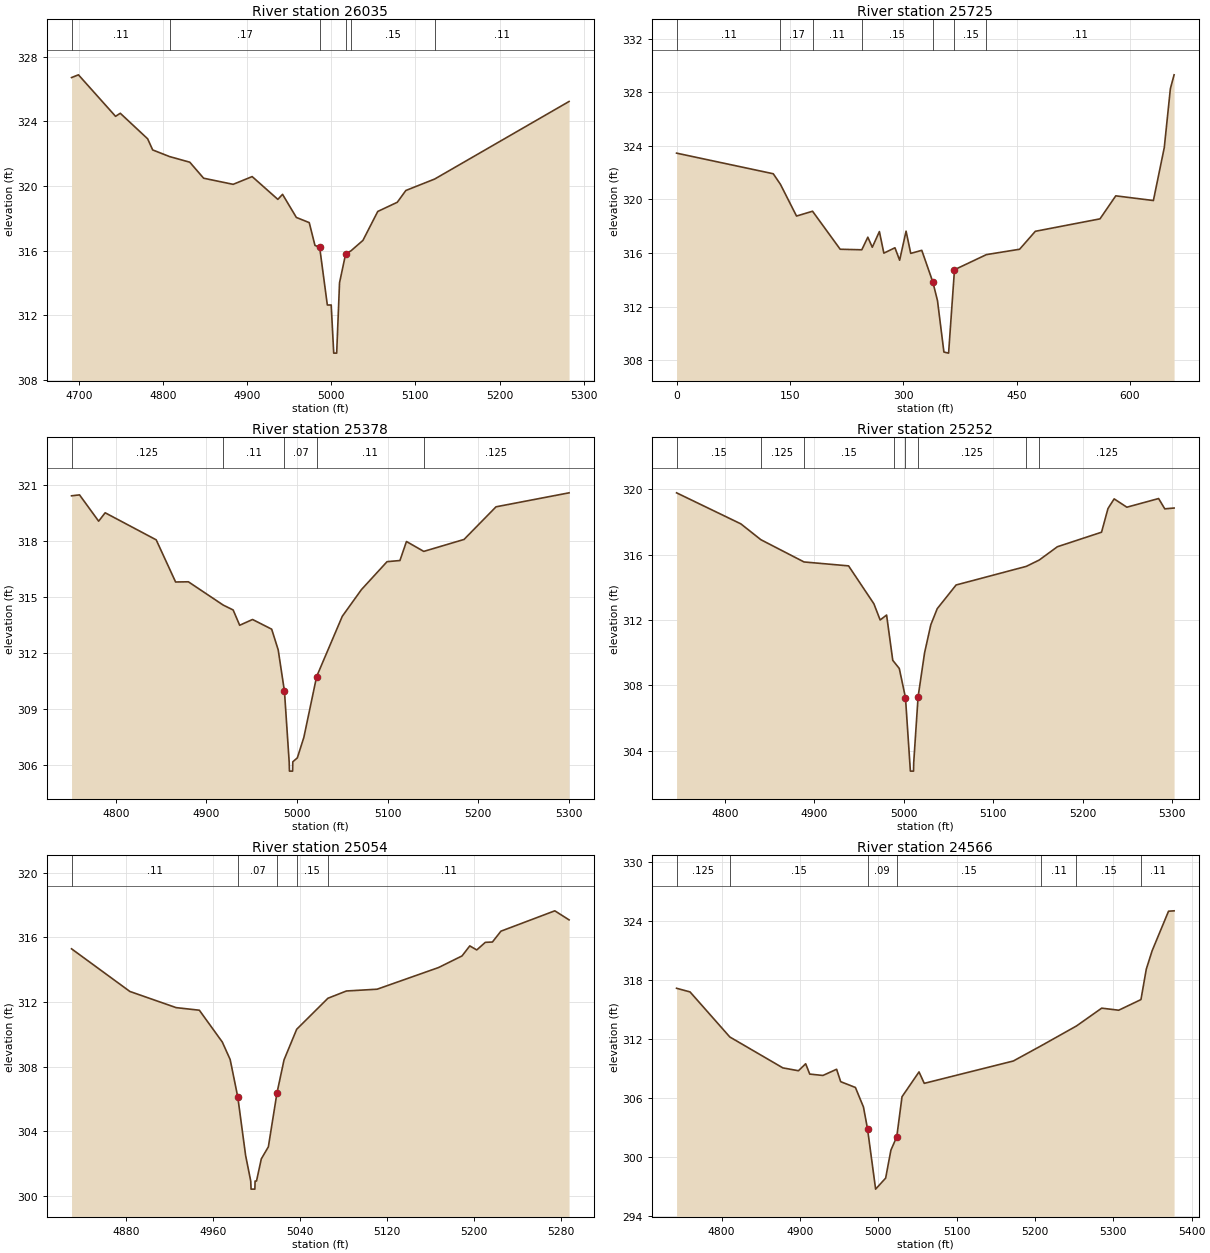
Type RM Length L Ch R = 1 ,26035   ,310,310,310
BEGIN DESCRIPTION:
CCLC 024 47.0
END DESCRIPTION:
XS GIS Cut Line= 3
      3704917.85     10114711.07      3705061.32     10114437.97
      3705117.85     10114161.08
#Sta/Elev= 30
  4691.5  326.71  4699.7  326.88  4743.8  324.31  4749.4   324.5  4781.9  322.92
  4787.9  322.23  4807.9  321.82    4832  321.47  4848.4  320.48  4883.5   320.1
  4906.1  320.58  4936.6  319.17  4942.2  319.48  4958.6  318.05  4973.9  317.73
  4980.7  316.32  4986.3   316.2  4995.4  312.63    5000  312.63    5003  309.65
  5006.5  309.65  5009.9  314.01  5017.2   315.8  5023.4  315.98  5037.7  316.63
  5055.3  318.42  5078.5  318.99  5088.7  319.72    5123  320.43  5282.6  325.23
#Mann= 6 ,-1 , 0
  4691.5     .11       0  4807.9     .17       0  4986.3     .09       0
  5017.2     .17       0  5023.4     .15       0    5123     .11       0
Bank Sta=4986.3,5017.2
XS Rating Curve= 0 ,0
Exp/Cntr=0.3,0.1

Type RM Length L Ch R = 1 ,25725   ,347,347,347
BEGIN DESCRIPTION:
CCLC 024 46.0
END DESCRIPTION:
XS GIS Cut Line= 4
      3705158.01      10114759.3      3705303.84     10114524.93
      3705480.93     10114285.34      3705533.35     10114218.34
#Sta/Elev= 30
       0  323.46     128  321.92   137.5  321.13   158.8  318.76     180  319.12
   216.6  316.28   245.2  316.24   253.2  317.18   259.1  316.43   268.5   317.6
   274.4  315.99   289.1  316.39   295.3  315.46   303.8  317.63     310  315.97
   324.6   316.2   339.2  313.84   345.4  312.44   353.9   308.6   360.1  308.52
   367.9  314.75   410.2  315.88   454.1  316.28   474.9  317.62   560.5  318.55
   581.4  320.27   631.2  319.92   645.6  323.87   653.7  328.28   658.6  329.31
#Mann= 7 ,-1 , 0
       0     .11       0   137.5     .17       0     180     .11       0
   245.2     .15       0   339.2     .09       0   367.9     .15       0
   410.2     .11       0
Bank Sta=339.2,367.9
XS Rating Curve= 0 ,0
Exp/Cntr=0.3,0.1

Type RM Length L Ch R = 1 ,25378   ,126,126,126
BEGIN DESCRIPTION:
Mapping XS 00cac6fd
END DESCRIPTION:
XS GIS Cut Line= 2
      3705392.38     10114847.85      3705772.62     10114451.98
#Sta/Elev= 30
  4751.2  320.43    4760  320.48  4781.1  319.07  4788.3  319.52  4844.6  318.07
    4866  315.81  4880.1  315.82  4918.6  314.57  4929.5  314.31  4936.7  313.49
  4950.9   313.8    4972  313.28  4979.2  312.17  4986.1  309.95  4991.3  306.17
  4991.6  305.67  4995.1  305.67  4995.3  306.17  5000.3  306.38  5007.5  307.48
  5021.6  310.74  5049.9  313.97    5071   315.4  5099.3   316.9  5113.5  316.96
  5120.7  317.98  5139.8  317.45  5184.2  318.09  5219.5  319.84  5300.1  320.59
#Mann= 5 ,-1 , 0
  4751.2    .125       0  4918.6     .11       0  4986.1     .07       0
  5021.6     .11       0  5139.8    .125       0
Bank Sta=4986.1,5021.6
XS Rating Curve= 0 ,0
Exp/Cntr=0.3,0.1

Type RM Length L Ch R = 1 ,25252   ,198,198,198
BEGIN DESCRIPTION:
Mapping XS 471dc94f
END DESCRIPTION:
XS GIS Cut Line= 2
      3705486.13     10114931.18      3705871.53     10114530.15
#Sta/Elev= 30
  4745.9  319.78  4817.8  317.88  4840.2  316.91  4888.4  315.55  4938.2  315.31
  4966.5  312.99  4973.5     312  4980.7   312.3  4987.6  309.53  4988.5  309.47
  4994.9  309.03  5001.8  307.25  5007.3  302.75  5010.8  302.75    5011  303.25
  5015.9  307.29  5023.2     310  5030.1   311.7  5037.3  312.69  5058.4  314.14
  5136.9  315.28  5151.4  315.67  5171.6  316.48    5221  317.37  5228.2  318.82
  5235.1  319.41  5249.3   318.9  5284.8  319.43  5291.7   318.8  5302.1  318.85
#Mann= 8 ,-1 , 0
  4745.9     .15       0  4840.2    .125       0  4888.4     .15       0
  4988.5     .11       0  5001.8     .07       0  5015.9    .125       0
  5136.9     .11       0  5151.4    .125       0
Bank Sta=5001.8,5015.9
XS Rating Curve= 0 ,0
Exp/Cntr=0.3,0.1

Type RM Length L Ch R = 1 ,25054   ,488,488,488
BEGIN DESCRIPTION:
CCLC 024 45.0
END DESCRIPTION:
XS GIS Cut Line= 3
      3705689.28     10114988.45      3705807.42     10114866.35
      3705990.76     10114645.42
#Sta/Elev= 30
  4830.1   315.3  4883.7  312.66  4926.2  311.66  4947.5   311.5  4968.6  309.53
  4975.8  308.45  4982.8  306.13    4990  302.51  4994.7  300.93    4995  300.43
  4998.5  300.43  4998.7  300.93    5000  300.93  5004.4   302.3  5010.9  303.05
  5018.8  306.38  5025.3  308.43  5036.9  310.32  5065.6  312.24  5082.6  312.69
  5110.8   312.8  5167.2  314.14  5188.8  314.86  5195.9  315.48  5202.3  315.23
  5210.2   315.7  5216.7  315.72  5224.5  316.39    5274  317.65  5287.1  317.09
#Mann= 5 ,-1 , 0
  4830.1     .11       0  4982.8     .07       0  5018.8     .11       0
  5036.9     .15       0  5065.6     .11       0
Bank Sta=4982.8,5018.8
XS Rating Curve= 0 ,0
Exp/Cntr=0.3,0.1

Type RM Length L Ch R = 1 ,24566   ,463,463,463
BEGIN DESCRIPTION:
CCLC 024 44.0
END DESCRIPTION:
XS GIS Cut Line= 3
      3705867.84     10115211.07      3706116.01     10115142.39
      3706367.87     10114861.05
#Sta/Elev= 30
  4742.5  317.17  4759.7   316.8  4810.5  312.22  4878.2  309.08  4898.1  308.79
  4907.3   309.5  4912.5  308.45  4929.3  308.31  4946.8  308.94    4952  307.68
  4970.8  307.09  4981.1   305.1  4986.3  302.87  4996.6  296.76  5009.4  297.88
  5016.1  300.72  5023.6  302.08  5030.3  306.15    5052  308.67  5058.7  307.51
  5172.4  309.78    5208  311.33    5253  313.34  5285.2  315.15  5306.9  314.94
  5335.3  316.02  5342.1  319.11  5349.6  320.99  5370.5     325  5377.6  325.04
#Mann= 7 ,-1 , 0
  4742.5    .125       0  4810.5     .15       0  4986.3     .09       0
  5023.6     .15       0    5208     .11       0    5253     .15       0
  5335.3     .11       0
Bank Sta=4986.3,5023.6
XS Rating Curve= 0 ,0
Exp/Cntr=0.3,0.1

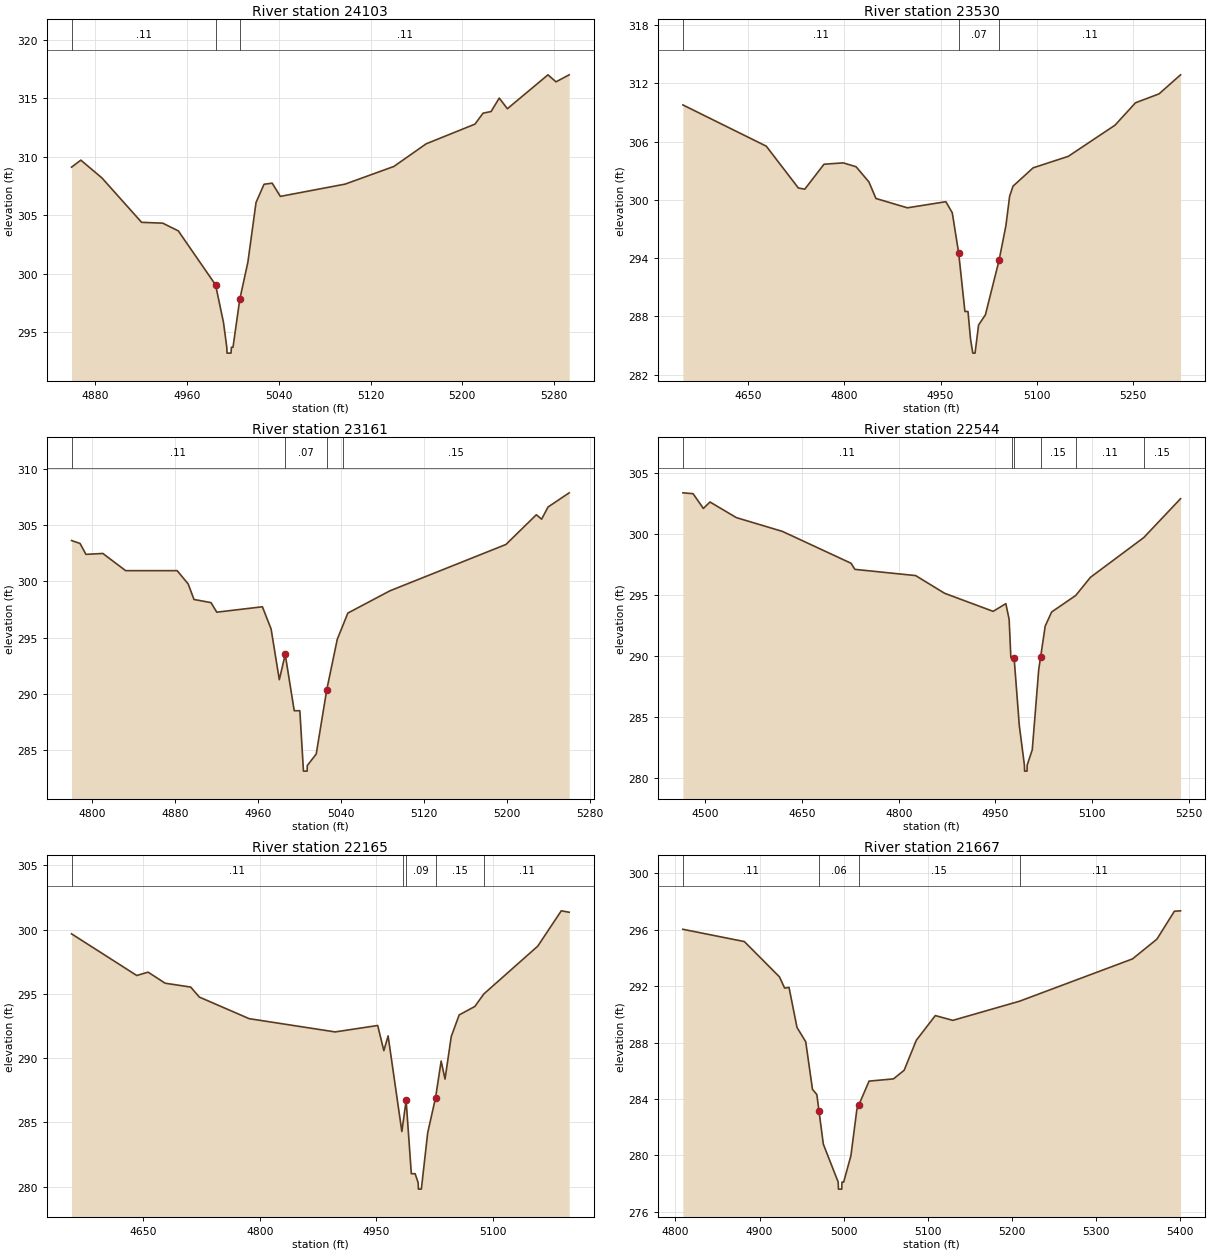
Type RM Length L Ch R = 1 ,24103   ,573,573,573
BEGIN DESCRIPTION:
CCLC 024 43.0
END DESCRIPTION:
XS GIS Cut Line= 3
      3706361.15     10115576.97      3706415.49     10115447.08
      3706621.53     10115238.48
#Sta/Elev= 30
  4859.2  309.11  4867.3  309.71  4885.7  308.19  4920.3  304.39  4938.7  304.32
  4952.3  303.66  4984.8  299.04  4991.7  295.83  4994.6   293.7  4994.8   293.2
  4998.3   293.2  4998.6   293.7    5000   293.7  5005.9  297.79    5013  300.99
  5020.1  306.09  5027.1  307.65  5034.2  307.74  5041.3  306.61  5097.8  307.66
  5140.3  309.17  5168.5  311.11    5211  312.79  5218.1  313.73  5225.1  313.87
  5232.2  315.02  5239.3  314.11  5274.7  317.01  5281.7  316.41  5293.2  317.01
#Mann= 3 ,-1 , 0
  4859.2     .11       0  4984.8     .07       0  5005.9     .11       0
Bank Sta=4984.8,5005.9
XS Rating Curve= 0 ,0
Exp/Cntr=0.3,0.1

Type RM Length L Ch R = 1 ,23530   ,369,369,369
BEGIN DESCRIPTION:
CCLC 024 42.0
END DESCRIPTION:
XS GIS Cut Line= 3
      3706817.85      10116261.1       3706840.3     10115816.59
      3706954.53     10115505.05
#Sta/Elev= 30
  4547.8  309.78    4678  305.53  4728.1  301.22  4738.1   301.1  4768.1  303.67
  4798.2  303.81  4818.2  303.41  4838.2  301.85  4849.2  300.14  4898.3  299.18
  4958.4  299.81  4968.4  298.66  4978.4  294.49  4988.1   288.5  4992.9   288.5
  4996.9  285.63  5000.4  284.21  5003.9  284.21  5009.4   287.1  5020.1  288.16
  5041.4  293.77    5052  297.31  5057.9  300.37  5063.2  301.41  5094.6   303.3
  5149.4  304.48  5222.4  307.69  5254.4     310  5291.2  310.92  5324.7  312.88
#Mann= 3 ,-1 , 0
  4547.8     .11       0  4978.4     .07       0  5041.4     .11       0
Bank Sta=4978.4,5041.4
XS Rating Curve= 0 ,0
Exp/Cntr=0.3,0.1

Type RM Length L Ch R = 1 ,23161   ,617,617,617
BEGIN DESCRIPTION:
CCLC 024 41.0
END DESCRIPTION:
XS GIS Cut Line= 3
      3707017.83      10116161.1      3707121.06      10115966.6
      3707167.86     10115711.05
#Sta/Elev= 30
  4779.8  303.63    4788  303.37  4793.7   302.4    4810  302.48    4832  300.95
  4881.7  300.95  4892.3  299.77  4897.9  298.39  4914.3  298.11  4919.9  297.26
  4963.9  297.74  4972.3  295.76  4980.2  291.26  4985.9   293.5  4994.6   288.5
    5000   288.5  5003.5  283.13    5007  283.13  5007.2  283.63  5015.8  284.65
    5026  290.38  5036.1  294.85  5041.9  296.17  5046.3  297.18  5086.9  299.16
  5198.8  303.28  5228.1  305.92  5233.2  305.53  5239.4  306.61  5259.8  307.87
#Mann= 4 ,-1 , 0
  4779.8     .11       0  4985.9     .07       0    5026     .11       0
  5041.9     .15       0
Bank Sta=4985.9,5026
XS Rating Curve= 0 ,0
Exp/Cntr=0.3,0.1

Type RM Length L Ch R = 1 ,22544   ,379,379,379
BEGIN DESCRIPTION:
CCLC 024 40.0
END DESCRIPTION:
XS GIS Cut Line= 3
      3707605.93     10116582.23      3707501.76     10116082.22
      3707480.93      10115821.8
#Sta/Elev= 30
  4465.1  303.36  4480.9  303.29  4496.9  302.08  4507.1  302.61    4548  301.33
  4619.5   300.2    4726  297.59  4731.9  297.09  4826.2  296.58  4871.1  295.13
  4946.4  293.65  4966.1  294.28  4971.2     293  4973.9  289.86  4975.5  289.86
  4978.9  289.86    4987  284.29  4994.9  281.06  4995.2  280.56    4999  280.56
  4999.2  281.06  5007.1  282.31  5017.1  288.87 5020.03289.9084  5027.2  292.45
  5037.2   293.6  5074.5  294.95  5097.4  296.44  5180.2   299.7  5237.1  302.88
#Mann= 6 ,-1 , 0
  4465.1     .11       0  4975.5     .15       0  4978.9     .09       0
 5020.03     .15       0  5074.5     .11       0  5180.2     .15       0
Bank Sta=4978.9,5020.03
XS Rating Curve= 0 ,0
Exp/Cntr=0.3,0.1

Type RM Length L Ch R = 1 ,22165   ,498,498,498
BEGIN DESCRIPTION:
CCLC 024 39.0
END DESCRIPTION:
XS GIS Cut Line= 3
      3707667.84      10116411.1      3707848.31     10116007.07
      3707817.84     10115811.02
#Sta/Elev= 30
  4557.5  299.67  4641.5  296.43  4656.1  296.69    4678  295.83  4710.9  295.53
  4722.1  294.75  4786.3  293.07    4897  292.04  4951.8  292.54  4959.7  290.58
  4965.2  291.73  4982.9  284.29  4984.2  284.86  4988.4  286.71  4995.1  281.01
    5000  281.01  5003.9  280.31  5004.2  279.81    5008  279.81  5016.2   284.2
  5026.3  286.92  5033.5  289.77  5038.5  288.37  5046.5  291.68  5056.7  293.36
  5076.9  294.02  5088.4  294.99  5157.9  298.71  5188.2  301.46  5198.4  301.35
#Mann= 5 ,-1 , 0
  4557.5     .11       0  4984.2     .15       0  4988.4     .09       0
  5026.3     .15       0  5088.4     .11       0
Bank Sta=4988.4,5026.3
XS Rating Curve= 0 ,0
Exp/Cntr=0.3,0.1

Type RM Length L Ch R = 1 ,21667   ,497,497,497
BEGIN DESCRIPTION:
CCLC 024 38.0
END DESCRIPTION:
XS GIS Cut Line= 3
      3708367.85     10116311.05      3708312.97     10116127.89
      3708067.83     10115811.05
#Sta/Elev= 30
  4808.8  296.04  4881.9  295.17  4923.6  292.67  4929.8  291.87    4935  291.92
  4944.5  289.08  4954.9  288.06  4962.9  284.69  4968.1  284.32  4970.6283.1771
  4975.8   280.8  4993.5  278.11  4993.8  277.61  4997.7  277.61    4998  278.11
    5000  278.11  5008.6  279.98  5015.7  283.26  5018.1  283.59  5030.2  285.27
  5059.2  285.43  5071.9  286.04  5086.4  288.17    5109  289.92  5129.8  289.58
  5209.2  290.94  5343.5  293.94  5372.5  295.34  5393.3  297.32  5400.6  297.35
#Mann= 4 ,-1 , 0
  4808.8     .11       0  4970.6     .06       0  5018.1     .15       0
  5209.2     .11       0
Bank Sta=4970.6,5018.1
XS Rating Curve= 0 ,0
Exp/Cntr=0.3,0.1

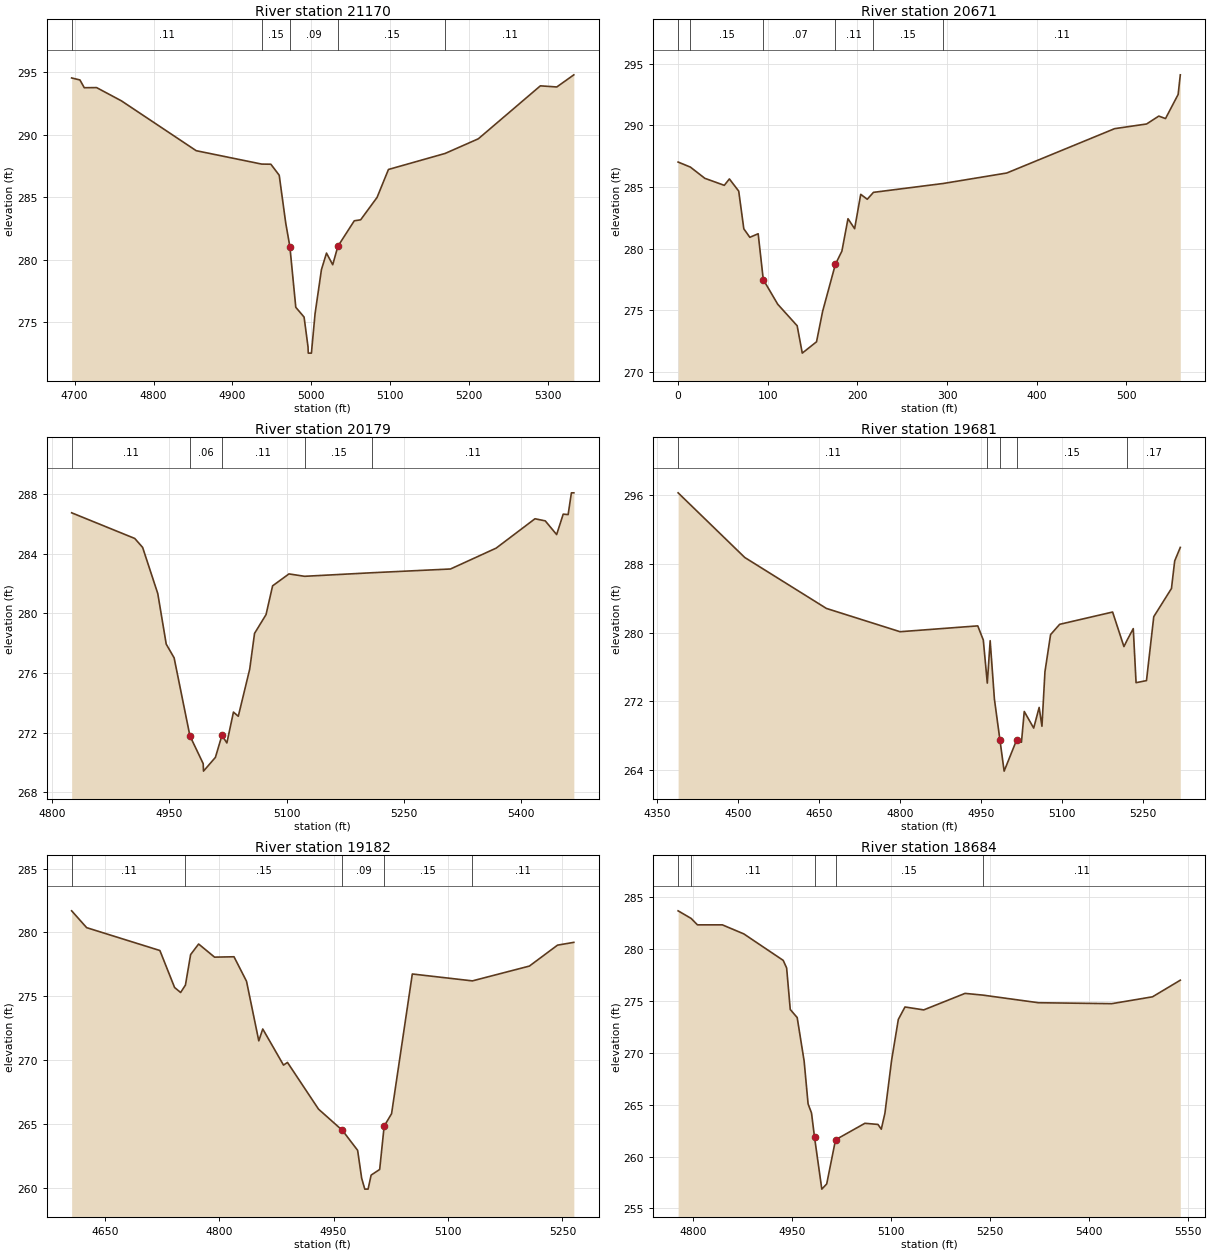
Type RM Length L Ch R = 1 ,21170   ,499,499,499
BEGIN DESCRIPTION:
CCLC 024 37.0
END DESCRIPTION:
XS GIS Cut Line= 3
      3708767.86     10116161.08      3708673.71     10115872.24
      3708467.88     10115611.11
#Sta/Elev= 30
  4696.2  294.53  4706.7  294.37  4712.2  293.75  4727.8  293.76  4759.3   292.7
    4854  288.72    4937  287.65  4948.6  287.64  4959.2  286.76  4967.5  282.92
  4972.7  281.06  4980.2  276.21  4990.7  275.43  4995.7  273.05    4996  272.55
    5000  272.55  5004.6  275.69  5012.7  279.22  5019.1  280.54    5027  279.61
  5033.5  281.08  5054.3  283.12  5062.4   283.2  5083.2  284.99  5097.6  287.22
  5169.4   288.5  5211.5  289.67  5290.1   293.9  5310.9  293.81  5332.5  294.78
#Mann= 5 ,-1 , 0
  4696.2     .11       0    4937     .15       0  4972.7     .09       0
  5033.5     .15       0  5169.4     .11       0
Bank Sta=4972.7,5033.5
XS Rating Curve= 0 ,0
Exp/Cntr=0.3,0.1

Type RM Length L Ch R = 1 ,20671   ,492,492,492
BEGIN DESCRIPTION:
CCLC 024 36.0
END DESCRIPTION:
XS GIS Cut Line= 4
      3709167.85     10115861.07      3709095.18     10115729.81
      3709007.53     10115648.07      3708811.56     10115432.56
#Sta/Elev= 30
       0  287.02    13.7  286.61    29.8   285.7    51.5  285.13    57.2  285.65
    67.6  284.66    73.3   281.6      80  280.91    89.3   281.2      95  277.48
   111.1  275.48   132.8  273.73   138.5  271.51   154.4  272.43   161.2   274.9
   175.4  278.71   182.7  279.79   189.5  282.42   196.9  281.61   203.7   284.4
     211     284   217.9  284.56   295.7  285.28   366.6  286.13   486.9  289.73
   522.6  290.11   536.2  290.75   543.7  290.55   557.8  292.51   560.2   294.1
#Mann= 6 ,-1 , 0
       0     .11       0    13.7     .15       0      95     .07       0
   175.4     .11       0   217.9     .15       0   295.7     .11       0
Bank Sta=95,175.4
XS Rating Curve= 0 ,0
Exp/Cntr=0.3,0.1

Type RM Length L Ch R = 1 ,20179   ,498,498,498
BEGIN DESCRIPTION:
CCLC 024 35.0
END DESCRIPTION:
XS GIS Cut Line= 3
      3709567.85     10115811.07       3709544.9     10115637.48
      3709267.84     10115261.05
#Sta/Elev= 30
  4824.9  286.74  4905.6  285.02  4915.7  284.42  4935.1  281.32  4945.9  277.93
    4956  277.01  4976.2  271.78  4993.2  269.91  4993.6  269.41  5008.8  270.33
  5017.2  271.81  5023.5   271.3  5031.9  273.37  5038.1  273.09  5052.7  276.25
  5058.9  278.65  5073.6  279.91    5082  281.84  5102.9  282.64    5123  282.48
  5209.6  282.72  5309.6  282.97    5368  284.37  5417.7  286.34  5430.8   286.2
  5445.4  285.28  5453.8  286.65  5460.1  286.62  5464.3  288.08  5467.4  288.08
#Mann= 5 ,-1 , 0
  4824.9     .11       0  4976.2     .06       0  5017.2     .11       0
    5123     .15       0  5209.6     .11       0
Bank Sta=4976.2,5017.2
XS Rating Curve= 0 ,0
Exp/Cntr=0.3,0.1

Type RM Length L Ch R = 1 ,19681   ,499,499,499
BEGIN DESCRIPTION:
CCLC 024 34.0
END DESCRIPTION:
XS GIS Cut Line= 3
      3709767.84      10116061.1      3709911.21     10115466.85
      3709817.85     10115161.08
#Sta/Elev= 30
  4388.7  296.27  4512.2  288.75  4663.6  282.82  4800.2  280.11  4944.2  280.79
  4954.5  279.14  4961.9  274.13  4967.2  279.07  4975.1  272.25  4985.4  267.48
  4993.1  263.89  5016.5  267.55  5025.2  267.25  5030.4  270.83  5047.9   268.9
    5058   271.3  5063.2  269.11  5068.8  275.47  5079.2  279.77    5096  280.97
  5194.2   282.4  5215.2  278.38  5221.6  279.19  5232.5  280.47  5237.7  274.18
    5257  274.42  5270.5  281.86  5303.3  285.14  5309.3  288.35  5319.7  289.92
#Mann= 5 ,-1 , 0
  4388.7     .11       0  4961.9     .15       0  4985.4     .09       0
  5016.5     .15       0  5221.6     .17       0
Bank Sta=4985.4,5016.5
XS Rating Curve= 0 ,0
Exp/Cntr=0.3,0.1

Type RM Length L Ch R = 1 ,19182   ,498,498,498
BEGIN DESCRIPTION:
CCLC 024 33.0
END DESCRIPTION:
XS GIS Cut Line= 3
      3710189.27     10115899.89      3710307.13     10115524.45
      3710443.56     10115297.27
#Sta/Elev= 30
  4606.5  281.69  4626.2  280.37  4722.2  278.58  4741.5  275.68  4749.4  275.29
  4755.7  275.87  4762.5  278.26    4773  279.09  4793.9  278.06  4819.4  278.09
  4835.8  276.17  4851.9   271.5  4857.1  272.43  4884.3   269.6  4889.5  269.81
  4930.2  266.15  4961.6  264.48  4981.5  262.92  4986.8  260.73  4990.9  259.88
  4995.2  259.88  4999.2  260.98  5010.4  261.42  5016.3  264.82    5026  265.79
  5053.2  276.74    5132   276.2  5206.7  277.36  5243.6     279    5265  279.22
#Mann= 5 ,-1 , 0
  4606.5     .11       0  4755.7     .15       0  4961.6     .09       0
  5016.3     .15       0    5132     .11       0
Bank Sta=4961.6,5016.3
XS Rating Curve= 0 ,0
Exp/Cntr=0.3,0.1

Type RM Length L Ch R = 1 ,18684   ,498,498,498
BEGIN DESCRIPTION:
CCLC 024 32.0
END DESCRIPTION:
XS GIS Cut Line= 3
      3710553.85     10115983.25      3710620.41     10115770.52
      3710699.67     10115238.49
#Sta/Elev= 30
  4777.1  283.66  4796.8  282.93  4806.4  282.31  4844.1  282.31  4876.6  281.44
  4936.3  278.89  4941.5  278.16    4947  274.16  4957.5  273.38    4968   269.2
    4974  265.07  4979.2  264.19 4983.76261.8537  4994.8  256.86  5002.2  257.36
  5015.6  261.61  5060.1   263.2  5079.9  263.09  5084.9  262.63  5090.4  264.17
  5100.5  269.26  5110.7   273.2  5120.8   274.4  5149.2  274.12  5211.8  275.71
  5239.2  275.54    5323  274.81  5434.2  274.72  5495.8  275.38  5537.9  276.98
#Mann= 5 ,-1 , 0
  4777.1     .17       0  4796.8     .11       0 4983.76     .06       0
  5015.6     .15       0  5239.2     .11       0
Bank Sta=4983.76,5015.6
XS Rating Curve= 0 ,0
Exp/Cntr=0.3,0.1

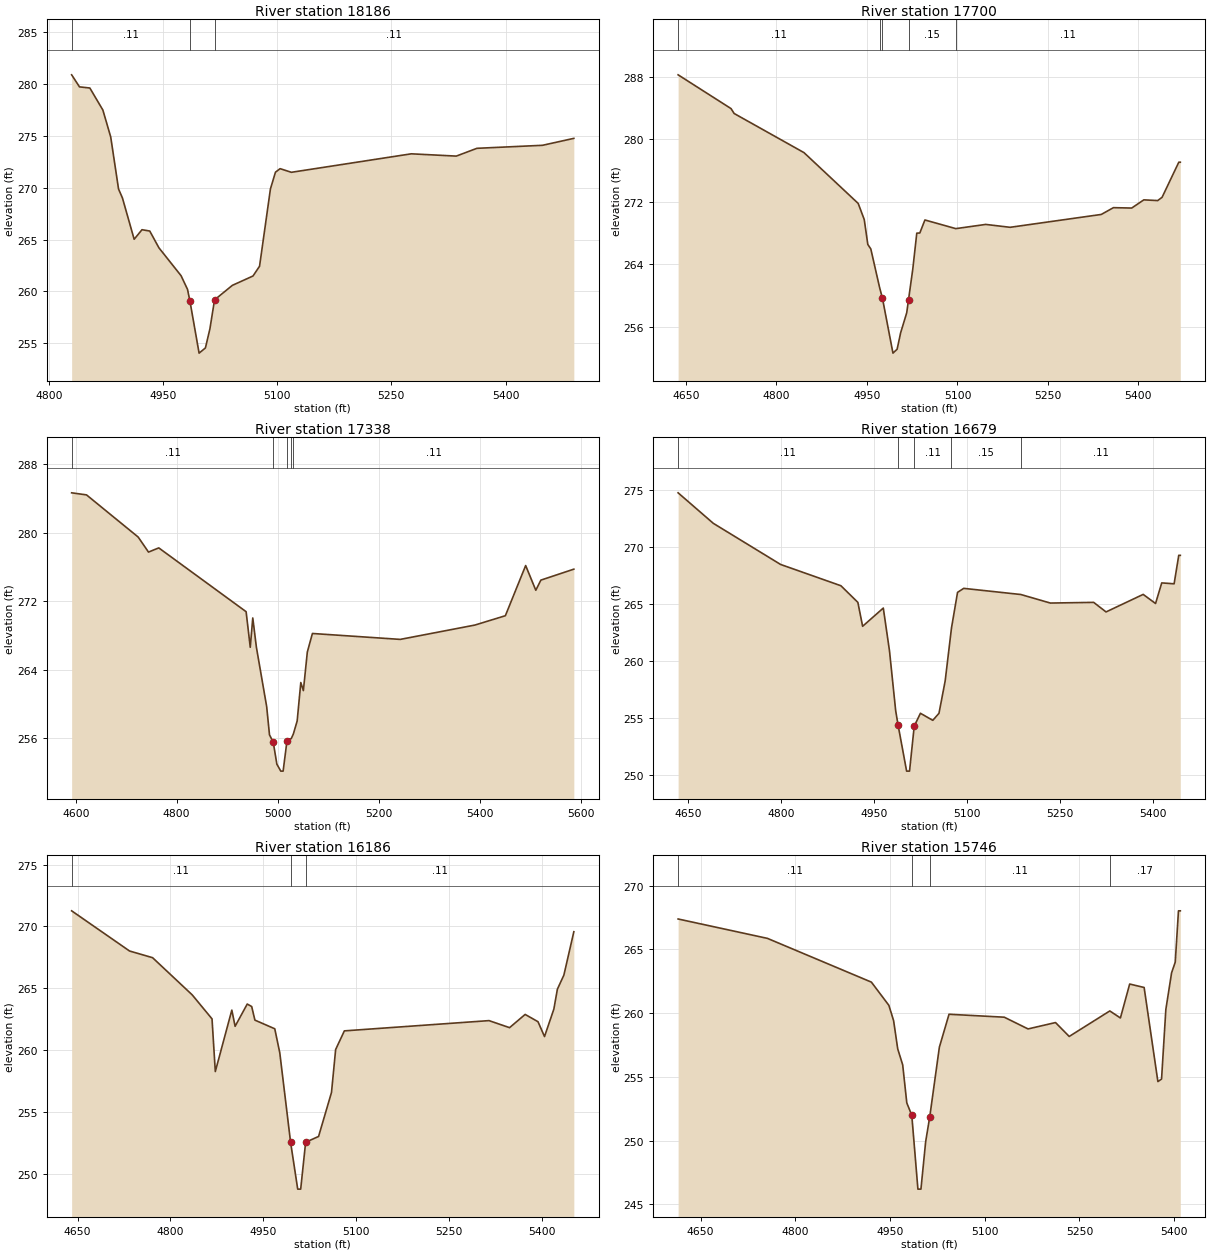
Type RM Length L Ch R = 1 ,18186   ,486,486,486
BEGIN DESCRIPTION:
CCLC 024 31.0
END DESCRIPTION:
XS GIS Cut Line= 3
      3711067.85     10115861.06      3711029.66     10115695.51
      3710746.64     10115295.88
#Sta/Elev= 30
  4830.1  280.87  4840.4  279.71    4854   279.6  4871.1  277.48  4881.4  274.89
  4891.7  269.87  4896.8  269.01  4912.2  265.03  4922.5  265.95  4932.7  265.82
  4944.7  264.21  4973.8  261.52  4982.3   260.2 4985.54 259.041  4997.5  254.06
  5005.8  254.56  5011.7   256.4  5017.8  259.19  5041.2  260.59  5068.3  261.49
  5076.9  262.43  5091.2  269.88  5097.8  271.49  5103.9  271.83  5118.7  271.48
  5276.2  273.26  5335.3  273.04  5362.4  273.79  5448.5  274.08  5489.7  274.75
#Mann= 3 ,-1 , 0
  4830.1     .11       0 4985.54     .06       0  5017.8     .11       0
Bank Sta=4985.54,5017.8
XS Rating Curve= 0 ,0
Exp/Cntr=0.3,0.1

Type RM Length L Ch R = 1 ,17700   ,362,362,362
BEGIN DESCRIPTION:
CCLC 024 30.0
END DESCRIPTION:
XS GIS Cut Line= 3
      3711444.47     10115988.45      3711477.16     10115626.83
      3711417.85     10115161.09
#Sta/Elev= 30
  4636.9  288.29  4724.6  283.96  4729.8  283.33  4845.6  278.31  4935.5  271.79
  4945.5  269.72  4951.4  266.53  4956.4  265.95    4971  260.99  4975.7  259.62
  4993.1  252.59    5000  253.09  5005.8  255.19  5015.9  257.76 5018.92259.4434
    5026  263.39  5032.6  267.98  5037.6     268  5046.1  269.67  5097.3  268.56
  5146.9   269.1  5187.3  268.73  5338.5  270.38  5358.6  271.25  5388.9   271.2
    5409  272.25  5432.1  272.16  5439.3  272.58    5467  277.08  5469.5  277.08
#Mann= 5 ,-1 , 0
  4636.9     .11       0    4971     .15       0  4975.7     .09       0
 5018.92     .15       0  5097.3     .11       0
Bank Sta=4975.7,5018.92
XS Rating Curve= 0 ,0
Exp/Cntr=0.3,0.1

Type RM Length L Ch R = 1 ,17338   ,659,659,659
BEGIN DESCRIPTION:
CCLC 024 29.0
END DESCRIPTION:
XS GIS Cut Line= 3
      3711746.54     10116040.58      3711819.47     10115655.13
      3711756.97     10115056.17
#Sta/Elev= 30
    4592  284.64  4621.4   284.4  4723.8  279.48  4744.2  277.73  4764.5  278.22
  4937.5  270.78  4945.7  266.63  4950.7  270.05  4957.9  266.62  4978.2  259.72
  4983.8  256.42 4991.19255.5685  4998.4     253  5006.2  252.19  5010.8  252.19
  5018.5  255.75  5026.8  255.98    5031  256.51  5038.6  258.04  5045.8  262.52
  5050.9  261.58  5058.7  266.07  5068.8  268.24  5242.7  267.55  5390.5  269.22
  5450.9  270.31  5491.1  276.16  5511.2  273.28  5521.2  274.46  5586.5  275.74
#Mann= 5 ,-1 , 0
    4592     .11       0 4991.19     .06       0  5018.5     .11       0
  5026.8     .15       0    5031     .11       0
Bank Sta=4991.19,5018.5
XS Rating Curve= 0 ,0
Exp/Cntr=0.3,0.1

Type RM Length L Ch R = 1 ,16679   ,493,493,493
BEGIN DESCRIPTION:
CCLC 024 28.0
END DESCRIPTION:
XS GIS Cut Line= 3
      3712225.71     10116009.31      3712314.26     10115722.84
      3712317.85      10115211.1
#Sta/Elev= 30
  4633.3  274.76  4690.2  272.08  4798.9  268.47  4896.4   266.6  4923.8  265.14
  4931.5  263.04  4964.9  264.64  4974.9  260.89  4984.9  255.63 4988.79254.3657
  5002.6  250.32  5007.3  250.32  5014.9  254.27  5024.9   255.4  5044.9  254.78
  5054.9   255.4  5064.9  258.24  5075.1  262.89  5084.9  266.02  5094.9  266.37
  5187.2  265.83  5234.9  265.08  5304.9  265.14  5324.9   264.3  5384.9  265.84
  5404.9  265.04  5414.9  266.85  5434.9  266.77  5442.4  269.27  5444.9  269.27
#Mann= 5 ,-1 , 0
  4633.3     .11       0 4988.79     .06       0  5014.9     .11       0
  5075.1     .15       0  5187.2     .11       0
Bank Sta=4988.79,5014.9
XS Rating Curve= 0 ,0
Exp/Cntr=0.3,0.1

Type RM Length L Ch R = 1 ,16186   ,440,440,440
BEGIN DESCRIPTION:
CCLC 024 27.0
END DESCRIPTION:
XS GIS Cut Line= 3
      3712652.81     10116181.14      3712762.18     10115842.63
      3712892.24     10115405.62
#Sta/Elev= 30
  4640.3  271.26  4733.9  268.01  4771.1  267.47  4835.2  264.46  4867.2  262.52
  4872.5  258.26  4899.2  263.23  4904.5  261.92  4924.1  263.72  4931.3  263.52
  4936.5  262.42  4968.6  261.72  4976.7  259.78  4994.2  252.53  5005.7  248.75
  5010.5  248.75  5018.5  252.54  5039.4  253.01  5060.3  256.57    5067  260.04
  5081.1  261.55  5314.9  262.38  5348.1  261.81  5373.3  262.88  5394.1  262.29
  5404.6  261.09  5419.7  263.31  5425.4  264.92  5435.9  266.06    5452  269.57
#Mann= 3 ,-1 , 0
  4640.3     .11       0  4994.2     .06       0  5018.5     .11       0
Bank Sta=4994.2,5018.5
XS Rating Curve= 0 ,0
Exp/Cntr=0.3,0.1

Type RM Length L Ch R = 1 ,15746   ,500,500,500
BEGIN DESCRIPTION:
CCLC 024 26.0
END DESCRIPTION:
XS GIS Cut Line= 3
      3712867.89     10116211.04      3713168.21     10115969.02
      3713367.87     10115611.04
#Sta/Elev= 30
  4614.3  267.38  4755.8  265.86  4920.5  262.43  4948.2  260.61  4955.7  259.41
  4962.2   257.2  4970.1  255.94  4976.6  252.96  4984.5  251.99  4994.2   246.2
    4999   246.2  5006.5  249.93 5012.91251.8522  5028.2  257.33  5043.5  259.91
    5131  259.68  5168.7  258.76  5212.2  259.26  5233.9  258.17  5298.2  260.17
    5315  259.62  5329.7  262.28  5352.6  262.01  5374.4  254.63  5380.2  254.83
    5387  260.29  5396.1  263.16  5401.9     264    5407  268.02  5409.9  268.02
#Mann= 4 ,-1 , 0
  4614.3     .11       0  4984.5     .06       0 5012.91     .11       0
  5298.2     .17       0
Bank Sta=4984.5,5012.91
XS Rating Curve= 0 ,0
Exp/Cntr=0.3,0.1

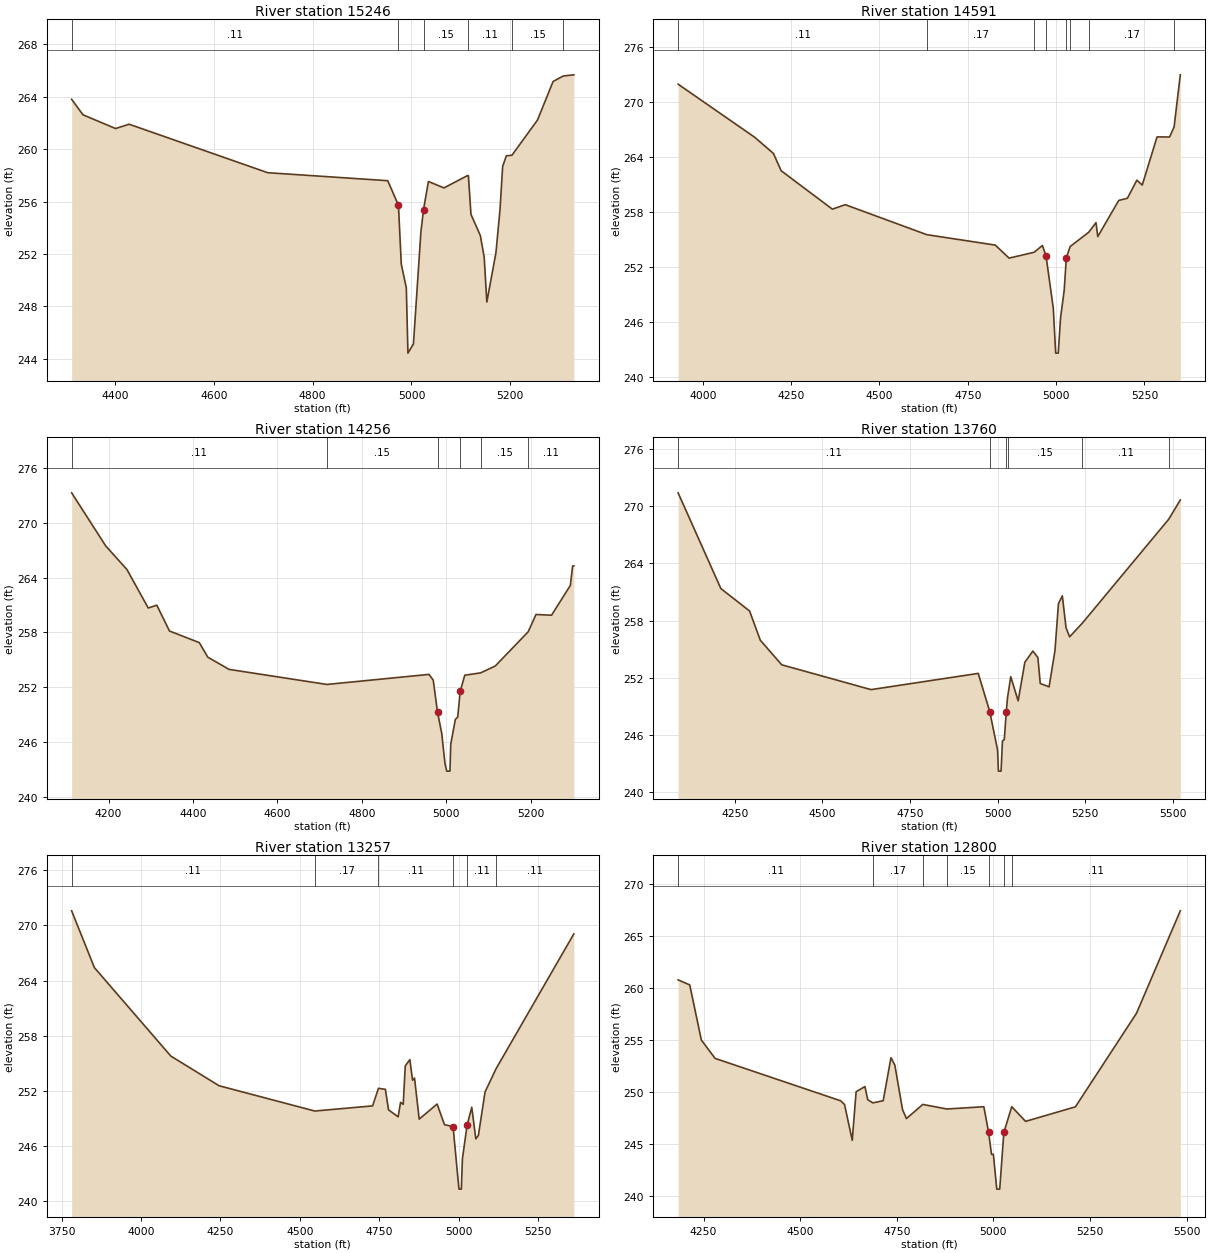
Type RM Length L Ch R = 1 ,15246   ,655,655,655
BEGIN DESCRIPTION:
CCLC 024 25.0
END DESCRIPTION:
XS GIS Cut Line= 3
      3713017.86     10116461.07      3713616.77     10116123.69
      3713717.84     10115811.12
#Sta/Elev= 30
  4312.6  263.81  4335.5  262.63  4401.5  261.58  4428.9  261.91  4709.2  258.21
    4952   257.6  4973.7  255.73  4979.4  251.24  4989.6  249.43  4992.9  244.44
    5004  245.14  5019.1  253.67  5024.4  255.38  5034.3  257.54  5065.8  257.05
  5113.4  257.99  5115.2  257.99  5120.4  255.03  5139.4  253.41  5147.2  251.74
  5152.5  248.34  5170.9   252.1  5179.2  255.42  5184.5  258.68  5191.9   259.5
  5203.2  259.54    5255  262.23  5286.5  265.17    5307  265.59  5328.5  265.68
#Mann= 6 ,-1 , 0
  4312.6     .11       0  4973.7     .06       0  5024.4     .15       0
  5113.4     .11       0  5203.2     .15       0    5307     .17       0
Bank Sta=4973.7,5024.4
XS Rating Curve= 0 ,0
Exp/Cntr=0.3,0.1

Type RM Length L Ch R = 1 ,14591   ,335,335,335
BEGIN DESCRIPTION:
Mapping XS 9ee30098
END DESCRIPTION:
XS GIS Cut Line= 3
      3713918.41      10117295.8      3714246.55     10116353.05
       3714147.6     10115941.61
#Sta/Elev= 30
  3930.3  271.93  4147.1  266.14    4200  264.38    4222  262.49  4366.9   258.3
  4403.3  258.79  4634.1  255.52    4828  254.38  4867.1  252.96    4938   253.6
  4961.4  254.34  4971.7   253.2  4992.3  247.46  4998.9   242.6  5006.2   242.6
  5012.8  246.47  5023.1  249.46  5029.1  253.01  5040.1  254.23  5092.7  255.79
    5113  256.83  5118.1  255.31  5177.4  259.25    5202  259.49  5228.8  261.46
    5244  260.93  5285.9  266.18  5321.4  266.17  5334.1  267.26  5351.7  272.95
#Mann= 8 ,-1 , 0
  3930.3     .11       0  4634.1     .17       0    4938     .17       0
  4971.7     .09       0  5029.1     .17       0  5040.1     .15       0
  5092.7     .17       0  5334.1     .11       0
Bank Sta=4971.7,5029.1
XS Rating Curve= 0 ,0
Exp/Cntr=0.3,0.1

Type RM Length L Ch R = 1 ,14256   ,496,496,496
BEGIN DESCRIPTION:
CCLC 024 24.0
END DESCRIPTION:
XS GIS Cut Line= 3
      3714667.85     10117111.07      3714555.19     10116230.75
      3714417.87     10115961.11
#Sta/Elev= 30
  4112.5  273.29  4193.2  267.48  4243.6  264.89    4294  260.68  4314.3  260.99
  4344.4  258.16    4415  256.89  4435.1   255.3  4485.5  253.96  4717.4  252.31
  4959.4  253.41  4969.4  252.78  4979.5  249.29  4989.6  246.94  4997.3  243.63
  5001.5  242.82    5009  242.82  5010.9  245.77  5021.8  248.48  5027.4  248.74
  5033.3  251.55  5044.1  253.32  5081.9  253.58  5116.4  254.33  5194.5  258.08
  5212.9  259.97  5249.8  259.89  5294.3  263.15  5299.8  265.29  5302.6  265.29
#Mann= 6 ,-1 , 0
  4112.5     .11       0  4717.4     .15       0  4979.5     .07       0
  5033.3     .11       0  5081.9     .15       0  5194.5     .11       0
Bank Sta=4979.5,5033.3
XS Rating Curve= 0 ,0
Exp/Cntr=0.3,0.1

Type RM Length L Ch R = 1 ,13760   ,503,503,503
BEGIN DESCRIPTION:
CCLC 024 23.0
END DESCRIPTION:
XS GIS Cut Line= 3
      3715217.85     10117061.05      3715037.92     10116166.87
      3714876.77     10115670.79
#Sta/Elev= 30
  4087.9  271.38  4209.9  261.35  4291.9     259  4322.5  255.94  4383.7  253.36
  4638.7  250.76  4944.7  252.46  4977.7  248.45    5000  244.42  5002.3  242.22
  5009.9  242.22  5013.9  245.39  5019.1  245.52 5024.79248.4432  5028.3  249.91
  5037.6  252.11  5058.7  249.58  5077.8  253.63  5100.7   254.8    5115  254.12
  5121.8   251.4    5147  251.05  5163.8  254.85  5173.7  259.77  5184.8  260.59
  5195.4  257.24  5205.6  256.29    5242  257.73  5488.9  268.63  5521.6  270.63
#Mann= 6 ,-1 , 0
  4087.9     .11       0  4977.7     .06       0 5024.79     .11       0
  5028.3     .15       0    5242     .11       0  5488.9     .15       0
Bank Sta=4977.7,5024.79
XS Rating Curve= 0 ,0
Exp/Cntr=0.3,0.1

Type RM Length L Ch R = 1 ,13257   ,457,457,457
BEGIN DESCRIPTION:
CCLC 024 22.0
END DESCRIPTION:
XS GIS Cut Line= 3
      3715366.34     10117082.23      3715486.13     10116050.97
      3715167.83     10115611.04
#Sta/Elev= 30
  3781.5  271.59  3853.1  265.41  4093.8  255.78  4245.8  252.55  4547.1   249.8
    4729  250.36  4747.5  252.27  4769.3  252.16  4779.3  249.93  4809.5  249.17
  4817.1  250.74  4825.5  250.53  4831.9   254.7  4846.4   255.4  4854.9  253.15
  4861.1  253.39  4875.8  248.92  4932.2  250.56  4955.3  248.32  4982.5   248.1
  5000.9   241.3  5008.5   241.3  5011.9  244.62  5026.6  248.25  5041.3  250.21
  5054.1  246.77  5062.2  247.15  5083.1  251.87  5117.6  254.39  5362.7  269.08
#Mann= 6 ,-1 , 0
  3781.5     .11       0  4547.1     .17       0  4747.5     .11       0
  4982.5     .06       0  5026.6     .11       0  5117.6     .11       0
Bank Sta=4982.5,5026.6
XS Rating Curve= 0 ,0
Exp/Cntr=0.3,0.1

Type RM Length L Ch R = 1 ,12800   ,499,499,499
BEGIN DESCRIPTION:
CCLC 024 21.0
END DESCRIPTION:
XS GIS Cut Line= 3
      3715767.85     10116611.08      3715810.24     10115796.38
      3715517.85     10115411.06
#Sta/Elev= 30
  4184.2  260.77  4214.3  260.28  4244.3  254.98  4279.9  253.21  4604.8  249.13
  4614.8  248.78  4634.8  245.33  4644.8     250  4667.6   250.5  4674.9  249.23
  4688.2  248.93  4714.9  249.14    4735  253.28    4745  252.56    4765  248.27
    4775  247.42  4817.4  248.78  4879.6  248.34  4975.3  248.56 4987.69246.0896
  4995.1  243.98    5000  243.98  5008.8  240.63  5016.4  240.63  5027.1  246.08
  5047.5  248.56  5083.3  247.15  5212.3  248.55  5370.3  257.55  5483.7  267.41
#Mann= 7 ,-1 , 0
  4184.2     .11       0  4688.2     .17       0  4817.4     .11       0
  4879.6     .15       0 4987.69     .09       0  5027.1     .15       0
  5047.5     .11       0
Bank Sta=4987.69,5027.1
XS Rating Curve= 0 ,0
Exp/Cntr=0.3,0.1