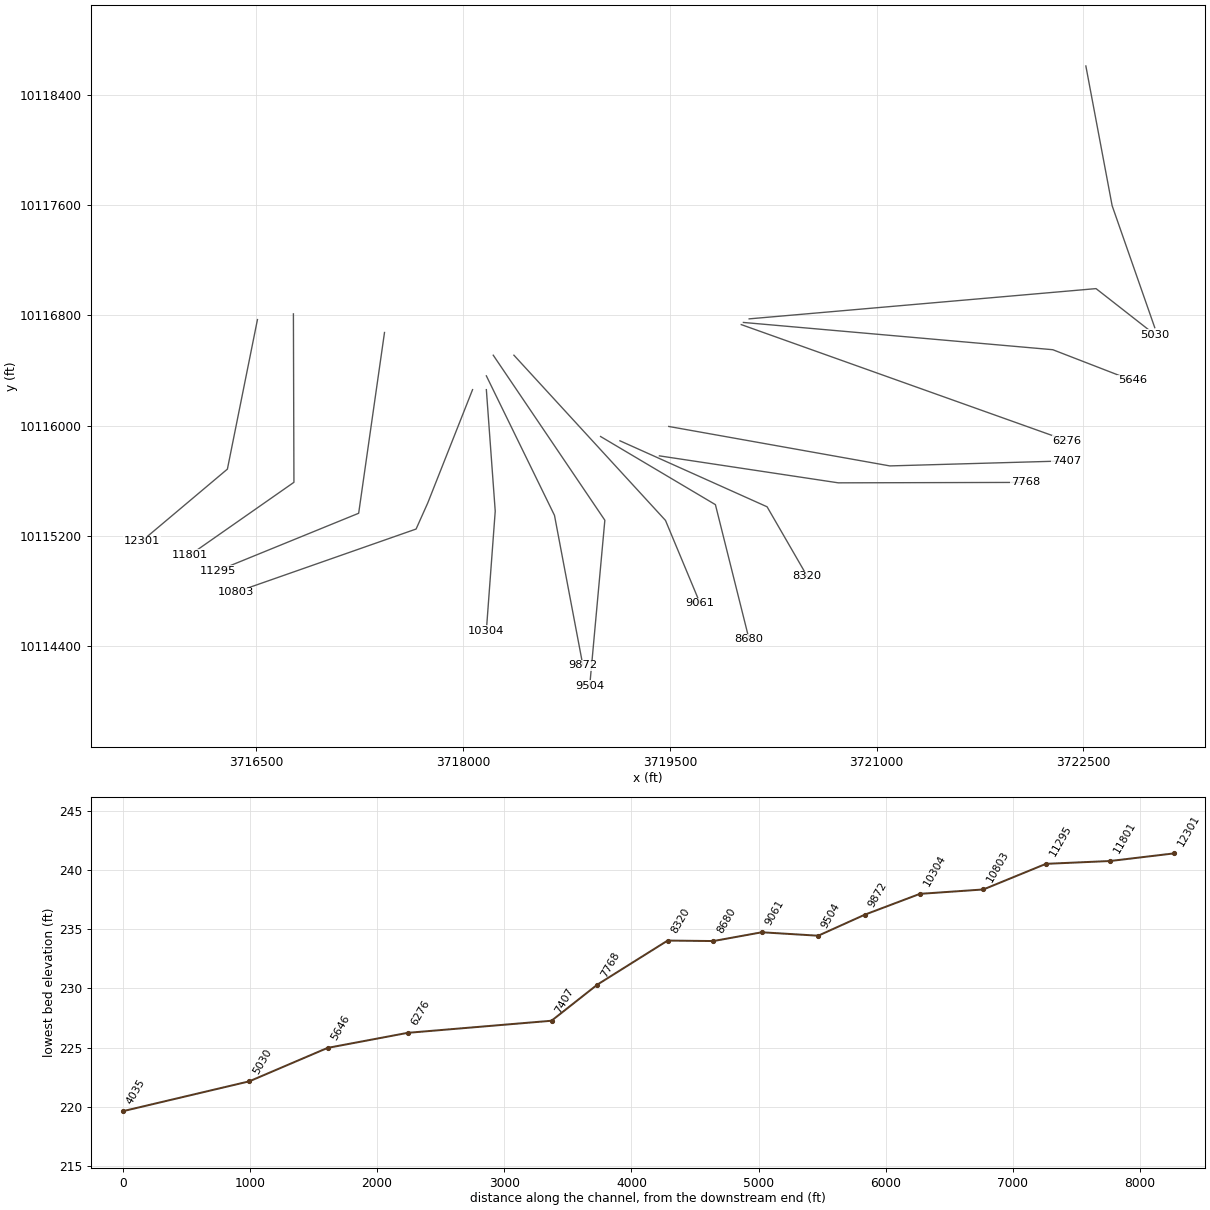
HEC-RAS study CCLC 024.prj: CCLC 024 Base Level Engineering

--- CCLC 024.g01 (geometry) --- (continued)

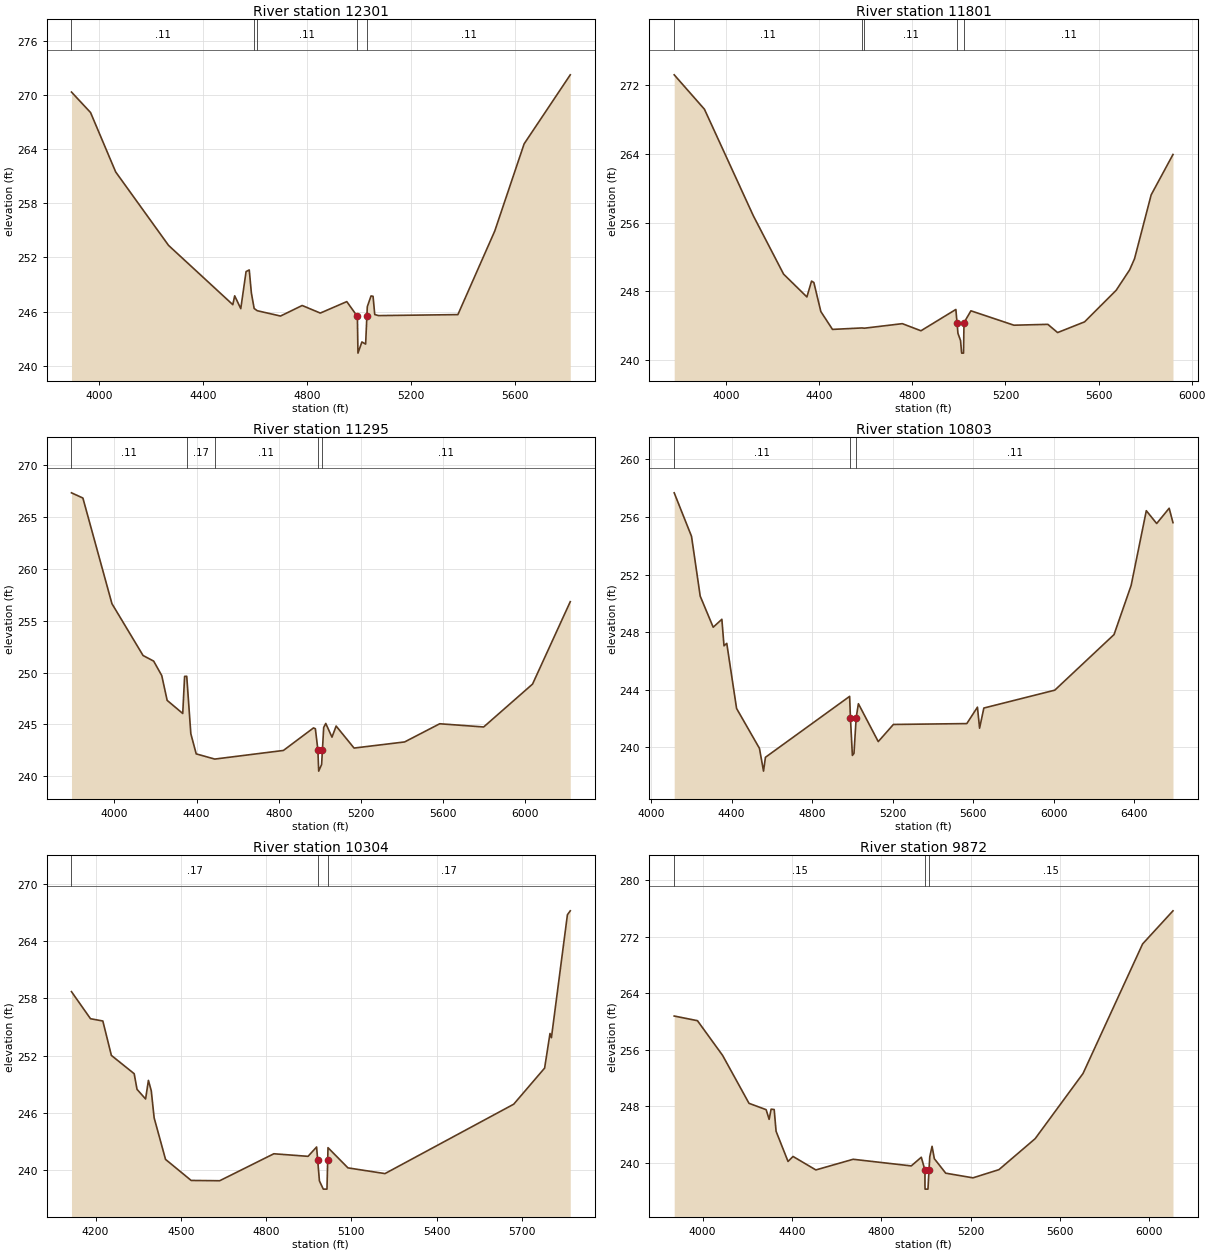
Type RM Length L Ch R = 1 ,12301   ,500,500,500
BEGIN DESCRIPTION:
CCLC 024 20.0
END DESCRIPTION:
XS GIS Cut Line= 3
      3716506.96     10116769.68      3716288.88     10115683.96
      3715667.89      10115161.1
#Sta/Elev= 30
  3892.6  270.33    3966  268.06  4062.6  261.48  4266.2  253.33  4513.4  246.76
  4520.6  247.74    4544  246.32  4564.4  250.43  4576.6  250.61  4584.8  248.06
  4595.5  246.34  4607.5  246.09    4697   245.5  4780.2  246.67    4850  245.83
  4951.9   247.1  4992.7  245.46  4994.9  241.39  5010.1  242.63  5024.4  242.39
 5029.24245.4804  5030.9  246.54  5045.2  247.73    5053  247.69  5059.5  245.67
  5073.8  245.55  5379.4  245.66  5521.2  254.92  5634.3  264.59  5811.8  272.24
#Mann= 5 ,-1 , 0
  3892.6     .11       0  4595.5     .15       0  4607.5     .11       0
  4992.7     .06       0 5029.24     .11       0
Bank Sta=4992.7,5029.24
XS Rating Curve= 0 ,0
Exp/Cntr=0.3,0.1

Type RM Length L Ch R = 1 ,11801   ,506,506,506
BEGIN DESCRIPTION:
CCLC 024 19.0
END DESCRIPTION:
XS GIS Cut Line= 3
      3716767.85     10116811.06      3716771.67     10115588.17
      3716017.87     10115061.08
#Sta/Elev= 30
  3777.1  273.24  3907.1  269.22  4117.1  256.78  4247.1  249.97  4347.1  247.31
  4367.1  249.16  4377.1  248.99  4407.1   245.6  4457.1  243.52    4584  243.69
  4594.1  243.66  4757.1  244.19  4837.1  243.36  4987.1  245.85 4992.07244.2977
    4996  243.07  5007.2  242.22  5011.9  240.75    5020  240.75    5022   244.3
  5051.7  245.69  5236.6  244.01  5382.2  244.11  5424.1  243.15    5540   244.4
  5675.8  248.09  5733.6  250.47  5754.6  251.77  5826.1  259.23  5919.8  263.94
#Mann= 5 ,-1 , 0
  3777.1     .11       0    4584     .15       0  4594.1     .11       0
 4992.07     .06       0    5022     .11       0
Bank Sta=4992.07,5022
XS Rating Curve= 0 ,0
Exp/Cntr=0.3,0.1

Type RM Length L Ch R = 1 ,11295   ,492,492,492
BEGIN DESCRIPTION:
CCLC 024 18.0
END DESCRIPTION:
XS GIS Cut Line= 3
      3717428.85     10116675.99      3717241.34     10115363.47
      3716221.66     10114947.27
#Sta/Elev= 30
  3791.3   267.3  3846.8   266.8  3988.2  256.63  4139.7  251.64  4191.3   251.1
  4230.6  249.71  4256.9  247.32  4332.7  246.06  4341.8  249.63  4352.2  249.64
  4372.1  244.11  4398.3  242.17  4488.6  241.67  4822.6   242.5  4969.1  244.67
  4978.1  244.59 4990.29242.5735  4994.3  240.51  5008.5  241.15  5012.4242.5246
  5018.6  244.71  5028.7   245.1    5059  243.78  5079.2  244.85  5166.4  242.73
  5412.5  243.32  5583.3  245.07  5797.1  244.76    6035  248.89  6218.5  256.82
#Mann= 5 ,-1 , 0
  3791.3     .11       0  4352.2     .17       0  4488.6     .11       0
 4990.29     .06       0  5012.4     .11       0
Bank Sta=4990.29,5012.4
XS Rating Curve= 0 ,0
Exp/Cntr=0.3,0.1

Type RM Length L Ch R = 1 ,10803   ,499,499,499
BEGIN DESCRIPTION:
CCLC 024 17.0
END DESCRIPTION:
XS GIS Cut Line= 4
      3718067.86     10116261.09      3717742.56     10115437.94
      3717658.01     10115248.88      3716351.77     10114790.92
#Sta/Elev= 30
  4114.9  257.67  4200.9  254.65    4244   250.5  4308.5  248.34  4351.5  248.89
  4362.2  247.05  4375.9  247.22  4424.6   242.7  4538.2  239.93  4558.4  238.35
  4567.9  239.31  4985.9  243.54  4989.9242.0347  4999.6  239.44  5007.5  239.58
  5018.4  242.06  5029.4  243.03    5128   240.4  5203.2  241.59  5567.6  241.65
  5620.5  242.79  5631.1  241.33  5652.3  242.73  6004.4  243.97  6298.6  247.83
  6383.5  251.24  6458.9  256.43  6510.3  255.54  6572.3   256.6  6591.3   255.6
#Mann= 3 , 0 , 0
  4114.9     .11       0  4989.9     .07       0  5018.4     .11       0
Bank Sta=4989.9,5018.4
XS Rating Curve= 0 ,0
Exp/Cntr=0.3,0.1

Type RM Length L Ch R = 1 ,10304   ,432,432,432
BEGIN DESCRIPTION:
CCLC 024 16.0
END DESCRIPTION:
XS GIS Cut Line= 3
      3718167.85     10116261.07      3718232.26     10115378.62
      3718167.85      10114511.1
#Sta/Elev= 30
  4115.2   258.7  4182.1  255.86  4225.5  255.62  4255.6  252.01  4335.8  250.09
  4345.8  248.45  4375.9  247.44  4385.9  249.39  4395.9   248.3    4406  245.46
  4446.1   241.1  4536.3  238.89  4636.6  238.86  4827.1  241.69  4947.4  241.42
  4977.5   242.4 4981.25 241.065  4987.5  238.84  5001.1  237.98    5014  237.98
 5016.59241.0754  5017.6  242.33  5087.8  240.21  5218.1  239.61  5670.9  246.89
  5779.7  250.68  5798.6  254.31  5803.6  253.87  5859.9  266.77  5869.9  267.18
#Mann= 3 , 0 , 0
  4115.2     .17       0 4981.25     .09       0 5016.59     .17       0
Bank Sta=4981.25,5016.59
XS Rating Curve= 0 ,0
Exp/Cntr=0.3,0.1

Type RM Length L Ch R = 1 ,9872    ,368,368,368
BEGIN DESCRIPTION:
CCLC 024 15.0
END DESCRIPTION:
XS GIS Cut Line= 3
      3718167.84     10116361.09      3718662.26     10115347.99
      3718867.85     10114261.07
#Sta/Elev= 30
  3872.7  260.76  3976.9   260.1  4089.5  255.18  4207.7  248.39  4284.4  247.49
  4297.8  246.12  4306.7  247.56  4320.4  247.51  4328.9  244.43  4382.4  240.15
  4404.9  240.86    4507  238.95  4673.9  240.46  4934.2  239.52  4979.2  240.75
  4995.5  238.91  4995.6  236.73  4996.1  236.23    5009  236.23 5013.58238.9025
  5017.2  240.83  5027.4   242.3  5037.6  240.54  5088.5  238.49  5210.6  237.83
  5326.8  238.99    5489  243.38  5703.4  252.62  5970.2  270.98  6106.2  275.67
#Mann= 3 , 0 , 0
  3872.7     .15       0  4995.5     .08       0 5013.58     .15       0
Bank Sta=4995.5,5013.58
XS Rating Curve= 0 ,0
Exp/Cntr=0.3,0.1

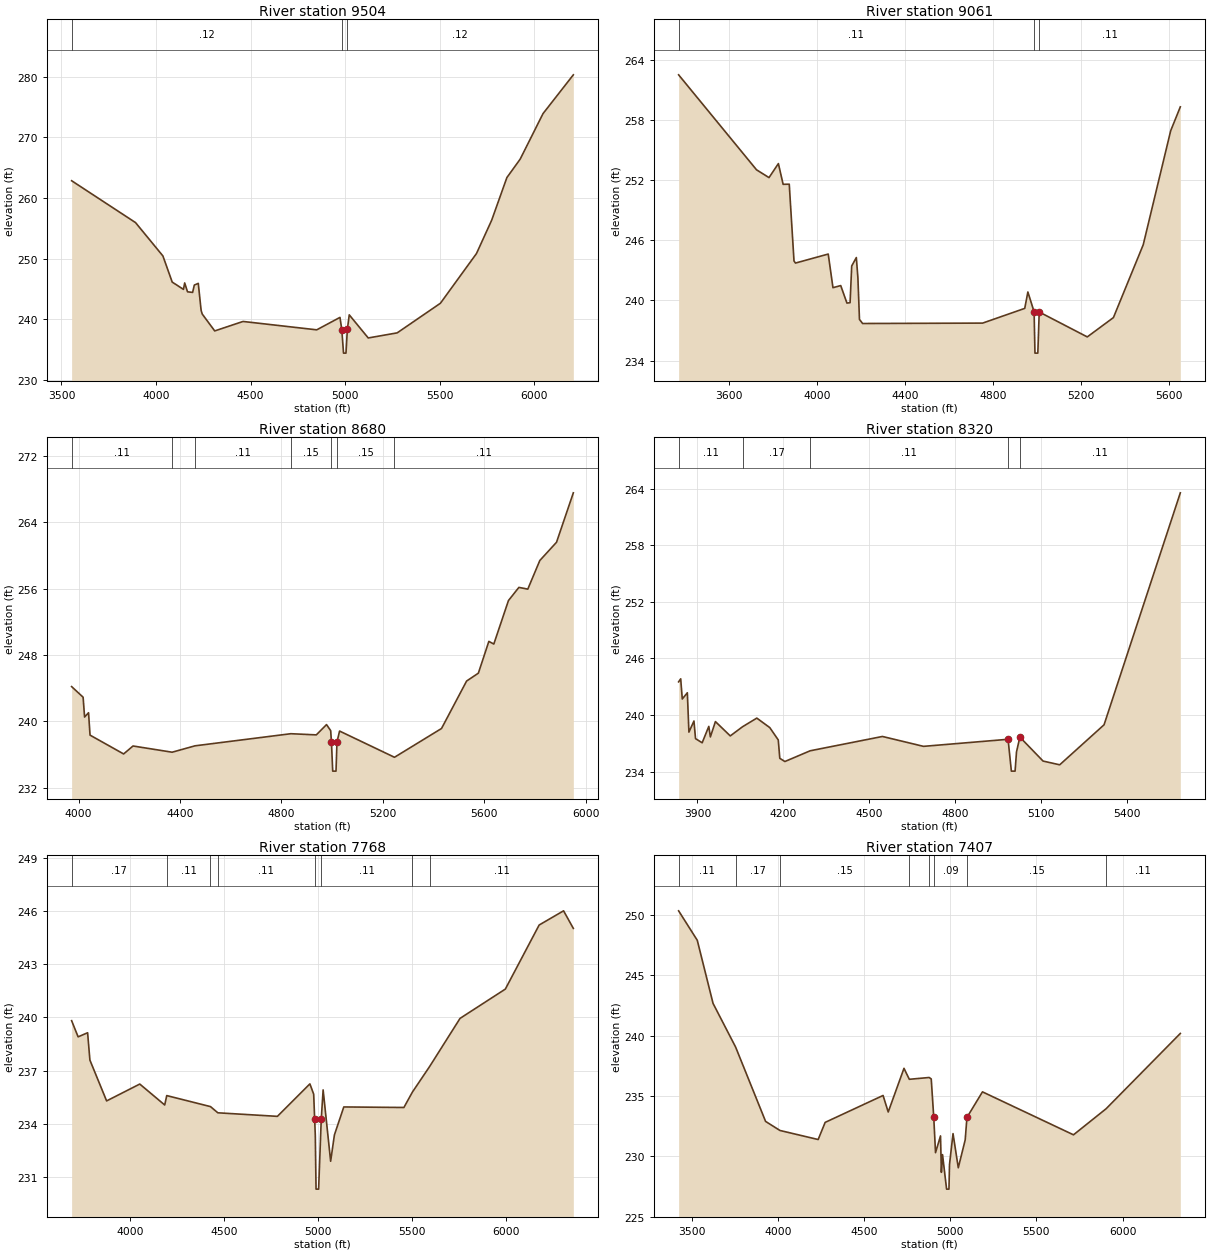
Type RM Length L Ch R = 1 ,9504    ,443,443,443
BEGIN DESCRIPTION:
CCLC 024 14.0
END DESCRIPTION:
XS GIS Cut Line= 3
      3718217.88     10116511.03      3719027.66      10115312.8
      3718917.86     10114111.11
#Sta/Elev= 30
  3553.8  262.87  3891.7  255.97  4036.5  250.47  4085.7  246.16  4145.2  244.96
  4151.6  246.02  4166.6  244.56  4193.6  244.46  4202.5  245.67  4223.5  245.95
  4238.5  241.51  4244.5  240.89  4310.4  238.11  4460.3  239.67  4849.9  238.29
  4972.7  240.34 4982.39238.3215  4991.5  234.45  5004.5  234.45  5011.8  238.37
  5021.8  240.76  5122.2  236.95  5275.3  237.79  5503.8  242.67  5694.6  250.87
  5774.9  256.36  5855.3  263.39  5925.6  266.43  6046.5  273.94  6206.7  280.33
#Mann= 3 , 0 , 0
  3553.8     .12       0 4982.39     .08       0  5011.8     .12       0
Bank Sta=4982.39,5011.8
XS Rating Curve= 0 ,0
Exp/Cntr=0.3,0.1

Type RM Length L Ch R = 1 ,9061    ,381,381,381
BEGIN DESCRIPTION:
CCLC 024 13.0
END DESCRIPTION:
XS GIS Cut Line= 3
      3718367.82     10116511.11       3719467.7     10115311.38
      3719717.84     10114711.11
#Sta/Elev= 30
  3372.4  262.55  3726.1  253.06  3782.8  252.28  3825.4  253.68  3846.9  251.61
  3874.7  251.62  3896.3  243.95    3903  243.74  4051.7  244.64  4073.2  241.28
  4108.4  241.49  4136.7  239.74  4150.9  239.78  4158.3  243.45  4179.3  244.29
  4186.4  242.28  4193.5  238.11  4207.7   237.7  4752.7  237.74  4943.9  239.21
  4958.1  240.85  4986.4  238.87  4990.3  234.74  5003.3  234.74  5009.6  238.85
  5227.8  236.36  5346.5  238.29  5481.9  245.57  5606.5  256.96  5650.3  259.35
#Mann= 3 , 0 , 0
  3372.4     .11       0  4986.4     .07       0  5009.6     .11       0
Bank Sta=4986.4,5009.6
XS Rating Curve= 0 ,0
Exp/Cntr=0.3,0.1

Type RM Length L Ch R = 1 ,8680    ,360,360,360
BEGIN DESCRIPTION:
CCLC 024 12.0
END DESCRIPTION:
XS GIS Cut Line= 3
      3718996.52     10115920.78      3719829.88     10115425.97
      3720074.68     10114446.79
#Sta/Elev= 30
  3972.8  244.19  4018.1  242.91  4023.9  240.52  4039.5  241.04  4045.4  238.34
  4177.9  236.07  4214.9  237.03  4369.2  236.28  4459.3  237.05  4837.3  238.51
  4937.8  238.37    4978  239.61  4994.4  238.88 4997.44237.4886  5002.4     234
  5015.4     234  5019.2  237.51  5029.5  238.83    5246  235.67  5431.5  239.14
  5530.4  244.86  5576.8  245.81  5618.1  249.64  5637.7  249.32  5695.4  254.56
  5736.6  256.15  5771.7  255.94  5819.1  259.39    5885  261.59  5951.3  267.55
#Mann= 7 ,-1 , 0
  3972.8     .11       0  4369.2     .17       0  4459.3     .11       0
  4837.3     .15       0 4997.44     .09       0  5019.2     .15       0
    5246     .11       0
Bank Sta=4997.44,5019.2
XS Rating Curve= 0 ,0
Exp/Cntr=0.3,0.1

Type RM Length L Ch R = 1 ,8320    ,552,552,552
BEGIN DESCRIPTION:
CCLC 024 11.0
END DESCRIPTION:
XS GIS Cut Line= 3
      3719137.18     10115889.51      3720204.88     10115410.34
      3720496.28     10114905.61
#Sta/Elev= 30
  3834.3  243.52  3841.6  243.84  3847.1   241.7  3864.8  242.36  3870.3  238.18
  3887.9  239.36  3893.4  237.49  3916.6  237.05  3939.8  238.79  3945.3  237.67
  3962.9   239.3  4014.8  237.78  4058.1  238.76  4107.5  239.67  4152.9  238.66
  4182.5  237.35  4187.9   235.4  4205.6  235.06    4294   236.2  4546.5  237.72
    4690  236.67  4985.5  237.42    4997  234.04    5010  234.04    5015  236.09
  5026.8  237.65  5107.7  235.11  5165.9  234.71  5320.9  238.96  5587.4  263.59
#Mann= 5 ,-1 , 0
  3834.3     .11       0  4058.1     .17       0    4294     .11       0
  4985.5     .06       0  5026.8     .11       0
Bank Sta=4985.5,5026.8
XS Rating Curve= 0 ,0
Exp/Cntr=0.3,0.1

Type RM Length L Ch R = 1 ,7768    ,361,361,361
BEGIN DESCRIPTION:
CCLC 024 10.0
END DESCRIPTION:
XS GIS Cut Line= 3
      3719423.67     10115780.13      3720721.29     10115584.36
      3722079.89     10115587.43
#Sta/Elev= 30
  3687.7  239.82  3722.3  238.91  3772.8  239.14    3785   237.6    3874   235.3
  4050.5  236.25  4183.3  235.07  4194.1   235.6  4426.9  234.98  4466.1  234.63
  4783.2  234.43  4956.1  236.26  4976.3  235.68 4981.39234.3009  4984.9  233.35
  4988.9  230.33  5002.6  230.33  5016.6  234.27  5026.6  235.92  5066.6   231.9
  5086.6  233.38  5136.6  234.96  5456.6  234.93    5502   235.8  5593.7  237.24
  5755.5  239.95  5996.6   241.6  6176.6  245.21  6306.6  246.01  6358.6  245.02
#Mann= 8 ,-1 , 0
  3687.7     .17       0  4194.1     .11       0  4426.9     .15       0
  4466.1     .11       0 4981.39     .06       0  5016.6     .11       0
    5502     .15       0  5593.7     .11       0
Bank Sta=4981.39,5016.6
XS Rating Curve= 0 ,0
Exp/Cntr=0.3,0.1

Type RM Length L Ch R = 1 ,7407    ,1131,1131,1131
BEGIN DESCRIPTION:
CCLC 024 9.0
END DESCRIPTION:
XS GIS Cut Line= 3
      3719491.29     10115993.69      3721095.51     10115707.22
       3722374.8     10115743.62
#Sta/Elev= 30
  3425.2  250.34  3533.4   247.9  3624.9  242.67  3755.8  239.05  3929.6  232.89
  4012.9  232.14  4234.4  231.39    4275  232.81  4610.8  235.04  4640.7  233.67
  4732.1  237.29    4763  236.38  4878.2  236.53  4890.1  236.41  4904.8  233.22
    4915   230.3  4943.9  231.69    4949  228.67  4955.6  230.14  4979.2  227.28
  4992.9  227.28  4996.2  229.34  5016.5  231.88    5047  229.05  5087.1  231.36
  5097.2  233.22  5187.2  235.34    5715  231.78  5904.2  233.94  6334.6  240.18
#Mann= 8 ,-1 , 0
  3425.2     .11       0  3755.8     .17       0  4012.9     .15       0
    4763     .11       0  4878.2     .15       0  4904.8     .09       0
  5097.2     .15       0  5904.2     .11       0
Bank Sta=4904.8,5097.2
XS Rating Curve= 0 ,0
Exp/Cntr=0.3,0.1

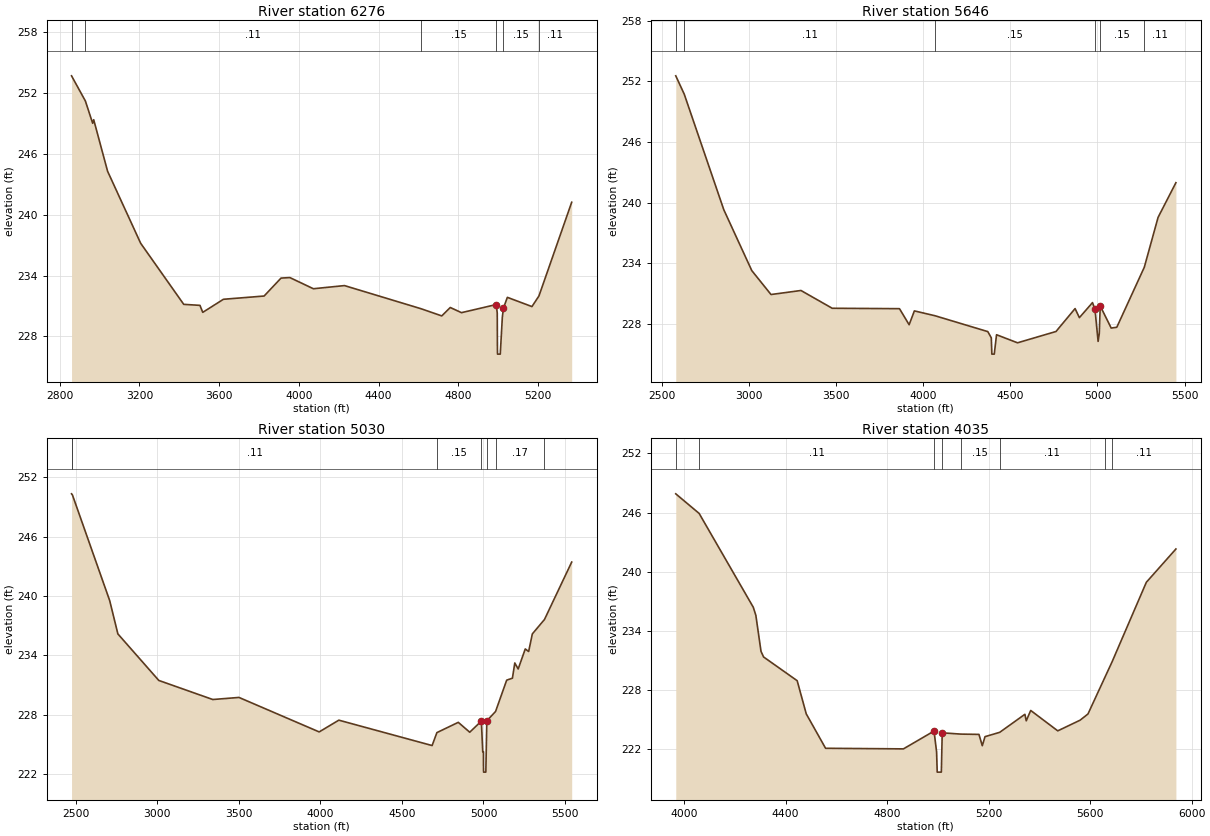
Type RM Length L Ch R = 1 ,6276    ,630,630,630
BEGIN DESCRIPTION:
Mapping XS d1ad49b5
END DESCRIPTION:
XS GIS Cut Line= 2
      3720017.43     10116733.24        3722382.      10115889.5
#Sta/Elev= 30
  2859.1  253.71  2928.5  251.23  2965.1  249.03  2970.4  249.38    3040   244.3
  3206.2  237.19  3422.3  231.17  3503.6  231.07  3517.8  230.38  3621.5  231.67
  3825.7  231.99  3910.7  233.76  3955.1  233.81    4073  232.71  4229.2  233.02
  4613.1  230.74  4717.6  230.03  4760.2  230.86  4816.5  230.35  4990.7  231.15
    4996  230.31  4996.9  226.76  4997.4  226.26  5011.2  226.26  5021.5  229.88
  5026.8  230.78  5046.8  231.86  5170.2  230.95  5205.4     232  5369.7  241.24
#Mann= 6 ,-1 , 0
  2859.1     .17       0  2928.5     .11       0  4613.1     .15       0
  4990.7     .09       0  5026.8     .15       0  5205.4     .11       0
Bank Sta=4990.7,5026.8
XS Rating Curve= 0 ,0
Exp/Cntr=0.3,0.1

Type RM Length L Ch R = 1 ,5646    ,616,616,616
BEGIN DESCRIPTION:
Mapping XS 0d2dc457
END DESCRIPTION:
XS GIS Cut Line= 3
      3720033.03     10116748.88       3722277.8     10116550.97
      3722854.37     10116327.61
#Sta/Elev= 30
  2578.5  252.54  2627.1  250.73  2854.4  239.28    3015  233.26  3125.4  230.89
  3297.4  231.29  3476.8  229.53  3863.1  229.49  3918.5   227.9  3948.6  229.27
    4067  228.79  4370.2  227.22  4390.3   226.6  4393.5  224.99  4407.3  224.99
  4420.4  226.91  4540.9  226.11  4761.8  227.23  4871.4   229.5    4896   228.6
  4971.4  230.09  4985.7  229.41  5003.6  226.25  5010.3  227.03  5015.7  229.76
  5078.7  227.57  5110.9  227.65  5268.8  233.59    5348  238.53  5450.3  241.96
#Mann= 6 ,-1 , 0
  2578.5     .17       0  2627.1     .11       0    4067     .15       0
  4985.7     .09       0  5015.7     .15       0  5268.8     .11       0
Bank Sta=4985.7,5015.7
XS Rating Curve= 0 ,0
Exp/Cntr=0.3,0.1

Type RM Length L Ch R = 1 ,5030    ,995,995,995
BEGIN DESCRIPTION:
CCLC 024 8.0
END DESCRIPTION:
XS GIS Cut Line= 3
       3720074.7     10116774.93      3722591.73     10116994.59
      3723017.84     10116661.08
#Sta/Elev= 30
  2473.4  250.34    2479  250.22  2707.4  239.53  2757.6  236.16  3008.6  231.45
  3339.8  229.52  3500.4  229.73  3992.3  226.24  4112.8  227.43  4684.9  224.86
  4714.4  226.17  4845.5  227.21  4915.8  226.21 4987.13227.3377  4995.5  224.23
    5000  224.23  5000.2  222.67  5000.7  222.17  5014.5  222.17  5020.5  227.36
  5074.2  228.31  5142.4  231.48  5177.6  231.68  5192.1  233.22  5212.9  232.61
  5256.3  234.64  5277.1  234.38  5299.7  236.16  5374.2  237.62  5541.1  243.43
#Mann= 7 ,-1 , 0
  2473.4     .17       0    2479     .11       0  4714.4     .15       0
 4987.13     .09       0  5020.5     .15       0  5074.2     .17       0
  5374.2     .11       0
Bank Sta=4987.13,5020.5
XS Rating Curve= 0 ,0
Exp/Cntr=0.3,0.1

Type RM Length L Ch R = 1 ,4035    ,462,462,462
BEGIN DESCRIPTION:
CCLC 024 7.0
END DESCRIPTION:
XS GIS Cut Line= 3
      3722517.84     10118611.11      3722708.54     10117596.57
      3723017.86     10116711.04
#Sta/Elev= 30
  3967.7   247.9  4059.8  245.91    4273  236.39  4283.2  235.57  4303.5  231.91
  4313.7  231.34    4446  228.93  4481.8  225.56  4557.9  222.07  4864.6  222.01
  4985.2  223.82  4995.2  221.71  4997.7  219.65  5013.9  219.65  5017.4  223.64
    5090  223.51  5162.1  223.48  5175.3  222.33  5185.9  223.25  5243.9  223.69
  5343.1  225.52  5348.4  224.86    5366  225.91  5472.6  223.84  5560.4  224.92
  5591.5  225.55  5658.6  229.29  5686.6  230.85  5821.5  238.92    5938   242.3
#Mann= 8 ,-1 , 0
  3967.7     .17       0  4059.8     .11       0  4985.2     .06       0
  5017.4     .11       0    5090     .15       0  5243.9     .11       0
  5658.6     .15       0  5686.6     .11       0
Bank Sta=4985.2,5017.4
XS Rating Curve= 0 ,0
Exp/Cntr=0.3,0.1