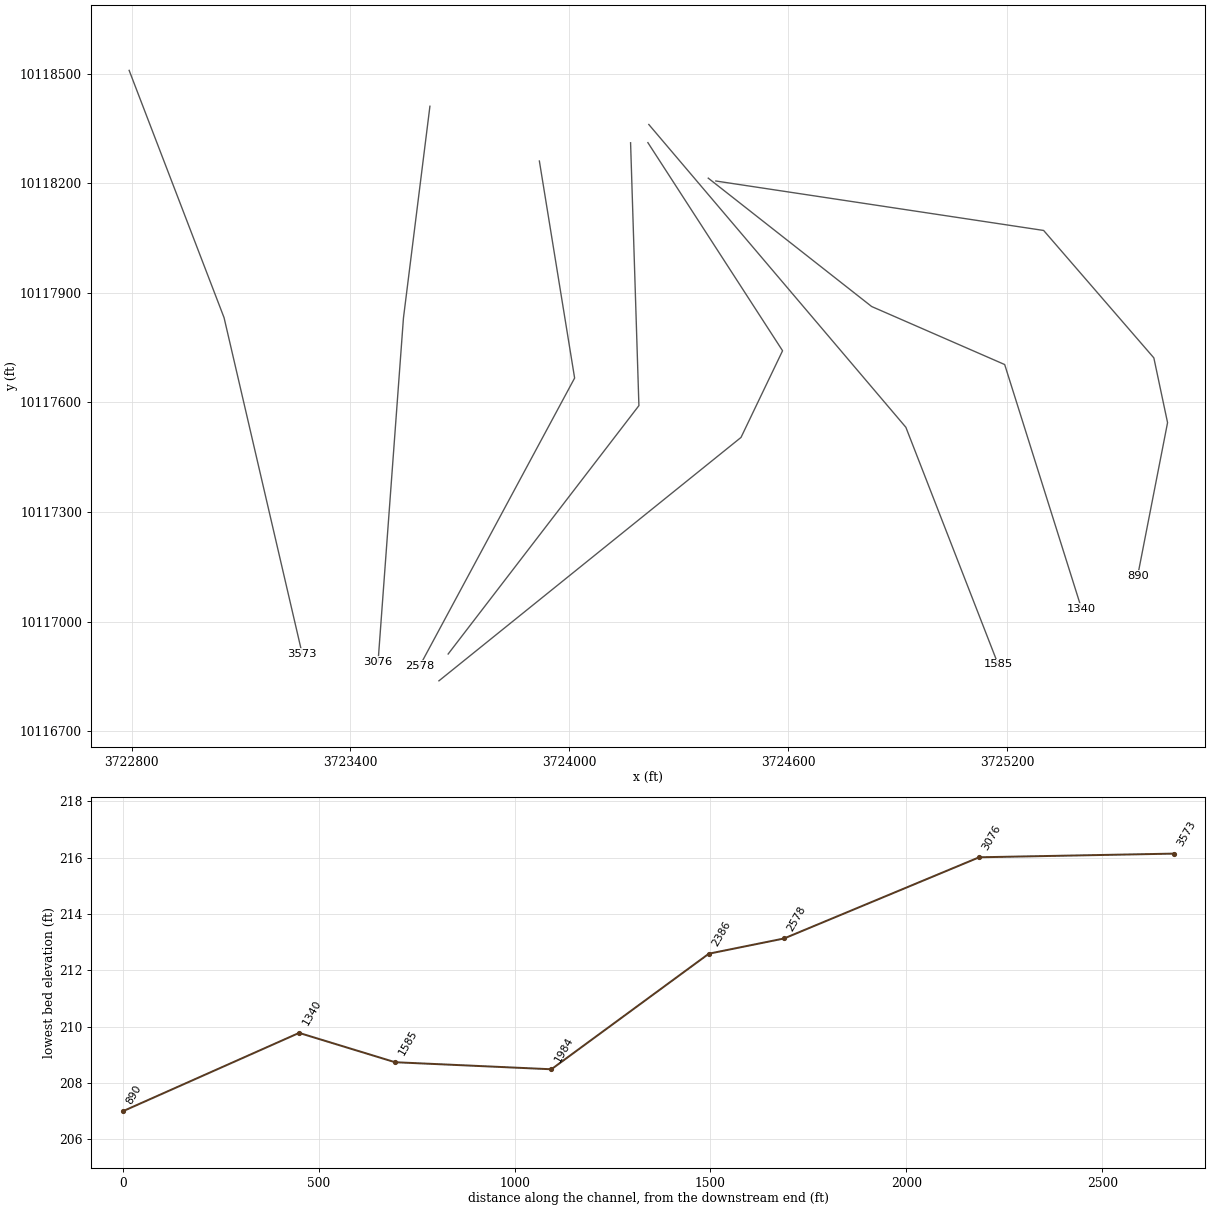
HEC-RAS study CCLC 024.prj: CCLC 024 Base Level Engineering

--- CCLC 024.g01 (geometry) --- (continued)

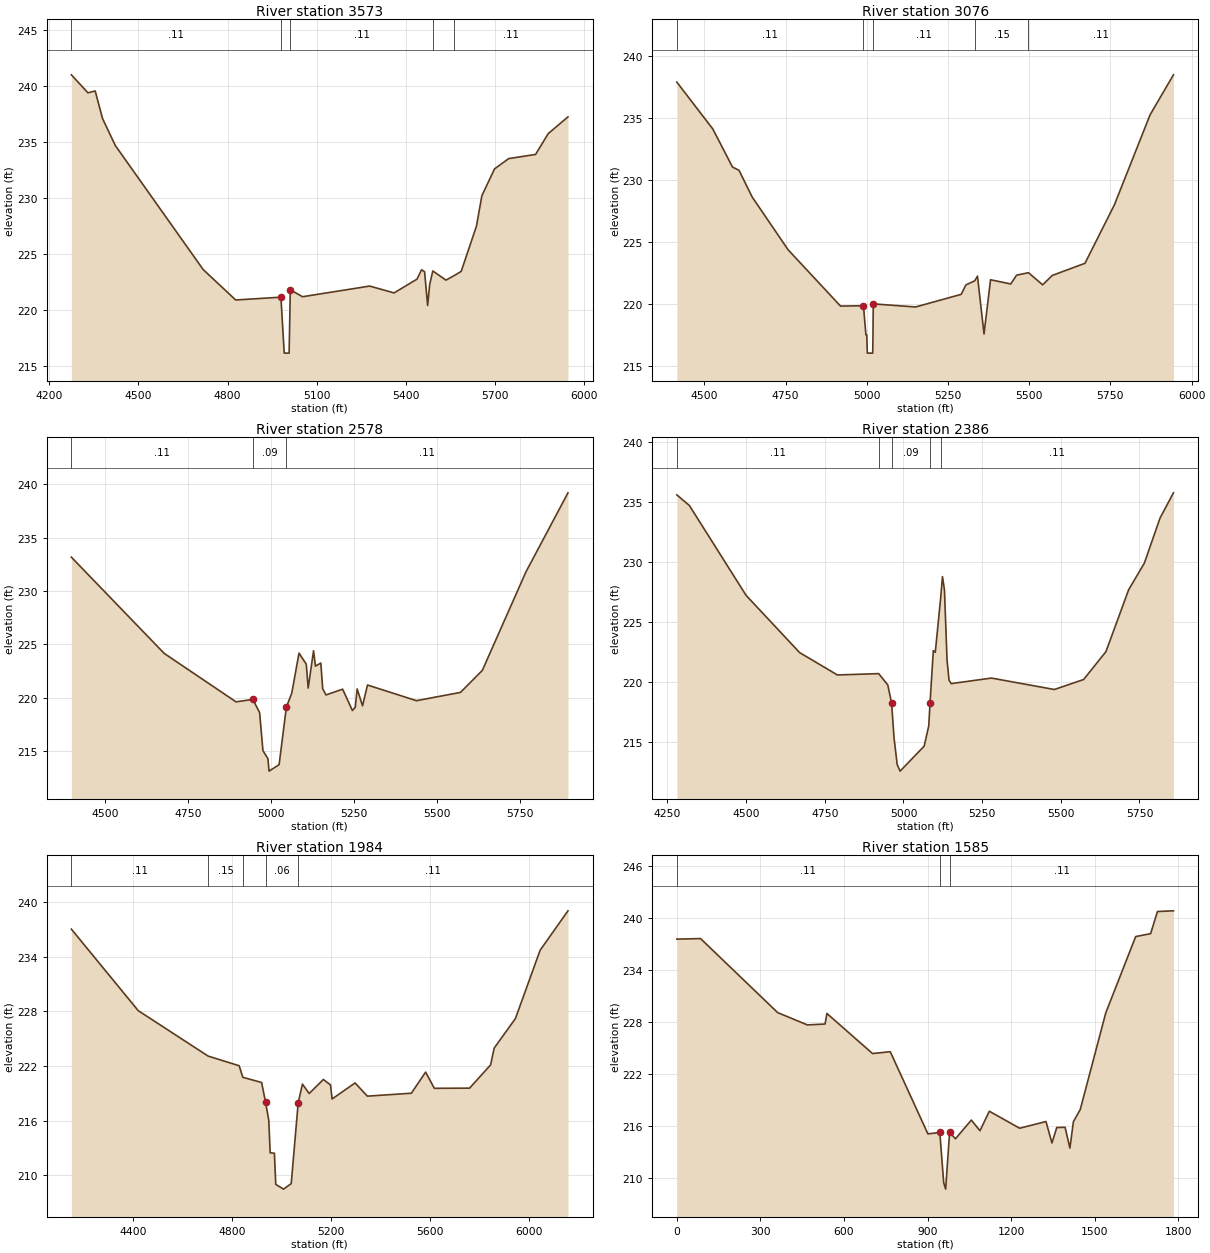
Type RM Length L Ch R = 1 ,3573    ,497,497,497
BEGIN DESCRIPTION:
CCLC 024 6.0
END DESCRIPTION:
XS GIS Cut Line= 3
      3722793.44     10118509.26      3723053.62     10117832.02
      3723267.84     10116911.11
#Sta/Elev= 30
  4274.5  240.96  4330.1  239.36  4354.7  239.52  4379.4  237.06  4422.5  234.65
  4718.1  223.59  4827.4  220.88  4979.6  221.13  4990.7  216.14  5007.2  216.14
  5011.2  221.79  5052.3  221.17  5278.2  222.12  5360.3  221.51  5437.6  222.74
  5452.7  223.57    5463   223.4  5473.3  220.39  5480.2  222.27  5490.7  223.47
  5534.9  222.65  5560.3  223.02  5586.2  223.43  5637.5  227.46  5655.8  230.18
  5698.4  232.57  5746.1  233.49  5836.5  233.86  5879.1  235.72  5945.5  237.21
#Mann= 5 ,-1 , 0
  4274.5     .11       0  4979.6     .06       0  5011.2     .11       0
  5490.7     .15       0  5560.3     .11       0
Bank Sta=4979.6,5011.2
XS Rating Curve= 0 ,0
Exp/Cntr=0.3,0.1

Type RM Length L Ch R = 1 ,3076    ,498,498,498
BEGIN DESCRIPTION:
CCLC 024 5.0
END DESCRIPTION:
XS GIS Cut Line= 3
      3723617.85     10118411.06      3723545.28     10117830.99
      3723475.72     10116889.55
#Sta/Elev= 30
  4415.4  237.91  4526.2  234.12  4586.7  231.05  4606.9  230.78  4647.2  228.63
    4758  224.36  4919.3  219.81  4989.8  219.84  4997.4  217.49    5000  217.49
  5001.7  216.01  5018.2  216.01  5018.7  216.51    5020  219.99  5150.3  219.74
  5290.7  220.76    5305  221.52  5332.1  221.85  5340.8  222.23  5360.9  217.56
    5381  221.94  5443.1   221.6  5461.2  222.31  5497.8  222.51  5541.4  221.53
  5571.1  222.29  5671.7  223.27    5762  227.98  5872.3  235.28    5944   238.5
#Mann= 5 ,-1 , 0
  4415.4     .11       0  4989.8     .06       0    5020     .11       0
  5332.1     .15       0  5497.8     .11       0
Bank Sta=4989.8,5020
XS Rating Curve= 0 ,0
Exp/Cntr=0.3,0.1

Type RM Length L Ch R = 1 ,2578    ,192,192,192
BEGIN DESCRIPTION:
CCLC 024 4.0
END DESCRIPTION:
XS GIS Cut Line= 3
      3723917.86     10118261.03      3724014.47     10117666.73
      3723590.29     10116879.08
#Sta/Elev= 30
  4397.9  233.18  4677.4  224.17  4894.3  219.62  4944.9  219.85  4965.2  218.62
  4975.3  215.05  4990.2   214.3  4993.8  213.13    5024  213.74  5045.9  219.13
  5062.1  220.43    5084  224.19  5105.9  223.15  5111.6  220.91  5127.8  224.41
  5133.5  222.97  5149.7  223.26  5155.4  220.85  5165.4  220.27  5215.4  220.81
  5244.9  218.81  5253.6  219.12  5259.2  220.83  5275.5  219.25  5290.4   221.2
    5438  219.73  5570.7  220.51  5636.5  222.57  5767.9   231.8  5894.6  239.21
#Mann= 3 , 0 , 0
  4397.9     .11       0  4944.9     .09       0  5045.9     .11       0
Bank Sta=4944.9,5045.9
XS Rating Curve= 0 ,0
Exp/Cntr=0.3,0.1

Type RM Length L Ch R = 1 ,2386    ,402,402,402
BEGIN DESCRIPTION:
CCLC 024 3.0
END DESCRIPTION:
XS GIS Cut Line= 3
      3724167.85     10118311.05      3724190.68     10117591.21
      3723667.83     10116911.05
#Sta/Elev= 30
  4279.8  235.57  4319.8  234.68  4499.9  227.21    4670  222.45    4790  220.59
  4921.2   220.7  4950.1  219.76 4962.11218.2784  4970.1  215.33  4980.1  213.13
  4989.3  212.59  5065.8  214.67  5080.3  216.35 5084.46 218.288  5094.8  222.61
  5101.1  222.48  5118.7  227.13  5123.9  228.77  5130.2  227.67  5138.4  221.85
  5144.7  220.17  5151.5  219.87  5279.7  220.33  5479.5  219.38  5572.4  220.21
  5643.4  222.53  5715.6  227.68  5765.4  229.89  5815.3  233.64  5857.9  235.74
#Mann= 5 ,-1 , 0
  4279.8     .11       0  4921.2     .15       0 4962.11     .09       0
 5084.46     .15       0  5118.7     .11       0
Bank Sta=4962.11,5084.46
XS Rating Curve= 0 ,0
Exp/Cntr=0.3,0.1

Type RM Length L Ch R = 1 ,1984    ,399,399,399
BEGIN DESCRIPTION:
CCLC 024 2.0
END DESCRIPTION:
XS GIS Cut Line= 4
       3724215.3     10118311.39      3724584.45     10117741.48
      3724470.51     10117504.09      3723642.59     10116837.59
#Sta/Elev= 30
  4152.4  237.04  4422.3  228.09  4704.5   223.1    4830  222.04  4844.6  220.77
  4920.6   220.2  4936.6218.0242  4949.5  216.05  4955.1  212.48  4972.2  212.43
  4977.7  209.01  5009.1  208.49  5040.1  209.09  5068.3  217.98  5085.4  220.02
  5112.5  218.99    5170  220.53  5198.8  219.93  5205.2  218.39    5298  220.15
  5347.6   218.7  5525.2  219.02  5582.8  221.34    5618  219.56  5760.3  219.58
  5845.1  222.13  5859.5  223.97  5945.4  227.22  6045.1  234.72  6157.6  239.05
#Mann= 5 ,-1 , 0
  4152.4     .11       0  4704.5     .15       0  4844.6     .11       0
  4936.6     .06       0  5068.3     .11       0
Bank Sta=4936.6,5068.3
XS Rating Curve= 0 ,0
Exp/Cntr=0.3,0.1

Type RM Length L Ch R = 1 ,1585    ,245,245,245
XS GIS Cut Line= 3
      3724217.85     10118361.07      3724922.43     10117531.85
      3725175.03     10116883.41
#Sta/Elev= 30
       0  237.56    85.1  237.62   361.9  229.09   468.4  227.67   532.1  227.77
   538.7  228.99   702.4  224.37   766.1  224.58   901.2  215.11     944  215.27
   957.9  209.47   964.9  208.74   979.1  215.29    1000  214.54  1057.1   216.7
  1088.1  215.47  1121.7  217.72  1230.5  215.76  1325.1  216.53  1346.5  214.06
  1363.7  215.84  1393.6  215.87  1410.9  213.47  1423.5  216.52    1448  217.91
  1539.7  229.06    1647  237.85  1700.7  238.19  1725.2  240.74  1782.6  240.82
#Mann= 3 , 0 , 0
       0     .11       0     944     .06       0   979.1     .11       0
Bank Sta=944,979.1
XS Rating Curve= 0 ,0
Exp/Cntr=0.3,0.1

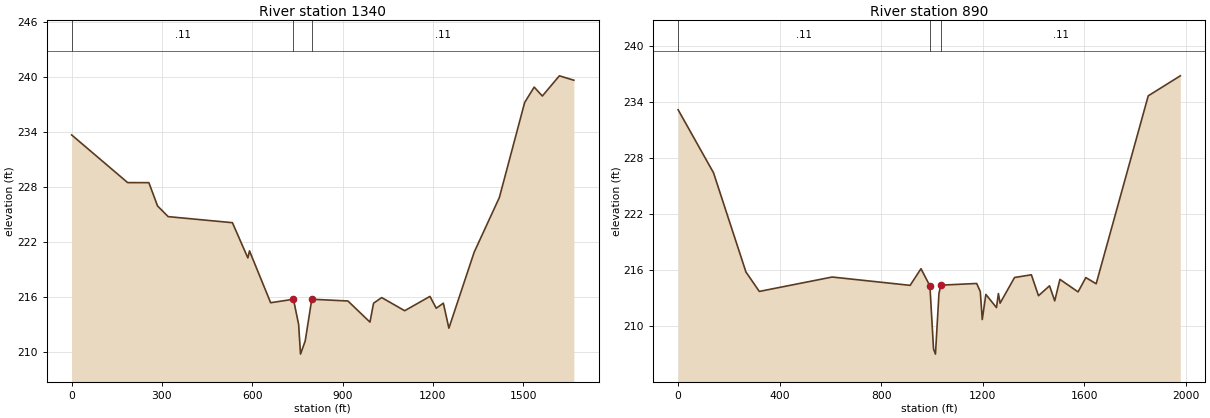
Type RM Length L Ch R = 1 ,1340    ,450,450,450
XS GIS Cut Line= 4
      3724380.76     10118214.14      3724828.68     10117862.58
      3725193.26     10117703.72       3725404.2     10117034.45
#Sta/Elev= 30
       0  233.66   185.9  228.47   256.5  228.46   285.4  225.92   320.6  224.76
     534   224.1   585.3  220.26   590.7  221.03     661  215.38   736.7  215.76
   753.9  213.02   760.2  209.78   775.8  211.22   797.6  215.76   917.6  215.57
   990.8  213.27  1002.8  215.33  1029.9  215.94  1106.2  214.51  1190.1  216.07
    1211  214.78  1234.6  215.33    1253  212.61  1336.9  220.88  1420.7  226.85
  1504.6  237.19  1536.3  238.87  1563.4   237.9  1619.9   240.1    1668  239.62
#Mann= 3 , 0 , 0
       0     .11       0   736.7     .06       0   797.6     .11       0
Bank Sta=736.7,797.6
XS Rating Curve= 0 ,0
Exp/Cntr=0.3,0.1

Type RM Length L Ch R = 1 ,890     ,0,0,0
XS GIS Cut Line= 5
      3724401.59     10118206.33      3725300.03     10118070.91
      3725602.11     10117721.95       3725639.7     10117544.56
      3725557.84      10117125.6
#Sta/Elev= 30
       0  233.15   139.4  226.41   267.2  215.79   319.8  213.71   606.8  215.25
   913.9  214.36   956.7  216.14   991.8   214.3  1006.1  207.55  1013.7     207
  1027.4  213.48  1034.6  214.38  1176.1  214.56  1190.3  213.69    1198   210.7
  1212.2  213.39    1254  211.98  1261.6  213.48  1268.2  212.45  1325.2   215.2
  1391.5  215.49  1419.5  213.25    1463  214.31  1483.5   212.7  1503.9     215
  1575.4  213.66    1606  215.19  1646.7  214.53  1851.8  234.64  1978.1  236.78
#Mann= 3 , 0 , 0
       0     .11       0   991.8     .06       0  1034.6     .11       0
Bank Sta=991.8,1034.6
XS Rating Curve= 0 ,0
Exp/Cntr=0.3,0.1

Chan Stop Cuts=-1
Use User Specified Reach Order=0
Composite Channel Slope=5