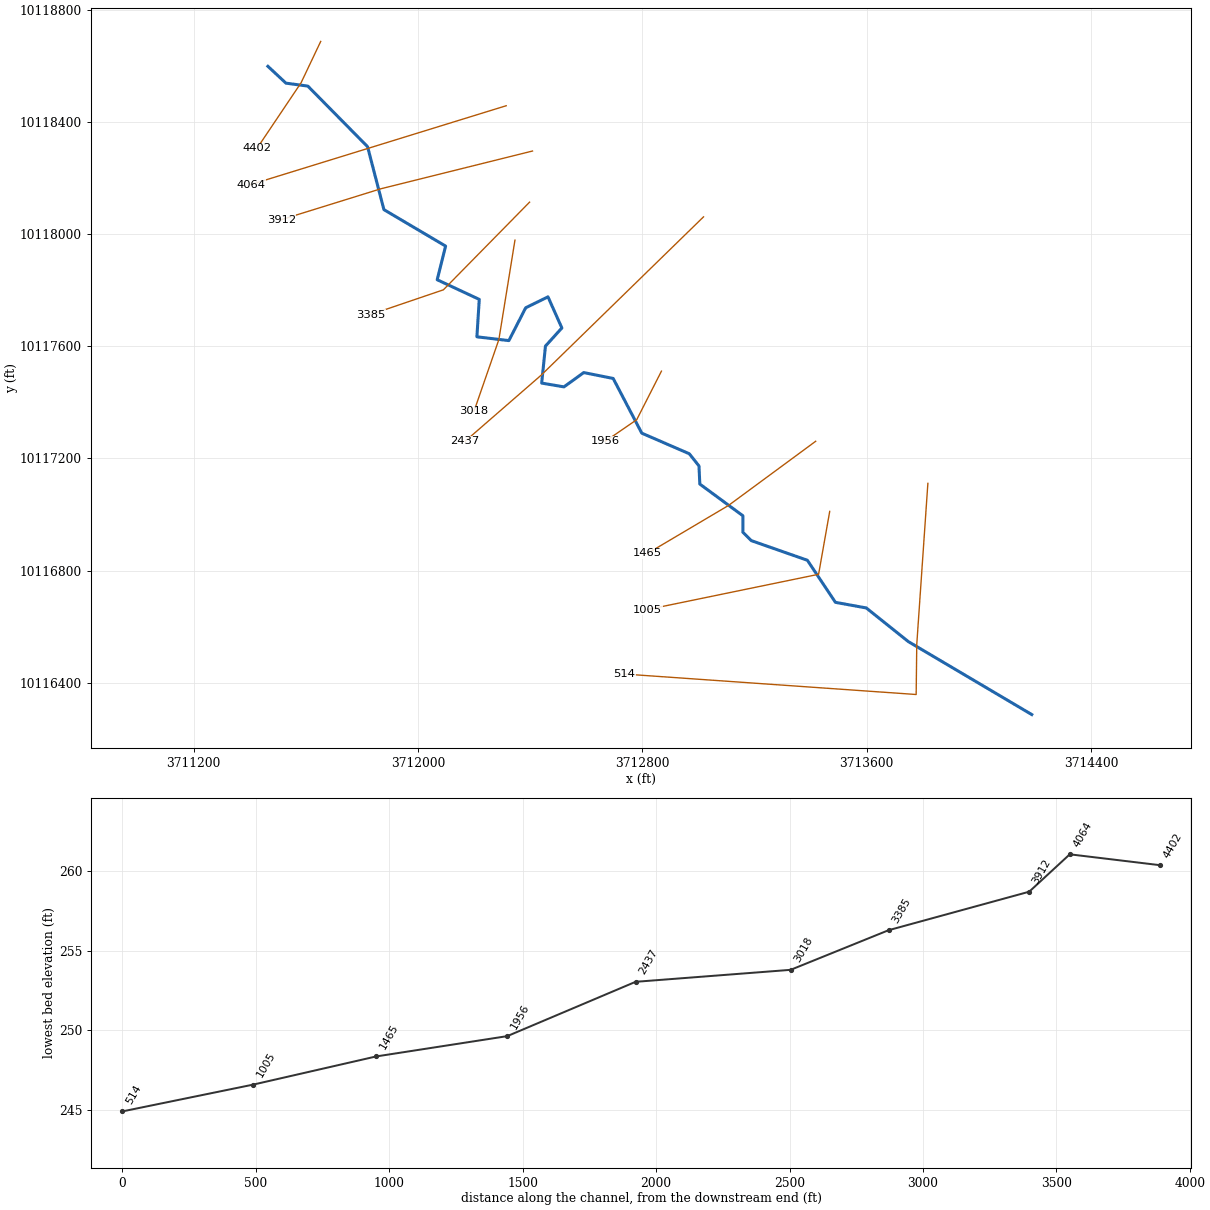
--- CCLC 025.prj (project) ---

Proj Title=CCLC 025 Base Level Engineering
Current Plan=p01
Default Exp/Contr=0.3,0.1
English Units
Geom File=g01
Flow File=f01
Flow File=f02
Plan File=p01
Y Axis Title=Elevation
X Axis Title(PF)=Main Channel Distance
X Axis Title(XS)=Station
BEGIN DESCRIPTION:
CCLC 025
END DESCRIPTION:
DSS Export Rating Curves= 0
DSS Export Rating Curve Sorted= 0
DSS Export Volume Flow Curves= 0
DXF OffsetX= 0
DXF OffsetY= 0
DXF ScaleX= 1
DXF ScaleY= 10

--- CCLC 025.p01 (plan) ---

Plan Title=Multiple Run
Program Version=4.10
Short Identifier=Multiple
Geom File=g01
Flow File=f01
Subcritical Flow
K Sum by GR= 0
Std Step Tol= 0.01
Critical Tol= 0.01
Num of Std Step Trials= 20
Max Error Tol= 0.3
Flow Tol Ratio= 0.001
Split Flow NTrial= 30
Split Flow Tol= 0.02
Split Flow Ratio= 0.02
Log Output Level= 0
Friction Slope Method= 1
Unsteady Friction Slope Method= 2
Unsteady Bridges Friction Slope Method= 1
Parabolic Critical Depth
Global Vel Dist= 1 , 1 , 1
Global Log Level= 0
CheckData=True
Encroach Param=-1 ,0,0, 0
BEGIN DESCRIPTION:
Multiple Run
END DESCRIPTION:
Computation Interval=1HOUR
Output Interval=1HOUR
Run HTab= 0
Run UNet= 0
Run PostProcess= 0
Run WQNet= 0
UNET Theta= 1
UNET Theta Warmup= 1
UNET ZTol= 0.02
UNET ZSATol= 0.05
UNET MxIter= 20
UNET MaxInSteps= 0
UNET DtIC= 0
UNET DtMin= 0
UNET MaxCRTS= 20
UNET WFStab= 2
UNET SFStab= 1
UNET WFX= 1
UNET SFX= 1
UNET DSS MLevel= 4
UNET DZMax Abort= 100
UNET Convert EG Bridges= 0
UNET Use Existing IB Tables=-1
UNET Froude Reduction=False
UNET Froude Limit= 1
UNET Froude Power= 10
UNET Time Slicing=0,0, 5
UNET Junction Losses=0
Instantaneous Interval=1HOUR
Write IC File= 0
Write IC File at Sim End=0
Echo Input=False
Echo Parameters=False
Echo Output=False
Write Detailed= 0
WQ AD Non Conservative
WQ ULTIMATE=-1
WQ Max Comp Step=1HOUR
WQ Output Interval=15MIN
WQ Output Selected Increments= 0
WQ Output face flow=0
WQ Output face velocity=0
WQ Output face area=0
WQ Output face dispersion=0
WQ Output cell volume=0
WQ Output cell surface area=0
WQ Output cell continuity=0
WQ Output cumulative cell continuity=0
WQ Output face conc=0
WQ Output face dconc_dx=0
WQ Output face courant=0
WQ Output face peclet=0
WQ Output face adv mass=0
WQ Output face disp mass=0
WQ Output cell mass=0
WQ Output cell source sink temp=0
WQ Output cell source sink nsm=0
WQ Output MaxMinRange=-1
WQ Daily Max Min Mean=-1
WQ Daily Range=0
WQ Daily Time=0
WQ Create Restart=0
WQ Fixed Restart=0
WQ System Summary=0
WQ Use Fixed Temperature=0
Sorting and Armoring Iterations= 10
XS Update Threshold= 0.02
Hydraulics Update Threshold= 0.02
Energy Slope Method= 1
Volume Change Method= 0
XS Weighting Method= 0
Number of US Weighted Cross Sections= 1
Number of DS Weighted Cross Sections= 1
Upstream XS Weight=0.25
Main XS Weight=0.5
Downstream XS Weight=0.25
Number of DS XS's Weighted with US Boundary= 1
Upstream Boundary Weight= 1
Weight of XSs Associated with US Boundary= 0
Number of US XS's Weighted with DS Boundary= 1
Downstream Boundary Weight= 0.5
Weight of XSs Associated with DS Boundary= 0.5
Sediment Output Level= 4
Mass or Volume Output= 0
Output Increment Type= 1
Profile and TS Output Increment= 10
XS Output Flag= 0
XS Output Increment= 10
Disregard all LS=0
Disregard all Conn=0
Disregard all Breaches=0
Disregard all Pumps=0

--- CCLC 025.f01 (steady flow) ---

Flow Title=Multiple
Program Version=4.10
Number of Profiles= 7
Profile Names=10-year,25-year,50-year,1pct_min,100-year,1pct_plu,500-year
River Rch & RM=CCLC 025,Reach-1         ,4402
     796    1102    1511     682    2061    6224    3959
Boundary for River Rch & Prof#=CCLC 025,Reach-1         , 1
Up Type= 0
Dn Type= 3
Dn Slope=0.005
Boundary for River Rch & Prof#=CCLC 025,Reach-1         , 2
Up Type= 0
Dn Type= 3
Dn Slope=0.005
Boundary for River Rch & Prof#=CCLC 025,Reach-1         , 3
Up Type= 0
Dn Type= 3
Dn Slope=0.005
Boundary for River Rch & Prof#=CCLC 025,Reach-1         , 4
Up Type= 0
Dn Type= 3
Dn Slope=0.005
Boundary for River Rch & Prof#=CCLC 025,Reach-1         , 5
Up Type= 0
Dn Type= 3
Dn Slope=0.005
Boundary for River Rch & Prof#=CCLC 025,Reach-1         , 6
Up Type= 0
Dn Type= 3
Dn Slope=0.005
Boundary for River Rch & Prof#=CCLC 025,Reach-1         , 7
Up Type= 0
Dn Type= 3
Dn Slope=0.005
DSS Import GetInterval= 0
DSS Import GetPeak= 0
DSS Import FillOption= 0

--- CCLC 025.f02 (steady flow) ---

Flow Title=Orig_BLE_Flows
Program Version=4.10
Number of Profiles= 7
Profile Names=10-year,25-year,50-year,1pct_min,100-year,1pct_plu,500-year
River Rch & RM=CCLC 025,Reach-1         ,4402
     796    1080    1314     525    1585    4786    2302
Boundary for River Rch & Prof#=CCLC 025,Reach-1         , 1
Up Type= 0
Dn Type= 3
Dn Slope=0.005
Boundary for River Rch & Prof#=CCLC 025,Reach-1         , 2
Up Type= 0
Dn Type= 3
Dn Slope=0.005
Boundary for River Rch & Prof#=CCLC 025,Reach-1         , 3
Up Type= 0
Dn Type= 3
Dn Slope=0.005
Boundary for River Rch & Prof#=CCLC 025,Reach-1         , 4
Up Type= 0
Dn Type= 3
Dn Slope=0.005
Boundary for River Rch & Prof#=CCLC 025,Reach-1         , 5
Up Type= 0
Dn Type= 3
Dn Slope=0.005
Boundary for River Rch & Prof#=CCLC 025,Reach-1         , 6
Up Type= 0
Dn Type= 3
Dn Slope=0.005
Boundary for River Rch & Prof#=CCLC 025,Reach-1         , 7
Up Type= 0
Dn Type= 3
Dn Slope=0.005
DSS Import GetInterval= 0
DSS Import GetPeak= 0
DSS Import FillOption= 0

--- CCLC 025.g01 (geometry) ---

Geom Title=Existing Conditions
Program Version=4.10

River Reach=CCLC 025        ,Reach-1
Reach XY= 30
      3711464.47     10118597.73      3711528.96     10118537.74
      3711606.94     10118527.24       3711819.9     10118311.29
      3711878.23     10118086.84      3712098.23     10117956.84
      3712068.23     10117836.84      3712218.23     10117766.84
      3712209.83     10117633.41      3712323.81     10117619.92
      3712383.79     10117736.89      3712463.28     10117775.89
      3712512.77     10117664.91      3712454.28     10117600.42
      3712440.78     10117468.44      3712520.27     10117454.95
      3712590.76     10117505.94      3712695.74     10117484.94
      3712797.72     10117289.98      3712967.19     10117216.49
      3713001.68       10117173.      3713004.68     10117108.51
      3713158.23     10116995.45      3713158.23     10116936.84
      3713188.23     10116906.84      3713388.23     10116836.84
      3713488.23     10116686.84      3713598.23     10116666.84
      3713748.23     10116546.84      3714188.23     10116286.84

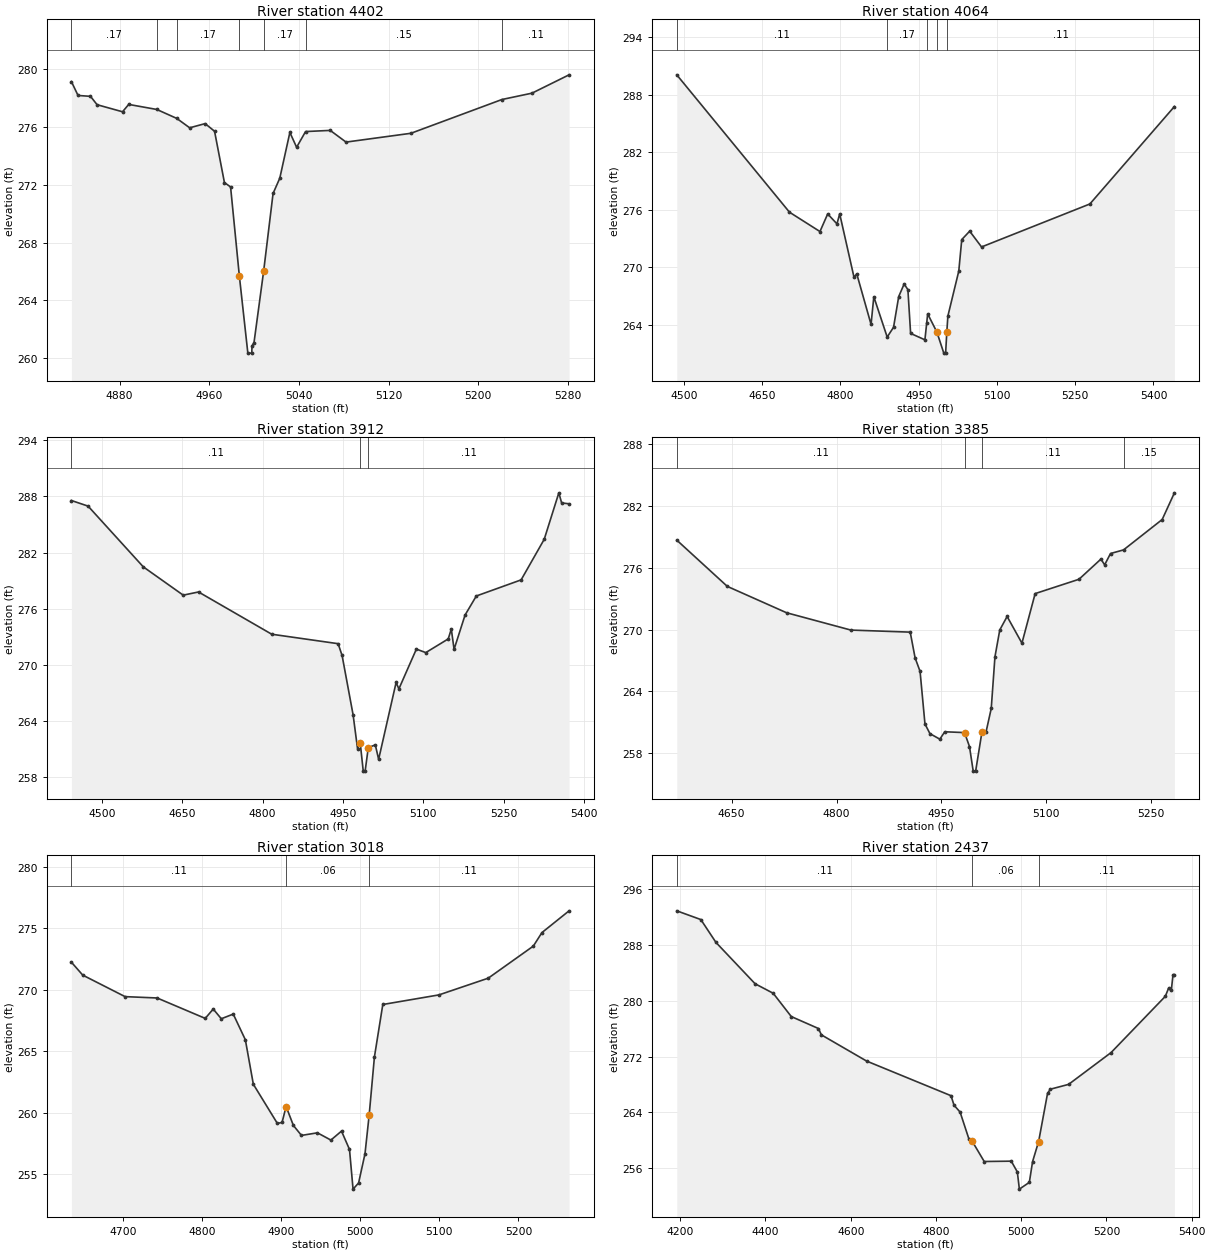
Type RM Length L Ch R = 1 ,4402    ,338,338,338
BEGIN DESCRIPTION:
CCLC 025 9.0
END DESCRIPTION:
XS GIS Cut Line= 3
      3711652.81      10118686.4      3711582.95     10118539.24
      3711426.18     10118305.92
#Sta/Elev= 30
  4837.1  279.15    4843  278.19  4854.1  278.13    4860  277.55  4882.7  277.06
  4888.2  277.57  4913.3  277.22  4931.1   276.6  4942.6  275.95  4956.4  276.24
  4964.8  275.71  4973.6  272.16  4979.1  271.85  4986.9   265.7  4994.5  260.34
    4998  260.34  4998.2  260.84    5000  261.07  5008.6266.0195    5017   271.4
    5023  272.46    5032  275.63    5038   274.6    5046  275.69    5068  275.77
  5082.1  274.96    5140  275.57  5221.2  277.91    5248  278.35  5281.1  279.62
#Mann= 7 ,-1 , 0
  4837.1     .17       0  4913.3     .11       0  4931.1     .17       0
  4986.9     .09       0  5008.6     .17       0    5046     .15       0
  5221.2     .11       0
Bank Sta=4986.9,5008.6
XS Rating Curve= 0 ,0
Exp/Cntr=0.3,0.1

Type RM Length L Ch R = 1 ,4064    ,152,152,152
BEGIN DESCRIPTION:
Mapping XS f6a2eb72
END DESCRIPTION:
XS GIS Cut Line= 2
      3712314.23     10118457.21      3711403.02     10118176.04
#Sta/Elev= 30
  4486.5  290.09  4702.5  275.74  4760.9  273.72  4775.7  275.56  4793.5  274.52
  4798.7  275.57  4826.2  268.93  4831.4   269.3  4858.8  264.02  4864.1  266.91
  4889.7   262.7  4901.9  263.72  4911.8  266.93  4922.2  268.24  4929.4  267.65
  4934.6  263.08    4962  262.41  4965.4  264.15  4967.3  265.12    4985  263.21
  4998.2  261.02  5001.7  261.02 5003.97263.2216    5006  264.89  5026.9  269.59
  5032.6  272.88  5047.8  273.76  5070.5  272.11  5278.1   276.6  5440.1  286.78
#Mann= 5 ,-1 , 0
  4486.5     .11       0  4889.7     .17       0  4965.4     .11       0
    4985     .06       0 5003.97     .11       0
Bank Sta=4985,5003.97
XS Rating Curve= 0 ,0
Exp/Cntr=0.3,0.1

Type RM Length L Ch R = 1 ,3912    ,527,527,527
BEGIN DESCRIPTION:
CCLC 025 8.0
END DESCRIPTION:
XS GIS Cut Line= 3
      3712408.01     10118295.76      3711867.89     10118161.31
       3711512.5     10118051.07
#Sta/Elev= 30
  4443.4  287.56  4474.5  286.96  4577.5  280.48    4652  277.46  4680.6   277.8
  4817.2  273.29  4941.1  272.28  4948.5  271.02  4969.1  264.67  4977.3  261.09
  4982.4  261.65    4988  258.68  4991.5  258.68  4997.4  261.19  5010.5  261.48
  5016.7  259.94  5049.3  268.14  5054.5  267.46  5087.1   271.7  5104.7  271.33
  5146.6  272.79  5152.3  273.84  5157.5  271.68    5178  275.34    5199  277.37
  5282.6  279.09  5325.7  283.42    5353  288.38  5358.2   287.3  5372.1  287.21
#Mann= 3 ,-1 , 0
  4443.4     .11       0  4982.4     .07       0  4997.4     .11       0
Bank Sta=4982.4,4997.4
XS Rating Curve= 0 ,0
Exp/Cntr=0.3,0.1

Type RM Length L Ch R = 1 ,3385    ,367,367,367
BEGIN DESCRIPTION:
CCLC 025 7.0
END DESCRIPTION:
XS GIS Cut Line= 3
      3712397.58     10118113.46       3712090.3     10117800.97
      3711831.32     10117712.92
#Sta/Elev= 30
  4571.5  278.69  4643.8   274.2  4728.6  271.64  4820.5  269.96  4905.4  269.76
  4912.4  267.26  4919.5  265.95  4926.5  260.85  4933.6  259.91  4947.8  259.37
  4954.8  260.09  4983.1  260.01  4990.2  258.65  4995.5  256.27    4999  256.27
  5007.9  260.02  5013.7  260.02  5021.3  262.35  5026.6  267.36  5033.5  269.97
    5044  271.28  5065.2  268.69  5084.1   273.5  5146.8  274.89  5178.2  276.85
  5183.5  276.29  5191.9  277.39  5210.5  277.74  5265.8  280.69  5283.3  283.28
#Mann= 4 ,-1 , 0
  4571.5     .11       0  4983.1     .06       0  5007.9     .11       0
  5210.5     .15       0
Bank Sta=4983.1,5007.9
XS Rating Curve= 0 ,0
Exp/Cntr=0.3,0.1

Type RM Length L Ch R = 1 ,3018    ,581,581,581
BEGIN DESCRIPTION:
CCLC 025 6.0
END DESCRIPTION:
XS GIS Cut Line= 3
       3712345.5     10117978.01      3712288.22     10117623.88
      3712199.66     10117368.64
#Sta/Elev= 30
  4635.1  272.25  4649.4   271.2  4702.9  269.45  4743.4  269.34  4804.2  267.68
  4814.3  268.44  4824.5  267.65  4839.6  268.03  4854.9  265.94    4865  262.32
  4895.4  259.13  4901.3  259.22  4906.4  260.51  4915.6  258.97  4925.8  258.16
    4946  258.37    4963  257.78  4976.4  258.51  4986.5  257.02    4991  253.79
    4998  254.29  5006.1  256.67  5011.4  259.84    5018  264.54  5028.6  268.81
  5099.5  269.59  5161.8  270.95  5218.8  273.56  5229.7  274.66    5264  276.43
#Mann= 3 , 0 , 0
  4635.1     .11       0  4906.4     .06       0  5011.4     .11       0
Bank Sta=4906.4,5011.4
XS Rating Curve= 0 ,0
Exp/Cntr=0.3,0.1

Type RM Length L Ch R = 1 ,2437    ,481,481,481
BEGIN DESCRIPTION:
CCLC 025 5.0
END DESCRIPTION:
XS GIS Cut Line= 3
      3713017.87     10118061.09      3712439.28     10117496.94
      3712167.85     10117261.07
#Sta/Elev= 30
  4191.9  292.84  4248.4  291.59  4283.9  288.32  4375.7  282.41  4418.2  281.05
  4460.6  277.72  4524.3  276.01  4531.3   275.1  4637.5  271.35  4835.4   266.4
  4842.5  265.04  4856.7  264.06  4877.8  260.14    4885   259.9  4913.3  256.99
  4976.8  257.04    4991   255.5  4995.8  253.04  5019.2  254.01  5026.8  256.98
    5041  259.85  5061.9  266.73  5068.5  267.33  5111.3  268.02    5211  272.57
  5338.2  280.61  5345.8  281.76  5352.5  281.58  5356.3   283.7  5359.6   283.7
#Mann= 3 , 0 , 0
  4191.9     .11       0    4885     .06       0    5041     .11       0
Bank Sta=4885,5041
XS Rating Curve= 0 ,0
Exp/Cntr=0.3,0.1

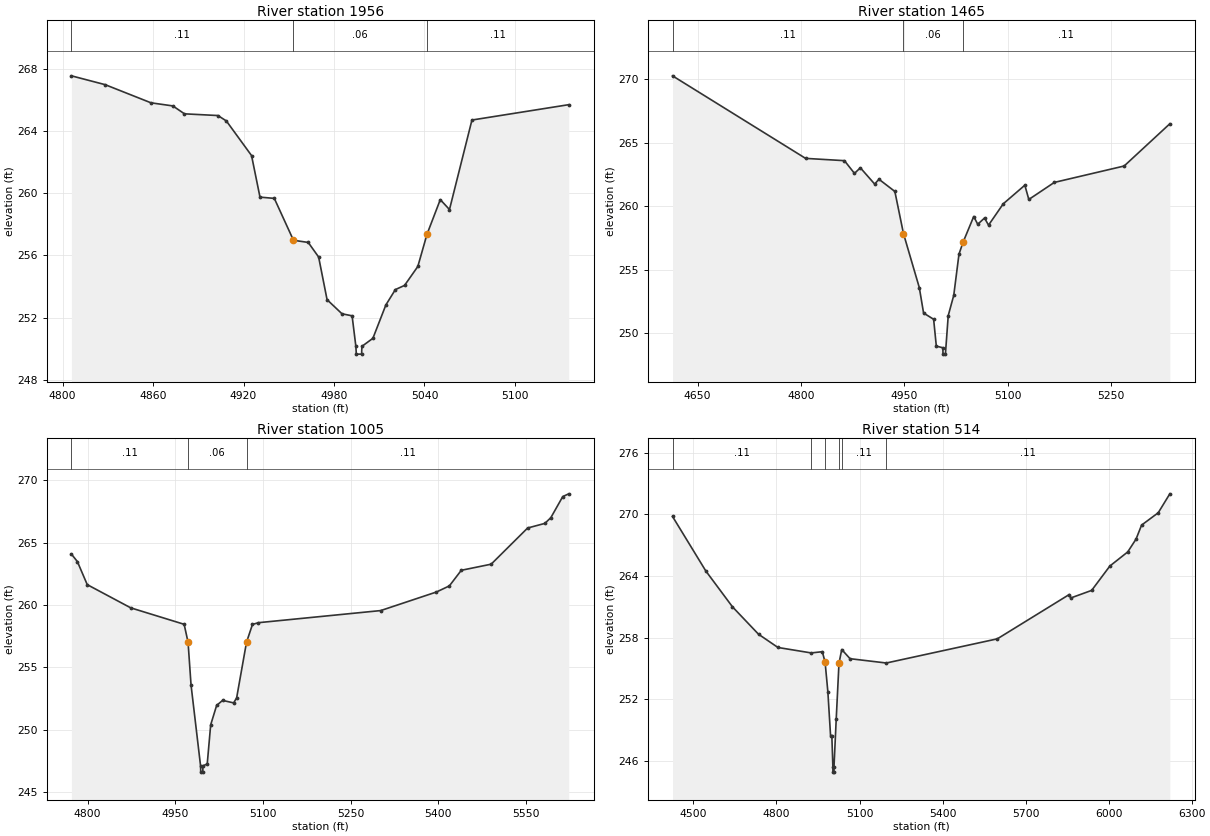
Type RM Length L Ch R = 1 ,1956    ,491,491,491
BEGIN DESCRIPTION:
CCLC 025 4.0
END DESCRIPTION:
XS GIS Cut Line= 3
      3712867.83     10117511.03      3712779.72     10117337.97
      3712667.89      10117261.1
#Sta/Elev= 30
  4805.8  267.58  4828.2  267.01  4858.6  265.84  4873.1  265.64  4880.8  265.13
    4903  265.02  4908.6  264.67  4925.3  262.44  4930.9  259.76  4940.4  259.68
  4953.1  256.98  4962.9  256.84  4969.8   255.9  4975.4  253.15  4985.3  252.24
    4992  252.11  4994.5  250.14  4994.8  249.64  4998.3  249.64  4998.5  250.14
  5005.8  250.66  5014.4  252.81  5020.7   253.8  5026.8  254.07  5035.6  255.29
  5041.7  257.37  5050.5   259.6  5056.6  258.96  5071.5  264.73  5135.7  265.72
#Mann= 3 , 0 , 0
  4805.8     .11       0  4953.1     .06       0  5041.7     .11       0
Bank Sta=4953.1,5041.7
XS Rating Curve= 0 ,0
Exp/Cntr=0.3,0.1

Type RM Length L Ch R = 1 ,1465    ,460,460,460
BEGIN DESCRIPTION:
CCLC 025 3.0
END DESCRIPTION:
XS GIS Cut Line= 3
      3713417.85     10117261.07      3713106.66     10117032.03
      3712817.86     10116861.08
#Sta/Elev= 30
  4613.6  270.25  4806.8  263.76  4863.2  263.58  4877.8  262.58  4886.3  263.02
  4907.1  261.74  4913.3  262.12  4936.4  261.16  4948.9  257.85  4971.9   253.6
  4978.1   251.6  4992.7  251.11  4996.6     249  5006.1  248.87  5006.3  248.37
  5009.8  248.37  5013.9   251.4  5021.9  252.99  5029.5  256.23  5035.3  257.15
  5050.9  259.19  5056.7  258.58  5066.6  259.07  5072.4  258.51  5093.8  260.19
  5125.1  261.65  5130.9  260.53  5167.9  261.87  5269.3  263.16  5335.6  266.48
#Mann= 3 , 0 , 0
  4613.6     .11       0  4948.9     .06       0  5035.3     .11       0
Bank Sta=4948.9,5035.3
XS Rating Curve= 0 ,0
Exp/Cntr=0.3,0.1

Type RM Length L Ch R = 1 ,1005    ,491,491,491
BEGIN DESCRIPTION:
CCLC 025 2.0
END DESCRIPTION:
XS GIS Cut Line= 3
      3713467.85     10117011.07      3713428.23     10116786.84
      3712817.85     10116661.07
#Sta/Elev= 30
  4772.3  264.09  4782.5  263.49  4799.4  261.64  4873.8  259.78  4965.2  258.46
  4971.9  257.02    4977  253.59  4993.3  247.11  4993.6  246.61  4997.1  246.61
  4997.3  247.11  5004.7  247.27  5010.6   250.4  5020.8  251.96    5031  252.36
  5049.9  252.16    5055  252.56  5071.9  257.02  5082.1  258.45  5092.3  258.59
  5301.4  259.56  5396.9  261.05    5419  261.54  5439.4  262.79  5490.5  263.28
  5552.9  266.18  5582.4  266.55  5592.6  267.01    5613   268.7  5623.2  268.92
#Mann= 3 , 0 , 0
  4772.3     .11       0  4971.9     .06       0  5071.9     .11       0
Bank Sta=4971.9,5071.9
XS Rating Curve= 0 ,0
Exp/Cntr=0.3,0.1

Type RM Length L Ch R = 1 ,514     ,0,0,0
BEGIN DESCRIPTION:
CCLC 025 1.0
END DESCRIPTION:
XS GIS Cut Line= 4
      3713817.85     10117111.08      3713778.23     10116536.84
      3713776.11     10116358.28      3712736.14     10116431.18
#Sta/Elev= 30
  4424.4  269.79  4544.7  264.49  4641.1     261  4735.1  258.34  4805.3  257.05
  4925.6  256.52  4965.7  256.64  4975.7  255.61  4985.7  252.73  4995.4  248.48
    5000  248.48  5003.8  245.43    5004  244.93  5007.5  244.93  5007.8  245.43
  5015.8  250.06  5025.8  255.51  5035.8  256.85  5065.8  255.96  5196.9  255.54
  5597.9  257.89  5857.8   262.2  5862.8  261.86  5938.7   262.6  6004.5  264.97
    6069  266.34  6099.1  267.59  6119.1  268.95  6179.3  270.15  6221.1  271.99
#Mann= 6 ,-1 , 0
  4424.4     .11       0  4925.6     .11       0  4975.7     .06       0
  5025.8     .11       0  5035.8     .11       0  5196.9     .11       0
Bank Sta=4975.7,5025.8
XS Rating Curve= 0 ,0
Exp/Cntr=0.3,0.1

Chan Stop Cuts=-1
Use User Specified Reach Order=0
Composite Channel Slope=5