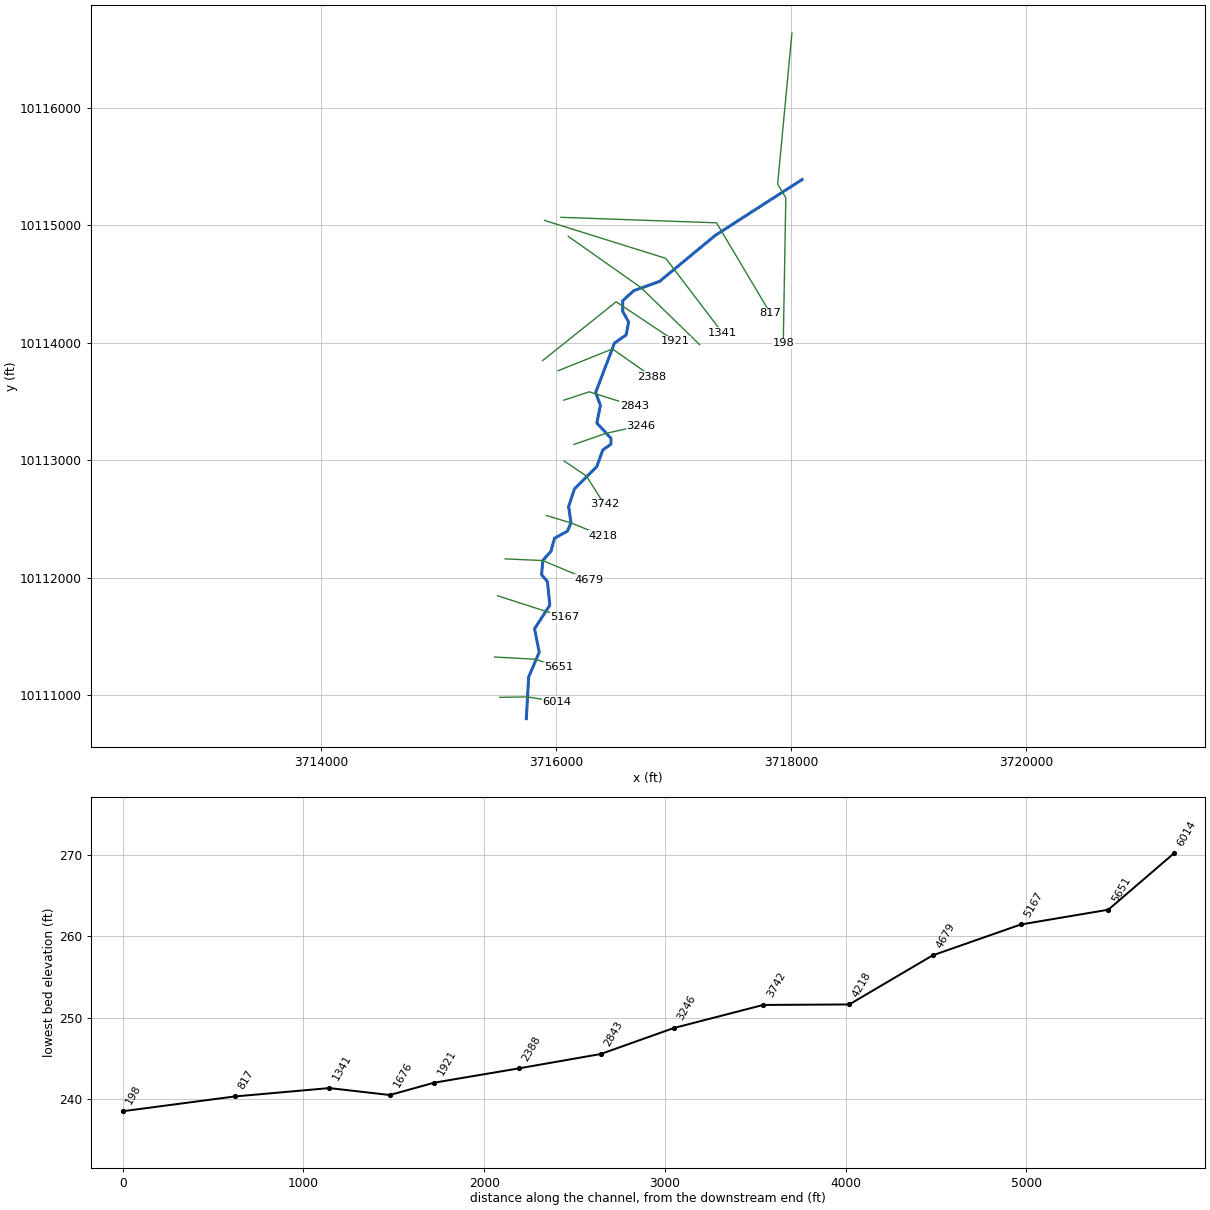
--- CCLC 026.prj (project) ---

Proj Title=CCLC 026 Base Level Engineering
Current Plan=p01
Default Exp/Contr=0.3,0.1
English Units
Geom File=g01
Flow File=f01
Flow File=f02
Plan File=p01
Y Axis Title=Elevation
X Axis Title(PF)=Main Channel Distance
X Axis Title(XS)=Station
BEGIN DESCRIPTION:
CCLC 026
END DESCRIPTION:
DSS Export Rating Curves= 0
DSS Export Rating Curve Sorted= 0
DSS Export Volume Flow Curves= 0
DXF OffsetX= 0
DXF OffsetY= 0
DXF ScaleX= 1
DXF ScaleY= 10

--- CCLC 026.p01 (plan) ---

Plan Title=Multiple Run
Short Identifier=Multiple
Geom File=g01
Flow File=f01
Subcritical Flow
K Sum by GR= 0
Std Step Tol= 0.01
Critical Tol= 0.01
Num of Std Step Trials= 20
Max Error Tol= 0.3
Flow Tol Ratio= 0.001
Split Flow NTrial= 30
Split Flow Tol= 0.02
Split Flow Ratio= 0.02
Log Output Level= 0
Friction Slope Method= 1
Unsteady Friction Slope Method= 2
Unsteady Bridges Friction Slope Method= 1
Parabolic Critical Depth
Global Vel Dist=  1 , 1 , 1
Global Log Level= 0
CheckData=True
Encroach Param= -1, 0, 0, 0
BEGIN DESCRIPTION:
Multiple Run
END DESCRIPTION:

--- CCLC 026.f01 (steady flow) ---

Flow Title=Multiple
Program Version=4.10
Number of Profiles= 7
Profile Names=10-year,25-year,50-year,1pct_min,100-year,1pct_plu,500-year
River Rch & RM=CCLC 026,Reach-1         ,6014
     707     968    1317     590    1781    5379    3366
River Rch & RM=CCLC 026,Reach-1         ,1676
    1468    2089    2920    1340    4046   12219    8034
River Rch & RM=CCLC 026,Reach-1         ,1341
    1468    2089    2920    1340    4046   12219    8034
River Rch & RM=CCLC 026,Reach-1         ,198
    2480    3578    5044    2328    7029   21227   14135
Boundary for River Rch & Prof#=CCLC 026,Reach-1         , 1
Up Type= 0
Dn Type= 3
Dn Slope=0.005
Boundary for River Rch & Prof#=CCLC 026,Reach-1         , 2
Up Type= 0
Dn Type= 3
Dn Slope=0.005
Boundary for River Rch & Prof#=CCLC 026,Reach-1         , 3
Up Type= 0
Dn Type= 3
Dn Slope=0.005
Boundary for River Rch & Prof#=CCLC 026,Reach-1         , 4
Up Type= 0
Dn Type= 3
Dn Slope=0.005
Boundary for River Rch & Prof#=CCLC 026,Reach-1         , 5
Up Type= 0
Dn Type= 3
Dn Slope=0.005
Boundary for River Rch & Prof#=CCLC 026,Reach-1         , 6
Up Type= 0
Dn Type= 3
Dn Slope=0.005
Boundary for River Rch & Prof#=CCLC 026,Reach-1         , 7
Up Type= 0
Dn Type= 3
Dn Slope=0.005
DSS Import GetInterval= 0
DSS Import GetPeak= 0
DSS Import FillOption= 0

--- CCLC 026.f02 (steady flow) ---

Flow Title=Orig_BLE_Flows
Program Version=4.10
Number of Profiles= 7
Profile Names=10-year,25-year,50-year,1pct_min,100-year,1pct_plu,500-year
River Rch & RM=CCLC 026,Reach-1         ,6014
     707     949    1145     454    1370    4137    1957
River Rch & RM=CCLC 026,Reach-1         ,1676
    1468    2048    2539    1030    3112    9397    4671
River Rch & RM=CCLC 026,Reach-1         ,1341
    1468    2048    2539    1030    3112    9397    4671
River Rch & RM=CCLC 026,Reach-1         ,198
    2480    3508    4386    1790    5407   16328    8218
Boundary for River Rch & Prof#=CCLC 026,Reach-1         , 1
Up Type= 0
Dn Type= 3
Dn Slope=0.0008
Boundary for River Rch & Prof#=CCLC 026,Reach-1         , 2
Up Type= 0
Dn Type= 3
Dn Slope=0.0008
Boundary for River Rch & Prof#=CCLC 026,Reach-1         , 3
Up Type= 0
Dn Type= 3
Dn Slope=0.0008
Boundary for River Rch & Prof#=CCLC 026,Reach-1         , 4
Up Type= 0
Dn Type= 3
Dn Slope=0.0008
Boundary for River Rch & Prof#=CCLC 026,Reach-1         , 5
Up Type= 0
Dn Type= 3
Dn Slope=0.0008
Boundary for River Rch & Prof#=CCLC 026,Reach-1         , 6
Up Type= 0
Dn Type= 3
Dn Slope=0.0008
Boundary for River Rch & Prof#=CCLC 026,Reach-1         , 7
Up Type= 0
Dn Type= 3
Dn Slope=0.0008
DSS Import GetInterval= 0
DSS Import GetPeak= 0
DSS Import FillOption= 0

--- CCLC 026.g01 (geometry) ---

Geom Title=Existing Conditions
Program Version=4.10

River Reach=CCLC 026        ,Reach-1
Reach XY= 30
      3715748.23     10110801.84      3715768.23     10111156.84
      3715858.23     10111366.84      3715818.23     10111566.84
      3715948.23     10111766.84      3715928.23     10111966.84
      3715878.23     10112026.84      3715888.23     10112146.84
      3715958.23     10112226.84      3715988.23     10112336.84
      3716098.23     10112396.84      3716128.23     10112466.84
      3716108.23     10112606.84      3716158.23     10112756.84
      3716348.23     10112946.84      3716398.23     10113086.84
      3716468.23     10113136.84      3716468.23     10113186.84
      3716348.23     10113316.84      3716378.23     10113466.84
      3716338.23     10113576.84      3716498.23     10113996.84
      3716598.23     10114066.84      3716618.23     10114176.84
      3716568.23     10114266.84      3716568.23     10114356.84
      3716660.83       10114442.      3716881.34     10114521.06
      3717354.42     10114912.01      3718093.44     10115387.63

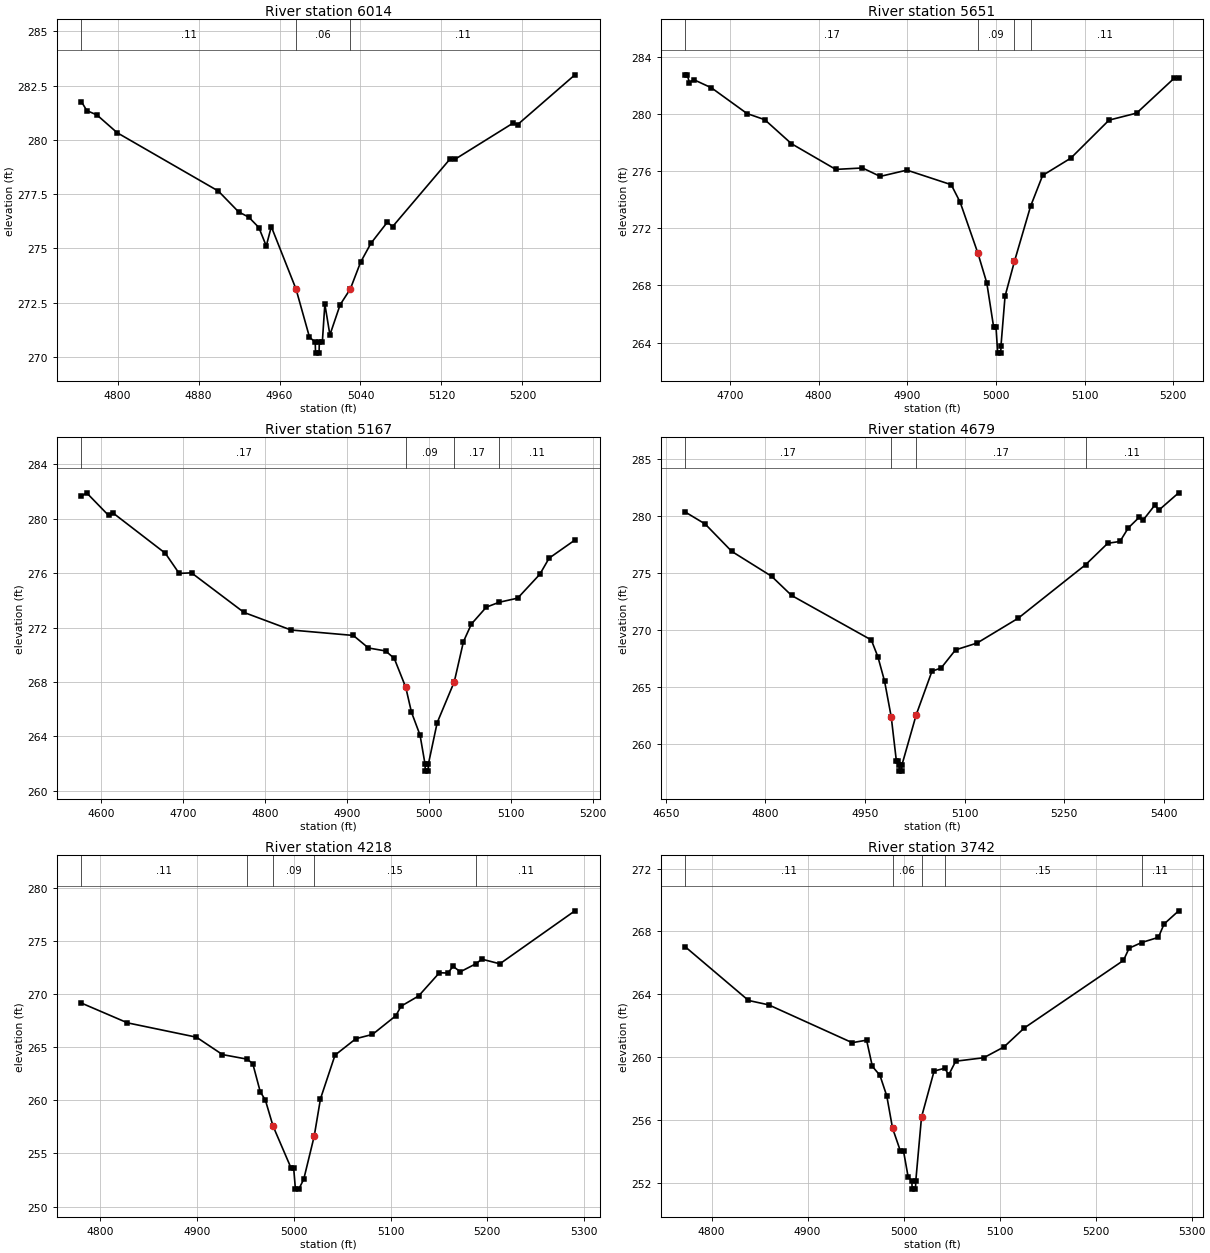
Type RM Length L Ch R = 1 ,6014    ,363,363,363
BEGIN DESCRIPTION:
CCLC 026 11.0
END DESCRIPTION:
XS GIS Cut Line= 3
      3715522.56     10110983.26      3715758.23     10110986.84
      3716006.93     10110946.81
#Sta/Elev= 30
  4764.3  281.76  4769.6  281.35  4779.6  281.15  4799.6  280.33  4899.6  277.64
  4919.6  276.68  4929.6  276.44  4939.6  275.96  4946.9  275.11  4951.9     276
 4976.29273.1269  4989.6  270.91  4995.3  270.67  4995.6  270.17  4999.1  270.17
  4999.3  270.67  5002.3  270.67  5004.8  272.43  5009.8  271.01  5019.9   272.4
    5030  273.13  5040.1  274.36  5050.3  275.23  5066.6  276.21  5071.7     276
  5128.5  279.12  5133.5  279.11  5190.3  280.76  5195.4  280.71  5251.9     283
#Mann= 3 , 0 , 0
  4764.3     .11       0 4976.29     .06       0    5030     .11       0
Bank Sta=4976.29,5030
XS Rating Curve= 0 ,0
Exp/Cntr=0.3,0.1

Type RM Length L Ch R = 1 ,5651    ,484,484,484
BEGIN DESCRIPTION:
CCLC 026 10.0
END DESCRIPTION:
XS GIS Cut Line= 3
      3715478.27     10111326.34      3715828.23     10111306.84
      3716022.56     10111238.48
#Sta/Elev= 30
  4649.5  282.74  4651.8  282.74  4654.2   282.2  4659.2   282.4  4679.1  281.83
  4719.2  280.03  4739.2   279.6  4769.3  277.92  4819.3  276.12  4849.4  276.22
  4869.4  275.63  4899.5  276.07  4949.5  275.05  4959.6  273.82  4979.6  270.25
  4989.6  268.18  4997.3   265.1    5000   265.1  5001.9  263.26  5005.4  263.26
  5005.6  263.76  5010.2  267.24  5020.8  269.68    5039  273.54  5052.6   275.7
  5084.4  276.91  5127.5  279.57  5158.6  280.06  5200.9   282.5    5206   282.5
#Mann= 4 ,-1 , 0
  4649.5     .17       0  4979.6     .09       0  5020.8     .17       0
    5039     .11       0
Bank Sta=4979.6,5020.8
XS Rating Curve= 0 ,0
Exp/Cntr=0.3,0.1

Type RM Length L Ch R = 1 ,5167    ,488,488,488
BEGIN DESCRIPTION:
CCLC 026 9.0
END DESCRIPTION:
XS GIS Cut Line= 3
      3715504.34     10111847.17      3715908.23     10111716.84
      3716078.97     10111665.82
#Sta/Elev= 30
  4575.6  281.65  4581.9   281.9  4608.7  280.24  4613.9  280.43    4678  277.46
  4694.9  275.98    4710  276.02  4774.1  273.11  4831.5  271.82  4907.6  271.42
    4926   270.5  4947.1  270.28  4957.6  269.73  4971.6  267.61  4978.6  265.78
  4989.1  264.09  4995.2  261.95  4995.4  261.45  4998.9  261.45  4999.2  261.95
    5010  265.01  5030.9  268.02  5042.1  270.97  5051.8  272.26    5070   273.5
  5085.8  273.86  5108.3  274.16  5135.3  275.91  5146.7   277.1  5178.2  278.43
#Mann= 4 ,-1 , 0
  4575.6     .17       0  4971.6     .09       0  5030.9     .17       0
  5085.8     .11       0
Bank Sta=4971.6,5030.9
XS Rating Curve= 0 ,0
Exp/Cntr=0.3,0.1

Type RM Length L Ch R = 1 ,4679    ,461,461,461
BEGIN DESCRIPTION:
CCLC 026 8.0
END DESCRIPTION:
XS GIS Cut Line= 3
      3715567.85     10112161.07      3715888.23     10112146.84
      3716277.78     10111983.27
#Sta/Elev= 30
  4679.3  280.36  4709.3  279.31  4749.4  276.91  4809.4  274.73  4839.5  273.05
  4959.6  269.15  4969.6  267.66  4979.6  265.53  4989.6  262.41  4997.3  258.57
    5000  258.57  5001.5  258.16  5001.8  257.66  5005.3  257.66  5005.5  258.16
  5027.3  262.61    5051  266.42  5064.7  266.69  5086.4  268.28  5118.9  268.88
  5180.7  271.05  5282.3  275.74  5315.7  277.62  5334.1  277.78  5346.7  278.97
  5363.3  279.91  5368.7  279.63    5387  280.99  5392.4  280.51  5422.5  282.04
#Mann= 4 ,-1 , 0
  4679.3     .17       0  4989.6     .09       0  5027.3     .17       0
  5282.3     .11       0
Bank Sta=4989.6,5027.3
XS Rating Curve= 0 ,0
Exp/Cntr=0.3,0.1

Type RM Length L Ch R = 1 ,4218    ,476,476,476
BEGIN DESCRIPTION:
CCLC 026 7.0
END DESCRIPTION:
XS GIS Cut Line= 3
      3715918.47     10112530.12      3716128.23     10112466.84
      3716397.57     10112358.27
#Sta/Elev= 30
  4780.9  269.16  4828.4   267.3  4899.6  265.95  4926.5  264.31    4952  263.88
  4957.8  263.45  4965.5  260.81  4970.8  260.02  4978.7  257.58  4997.2  253.65
    5000  253.65  5001.8  251.64  5005.3  251.64  5010.4  252.57  5021.2  256.62
  5027.7  260.15  5042.7  264.26  5064.3  265.81  5081.4  266.21  5105.5  267.97
  5110.9  268.87    5129  269.83  5150.5  272.02  5159.2  271.99  5164.6  272.62
  5172.1  272.11  5188.5  272.88  5194.2   273.3  5212.9  272.86  5290.4  277.85
#Mann= 5 ,-1 , 0
  4780.9     .11       0    4952     .15       0  4978.7     .09       0
  5021.2     .15       0  5188.5     .11       0
Bank Sta=4978.7,5021.2
XS Rating Curve= 0 ,0
Exp/Cntr=0.3,0.1

Type RM Length L Ch R = 1 ,3742    ,496,496,496
BEGIN DESCRIPTION:
CCLC 026 6.0
END DESCRIPTION:
XS GIS Cut Line= 3
      3716069.48     10112993.67      3716258.23     10112866.84
      3716412.31      10112625.3
#Sta/Elev= 30
  4772.6  267.02  4838.5   263.6  4859.5  263.32  4946.5  260.91  4961.5  261.07
  4967.5   259.4  4975.4  258.83  4982.5  257.52  4988.5  255.47  4996.8  253.99
    5000  253.99  5004.8  252.35  5008.7  252.08  5008.9  251.58  5012.4  251.58
  5012.7  252.08  5018.7  256.17  5031.8   259.1  5042.7  259.28  5047.1  258.87
  5054.3  259.73  5083.5  259.95  5104.6  260.64  5125.8  261.85    5229  266.15
  5234.9  266.93    5248  267.29  5265.4  267.62  5271.3  268.47  5286.5  269.31
#Mann= 5 ,-1 , 0
  4772.6     .11       0  4988.5     .06       0  5018.7     .11       0
  5042.7     .15       0    5248     .11       0
Bank Sta=4988.5,5018.7
XS Rating Curve= 0 ,0
Exp/Cntr=0.3,0.1

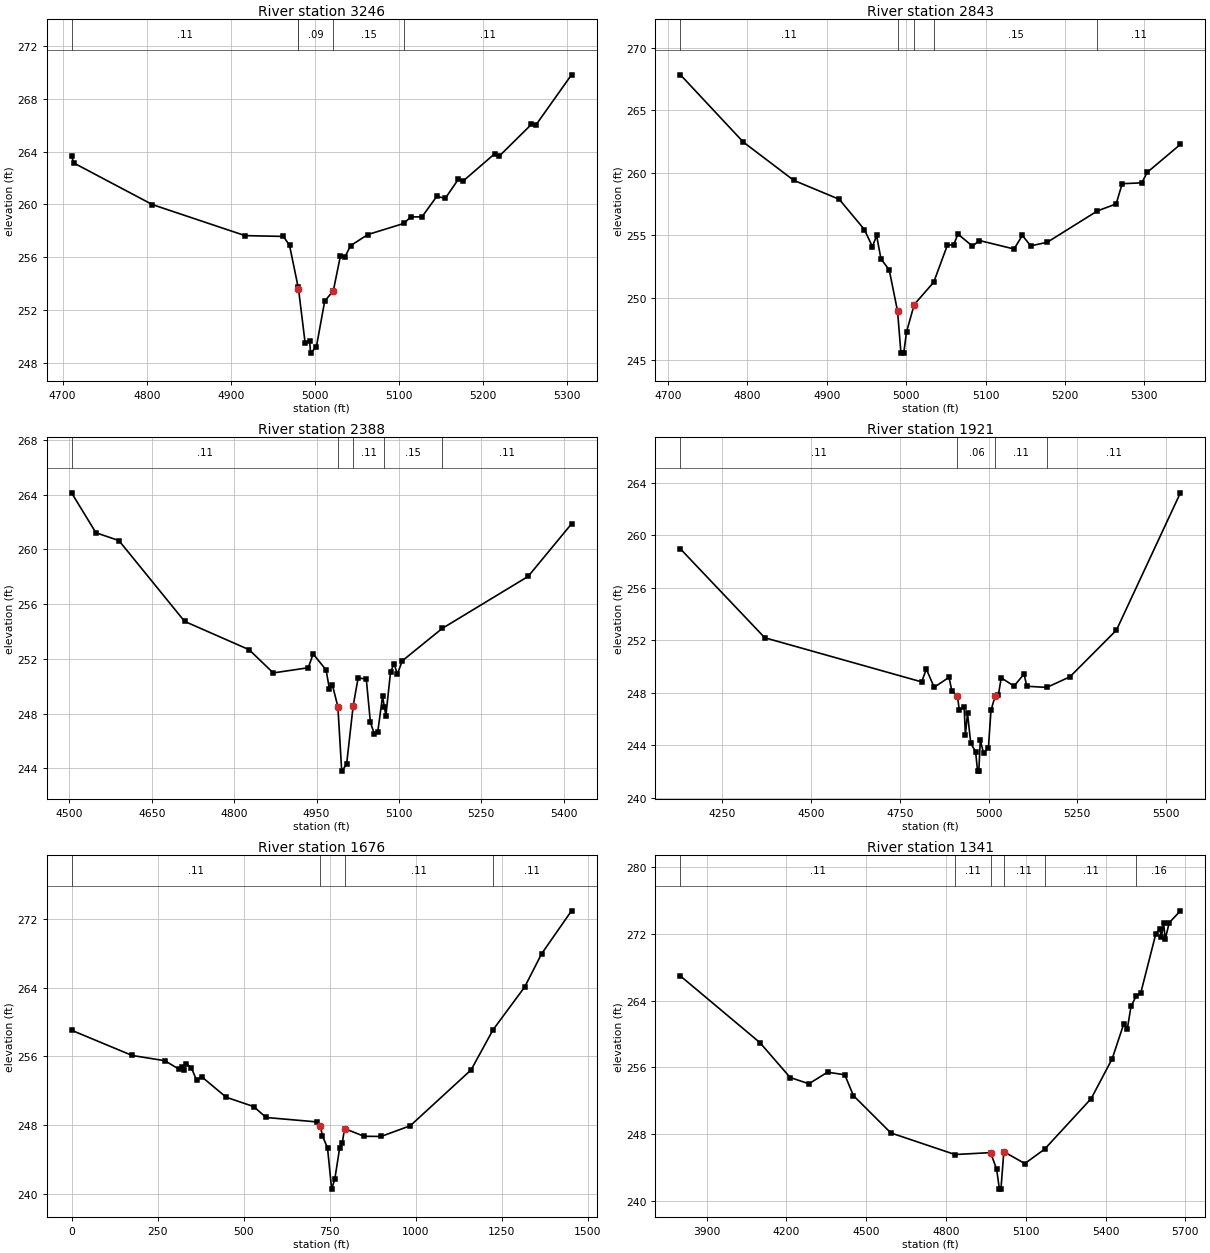
Type RM Length L Ch R = 1 ,3246    ,403,403,403
BEGIN DESCRIPTION:
CCLC 026 5.0
END DESCRIPTION:
XS GIS Cut Line= 3
      3716152.84     10113134.31      3716423.63     10113228.05
      3716724.31     10113295.44
#Sta/Elev= 30
  4710.6  263.67  4713.3  263.14  4806.8  259.99    4917  257.64  4962.6  257.58
  4969.9   256.9    4980  253.78  4980.5  253.63  4988.4  249.54  4993.7  249.67
    4995  248.74  5001.9  249.24  5011.7  252.67    5022  253.47  5030.5  256.13
  5035.6     256  5042.5  256.88    5063  257.72  5105.7  258.56  5114.2  259.06
  5127.4  259.06    5145  260.61  5155.2  260.47  5170.8  261.92  5175.9  261.75
  5214.1  263.85  5219.3  263.66  5257.5  266.06  5262.6  265.99  5305.3  269.82
#Mann= 5 ,-1 , 0
  4710.6     .11       0    4980     .15       0  4980.5     .09       0
    5022     .15       0  5105.7     .11       0
Bank Sta=4980.5,5022
XS Rating Curve= 0 ,0
Exp/Cntr=0.3,0.1

Type RM Length L Ch R = 1 ,2843    ,455,455,455
BEGIN DESCRIPTION:
CCLC 026 4.0
END DESCRIPTION:
XS GIS Cut Line= 3
      3716067.86     10113511.07      3716283.01     10113582.22
      3716667.88     10113461.06
#Sta/Elev= 30
  4715.5  267.85  4794.8  262.46  4858.3   259.4  4915.6  257.88  4947.3  255.46
  4957.5  254.07  4962.7  254.99  4968.2  253.11  4978.6  252.23  4989.1  248.93
  4993.4  245.56  4996.9  245.56  5000.4  247.25  5010.1  249.45  5034.7  251.24
    5052  254.22  5059.9  254.22  5065.1   255.1  5083.5  254.13  5092.3  254.58
  5135.9   253.9  5146.4  254.99  5156.9  254.15  5177.8  254.44    5241  256.95
  5264.6  257.51  5272.2  259.13    5297   259.2  5303.6  260.03  5345.6  262.28
#Mann= 5 ,-1 , 0
  4715.5     .11       0  4989.1     .06       0  5010.1     .11       0
  5034.7     .15       0    5241     .11       0
Bank Sta=4989.1,5010.1
XS Rating Curve= 0 ,0
Exp/Cntr=0.3,0.1

Type RM Length L Ch R = 1 ,2388    ,467,467,467
BEGIN DESCRIPTION:
CCLC 026 3.0
END DESCRIPTION:
XS GIS Cut Line= 3
      3716017.88     10113761.08      3716480.93      10113946.8
      3716817.85     10113711.08
#Sta/Elev= 30
    4504  264.14  4548.4  261.22  4590.2  260.65  4709.8  254.74  4827.2  252.67
  4871.2  250.97  4934.9  251.35  4943.8  252.36  4967.3  251.19  4973.4  249.81
  4978.8   250.1  4988.8   248.5  4995.8  243.79  5004.7  244.29 5016.65248.5642
  5025.6  250.59  5040.5  250.54    5048  247.36  5055.3   246.5  5061.4  246.66
  5070.1  249.25  5073.4  248.49  5076.2  247.84  5084.6  251.01    5091  251.66
  5097.1  250.87  5105.9  251.85  5178.6  254.22  5335.2  258.03  5414.1  261.87
#Mann= 5 ,-1 , 0
    4504     .11       0  4988.8     .06       0 5016.65     .11       0
  5073.4     .15       0  5178.6     .11       0
Bank Sta=4988.8,5016.65
XS Rating Curve= 0 ,0
Exp/Cntr=0.3,0.1

Type RM Length L Ch R = 1 ,1921    ,245,245,245
BEGIN DESCRIPTION:
CCLC 026 2.0
END DESCRIPTION:
XS GIS Cut Line= 3
      3715887.21     10113847.87      3716512.18     10114347.84
      3717017.85     10114011.08
#Sta/Elev= 30
  4132.3  258.95  4369.8  252.19  4811.6  248.83  4824.7  249.81  4846.8  248.42
  4888.7  249.18  4896.5  248.15 4912.47247.7412  4917.3  246.73  4931.2  246.94
  4934.7   244.8  4940.7  246.45  4949.7  244.17  4963.5  243.51    4969  242.04
  4972.5  242.04  4976.7  244.38  4985.7  243.43  4999.5  243.81  5006.8  246.67
 5018.74247.7713  5027.8  247.87  5035.6  249.14  5071.6  248.51  5099.9  249.43
  5107.7   248.5  5163.9  248.41  5229.2  249.22    5360  252.77  5540.2  263.22
#Mann= 4 ,-1 , 0
  4132.3     .11       0 4912.47     .06       0 5018.74     .11       0
  5163.9     .11       0
Bank Sta=4912.47,5018.74
XS Rating Curve= 0 ,0
Exp/Cntr=0.3,0.1

Type RM Length L Ch R = 1 ,1676    ,335,335,335
BEGIN DESCRIPTION:
CCLC 026 1.5
END DESCRIPTION:
XS GIS Cut Line= 3
      3716104.86     10114904.69      3716723.06     10114469.23
      3717222.67     10113983.23
#Sta/Elev= 30
       0  259.05   176.1  256.11     271   255.5   312.9   254.5   321.6  254.82
   327.7  254.44   333.9  255.15   348.6  254.65   363.4  253.22   378.2  253.63
   449.6  251.24   529.6  250.15   565.4  248.88   714.4  248.36   723.1  247.89
   729.2  246.74     744  245.34     756  240.53   765.3  241.73   779.4  245.35
   786.6  245.85   793.6  247.59   850.1  246.69   899.8  246.67   984.6  247.92
  1161.4  254.43  1224.9  259.09    1317  264.09  1366.4  267.97  1453.2  272.97
#Mann= 4 ,-1 , 0
       0     .11       0   723.1     .06       0   793.6     .11       0
  1224.9     .11       0
Bank Sta=723.1,793.6
XS Rating Curve= 0 ,0
Exp/Cntr=0.3,0.1

Type RM Length L Ch R = 1 ,1341    ,524,524,524
BEGIN DESCRIPTION:
Mapping XS dcc9ca66
END DESCRIPTION:
XS GIS Cut Line= 3
      3715902.83     10115040.54      3716934.05     10114717.63
      3717418.44      10114082.2
#Sta/Elev= 30
  3801.8  266.95  4100.5  258.96  4214.4  254.77  4284.6  254.02  4354.7  255.41
  4419.6   255.1  4452.1   252.6    4593  248.12    4834  245.53  4967.6  245.76
  4990.4  243.78  5000.9  241.38  5006.7  241.38  5017.5  245.87  5096.5  244.45
  5170.7  246.17  5345.9  252.24  5424.9  257.02  5468.5  261.22  5481.6  260.57
  5495.6   263.3  5515.8  264.59  5531.9  264.86  5589.1  272.03  5603.6  272.57
  5609.9  271.59  5618.2  273.25  5624.5  271.36    5639  273.33  5681.4  274.77
#Mann= 6 ,-1 , 0
  3801.8     .11       0    4834     .11       0  4967.6     .06       0
  5017.5     .11       0  5170.7     .11       0  5515.8     .16       0
Bank Sta=4967.6,5017.5
XS Rating Curve= 0 ,0
Exp/Cntr=0.3,0.1

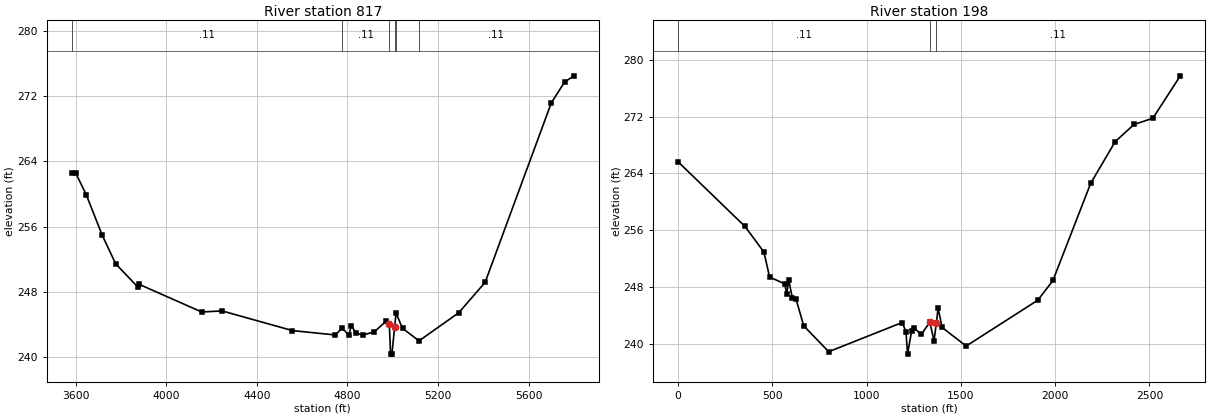
Type RM Length L Ch R = 1 ,817     ,619,619,619
BEGIN DESCRIPTION:
CCLC 026 1.0
END DESCRIPTION:
XS GIS Cut Line= 3
      3716043.43     10115066.59      3717366.34     10115019.72
      3717823.79     10114250.38
#Sta/Elev= 30
  3581.3  262.56  3598.4  262.61  3645.8  259.91  3715.8  254.97  3775.8  251.43
  3874.7  248.55  3879.7  248.91  4155.9  245.52  4246.1  245.65  4556.3  243.24
  4746.4   242.7  4776.5  243.56  4806.5  242.65  4816.5  243.86  4836.5     243
  4866.5  242.67  4919.3   243.1    4972  244.43  4984.9  243.99  4990.4  240.35
  4996.3  240.35  5008.2  243.66  5014.8  245.37  5043.1  243.52  5116.1  241.98
  5291.4  245.42  5408.2  249.16  5700.4  271.16  5758.9  273.72  5800.1  274.49
#Mann= 6 ,-1 , 0
  3581.3     .11       0  4776.5     .11       0  4984.9     .06       0
  5008.2     .11       0  5014.8     .11       0  5116.1     .11       0
Bank Sta=4984.9,5008.2
XS Rating Curve= 0 ,0
Exp/Cntr=0.3,0.1

Type RM Length L Ch R = 1 ,198     ,0,0,0
XS GIS Cut Line= 4
      3718007.77     10116634.11      3717886.24     10115349.39
      3717955.69      10115232.2      3717933.99     10113995.22
#Sta/Elev= 30
       0  265.62   354.6  256.52   455.1  252.91   485.2  249.39   565.6  248.44
   575.6  247.03   586.9  248.94   605.7  246.46   625.8  246.26     666  242.53
   798.6  238.88  1188.3  242.99  1208.4  241.71  1216.9  238.54  1238.5  241.83
  1248.6  242.25  1290.5  241.33    1335  243.05  1357.3  240.42  1369.9  242.98
  1378.8  245.03  1400.2  242.29  1527.8  239.68  1907.9  246.14  1987.9  248.91
  2187.9  262.58  2317.9  268.46    2418  270.88    2518  271.76  2663.4  277.73
#Mann= 3 , 0 , 0
       0     .11       0    1335     .06       0  1369.9     .11       0
Bank Sta=1335,1369.9
XS Rating Curve= 0 ,0
Exp/Cntr=0.3,0.1

Chan Stop Cuts=-1
Use User Specified Reach Order=0
Composite Channel Slope=5