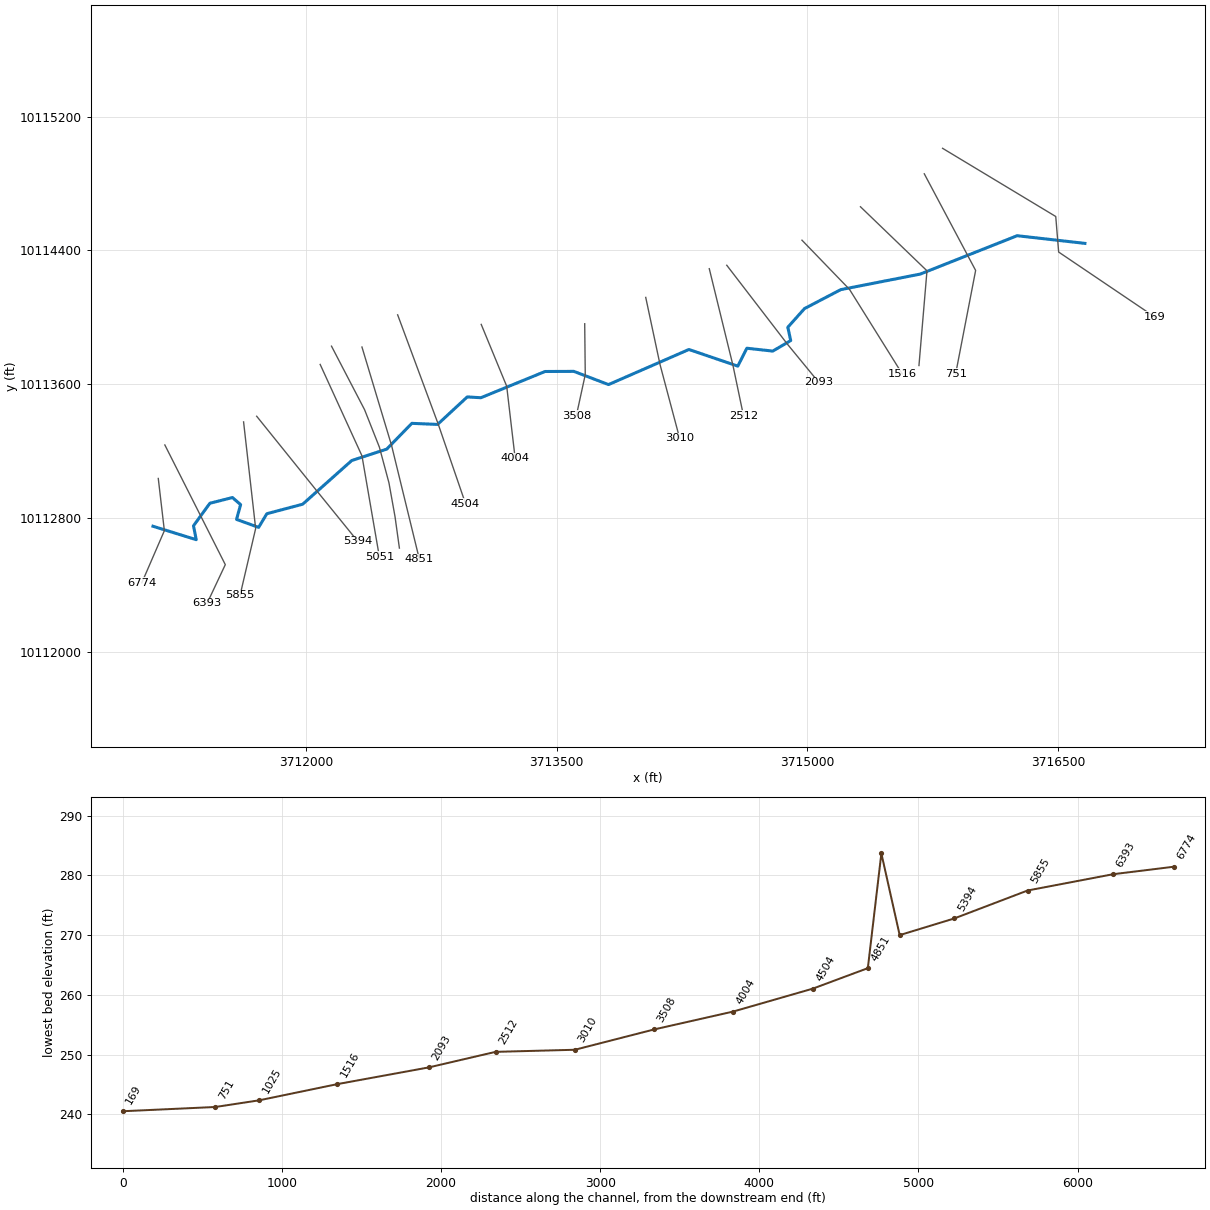
--- CCLC 027.prj (project) ---

Proj Title=CCLC 027 Base Level Engineering
Current Plan=p01
Default Exp/Contr=0.3,0.1
English Units
Geom File=g01
Flow File=f01
Flow File=f02
Plan File=p01
Y Axis Title=Elevation
X Axis Title(PF)=Main Channel Distance
X Axis Title(XS)=Station
BEGIN DESCRIPTION:
CCLC 027
END DESCRIPTION:
DSS Export Rating Curves= 0
DSS Export Rating Curve Sorted= 0
DSS Export Volume Flow Curves= 0
DXF OffsetX= 0
DXF OffsetY= 0
DXF ScaleX= 1
DXF ScaleY= 10

--- CCLC 027.p01 (plan) ---

Plan Title=Multiple Run
Short Identifier=Multiple
Geom File=g01
Flow File=f01
Subcritical Flow
K Sum by GR= 0
Std Step Tol= 0.01
Critical Tol= 0.01
Num of Std Step Trials= 20
Max Error Tol= 0.3
Flow Tol Ratio= 0.001
Split Flow NTrial= 30
Split Flow Tol= 0.02
Split Flow Ratio= 0.02
Log Output Level= 0
Friction Slope Method= 1
Unsteady Friction Slope Method= 2
Unsteady Bridges Friction Slope Method= 1
Parabolic Critical Depth
Global Vel Dist=  1 , 1 , 1
Global Log Level= 0
CheckData=True
Encroach Param= -1, 0, 0, 0
BEGIN DESCRIPTION:
Multiple Run
END DESCRIPTION:

--- CCLC 027.f01 (steady flow) ---

Flow Title=Multiple
Program Version=4.10
Number of Profiles= 7
Profile Names=10-year,25-year,50-year,1pct_min,100-year,1pct_plu,500-year
River Rch & RM=CCLC 027,Reach-1         ,6774
     805    1111    1519     684    2066    6239    3949
River Rch & RM=CCLC 027,Reach-1         ,4851
    1029    1440    1991     904    2730    8244    5315
River Rch & RM=CCLC 027,Reach-1         ,169
    1468    2089    2920    1340    4046   12219    8034
Boundary for River Rch & Prof#=CCLC 027,Reach-1         , 1
Up Type= 0
Dn Type= 3
Dn Slope=0.005
Boundary for River Rch & Prof#=CCLC 027,Reach-1         , 2
Up Type= 0
Dn Type= 3
Dn Slope=0.005
Boundary for River Rch & Prof#=CCLC 027,Reach-1         , 3
Up Type= 0
Dn Type= 3
Dn Slope=0.005
Boundary for River Rch & Prof#=CCLC 027,Reach-1         , 4
Up Type= 0
Dn Type= 3
Dn Slope=0.005
Boundary for River Rch & Prof#=CCLC 027,Reach-1         , 5
Up Type= 0
Dn Type= 3
Dn Slope=0.005
Boundary for River Rch & Prof#=CCLC 027,Reach-1         , 6
Up Type= 0
Dn Type= 3
Dn Slope=0.005
Boundary for River Rch & Prof#=CCLC 027,Reach-1         , 7
Up Type= 0
Dn Type= 3
Dn Slope=0.005
DSS Import GetInterval= 0
DSS Import GetPeak= 0
DSS Import FillOption= 0

--- CCLC 027.f02 (steady flow) ---

Flow Title=Orig_BLE_Flows
Program Version=4.10
Number of Profiles= 7
Profile Names=10-year,25-year,50-year,1pct_min,100-year,1pct_plu,500-year
River Rch & RM=CCLC 027,Reach-1         ,6774
     805    1089    1321     526    1589    4800    2296
River Rch & RM=CCLC 027,Reach-1         ,4851
    1029    1412    1731     695    2100    6343    3090
River Rch & RM=CCLC 027,Reach-1         ,169
    1468    2048    2539    1030    3112    9397    4671
Boundary for River Rch & Prof#=CCLC 027,Reach-1         , 1
Up Type= 0
Dn Type= 3
Dn Slope=0.005
Boundary for River Rch & Prof#=CCLC 027,Reach-1         , 2
Up Type= 0
Dn Type= 3
Dn Slope=0.005
Boundary for River Rch & Prof#=CCLC 027,Reach-1         , 3
Up Type= 0
Dn Type= 3
Dn Slope=0.005
Boundary for River Rch & Prof#=CCLC 027,Reach-1         , 4
Up Type= 0
Dn Type= 3
Dn Slope=0.005
Boundary for River Rch & Prof#=CCLC 027,Reach-1         , 5
Up Type= 0
Dn Type= 3
Dn Slope=0.005
Boundary for River Rch & Prof#=CCLC 027,Reach-1         , 6
Up Type= 0
Dn Type= 3
Dn Slope=0.005
Boundary for River Rch & Prof#=CCLC 027,Reach-1         , 7
Up Type= 0
Dn Type= 3
Dn Slope=0.005
DSS Import GetInterval= 0
DSS Import GetPeak= 0
DSS Import FillOption= 0

--- CCLC 027.g01 (geometry) ---

Geom Title=Existing Conditions
Program Version=4.10

River Reach=CCLC 027        ,Reach-1
Reach XY= 30
      3711084.54     10112749.47      3711343.41     10112669.09
      3711327.06      10112752.2      3711425.16     10112887.08
      3711560.04     10112921.14      3711609.09     10112878.91
      3711584.57     10112790.35      3711716.73     10112742.66
      3711765.78     10112824.41      3711980.18     10112881.26
      3712274.16     10113142.82       3712483.3     10113210.99
      3712633.46     10113365.15      3712787.43     10113358.77
       3712965.1     10113523.28      3713046.59      10113518.4
       3713430.7     10113675.46      3713602.95     10113676.12
      3713810.34     10113597.06       3714291.3     10113807.05
      3714583.95     10113707.55      3714638.07     10113814.66
      3714793.17     10113797.48      3714900.49     10113860.48
      3714883.12     10113940.05      3714983.02     10114051.87
      3715199.86     10114165.18      3715675.65      10114258.3
      3716255.37     10114487.87      3716660.83       10114442.

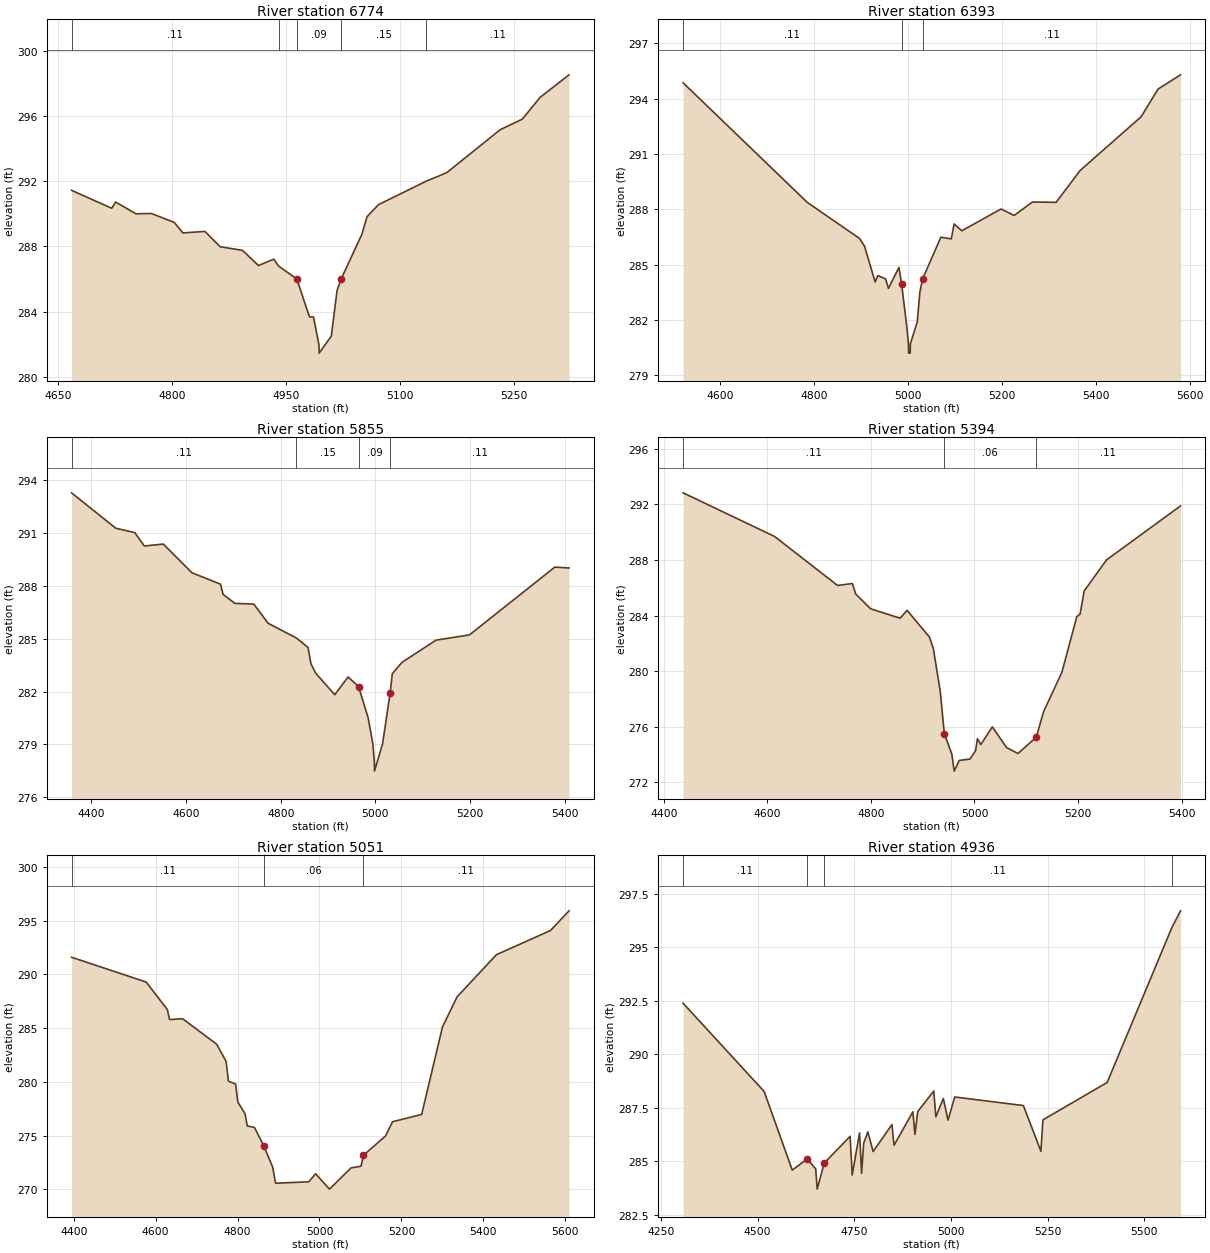
Type RM Length L Ch R = 1 ,6774    ,381,381,381
BEGIN DESCRIPTION:
CCLC 027 14.0
END DESCRIPTION:
XS GIS Cut Line= 3
      3711116.34     10113035.36       3711152.8     10112722.84
      3711017.84     10112411.03
#Sta/Elev= 30
    4668  291.44  4720.9  290.34  4725.9  290.72  4752.9     290    4773  290.02
  4803.2  289.47  4814.4  288.83  4843.5  288.92  4863.6  287.98  4892.8  287.76
  4913.9  286.83  4934.1  287.22  4940.3   286.8  4964.3  286.01    4981  283.68
  4986.3  283.68  4993.5  281.96  4993.7  281.46  5009.7   282.5  5017.3   285.3
  5022.7286.0098  5049.9  288.74  5056.7  289.82  5071.7  290.56  5134.1  291.99
  5161.5  292.52    5232  295.16  5260.9   295.8  5284.4  297.14  5322.4  298.52
#Mann= 5 ,-1 , 0
    4668     .11       0  4940.3     .15       0  4964.3     .09       0
  5022.7     .15       0  5134.1     .11       0
Bank Sta=4964.3,5022.7
XS Rating Curve= 0 ,0
Exp/Cntr=0.3,0.1

Type RM Length L Ch R = 1 ,6393    ,538,538,538
BEGIN DESCRIPTION:
CCLC 027 13.0
END DESCRIPTION:
XS GIS Cut Line= 3
      3711155.66      10113235.8      3711517.38     10112519.72
      3711408.29     10112287.86
#Sta/Elev= 30
  4521.2  294.86  4785.4  288.38  4896.9  286.42  4907.4     286  4929.8  284.07
  4935.9  284.41  4952.2  284.23  4958.2  283.72  4980.5  284.85  4986.1  283.98
    4997  281.69  5000.8  280.71    5001  280.21  5004.5  280.21  5004.8  280.71
  5019.4  281.89  5025.1  283.52  5030.7  284.22  5069.7  286.49  5091.9   286.4
  5097.9  287.21  5114.2  286.84  5197.8  288.02  5225.7  287.67  5264.7   288.4
  5314.9  288.38  5366.2  290.11  5495.9  293.02  5531.9  294.52  5579.7  295.29
#Mann= 3 , 0 , 0
  4521.2     .11       0  4986.1     .06       0  5030.7     .11       0
Bank Sta=4986.1,5030.7
XS Rating Curve= 0 ,0
Exp/Cntr=0.3,0.1

Type RM Length L Ch R = 1 ,5855    ,461,461,461
BEGIN DESCRIPTION:
CCLC 027 12.0
END DESCRIPTION:
XS GIS Cut Line= 3
      3711626.76     10113373.87      3711699.02     10112735.85
      3711605.91     10112337.38
#Sta/Elev= 30
  4357.9  293.29  4451.3  291.28  4491.5  291.03  4511.7  290.27  4551.9  290.38
  4612.3  288.75  4672.7   288.1  4678.2  287.52  4702.9  287.01  4743.1  286.97
  4773.3  285.88  4833.2  285.04  4857.6  284.51  4863.9  283.57    4874  283.04
  4914.2  281.82  4942.3  282.83  4964.5  282.28  4984.7  280.51  4994.7  279.03
  4997.9  277.98  4998.1  277.48  5015.2  279.03  5031.3  281.94  5035.7  283.01
  5056.2  283.66  5128.1  284.92  5198.9  285.22  5379.2  289.07  5409.2  289.02
#Mann= 4 ,-1 , 0
  4357.9     .11       0  4833.2     .15       0  4964.5     .09       0
  5031.3     .11       0
Bank Sta=4964.5,5031.3
XS Rating Curve= 0 ,0
Exp/Cntr=0.3,0.1

Type RM Length L Ch R = 1 ,5394    ,343,343,343
BEGIN DESCRIPTION:
CCLC 027 11.0
END DESCRIPTION:
XS GIS Cut Line= 3
      3711705.17     10113407.63      3712058.23     10112969.34
      3712309.06     10112660.33
#Sta/Elev= 30
  4437.2  292.84  4613.9   289.7  4735.5  286.17  4764.2  286.31  4770.7  285.55
  4799.4  284.49  4856.5  283.81  4869.8  284.38    4913  282.46  4920.7   281.6
  4933.8  278.58  4941.8  275.49  4956.2  274.04  4960.9   272.8  4970.6  273.57
  4991.4  273.67  5002.1  274.27  5005.8  275.14  5012.2  274.71  5034.5  275.99
  5062.2  274.49  5084.1  274.07  5119.3  275.24  5133.6  277.09  5168.8  279.91
  5197.6  283.92    5204  284.11  5211.9  285.77  5255.1  288.01    5398   291.9
#Mann= 3 , 0 , 0
  4437.2     .11       0  4941.8     .06       0  5119.3     .11       0
Bank Sta=4941.8,5119.3
XS Rating Curve= 0 ,0
Exp/Cntr=0.3,0.1

Type RM Length L Ch R = 1 ,5051    ,115,115,115
BEGIN DESCRIPTION:
Mapping XS 3ae9dd6c
END DESCRIPTION:
XS GIS Cut Line= 3
      3712085.09     10113717.63      3712335.09     10113170.76
      3712439.26     10112566.58
#Sta/Elev= 30
  4394.7  291.59    4577  289.28  4628.6  286.72  4634.1  285.79  4665.8  285.87
  4749.2  283.49  4772.2  281.88  4777.7  280.05  4795.2  279.79  4800.7  278.11
  4818.2  277.04  4823.7  275.89  4841.3  275.75  4863.7  274.06  4885.7  272.06
  4892.8  270.56  4973.7  270.69  4990.4  271.44  5024.4  270.01  5076.9  271.98
  5101.4  272.15  5107.3  273.16  5161.3  274.96  5178.3  276.28  5249.4  276.96
  5300.1  285.09  5335.8   287.9    5432  291.83    5564  294.08  5609.1  295.91
#Mann= 3 , 0 , 0
  4394.7     .11       0  4863.7     .06       0  5107.3     .11       0
Bank Sta=4863.7,5107.3
XS Rating Curve= 0 ,0
Exp/Cntr=0.3,0.1

Type RM Length L Ch R = 1 ,4936    ,85,85,85
BEGIN DESCRIPTION:
Mapping XS 456a1b8c
END DESCRIPTION:
XS GIS Cut Line= 6
      3712152.81     10113826.99      3712350.72      10113446.8
      3712439.26     10113222.84      3712496.55      10113009.3
      3712533.01     10112806.18      3712559.05     10112618.68
#Sta/Elev= 30
  4307.2  292.39  4516.8  288.26  4589.5  284.58    4628   285.1  4650.1  284.64
    4654  283.69  4672.2  284.91  4739.1  286.16  4744.5  284.35  4763.5  286.32
  4768.8  284.43  4774.2  285.84    4785  286.37  4798.6  285.45  4847.3  286.71
  4852.6  285.74  4901.4  287.31  4906.7  286.25    4914  287.32  4955.4  288.28
  4960.8  287.07  4980.1  287.93  4992.3  286.92  5009.5     288  5187.1   287.6
  5232.4  285.46  5237.5  286.93  5403.7  288.68  5571.3  295.94  5593.4  296.71
#Mann= 4 ,-1 , 0
  4307.2     .11       0    4628     .06       0  4672.2     .11       0
  5571.3     .17       0
Bank Sta=4628,4672.2
XS Rating Curve= 0 ,0
Exp/Cntr=0.3,0.1

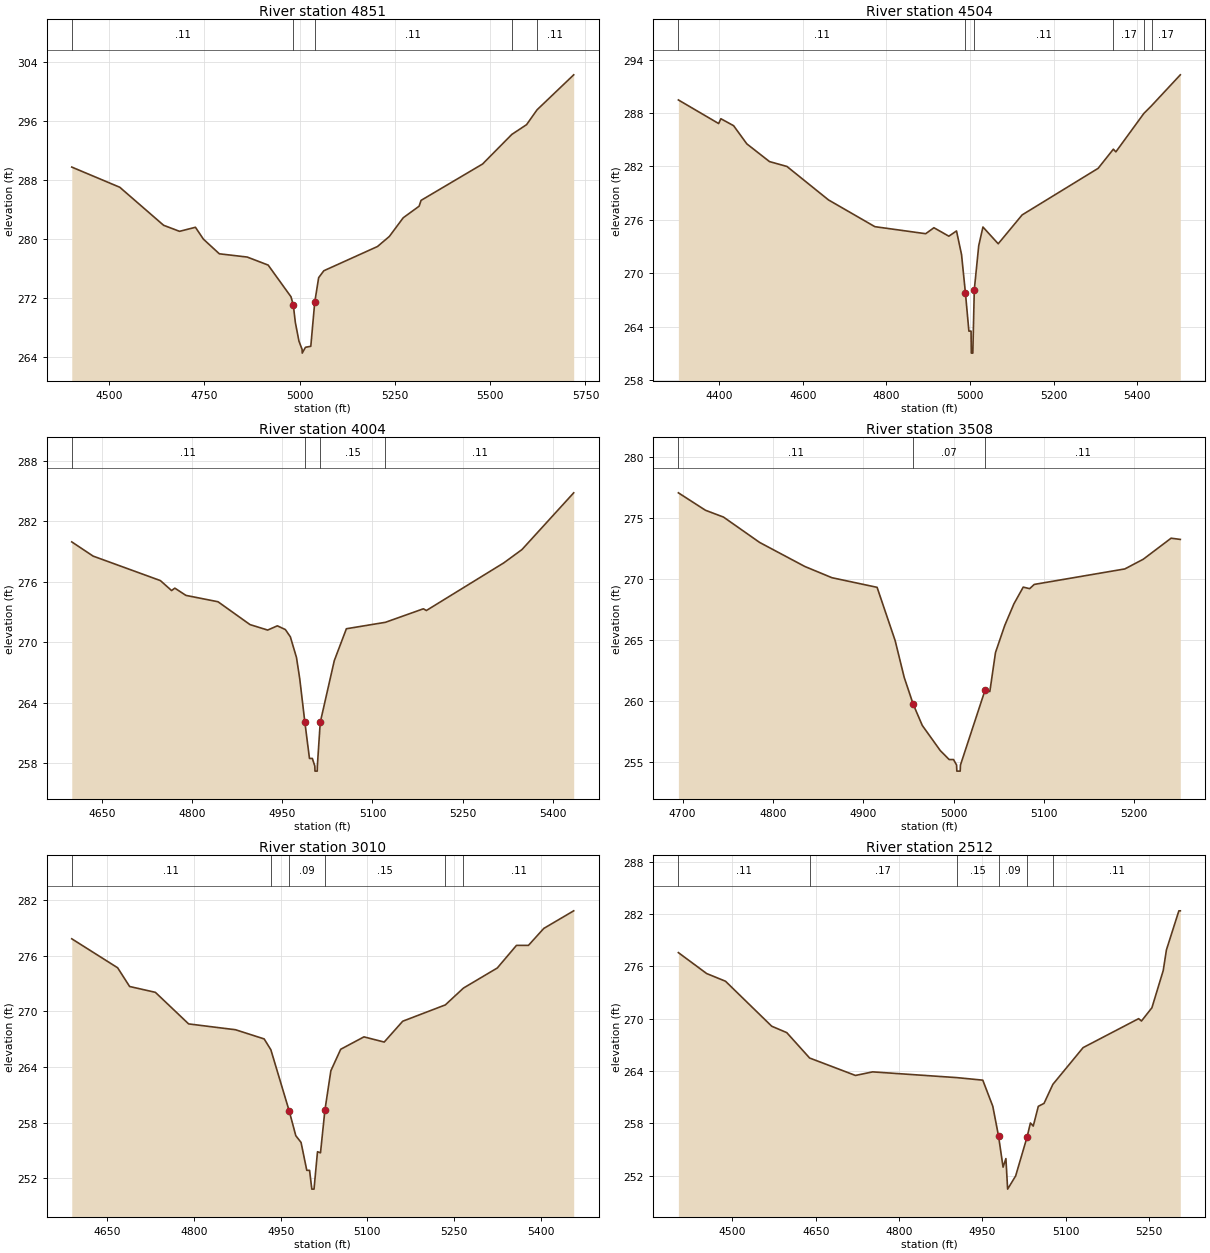
Type RM Length L Ch R = 1 ,4851    ,347,347,347
BEGIN DESCRIPTION:
CCLC 027 10.0
END DESCRIPTION:
XS GIS Cut Line= 3
      3712335.08     10113821.85      3712512.18     10113233.26
      3712678.84     10112550.97
#Sta/Elev= 30
  4402.2  289.73  4528.2  286.99  4643.2  281.83    4685  281.01  4726.7  281.56
  4747.6  279.95  4789.4  277.96  4862.5  277.52  4917.5  276.43  4977.4  272.13
  4983.5     271  4988.8  268.66  4998.3  266.11  5006.6  264.98  5006.9  264.48
  5015.4  265.27  5029.4  265.41  5039.7  271.37    5050  274.72  5063.6  275.66
  5204.4  278.95  5235.4  280.31  5271.9  282.85  5313.6  284.42  5318.7  285.21
  5480.2  290.15  5556.8  294.16  5595.6  295.49    5623   297.5  5719.2  302.25
#Mann= 5 ,-1 , 0
  4402.2     .11       0  4983.5     .06       0  5039.7     .11       0
  5556.8     .17       0    5623     .11       0
Bank Sta=4983.5,5039.7
XS Rating Curve= 0 ,0
Exp/Cntr=0.3,0.1

Type RM Length L Ch R = 1 ,4504    ,500,500,500
BEGIN DESCRIPTION:
CCLC 027 9.0
END DESCRIPTION:
XS GIS Cut Line= 3
      3712548.64     10114014.49      3712791.34     10113360.57
      3712954.57     10112885.22
#Sta/Elev= 30
  4302.5  289.47  4398.8  286.82  4404.1  287.36  4434.5  286.58  4466.1  284.54
  4520.3  282.55  4562.1     282  4661.5  278.24  4772.3  275.24  4893.8  274.45
  4913.5  275.12  4949.2  274.17  4967.5  274.76  4979.5  272.11  4988.8  267.81
  4997.1  263.51  5002.3  263.51  5002.9  261.04  5006.5  261.04    5010  268.15
  5020.6   273.1  5030.7   275.2  5067.2  273.32  5124.4  276.56  5306.1  281.79
  5342.5  283.94  5348.5  283.64  5415.5  287.96    5434  288.83  5502.6  292.29
#Mann= 6 ,-1 , 0
  4302.5     .11       0  4988.8     .07       0    5010     .11       0
  5342.5     .17       0  5415.5     .11       0    5434     .17       0
Bank Sta=4988.8,5010
XS Rating Curve= 0 ,0
Exp/Cntr=0.3,0.1

Type RM Length L Ch R = 1 ,4004    ,496,496,496
BEGIN DESCRIPTION:
CCLC 027 8.0
END DESCRIPTION:
XS GIS Cut Line= 3
      3713048.65     10113957.19      3713201.12     10113587.28
       3713251.7     10113155.63
#Sta/Elev= 30
  4599.9  279.96  4635.4  278.55  4747.3  276.12  4765.9  275.13  4771.3  275.37
  4789.8  274.65  4843.1  274.02  4896.4  271.75  4925.7  271.21  4941.8  271.63
  4955.1  271.26  4963.4  270.54  4973.6  268.49    4979  266.39  4987.5262.0837
  4995.2  258.47    5000  258.47  5004.1  257.71  5004.4  257.21  5008.1  257.21
  5008.3  257.71  5013.1  262.04  5036.5  268.18  5056.6  271.34  5121.5  271.98
  5184.6  273.32  5189.6  273.15  5318.4  277.88  5348.6   279.2  5434.6  284.83
#Mann= 4 ,-1 , 0
  4599.9     .11       0  4987.5     .06       0  5013.1     .15       0
  5121.5     .11       0
Bank Sta=4987.5,5013.1
XS Rating Curve= 0 ,0
Exp/Cntr=0.3,0.1

Type RM Length L Ch R = 1 ,3508    ,498,498,498
BEGIN DESCRIPTION:
CCLC 027 7.0
END DESCRIPTION:
XS GIS Cut Line= 3
      3713667.85     10113961.08      3713671.15      10113656.5
      3713617.86     10113411.12
#Sta/Elev= 30
  4695.4  277.04  4725.4  275.61  4745.4  275.05  4785.4  272.97  4835.4     271
  4865.4  270.08  4915.4  269.29  4935.4  264.92  4945.4  261.91  4955.4   259.7
  4965.4  257.97  4985.4   255.9  4995.2  255.17    5000  255.17  5003.4  254.72
  5003.7  254.22  5007.4  254.22  5007.7  254.72  5035.1   260.9  5040.2  260.74
  5046.5  263.95  5056.7  266.16  5066.9  267.94  5077.2  269.31  5084.3  269.18
  5089.4  269.53  5189.7   270.8  5210.2   271.6  5240.9  273.32  5251.1  273.22
#Mann= 3 , 0 , 0
  4695.4     .11       0  4955.4     .07       0  5035.1     .11       0
Bank Sta=4955.4,5035.1
XS Rating Curve= 0 ,0
Exp/Cntr=0.3,0.1

Type RM Length L Ch R = 1 ,3010    ,498,498,498
BEGIN DESCRIPTION:
CCLC 027 6.0
END DESCRIPTION:
XS GIS Cut Line= 3
      3714033.02     10114118.65      3714118.63     10113716.66
      3714235.98      10113275.5
#Sta/Elev= 30
    4589  277.85  4668.3  274.72    4689   272.7  4733.5  272.07    4791  268.66
    4872  268.03  4921.5  267.04  4933.1  265.87  4964.8  259.26  4976.2  256.59
  4985.3  255.86  4995.2  252.85    5000  252.85  5003.9  250.82  5007.7  250.82
  5013.7  254.86  5018.9  254.74  5026.5  259.34  5036.8   263.6  5053.8  265.92
    5094  267.26    5129   266.7    5161  268.95  5234.6  270.71    5266  272.53
  5324.5   274.7  5357.6  277.14  5378.3  277.14  5404.8  278.97  5456.5  280.87
#Mann= 6 ,-1 , 0
    4589     .11       0  4933.1     .15       0  4964.8     .09       0
  5026.5     .15       0  5234.6     .17       0    5266     .11       0
Bank Sta=4964.8,5026.5
XS Rating Curve= 0 ,0
Exp/Cntr=0.3,0.1

Type RM Length L Ch R = 1 ,2512    ,419,419,419
BEGIN DESCRIPTION:
CCLC 027 5.0
END DESCRIPTION:
XS GIS Cut Line= 3
      3714413.22     10114290.52      3714555.19     10113710.55
      3714617.86     10113411.03
#Sta/Elev= 30
  4402.9  277.58  4453.8  275.18  4487.7   274.3  4570.9  269.14  4597.9  268.41
    4639   265.5  4721.5   263.5  4752.4  263.91  4904.2  263.25  4950.6  262.96
  4968.6  259.97  4978.9  256.57  4987.1  252.99  4992.2  253.97  4995.3  250.47
  5009.7  251.98  5030.1   256.4  5036.3  258.05  5041.4   257.7  5050.5  259.96
  5060.8   260.3  5076.7  262.48  5131.1  266.69    5231  270.01  5236.1  269.74
  5254.9  271.26  5275.3  275.54    5281  277.89  5303.4  282.37    5306  282.37
#Mann= 6 ,-1 , 0
  4402.9     .11       0    4639     .17       0  4904.2     .15       0
  4978.9     .09       0  5030.1     .15       0  5076.7     .11       0
Bank Sta=4978.9,5030.1
XS Rating Curve= 0 ,0
Exp/Cntr=0.3,0.1

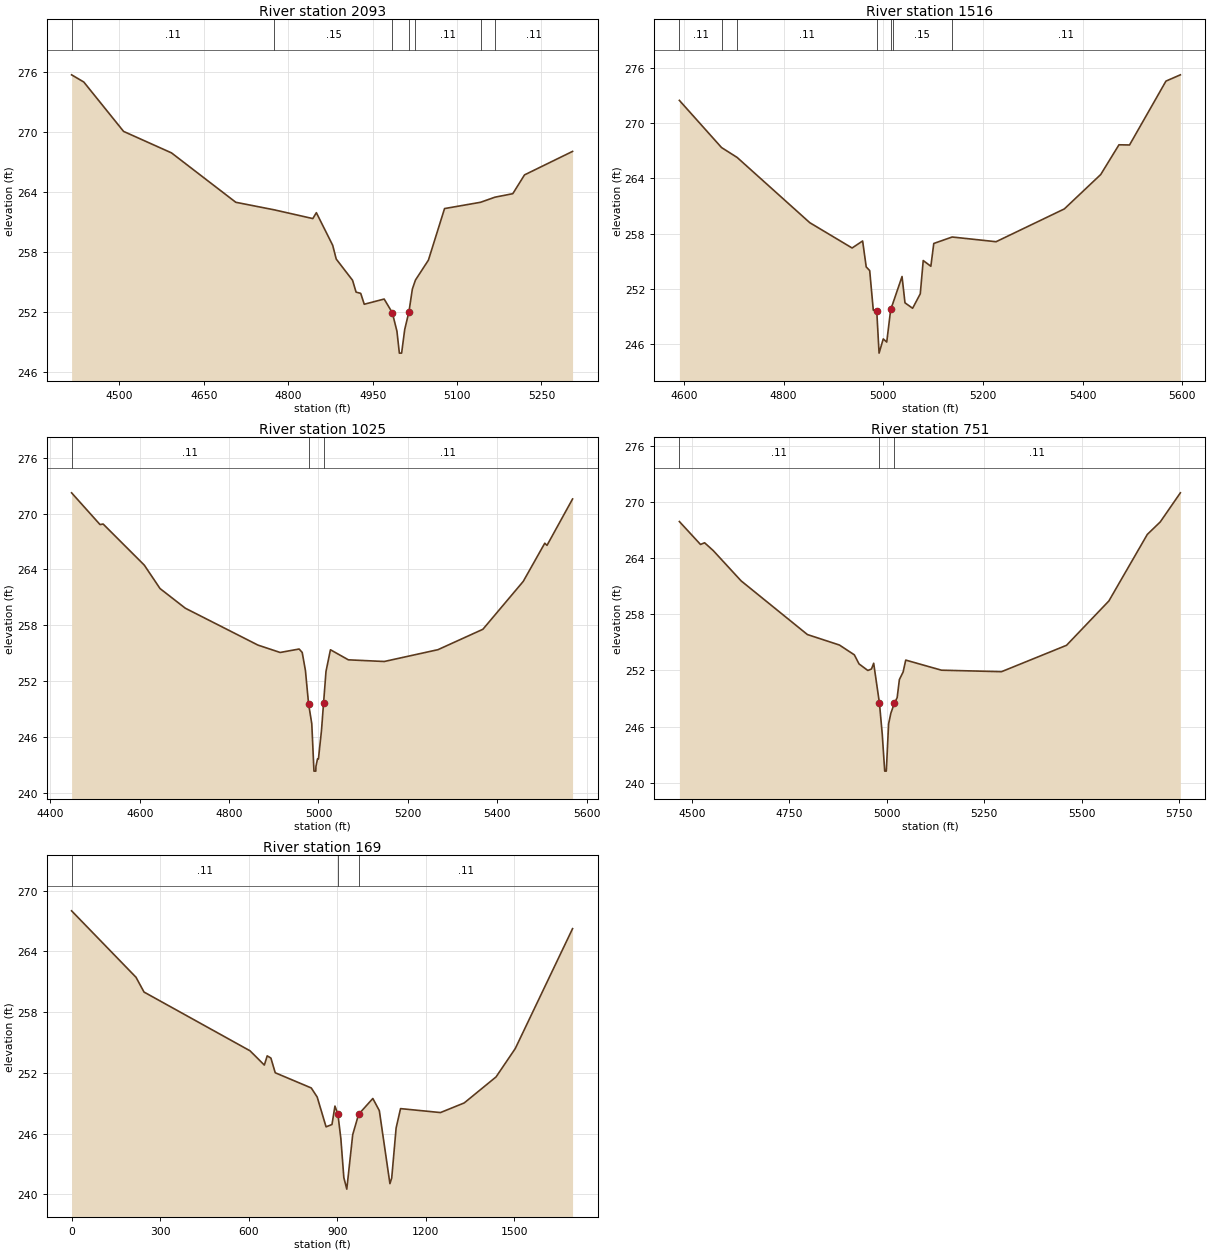
Type RM Length L Ch R = 1 ,2093    ,577,577,577
BEGIN DESCRIPTION:
CCLC 027 4.0
END DESCRIPTION:
XS GIS Cut Line= 3
      3714517.87     10114311.05      3714881.97     10113837.43
      3715067.85     10113611.07
#Sta/Elev= 30
    4415  275.71  4436.7  274.99  4507.4  270.05  4592.6   267.9  4706.8  262.96
  4775.5   262.2  4843.7  261.33    4850  261.92    4879  258.66  4885.3  257.28
  4914.3  255.16  4920.6  253.97  4928.8  253.85  4935.1  252.76  4970.5  253.28
    4985  251.91  4993.2  250.06  4997.5  247.87  5001.5  247.87    5007  250.23
  5014.6252.0337  5020.6  254.28  5026.1  255.18  5049.1  257.17  5077.8  262.33
  5141.8  262.96  5167.4  263.47  5199.1  263.82  5219.9   265.7  5305.3  268.05
#Mann= 7 ,-1 , 0
    4415     .11       0  4775.5     .15       0    4985     .09       0
  5014.6     .15       0  5026.1     .11       0  5141.8     .15       0
  5167.4     .11       0
Bank Sta=4985,5014.6
XS Rating Curve= 0 ,0
Exp/Cntr=0.3,0.1

Type RM Length L Ch R = 1 ,1516    ,491,491,491
BEGIN DESCRIPTION:
CCLC 027 3.0
END DESCRIPTION:
XS GIS Cut Line= 3
      3714967.86     10114461.06      3715252.14     10114166.87
      3715567.83     10113661.11
#Sta/Elev= 30
  4590.9  272.44  4675.5  267.33  4706.8  266.26  4852.6  259.19  4937.5  256.45
  4958.6  257.21  4965.8   254.4  4972.8     254    4980  249.72  4986.9  249.66
  4991.6  245.06    5000   246.6    5007  246.26 5015.03249.8354  5018.6  250.34
  5037.7  253.36  5043.6  250.51  5058.9  249.92  5074.3  251.49  5080.2  255.09
  5095.5  254.47  5101.4  256.94  5138.3  257.64  5226.4  257.13  5363.3  260.68
  5436.4  264.41    5473  267.63  5494.2  267.61  5567.3  274.53  5596.2  275.21
#Mann= 7 ,-1 , 0
  4590.9     .11       0  4675.5     .15       0  4706.8     .11       0
  4986.9     .06       0 5015.03     .11       0  5018.6     .15       0
  5138.3     .11       0
Bank Sta=4986.9,5015.03
XS Rating Curve= 0 ,0
Exp/Cntr=0.3,0.1

Type RM Length L Ch R = 1 ,1025    ,274,274,274
BEGIN DESCRIPTION:
CCLC 027 2.0
END DESCRIPTION:
XS GIS Cut Line= 3
      3715317.83     10114661.09      3715715.83     10114277.87
      3715667.85      10113711.1
#Sta/Elev= 30
  4447.5  272.23  4511.2  268.82  4518.1  268.88  4610.2  264.47  4645.5  261.95
  4702.1  259.84  4864.7  255.88  4914.3  255.09  4956.8  255.46  4963.7  255.09
  4970.9  253.15  4977.9  249.59  4985.1  247.44    4990  242.35  4994.1  242.35
  4994.4  242.85  4997.9  243.66    5000  243.66  5006.8   246.7 5011.52249.6676
  5016.9  253.05  5026.9  255.38    5067   254.3  5147.3  254.12  5267.6  255.39
  5368.1  257.58  5458.4  262.72  5506.6  266.82  5511.6  266.59  5568.8  271.57
#Mann= 3 , 0 , 0
  4447.5     .11       0  4977.9     .06       0 5011.52     .11       0
Bank Sta=4977.9,5011.52
XS Rating Curve= 0 ,0
Exp/Cntr=0.3,0.1

Type RM Length L Ch R = 1 ,751     ,582,582,582
BEGIN DESCRIPTION:
Mapping XS 43f94110
END DESCRIPTION:
XS GIS Cut Line= 3
       3715699.7     10114858.22      3716006.97     10114280.13
      3715887.18     10113660.37
#Sta/Elev= 30
  4467.7  267.92  4521.9  265.47  4532.4  265.65  4554.5  264.82  4626.1  261.58
  4796.3  255.84  4878.5  254.72  4916.8  253.67  4928.8   252.7  4951.4     252
  4960.8  252.16  4966.4  252.77 4981.25248.4918  4988.4   245.2  4994.7  241.24
  4998.8  241.24  5004.7  246.28  5010.4  247.42  5019.4  248.48  5026.7   249.1
  5032.4  251.03    5042  251.84  5048.7  253.11  5140.4  252.03  5294.6  251.87
  5461.4  254.69  5570.1  259.43  5668.7  266.54    5702  267.88  5753.6  270.99
#Mann= 3 , 0 , 0
  4467.7     .11       0 4981.25     .06       0  5019.4     .11       0
Bank Sta=4981.25,5019.4
XS Rating Curve= 0 ,0
Exp/Cntr=0.3,0.1

Type RM Length L Ch R = 1 ,169     ,0,0,0
XS GIS Cut Line= 4
      3715809.26     10115010.79      3716486.34      10114602.8
       3716503.7     10114390.13      3717078.79     10114001.67
#Sta/Elev= 30
       0  268.01   218.3  261.45   245.5  259.99   604.7  254.19   653.3  252.78
     663  253.69   675.5  253.47   690.2  252.02   812.3  250.52   832.4  249.62
   862.5  246.68   882.5  246.91   892.6  248.73   902.6  247.92   912.6  245.52
   922.7  241.67   932.7  240.53   952.8  245.91   972.8  247.92    1021  249.48
    1043  248.28  1078.9  241.07    1085  241.63  1099.9  246.57  1114.9  248.48
  1250.2  248.09  1330.7  249.04  1438.6  251.61  1503.7  254.41  1697.9  266.25
#Mann= 3 , 0 , 0
       0     .11       0   902.6     .06       0   972.8     .11       0
Bank Sta=902.6,972.8
XS Rating Curve= 0 ,0
Exp/Cntr=0.3,0.1

Chan Stop Cuts=-1
Use User Specified Reach Order=0
Composite Channel Slope=5