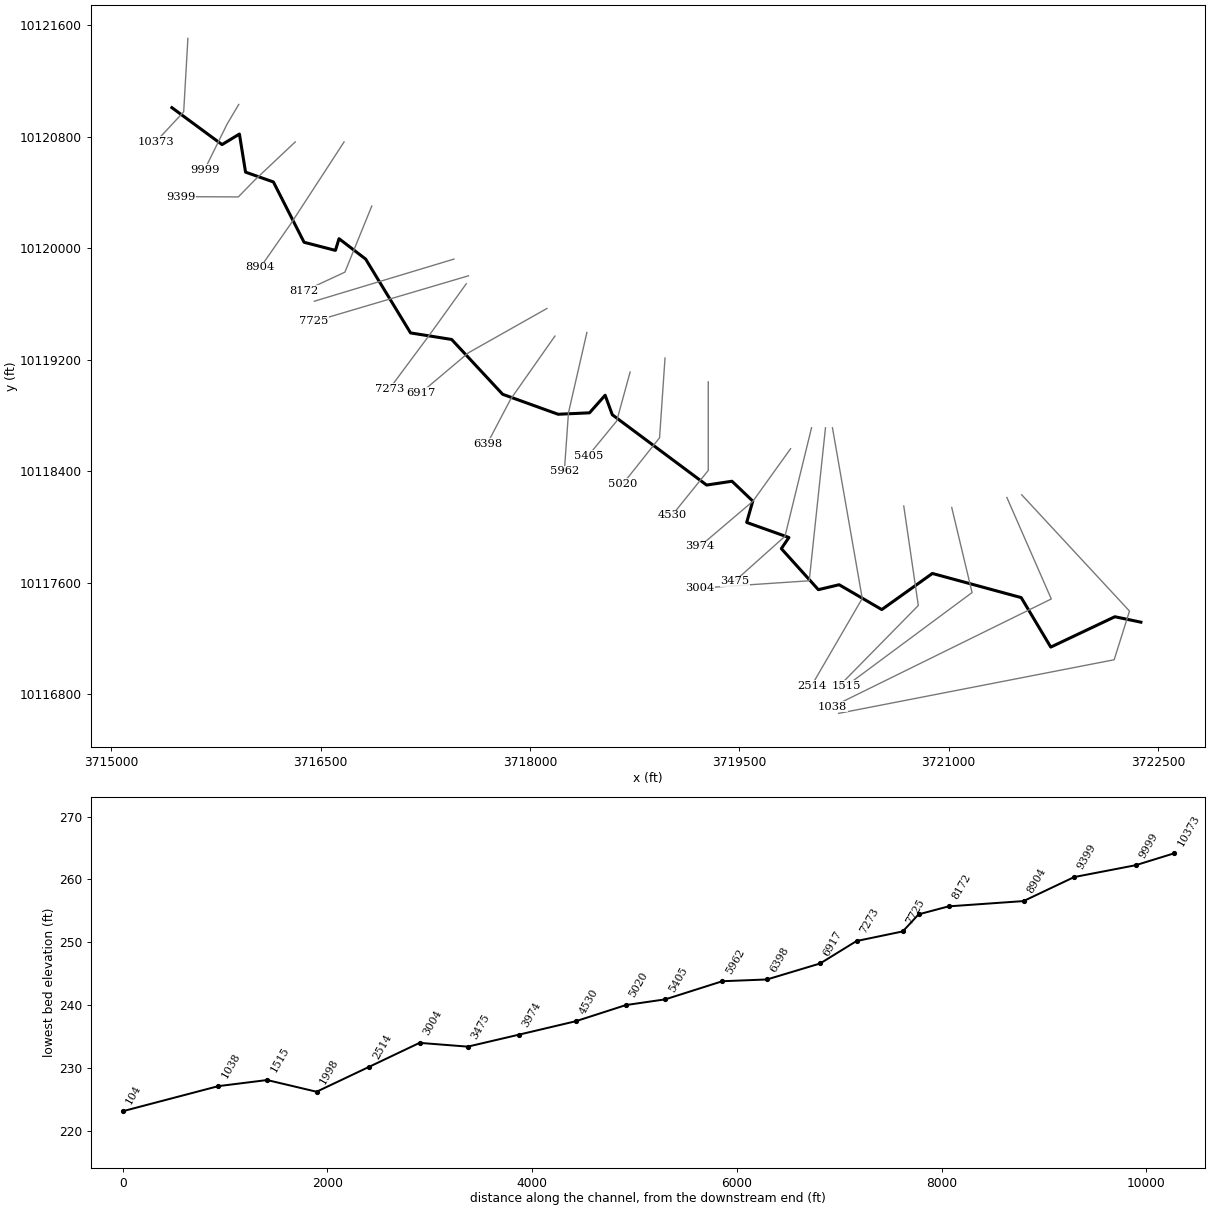
--- CCLC 028.prj (project) ---

Proj Title=CCLC 028 Base Level Engineering
Current Plan=p01
Default Exp/Contr=0.3,0.1
English Units
Geom File=g01
Flow File=f01
Flow File=f02
Plan File=p01
Y Axis Title=Elevation
X Axis Title(PF)=Main Channel Distance
X Axis Title(XS)=Station
BEGIN DESCRIPTION:
CCLC 028
END DESCRIPTION:
DSS Export Rating Curves= 0
DSS Export Rating Curve Sorted= 0
DSS Export Volume Flow Curves= 0
DXF OffsetX= 0
DXF OffsetY= 0
DXF ScaleX= 1
DXF ScaleY= 10

--- CCLC 028.p01 (plan) ---

Plan Title=Multiple Run
Short Identifier=Multiple
Geom File=g01
Flow File=f01
Subcritical Flow
K Sum by GR= 0
Std Step Tol= 0.01
Critical Tol= 0.01
Num of Std Step Trials= 20
Max Error Tol= 0.3
Flow Tol Ratio= 0.001
Split Flow NTrial= 30
Split Flow Tol= 0.02
Split Flow Ratio= 0.02
Log Output Level= 0
Friction Slope Method= 1
Unsteady Friction Slope Method= 2
Unsteady Bridges Friction Slope Method= 1
Parabolic Critical Depth
Global Vel Dist=  1 , 1 , 1
Global Log Level= 0
CheckData=True
Encroach Param= -1, 0, 0, 0
BEGIN DESCRIPTION:
Multiple Run
END DESCRIPTION:

--- CCLC 028.f01 (steady flow) ---

Flow Title=Multiple
Program Version=4.10
Number of Profiles= 7
Profile Names=10-year,25-year,50-year,1pct_min,100-year,1pct_plu,500-year
River Rch & RM=CCLC 028,Reach-1         ,10373
     759    1040    1418     636    1920    5798    3638
River Rch & RM=CCLC 028,Reach-1         ,3974
     663     893    1201     531    1603    4841    2955
Boundary for River Rch & Prof#=CCLC 028,Reach-1         , 1
Up Type= 0
Dn Type= 3
Dn Slope=0.005
Boundary for River Rch & Prof#=CCLC 028,Reach-1         , 2
Up Type= 0
Dn Type= 3
Dn Slope=0.005
Boundary for River Rch & Prof#=CCLC 028,Reach-1         , 3
Up Type= 0
Dn Type= 3
Dn Slope=0.005
Boundary for River Rch & Prof#=CCLC 028,Reach-1         , 4
Up Type= 0
Dn Type= 3
Dn Slope=0.005
Boundary for River Rch & Prof#=CCLC 028,Reach-1         , 5
Up Type= 0
Dn Type= 3
Dn Slope=0.005
Boundary for River Rch & Prof#=CCLC 028,Reach-1         , 6
Up Type= 0
Dn Type= 3
Dn Slope=0.005
Boundary for River Rch & Prof#=CCLC 028,Reach-1         , 7
Up Type= 0
Dn Type= 3
Dn Slope=0.005
DSS Import GetInterval= 0
DSS Import GetPeak= 0
DSS Import FillOption= 0

--- CCLC 028.f02 (steady flow) ---

Flow Title=Orig_BLE_Flows
Program Version=4.10
Number of Profiles= 7
Profile Names=10-year,25-year,50-year,1pct_min,100-year,1pct_plu,500-year
River Rch & RM=CCLC 028,Reach-1         ,10373
     759    1020    1233     489    1477    4459    2115
River Rch & RM=CCLC 028,Reach-1         ,3974
     663     875    1044     408    1233    3724    1718
Boundary for River Rch & Prof#=CCLC 028,Reach-1         , 1
Up Type= 0
Dn Type= 3
Dn Slope=0.005
Boundary for River Rch & Prof#=CCLC 028,Reach-1         , 2
Up Type= 0
Dn Type= 3
Dn Slope=0.005
Boundary for River Rch & Prof#=CCLC 028,Reach-1         , 3
Up Type= 0
Dn Type= 3
Dn Slope=0.005
Boundary for River Rch & Prof#=CCLC 028,Reach-1         , 4
Up Type= 0
Dn Type= 3
Dn Slope=0.005
Boundary for River Rch & Prof#=CCLC 028,Reach-1         , 5
Up Type= 0
Dn Type= 3
Dn Slope=0.005
Boundary for River Rch & Prof#=CCLC 028,Reach-1         , 6
Up Type= 0
Dn Type= 3
Dn Slope=0.005
Boundary for River Rch & Prof#=CCLC 028,Reach-1         , 7
Up Type= 0
Dn Type= 3
Dn Slope=0.005
DSS Import GetInterval= 0
DSS Import GetPeak= 0
DSS Import FillOption= 0

--- CCLC 028.g01 (geometry) ---

Geom Title=Existing Conditions
Program Version=4.10

River Reach=CCLC 028        ,Reach-1
Reach XY= 30
      3715433.98     10121006.87       3715793.3     10120742.03
      3715917.86      10120817.6      3715961.77     10120544.45
       3716161.4     10120473.98      3716381.26     10120041.43
      3716605.95     10119983.22      3716631.67     10120067.14
      3716822.52     10119920.96      3717144.29     10119391.33
      3717438.96     10119344.38      3717804.14     10118951.31
      3718201.58     10118807.99      3718426.79     10118818.32
      3718538.81     10118944.35      3718590.03     10118804.55
      3719265.92     10118300.27      3719447.82     10118327.58
      3719596.85     10118185.38      3719553.18     10118032.16
      3719855.77     10117924.24      3719801.54     10117844.37
      3720066.74     10117549.98      3720215.73     10117585.41
      3720521.26     10117407.28      3720883.92     10117666.24
      3721520.52      10117493.1      3721732.25     10117138.17
      3722191.65     10117355.84      3722378.23     10117316.84

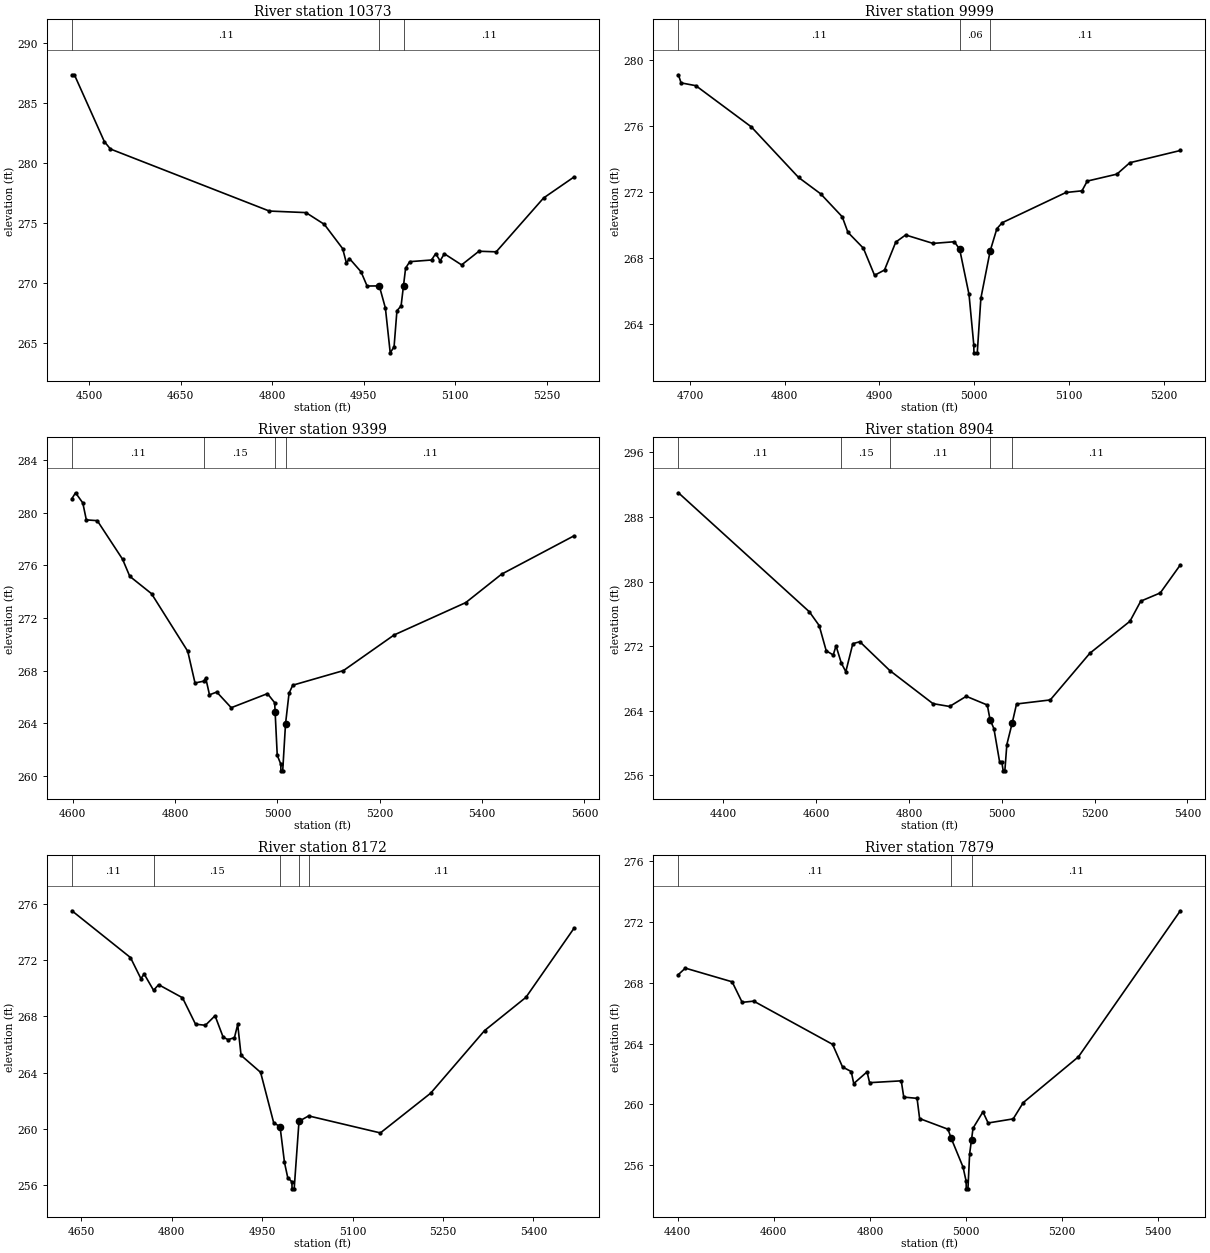
Type RM Length L Ch R = 1 ,10373   ,374,374,374
BEGIN DESCRIPTION:
CCLC 028 19.0
END DESCRIPTION:
XS GIS Cut Line= 3
      3715548.63     10121504.05      3715518.46     10120976.92
      3715317.83     10120761.05
#Sta/Elev= 30
    4472  287.32    4476  287.32  4525.1  281.75  4535.1  281.13  4795.5  275.96
  4855.6  275.83  4885.7  274.85  4915.7  272.83  4921.9  271.63  4926.9     272
  4945.8   270.9  4955.8  269.71  4975.8  269.72  4985.8  267.87  4993.7  264.14
    5000  264.64  5004.7  267.65  5011.5  268.05  5015.5269.7527  5018.9   271.2
  5025.7  271.74  5061.4  271.88  5068.2  272.41  5075.5  271.81  5082.4   272.4
  5110.7  271.47  5139.1  272.61  5167.4  272.56  5245.1  277.05  5294.7  278.79
#Mann= 3 , 0 , 0
    4472     .11       0  4975.8     .06       0  5015.5     .11       0
Bank Sta=4975.8,5015.5
XS Rating Curve= 0 ,0
Exp/Cntr=0.3,0.1

Type RM Length L Ch R = 1 ,9999    ,600,600,600
BEGIN DESCRIPTION:
CCLC 028 18.0
END DESCRIPTION:
XS GIS Cut Line= 3
      3715913.24     10121030.17      3715829.88     10120889.51
      3715667.87      10120561.1
#Sta/Elev= 30
  4687.8  279.08  4690.6  278.59  4706.2  278.42  4764.7  275.93  4814.6  272.87
  4837.9  271.88  4860.7  270.49  4866.7  269.55    4883  268.59  4894.8  266.95
  4905.3  267.27  4917.2  268.96  4927.6  269.39  4956.5  268.88    4979  268.98
  4984.6  268.53  4994.5  265.79  4999.5  262.76  4999.7  262.26  5003.2  262.26
    5007  265.56  5016.8  268.42  5023.9  269.77  5029.5  270.13  5096.8  271.96
  5113.7  272.06  5119.3  272.65  5150.6  273.07  5164.2  273.76  5217.5   274.5
#Mann= 3 , 0 , 0
  4687.8     .11       0  4984.6     .06       0  5016.8     .11       0
Bank Sta=4984.6,5016.8
XS Rating Curve= 0 ,0
Exp/Cntr=0.3,0.1

Type RM Length L Ch R = 1 ,9399    ,495,495,495
BEGIN DESCRIPTION:
CCLC 028 17.0
END DESCRIPTION:
XS GIS Cut Line= 4
      3716317.82     10120761.04      3716025.68     10120485.47
      3715910.05     10120366.69      3715496.52     10120368.68
#Sta/Elev= 30
  4598.4  281.08  4605.4  281.52  4619.6  280.75  4626.5  279.46  4647.9   279.4
  4697.3  276.47  4711.4  275.17  4753.9  273.85  4824.7  269.47  4838.9  267.06
  4856.2   267.2  4859.9  267.43  4867.2  266.16  4881.4  266.37  4909.7  265.18
  4980.5  266.25  4994.6  265.56  4995.5  264.84  4999.6  261.57  5006.6  260.88
  5006.8  260.38  5010.3  260.38  5015.8  263.95  5022.7  266.28  5029.9  266.89
  5128.9     268    5228  270.71    5368  273.17    5438  275.33  5579.3  278.24
#Mann= 4 ,-1 , 0
  4598.4     .11       0  4856.2     .15       0  4995.5     .06       0
  5015.8     .11       0
Bank Sta=4995.5,5015.8
XS Rating Curve= 0 ,0
Exp/Cntr=0.3,0.1

Type RM Length L Ch R = 1 ,8904    ,732,732,732
BEGIN DESCRIPTION:
CCLC 028 16.0
END DESCRIPTION:
XS GIS Cut Line= 3
      3716667.86     10120761.09      3716287.86     10120176.78
      3716067.86     10119861.08
#Sta/Elev= 30
    4303  290.99  4585.3  276.25  4606.4  274.55  4621.6  271.42  4636.7  270.91
  4642.7  272.03  4654.3  269.88  4663.8  268.84  4678.9   272.3    4694  272.55
  4758.6  268.98  4851.7  264.88  4887.5  264.53  4923.4  265.79  4968.8  264.71
  4974.7  262.89    4983  261.79  4995.4  257.64    5000  257.64  5003.1  256.56
  5006.6  256.56  5010.9  259.82  5022.4262.4749  5031.8  264.84  5104.5  265.34
  5189.8  271.12  5276.2  275.08  5299.5  277.57  5341.6  278.59  5384.8  282.06
#Mann= 5 ,-1 , 0
    4303     .11       0  4654.3     .15       0  4758.6     .11       0
  4974.7     .06       0  5022.4     .11       0
Bank Sta=4974.7,5022.4
XS Rating Curve= 0 ,0
Exp/Cntr=0.3,0.1

Type RM Length L Ch R = 1 ,8172    ,293,293,293
BEGIN DESCRIPTION:
CCLC 028 15.0
END DESCRIPTION:
XS GIS Cut Line= 3
      3716866.35     10120300.99      3716673.63     10119827.01
      3716382.45     10119691.82
#Sta/Elev= 30
  4634.5  275.51  4731.6  272.18  4748.9  270.68  4754.3  271.01  4769.9  269.85
  4778.3  270.25  4817.9  269.32  4839.5  267.44  4855.9  267.36  4871.9  268.04
  4885.4  266.51  4893.5  266.34  4904.1  266.48  4909.5  267.42  4915.1  265.22
  4947.5  264.01  4969.1  260.44  4979.8  260.13  4987.1   257.6  4992.5  256.52
  4999.4  256.22  4999.7  255.72  5003.2  255.72  5011.2  260.53  5027.2  260.91
  5146.2   259.7  5229.7  262.53    5319  266.98  5387.7  269.35  5467.2  274.25
#Mann= 5 ,-1 , 0
  4634.5     .11       0  4769.9     .15       0  4979.8     .09       0
  5011.2     .15       0  5027.2     .11       0
Bank Sta=4979.8,5011.2
XS Rating Curve= 0 ,0
Exp/Cntr=0.3,0.1

Type RM Length L Ch R = 1 ,7879    ,154,154,154
BEGIN DESCRIPTION:
Mapping XS 14d36def
END DESCRIPTION:
XS GIS Cut Line= 2
       3717454.9     10119920.76      3716454.93     10119618.69
#Sta/Elev= 30
  4401.4  268.54  4415.8  268.96  4513.2  268.06  4534.1  266.71  4558.1  266.79
  4722.2  263.95    4743  262.46  4761.1  262.16  4766.3  261.37    4794  262.14
  4799.3  261.43  4865.2  261.55  4870.4  260.48  4898.1   260.4  4903.4  259.07
  4962.4  258.37  4969.3  257.76  4993.8  255.88  5000.2  254.95  5000.5  254.45
    5004  254.45  5007.5  256.75 5011.44257.6878  5014.6  258.44  5035.2  259.51
    5046  258.78  5098.2  259.05  5119.1  260.12    5234  263.13    5446  272.73
#Mann= 3 , 0 , 0
  4401.4     .11       0  4969.3     .07       0 5011.44     .11       0
Bank Sta=4969.3,5011.44
XS Rating Curve= 0 ,0
Exp/Cntr=0.3,0.1

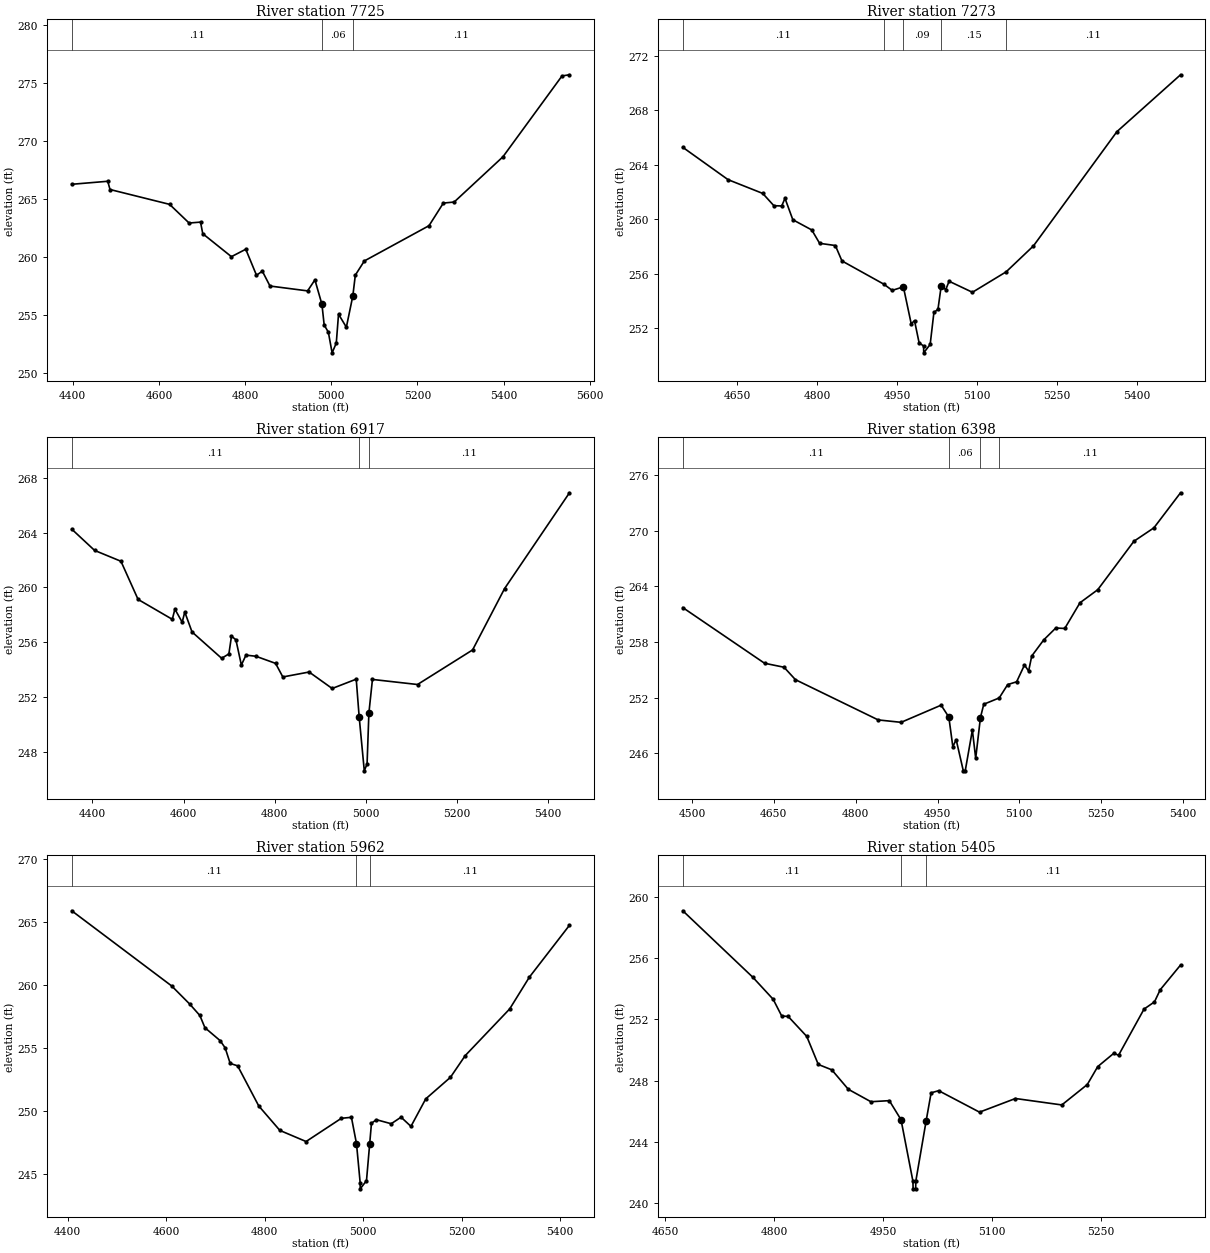
Type RM Length L Ch R = 1 ,7725    ,452,452,452
BEGIN DESCRIPTION:
Mapping XS 46089ed1
END DESCRIPTION:
XS GIS Cut Line= 2
      3717559.03     10119800.96      3716451.27     10119473.32
#Sta/Elev= 30
  4397.6  266.27  4481.2  266.53  4486.4  265.82  4624.7  264.54    4670  262.93
  4696.5  263.01  4701.7  262.01  4768.2  260.03  4801.5  260.67  4826.4  258.43
    4840  258.78  4857.7   257.5    4945  257.08    4962  258.03  4978.3  255.92
  4983.5  254.14  4993.2  253.52  5001.9  251.74  5011.6  252.58  5016.8  255.07
    5035  253.95    5050  256.65  5055.8  258.44  5076.7  259.66  5226.8   262.7
  5260.1  264.65  5285.2  264.74  5398.4  268.64  5535.5  275.61  5552.8  275.71
#Mann= 3 , 0 , 0
  4397.6     .11       0  4978.3     .06       0    5050     .11       0
Bank Sta=4978.3,5050
XS Rating Curve= 0 ,0
Exp/Cntr=0.3,0.1

Type RM Length L Ch R = 1 ,7273    ,356,356,356
BEGIN DESCRIPTION:
CCLC 028 14.0
END DESCRIPTION:
XS GIS Cut Line= 3
      3717543.42     10119743.66       3717277.8     10119373.88
      3716992.12     10118989.51
#Sta/Elev= 30
    4548  265.28  4632.9  262.91    4698   261.9  4718.9     261  4733.6  260.98
  4739.8  261.54  4754.5  259.97  4790.1  259.22  4804.8  258.24  4834.3  258.08
  4846.7  256.95  4925.1  255.25  4941.1  254.79    4962  255.05  4976.7  252.34
  4982.9  252.57  4991.5  250.95  4999.9  250.71  5000.2  250.21  5012.3  250.83
  5019.3  253.17  5026.9   253.4  5033.1  255.14  5041.5  254.84  5047.8  255.46
  5091.6  254.65  5154.9  256.15  5206.1  258.05  5362.8  266.43  5482.2   270.6
#Mann= 5 ,-1 , 0
    4548     .11       0  4925.1     .15       0    4962     .09       0
  5033.1     .15       0  5154.9     .11       0
Bank Sta=4962,5033.1
XS Rating Curve= 0 ,0
Exp/Cntr=0.3,0.1

Type RM Length L Ch R = 1 ,6917    ,519,519,519
BEGIN DESCRIPTION:
CCLC 028 13.0
END DESCRIPTION:
XS GIS Cut Line= 3
      3718121.53     10119566.58      3717559.05     10119248.88
      3717217.84     10118961.06
#Sta/Elev= 30
  4354.6  264.25  4404.8   262.7  4462.6  261.91  4500.2  259.13  4575.3  257.68
    4581  258.42    4597  257.47  4602.7  258.21  4618.6  256.76  4683.6  254.84
  4699.5  255.16  4705.2  256.45  4714.9  256.19  4726.9  254.35    4737  255.07
  4758.7  254.99    4802  254.47  4817.9  253.48  4875.6  253.84  4926.2  252.64
    4979  253.32  4985.4  250.59  4996.7  246.64  5002.8  247.14  5006.8  250.86
  5014.6   253.3  5113.5  252.93  5234.4  255.45  5304.6  259.92    5447   266.9
#Mann= 3 , 0 , 0
  4354.6     .11       0  4985.4     .06       0  5006.8     .11       0
Bank Sta=4985.4,5006.8
XS Rating Curve= 0 ,0
Exp/Cntr=0.3,0.1

Type RM Length L Ch R = 1 ,6398    ,436,436,436
BEGIN DESCRIPTION:
CCLC 028 12.0
END DESCRIPTION:
XS GIS Cut Line= 3
      3718178.85     10119368.68      3717861.13     10118915.55
      3717694.46     10118597.83
#Sta/Elev= 30
  4483.2   261.7    4633   255.7  4668.7  255.27  4689.6  253.93  4841.3  249.59
  4883.3  249.33  4956.6  251.18 4970.73249.9021  4978.1   246.7  4984.2  247.46
  4997.3   244.1  5000.8   244.1  5013.9  248.49    5020  245.45  5028.7  249.85
  5034.8  251.28  5063.1  251.96  5078.6   253.4    5095   253.7  5109.4  255.51
    5117  254.86  5122.7  256.48  5144.7  258.22  5166.8   259.5  5183.2  259.45
  5211.1  262.22  5243.7  263.63  5309.9  268.85  5346.6   270.3  5395.4  274.08
#Mann= 4 ,-1 , 0
  4483.2     .11       0 4970.73     .06       0  5028.7     .15       0
  5063.1     .11       0
Bank Sta=4970.73,5028.7
XS Rating Curve= 0 ,0
Exp/Cntr=0.3,0.1

Type RM Length L Ch R = 1 ,5962    ,557,557,557
BEGIN DESCRIPTION:
CCLC 028 11.0
END DESCRIPTION:
XS GIS Cut Line= 3
      3718408.02     10119394.75      3718275.85      10118817.8
      3718246.55     10118399.92
#Sta/Elev= 30
  4408.1  265.86  4611.1   259.9  4647.8  258.46  4668.3  257.56  4678.6  256.59
  4709.4  255.57  4719.6     255  4729.9  253.76    4745  253.57  4787.9  250.39
  4830.8  248.45    4884  247.57  4955.6  249.41  4976.1  249.49  4986.4   247.4
  4993.8  244.32    4994  243.82  5006.7  244.47 5013.19247.3937  5016.8  249.02
  5026.8   249.3  5056.9  248.98  5076.9   249.5    5097  248.77    5127  250.95
  5177.2  252.66  5207.2  254.38  5297.5  258.08  5337.5   260.6  5418.9  264.71
#Mann= 3 , 0 , 0
  4408.1     .11       0  4986.4     .06       0 5013.19     .11       0
Bank Sta=4986.4,5013.19
XS Rating Curve= 0 ,0
Exp/Cntr=0.3,0.1

Type RM Length L Ch R = 1 ,5405    ,385,385,385
BEGIN DESCRIPTION:
CCLC 028 10.0
END DESCRIPTION:
XS GIS Cut Line= 3
      3718717.86     10119111.12      3718621.55      10118759.3
      3718417.83     10118511.05
#Sta/Elev= 30
    4674  259.07  4770.6  254.73  4798.5   253.3  4810.3  252.21  4819.2  252.18
  4844.8  250.88  4860.7  249.05  4879.3   248.7  4902.1  247.43  4933.2  246.62
  4958.6  246.69  4974.7  245.45  4991.1  241.44  4991.4  240.94  4994.9  240.94
  4995.1  241.44 5009.39245.3862  5016.2   247.2  5026.6  247.34  5082.9  245.94
  5132.4  246.83  5196.3  246.41  5231.4  247.74  5245.8  248.91    5268  249.78
  5274.5  249.65  5309.6  252.66    5324  253.13  5331.9  253.92  5359.9  255.53
#Mann= 3 , 0 , 0
    4674     .11       0  4974.7     .06       0 5009.39     .11       0
Bank Sta=4974.7,5009.39
XS Rating Curve= 0 ,0
Exp/Cntr=0.3,0.1

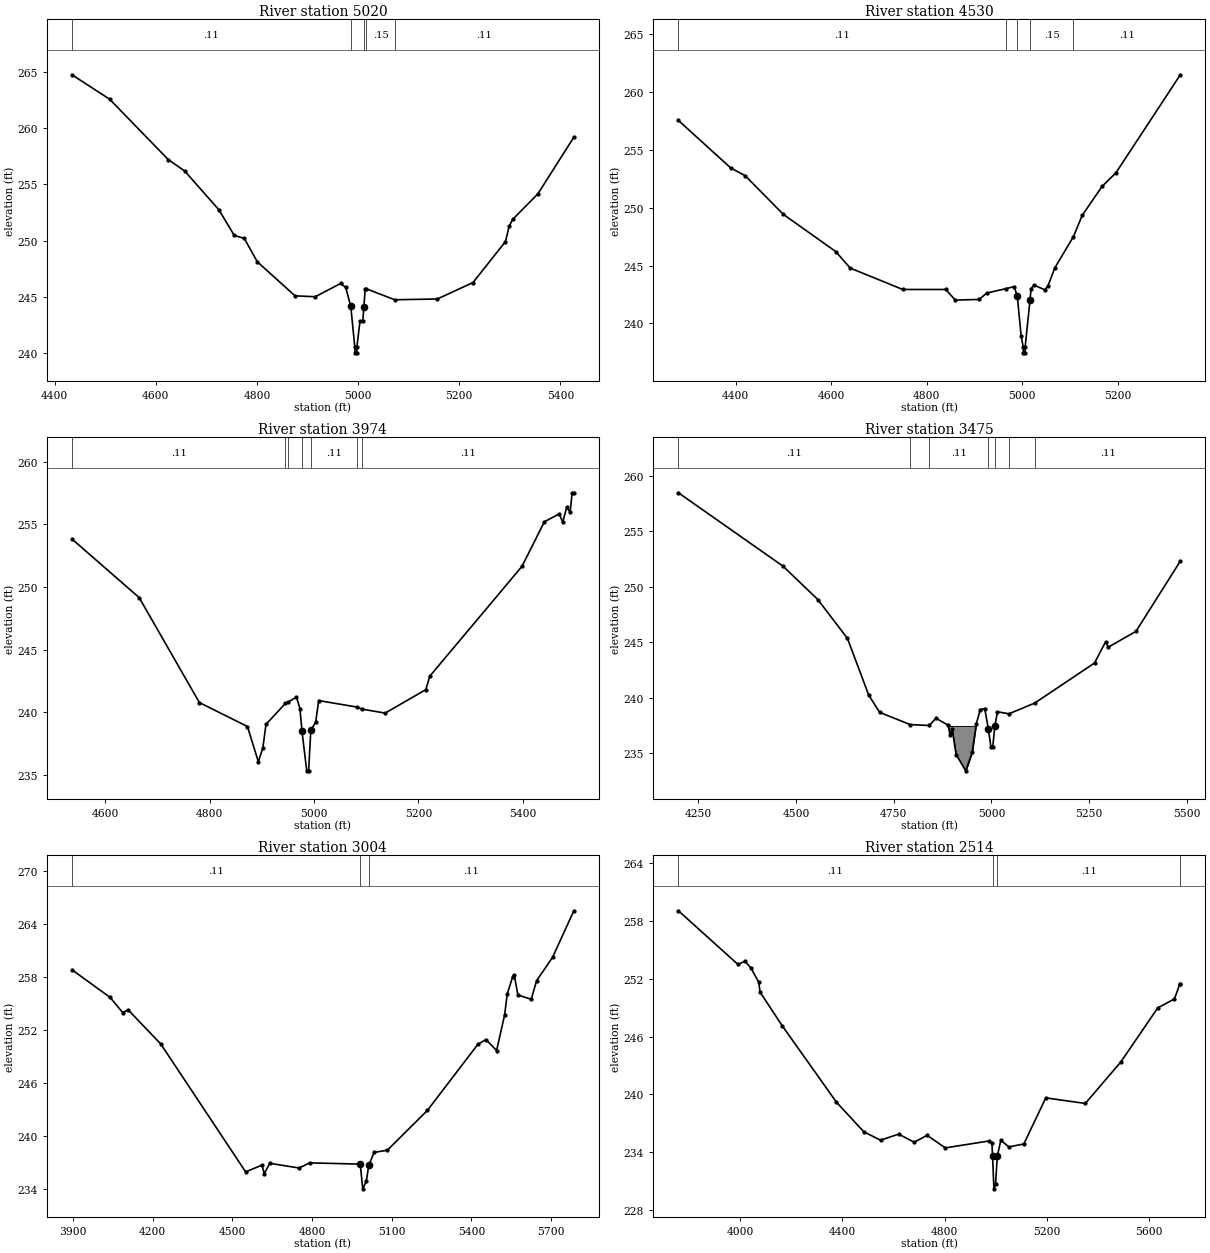
Type RM Length L Ch R = 1 ,5020    ,490,490,490
BEGIN DESCRIPTION:
CCLC 028 9.0
END DESCRIPTION:
XS GIS Cut Line= 3
      3718967.85      10119211.1      3718928.84     10118639.51
      3718667.87      10118311.1
#Sta/Elev= 30
  4434.3  264.71  4508.6  262.55  4624.8  257.18  4657.2  256.17    4725  252.72
  4755.1  250.46  4775.1  250.18  4800.8  248.11  4875.4  245.09  4915.4  245.01
  4965.6  246.19  4975.6  245.83  4985.6  244.17  4993.6  240.53  4993.9  240.03
  4997.4  240.03  4997.6  240.53  5003.9  242.86  5009.4  242.86  5011.5244.1112
  5014.2  245.72  5016.5  245.71  5072.6  244.74  5156.8  244.81  5227.3  246.27
  5291.4   249.9    5299  251.29  5305.8  251.88  5355.4  254.13  5426.7  259.17
#Mann= 5 ,-1 , 0
  4434.3     .11       0  4985.6     .06       0  5011.5     .11       0
  5016.5     .15       0  5072.6     .11       0
Bank Sta=4985.6,5011.5
XS Rating Curve= 0 ,0
Exp/Cntr=0.3,0.1

Type RM Length L Ch R = 1 ,4530    ,556,556,556
BEGIN DESCRIPTION:
CCLC 028 8.0
END DESCRIPTION:
XS GIS Cut Line= 3
       3719277.8     10119040.59       3719277.8     10118405.13
      3719017.38     10118082.21
#Sta/Elev= 30
  4280.5  257.56    4390  253.45    4420  252.79    4500  249.44    4610  246.21
    4640  244.79    4750  242.94    4840  242.94    4860  242.02    4910  242.08
  4925.7  242.63  4966.7  243.02  4983.3  243.19  4989.7  242.34  4997.7  238.92
  5002.1  237.96  5002.3  237.46  5005.8  237.46  5006.1  237.96 5016.23242.0261
  5018.5  243.02  5024.9  243.31  5047.2  242.91  5053.7  243.23  5068.1   244.8
  5107.1  247.51  5125.6  249.36  5167.2  251.86    5196  253.03  5330.8  261.51
#Mann= 5 ,-1 , 0
  4280.5     .11       0  4966.7     .15       0  4989.7     .09       0
 5016.23     .15       0  5107.1     .11       0
Bank Sta=4989.7,5016.23
XS Rating Curve= 0 ,0
Exp/Cntr=0.3,0.1

Type RM Length L Ch R = 1 ,3974    ,499,499,499
BEGIN DESCRIPTION:
CCLC 028 7.0
END DESCRIPTION:
XS GIS Cut Line= 3
      3719867.84     10118561.05       3719597.4     10118183.64
      3719217.85     10117861.07
#Sta/Elev= 30
  4535.7  253.83  4664.6  249.15  4780.1  240.77  4872.2  238.86  4893.1  236.05
  4901.7  237.14  4907.8  239.03  4945.1  240.71  4950.8  240.82  4966.2  241.21
  4972.9  240.29 4976.79 238.483  4985.9  235.32  4989.5  235.32  4993.8  238.58
    5003  239.19  5008.8  240.93  5082.5  240.41  5091.6  240.25  5136.2  239.93
  5214.2   241.8  5221.9  242.88  5398.7  251.65  5441.6  255.21  5470.1  255.83
  5476.7  255.18  5484.4  256.35    5491  255.98  5494.8  257.52  5498.1  257.52
#Mann= 7 ,-1 , 0
  4535.7     .11       0  4945.1     .15       0  4950.8     .11       0
 4976.79     .06       0  4993.8     .11       0  5082.5     .15       0
  5091.6     .11       0
Bank Sta=4976.79,4993.8
XS Rating Curve= 0 ,0
Exp/Cntr=0.3,0.1

Type RM Length L Ch R = 1 ,3475    ,471,471,471
BEGIN DESCRIPTION:
CCLC 028 6.0
END DESCRIPTION:
XS GIS Cut Line= 3
      3720017.86     10118711.11      3719827.84     10117933.18
      3719467.82     10117611.04
#Sta/Elev= 30
  4199.2  258.49  4466.9  251.87  4555.9  248.86  4631.6  245.36    4686  240.25
  4713.9  238.69  4792.2  237.59  4840.6  237.51  4858.1  238.16  4888.9  237.54
  4894.3  236.62  4899.5  237.15  4909.5  234.89  4934.2  233.42  4950.7   235.1
    4961  237.62  4971.3  238.95  4982.8  239.03  4991.9  237.23  4998.5  235.59
  5003.3  235.59  5008.7  237.47  5015.4  238.75  5044.5  238.56  5110.7  239.53
  5263.6  243.14    5292  245.06  5298.8  244.57  5369.8     246  5483.1  252.33
#Mann= 7 ,-1 , 0
  4199.2     .11       0  4792.2     .15       0  4840.6     .11       0
  4991.9     .06       0  5008.7     .11       0  5044.5     .15       0
  5110.7     .11       0
#Block Obstruct= 1 ,-1
 4888.99 4964.39  237.47
Bank Sta=4991.9,5008.7
XS Rating Curve= 0 ,0
Exp/Cntr=0.3,0.1

Type RM Length L Ch R = 1 ,3004    ,490,490,490
BEGIN DESCRIPTION:
CCLC 028 5.0
END DESCRIPTION:
XS GIS Cut Line= 3
      3720117.85     10118711.06      3720001.28     10117613.73
      3719217.85     10117561.07
#Sta/Elev= 30
  3896.5  258.83  4040.4  255.69  4087.6  253.97  4107.7   254.3  4230.6  250.43
  4550.1  235.94    4611   236.7  4620.5  235.75  4640.7  236.91  4751.3  236.38
  4791.1  236.96  4981.3  236.82  4990.8  234.02  5004.2  234.87  5013.5  236.68
  5033.5  238.14  5083.6   238.4    5234   242.9  5424.4   250.4  5454.5  250.92
  5494.5  249.68  5524.6  253.71  5534.6  256.09  5554.7  258.02  5560.6  258.27
  5574.7  255.97  5624.8  255.49  5644.9  257.59    5705  260.23  5785.2  265.51
#Mann= 3 , 0 , 0
  3896.5     .11       0  4981.3     .06       0  5013.5     .11       0
Bank Sta=4981.3,5013.5
XS Rating Curve= 0 ,0
Exp/Cntr=0.3,0.1

Type RM Length L Ch R = 1 ,2514    ,516,516,516
BEGIN DESCRIPTION:
CCLC 028 4.0
END DESCRIPTION:
XS GIS Cut Line= 3
      3720167.85     10118711.07      3720381.33     10117487.05
      3720017.83     10116861.03
#Sta/Elev= 30
  3757.5  259.02    3991  253.46  4017.9   253.8  4041.7   253.1  4072.2  251.62
  4077.4   250.6  4163.5  247.14  4376.7   239.2  4484.2  236.13  4549.3  235.27
  4620.3  235.89  4681.2  235.06    4732  235.77    4803  234.47  4975.6  235.19
  4985.8  234.98 4988.21233.6322  4993.6  230.23    5000  230.73  5006.9  233.61
  5020.6  235.26    5052  234.57  5110.8  234.88  5196.9  239.65  5351.7  239.07
  5490.8  243.37  5635.7  248.97  5700.7  249.89  5722.4  251.46  5723.9  251.46
#Mann= 4 ,-1 , 0
  3757.5     .11       0 4988.21     .06       0  5006.9     .11       0
  5722.4     .17       0
Bank Sta=4988.21,5006.9
XS Rating Curve= 0 ,0
Exp/Cntr=0.3,0.1

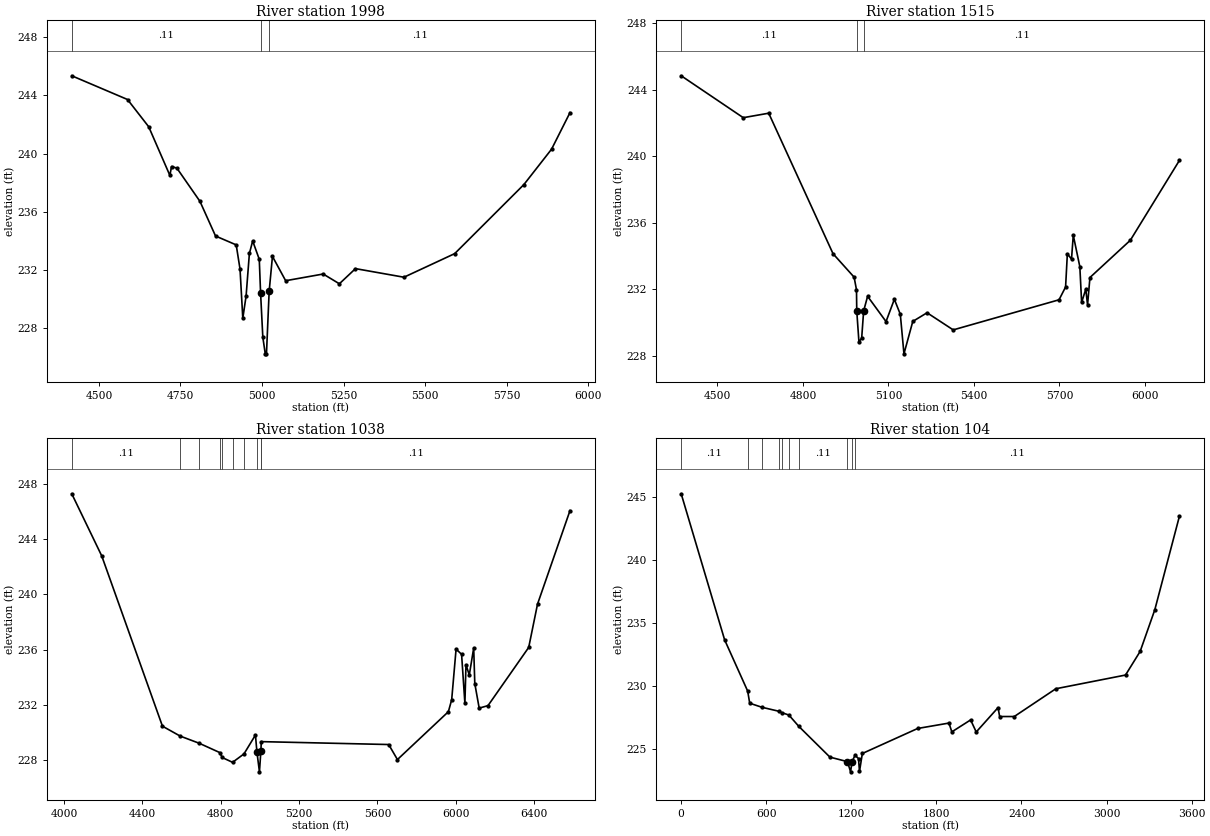
Type RM Length L Ch R = 1 ,1998    ,483,483,483
BEGIN DESCRIPTION:
CCLC 028 3.0
END DESCRIPTION:
XS GIS Cut Line= 3
      3720678.84     10118149.96      3720783.01     10117436.38
      3720217.85     10116861.07
#Sta/Elev= 30
  4416.8  245.34  4587.8  243.71  4652.7  241.84  4717.6   238.5  4722.7  239.11
  4739.1     239  4809.8  236.72  4857.6  234.34    4921  233.73  4932.7  232.07
  4941.2  228.69  4951.3  230.22  4961.4  233.14  4971.5     234  4991.7  232.74
 4995.76230.4143  5002.6  227.39  5010.1  226.25  5013.8  226.25    5022  230.53
  5032.1  232.94  5072.6  231.27  5187.7  231.73  5237.3  231.06  5286.7   232.1
  5435.3  231.51  5590.9  233.13    5803  237.87  5887.9   240.3  5944.4  242.81
#Mann= 3 ,-1 , 0
  4416.8     .11       0 4995.76     .07       0    5022     .11       0
Bank Sta=4995.76,5022
XS Rating Curve= 0 ,0
Exp/Cntr=0.3,0.1

Type RM Length L Ch R = 1 ,1515    ,477,477,477
BEGIN DESCRIPTION:
CCLC 028 2.0
END DESCRIPTION:
XS GIS Cut Line= 3
      3721022.59      10118139.5      3721168.31     10117529.26
      3720267.85     10116861.07
#Sta/Elev= 30
  4372.6  244.83  4590.5  242.31  4679.8  242.58  4905.6  234.13  4979.6  232.72
  4987.9  231.96 4988.82  230.69  4996.5  228.83  5006.1  229.05    5013  230.69
  5026.9  231.57  5091.6  230.05  5120.8  231.39  5141.7  230.49  5154.5  228.11
  5185.5  230.06  5235.6  230.58  5327.4  229.55  5698.8  231.36  5721.8  232.13
    5728  234.12  5742.6  233.81  5748.8  235.24  5771.8  233.35  5778.1   231.2
  5792.7     232  5798.9  231.05  5807.3   232.7  5949.1  234.94  6121.3  239.74
#Mann= 3 , 0 , 0
  4372.6     .11       0 4988.82     .06       0    5013     .11       0
Bank Sta=4988.82,5013
XS Rating Curve= 0 ,0
Exp/Cntr=0.3,0.1

Type RM Length L Ch R = 1 ,1038    ,934,934,934
BEGIN DESCRIPTION:
CCLC 028 1.0
END DESCRIPTION:
XS GIS Cut Line= 3
      3721417.84     10118211.09      3721736.13     10117483.26
      3720167.82     10116711.06
#Sta/Elev= 30
    4040   247.3  4192.8   242.8  4502.8  230.45  4593.6  229.73  4690.8  229.21
  4796.3  228.53  4807.3  228.18  4860.6  227.83  4918.8  228.44  4977.4  229.81
  4984.7   228.6  4997.8  227.14 5004.95228.6259  5007.2  229.33  5657.3  229.12
  5701.9  228.03  5961.9   231.5  5978.8  232.37  6001.2  236.04  6029.3  235.66
  6046.2  232.11  6051.7  234.91  6068.6  234.16  6091.1  236.12  6096.7  233.54
  6119.1  231.76  6164.1  231.94  6371.8  236.16  6416.8   239.3  6582.5  246.08
#Mann= 10 ,-1 , 0
    4040     .11       0  4593.6     .15       0  4690.8     .11       0
  4796.3     .15       0  4807.3     .11       0  4860.6     .15       0
  4918.8     .11       0  4984.7     .06       0 5004.95     .09       0
  5007.2     .11       0
Bank Sta=4984.7,5004.95
XS Rating Curve= 0 ,0
Exp/Cntr=0.3,0.1

Type RM Length L Ch R = 1 ,104     ,0,0,0
BEGIN DESCRIPTION:
CCLC 028 1.0
END DESCRIPTION:
XS GIS Cut Line= 4
      3721524.14     10118230.26      3722296.56     10117396.43
      3722186.68     10117047.38      3720211.98     10116662.78
#Sta/Elev= 30
       0  245.27   306.4  233.65   469.1  229.57   483.3  228.61   568.3  228.29
   688.5  227.97   709.5  227.86   759.4  227.67   830.2  226.76  1049.1  224.32
 1172.84  223.96  1194.7  223.15  1205.1  223.97  1226.1  224.46  1250.6  224.21
  1257.6  223.18  1277.7  224.61  1667.9   226.6  1888.5  227.03  1908.9  226.33
  2041.3  227.28  2080.9  226.32  2234.9  228.26    2246  227.55  2349.2  227.55
  2642.4  229.76  3133.8  230.85    3237  232.73  3340.3  236.04  3513.9  243.48
#Mann= 10 ,-1 , 0
       0     .11       0   469.1     .15       0   568.3     .11       0
   688.5     .15       0   709.5     .11       0   759.4     .15       0
   830.2     .11       0 1172.84     .06       0  1205.1     .09       0
  1226.1     .11       0
Bank Sta=1172.84,1205.1
XS Rating Curve= 0 ,0
Exp/Cntr=0.3,0.1

Chan Stop Cuts=-1
Use User Specified Reach Order=0
Composite Channel Slope=5