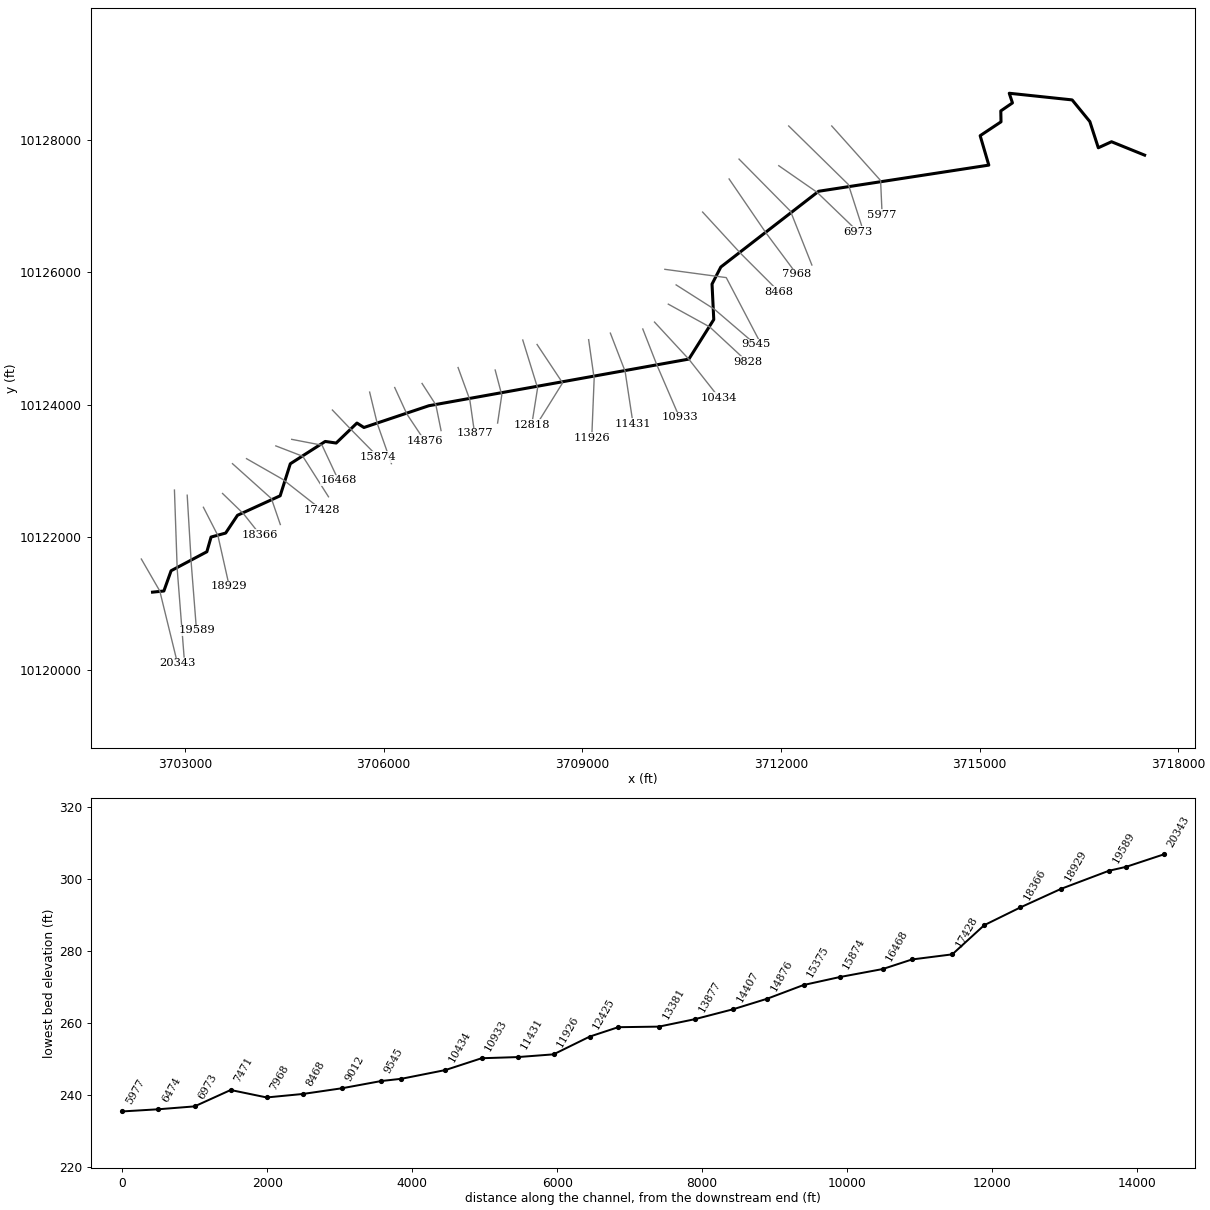
--- CCLC 030.prj (project) ---

Proj Title=CCLC 030 Base Level Engineering
Current Plan=p01
Default Exp/Contr=0.3,0.1
English Units
Geom File=g01
Flow File=f01
Flow File=f02
Plan File=p01
Y Axis Title=Elevation
X Axis Title(PF)=Main Channel Distance
X Axis Title(XS)=Station
BEGIN DESCRIPTION:
CCLC 030
END DESCRIPTION:
DSS Export Rating Curves= 0
DSS Export Rating Curve Sorted= 0
DSS Export Volume Flow Curves= 0
DXF OffsetX= 0
DXF OffsetY= 0
DXF ScaleX= 1
DXF ScaleY= 10

--- CCLC 030.p01 (plan) ---

Plan Title=Multiple Run
Short Identifier=Multiple
Geom File=g01
Flow File=f01
Subcritical Flow
K Sum by GR= 0
Std Step Tol= 0.01
Critical Tol= 0.01
Num of Std Step Trials= 20
Max Error Tol= 0.3
Flow Tol Ratio= 0.001
Split Flow NTrial= 30
Split Flow Tol= 0.02
Split Flow Ratio= 0.02
Log Output Level= 0
Friction Slope Method= 1
Unsteady Friction Slope Method= 2
Unsteady Bridges Friction Slope Method= 1
Parabolic Critical Depth
Global Vel Dist=  1 , 1 , 1
Global Log Level= 0
CheckData=True
Encroach Param= -1, 0, 0, 0
BEGIN DESCRIPTION:
Multiple Run
END DESCRIPTION:

--- CCLC 030.f01 (steady flow) ---

Flow Title=Multiple
Program Version=4.10
Number of Profiles= 7
Profile Names=10-year,25-year,50-year,1pct_min,100-year,1pct_plu,500-year
River Rch & RM=CCLC 030,Reach-1         ,20343
     959    1344    1860     846    2555    7716    4990
River Rch & RM=CCLC 030,Reach-1         ,15874
    1312    1859    2591    1185    3579   10808    7069
River Rch & RM=CCLC 030,Reach-1         ,10933
    1561    2223    3104    1422    4294   12968    8509
River Rch & RM=CCLC 030,Reach-1         ,3498
    1799    2569    3596    1649    4980   15039    9899
Boundary for River Rch & Prof#=CCLC 030,Reach-1         , 1
Up Type= 0
Dn Type= 3
Dn Slope=0.005
Boundary for River Rch & Prof#=CCLC 030,Reach-1         , 2
Up Type= 0
Dn Type= 3
Dn Slope=0.005
Boundary for River Rch & Prof#=CCLC 030,Reach-1         , 3
Up Type= 0
Dn Type= 3
Dn Slope=0.005
Boundary for River Rch & Prof#=CCLC 030,Reach-1         , 4
Up Type= 0
Dn Type= 3
Dn Slope=0.005
Boundary for River Rch & Prof#=CCLC 030,Reach-1         , 5
Up Type= 0
Dn Type= 3
Dn Slope=0.005
Boundary for River Rch & Prof#=CCLC 030,Reach-1         , 6
Up Type= 0
Dn Type= 3
Dn Slope=0.005
Boundary for River Rch & Prof#=CCLC 030,Reach-1         , 7
Up Type= 0
Dn Type= 3
Dn Slope=0.005
DSS Import GetInterval= 0
DSS Import GetPeak= 0
DSS Import FillOption= 0

--- CCLC 030.f02 (steady flow) ---

Flow Title=Orig_BLE_Flows
Program Version=4.10
Number of Profiles= 7
Profile Names=10-year,25-year,50-year,1pct_min,100-year,1pct_plu,500-year
River Rch & RM=CCLC 030,Reach-1         ,20343
     959    1318    1617     651    1965    5935    2901
River Rch & RM=CCLC 030,Reach-1         ,15874
    1312    1823    2253     912    2753    8315    4110
River Rch & RM=CCLC 030,Reach-1         ,10933
    1561    2179    2699    1094    3303    9974    4947
River Rch & RM=CCLC 030,Reach-1         ,3498
    1799    2519    3127    1269    3831   11571    5755
Boundary for River Rch & Prof#=CCLC 030,Reach-1         , 1
Up Type= 0
Dn Type= 3
Dn Slope=0.005
Boundary for River Rch & Prof#=CCLC 030,Reach-1         , 2
Up Type= 0
Dn Type= 3
Dn Slope=0.005
Boundary for River Rch & Prof#=CCLC 030,Reach-1         , 3
Up Type= 0
Dn Type= 3
Dn Slope=0.005
Boundary for River Rch & Prof#=CCLC 030,Reach-1         , 4
Up Type= 0
Dn Type= 3
Dn Slope=0.005
Boundary for River Rch & Prof#=CCLC 030,Reach-1         , 5
Up Type= 0
Dn Type= 3
Dn Slope=0.005
Boundary for River Rch & Prof#=CCLC 030,Reach-1         , 6
Up Type= 0
Dn Type= 3
Dn Slope=0.005
Boundary for River Rch & Prof#=CCLC 030,Reach-1         , 7
Up Type= 0
Dn Type= 3
Dn Slope=0.005
DSS Import GetInterval= 0
DSS Import GetPeak= 0
DSS Import FillOption= 0

--- CCLC 030.g01 (geometry) ---

Geom Title=Existing Conditions
Program Version=4.10

River Reach=CCLC 030        ,Reach-1
Reach XY= 30
      3702510.43     10121170.81       3702681.7     10121188.16
      3702791.09      10121494.3      3703330.94     10121781.08
      3703394.56     10122003.09      3703614.55     10122063.14
      3703793.57     10122331.68      3704437.91     10122625.98
      3704591.08     10123109.63      3705118.23     10123446.84
      3705283.95     10123422.77      3705597.47     10123724.46
      3705703.01      10123657.5      3706682.49     10123985.88
       3710610.5     10124690.63      3710986.22     10125287.67
       3710960.1     10125823.55      3711092.81     10126080.93
      3712569.93     10127225.07      3715139.87     10127619.89
      3715009.38     10128064.39      3715324.13     10128273.73
      3715321.11     10128438.38      3715497.01      10128559.4
      3715448.62     10128705.17      3716398.37     10128604.74
      3716665.65     10128277.61      3716793.56     10127881.79
      3716993.26     10127972.92      3717492.97     10127770.57

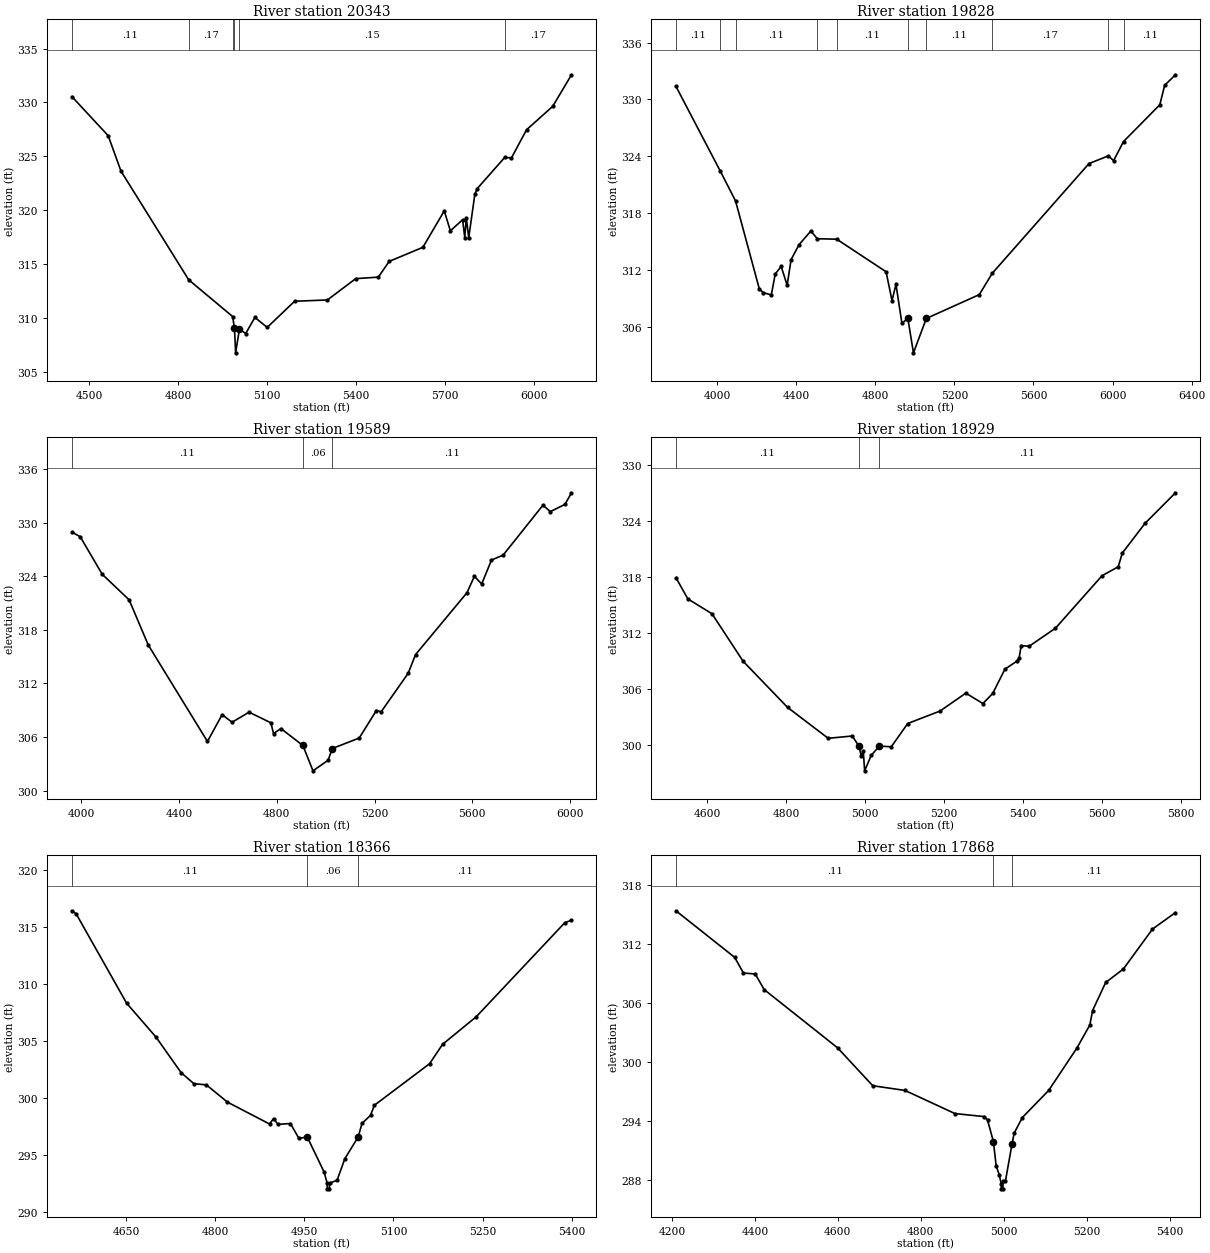
Type RM Length L Ch R = 1 ,20343   ,515,515,515
BEGIN DESCRIPTION:
CCLC 030 33.0
END DESCRIPTION:
XS GIS Cut Line= 3
      3702341.34     10121671.23      3702620.24     10121187.81
      3702887.85     10120094.59
#Sta/Elev= 30
  4441.9  330.53  4564.1   326.9  4607.2  323.61  4835.4  313.52  4983.5  310.11
 4989.71309.0044  4993.5  306.74  5006.4  308.95  5027.5  308.53  5058.4  310.03
  5099.9   309.1  5192.3  311.53  5302.9  311.65  5398.2  313.63  5474.5  313.77
    5511  315.23  5624.7  316.54  5696.7  319.92  5717.3  318.07  5758.5   319.1
  5765.8  317.45    5771  319.28  5779.1  317.42  5799.7  321.45  5807.4  321.98
  5900.3  324.88  5923.2  324.84  5973.9  327.45  6062.3  329.63  6125.5  332.56
#Mann= 6 ,-1 , 0
  4441.9     .11       0  4835.4     .17       0  4983.5     .15       0
 4989.71     .09       0  5006.4     .15       0  5900.3     .17       0
Bank Sta=4989.71,5006.4
XS Rating Curve= 0 ,0
Exp/Cntr=0.3,0.1

Type RM Length L Ch R = 1 ,19828   ,239,239,239
BEGIN DESCRIPTION:
CCLC 030 32.0
END DESCRIPTION:
XS GIS Cut Line= 3
      3702841.35     10122712.88      3702883.01     10121520.18
      3702987.18     10120192.09
#Sta/Elev= 30
  3792.3  331.38  4015.9  322.48  4093.7  319.31  4214.4     310  4234.4  309.65
  4274.4  309.41  4294.4  311.62  4324.4  312.41  4354.5  310.43  4374.5  313.13
  4414.5   314.7  4474.5  316.14  4507.1  315.33  4605.4  315.28  4854.8  311.85
  4884.8  308.81  4904.8  310.53  4934.8  306.41  4964.8  306.95  4993.1  303.31
 5058.37306.9337  5325.9  309.44  5391.6  311.69  5880.8  323.25  5979.2  324.06
  6004.9  323.55  6055.3  325.57  6238.7  329.44  6263.2  331.49  6317.9   332.6
#Mann= 10 ,-1 , 0
  3792.3     .11       0  4015.9     .17       0  4093.7     .11       0
  4507.1     .17       0  4605.4     .11       0  4964.8     .06       0
 5058.37     .11       0  5391.6     .17       0  5979.2     .15       0
  6055.3     .11       0
Bank Sta=4964.8,5058.37
XS Rating Curve= 0 ,0
Exp/Cntr=0.3,0.1

Type RM Length L Ch R = 1 ,19589   ,660,660,660
BEGIN DESCRIPTION:
CCLC 030 31.0
END DESCRIPTION:
XS GIS Cut Line= 3
      3703034.05      10122634.8      3703096.55     10121587.88
      3703174.56     10120594.62
#Sta/Elev= 30
  3961.2  328.94    3995  328.43  4085.2  324.22  4195.3  321.36  4273.6   316.3
  4515.9   305.5    4576   308.5  4616.7  307.65  4686.2  308.78  4775.7  307.59
  4786.4  306.38  4816.5  306.95  4906.6  305.05    4948  302.21    5010   303.4
  5026.8  304.71  5137.2  305.88  5207.4  308.96  5227.5  308.84  5337.8  313.14
  5367.9  315.23  5578.5  322.16  5608.6  323.99  5638.7  323.14  5678.8  325.82
  5726.5  326.37  5889.5  331.96  5919.6  331.24  5979.6  332.05  6006.3  333.35
#Mann= 3 , 0 , 0
  3961.2     .11       0  4906.6     .06       0  5026.8     .11       0
Bank Sta=4906.6,5026.8
XS Rating Curve= 0 ,0
Exp/Cntr=0.3,0.1

Type RM Length L Ch R = 1 ,18929   ,563,563,563
BEGIN DESCRIPTION:
CCLC 030 30.0
END DESCRIPTION:
XS GIS Cut Line= 3
      3703278.83     10122452.49       3703497.6     10122025.38
      3703669.48     10121259.71
#Sta/Elev= 30
  4521.6  317.92  4551.8  315.64  4612.8  314.05  4691.7  308.95  4804.1     304
  4907.1  300.68  4968.1  300.93 4985.14299.8202  4990.3  298.82  4995.9  299.29
  4999.3  297.19  5016.1  298.86  5036.6  299.85  5066.7  299.77  5108.4  302.27
  5190.4  303.61  5255.4  305.53  5298.7  304.41  5323.6   305.5  5354.4   308.1
  5385.1  308.97  5390.5  309.34  5395.6  310.63  5415.8  310.56  5482.2  312.49
  5600.3  318.13  5641.3  319.09  5651.6  320.56  5709.1  323.75  5786.2  327.03
#Mann= 3 , 0 , 0
  4521.6     .11       0 4985.14     .06       0  5036.6     .11       0
Bank Sta=4985.14,5036.6
XS Rating Curve= 0 ,0
Exp/Cntr=0.3,0.1

Type RM Length L Ch R = 1 ,18366   ,498,498,498
BEGIN DESCRIPTION:
CCLC 030 29.0
END DESCRIPTION:
XS GIS Cut Line= 3
      3703567.84     10122661.08       3703884.6     10122354.25
      3704132.96     10122041.07
#Sta/Elev= 30
    4559  316.42  4566.1  316.15    4651  308.31  4700.4  305.34  4742.8  302.21
  4764.2  301.25  4785.3  301.14  4820.7  299.63  4891.5  297.71  4898.4  298.19
  4905.6  297.68  4926.7  297.75  4940.9  296.45    4955  296.57  4983.3   293.5
  4988.5  292.52  4988.8  292.02  4992.3  292.02  4992.5  292.52  5005.2  292.77
  5018.2  294.66  5040.7  296.57  5047.1  297.76  5061.5  298.47  5067.9  299.35
  5160.9     303  5182.7   304.7  5239.4  307.12  5388.4  315.37  5399.7  315.59
#Mann= 3 , 0 , 0
    4559     .11       0    4955     .06       0  5040.7     .11       0
Bank Sta=4955,5040.7
XS Rating Curve= 0 ,0
Exp/Cntr=0.3,0.1

Type RM Length L Ch R = 1 ,17868   ,440,440,440
BEGIN DESCRIPTION:
CCLC 030 28.0
END DESCRIPTION:
XS GIS Cut Line= 3
      3703717.85     10123111.07      3704305.95     10122583.44
       3704440.3     10122192.06
#Sta/Elev= 30
  4209.9  315.35  4351.6  310.61  4372.5  309.02  4400.9  308.93  4422.6  307.34
  4599.5  301.42  4684.2  297.57    4762  297.09  4882.3  294.74  4953.3  294.43
  4960.8  294.09    4975   291.9  4981.7   289.4  4989.1  288.52  4993.9  287.59
  4994.2  287.09  4997.7  287.09    4998  287.86  5003.9  287.86  5019.8  291.63
  5025.1  292.76  5044.8  294.34  5108.2  297.09  5176.1  301.39  5207.4  303.74
    5214  305.21  5245.7  308.07    5288  309.42  5358.4  313.49  5413.8  315.17
#Mann= 3 , 0 , 0
  4209.9     .11       0    4975     .06       0  5019.8     .11       0
Bank Sta=4975,5019.8
XS Rating Curve= 0 ,0
Exp/Cntr=0.3,0.1

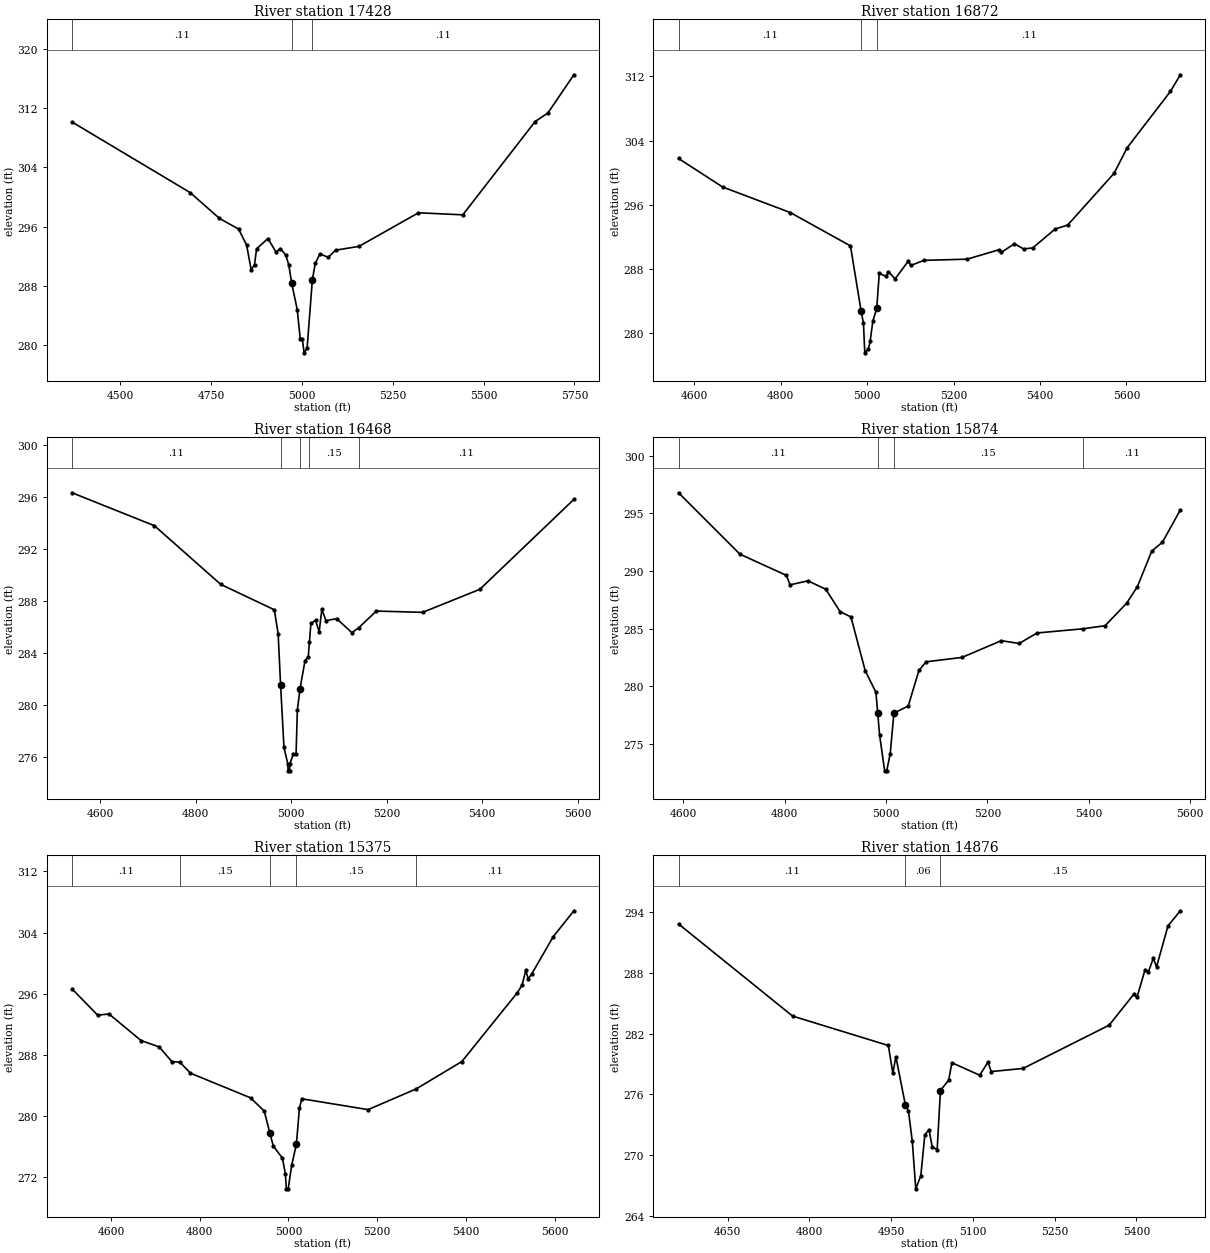
Type RM Length L Ch R = 1 ,17428   ,556,556,556
BEGIN DESCRIPTION:
CCLC 030 27.0
END DESCRIPTION:
XS GIS Cut Line= 3
      3703929.88     10123186.85      3704476.76     10122874.34
      3705067.87     10122411.06
#Sta/Elev= 30
  4367.4  310.11  4692.4   300.6    4773  297.12  4825.8  295.68  4847.9   293.5
  4860.3  290.17  4869.5   290.9  4875.2  293.02  4906.4  294.41  4928.5  292.59
  4940.9  293.05  4955.8  292.15    4964  290.81  4971.7   288.4    4987  284.84
  4995.5  280.81  5001.1  280.81  5006.1     279  5014.2  279.61  5028.7  288.87
  5036.8  291.08  5049.5  292.35    5072  291.87  5092.8  292.84    5157  293.35
  5320.7  297.88  5442.7   297.6  5641.6  310.17  5676.9  311.33  5748.3  316.48
#Mann= 3 , 0 , 0
  4367.4     .11       0  4971.7     .06       0  5028.7     .11       0
Bank Sta=4971.7,5028.7
XS Rating Curve= 0 ,0
Exp/Cntr=0.3,0.1

Type RM Length L Ch R = 1 ,16872   ,404,404,404
BEGIN DESCRIPTION:
CCLC 030 26.0
END DESCRIPTION:
XS GIS Cut Line= 3
      3704372.63     10123379.54       3704779.3     10123222.59
      3705167.84     10122611.09
#Sta/Elev= 30
  4564.1  301.77  4666.2  298.22  4822.6  295.04  4961.7  290.89  4986.3  282.78
  4991.7  281.27  4994.8  277.58  5003.3  278.08  5007.2  279.01  5013.6  281.57
  5022.4  283.11  5028.3  287.47  5043.6   287.1  5049.5  287.69  5064.8  286.78
  5095.3  288.99  5101.2  288.46  5131.7  289.09  5231.6  289.24  5304.4   290.4
  5310.4  290.08  5340.9  291.16    5362  290.51  5383.2  290.64  5434.9  292.99
  5463.9  293.48  5571.2  299.92  5601.7  303.12  5701.6  310.12  5724.5  312.19
#Mann= 3 , 0 , 0
  4564.1     .11       0  4986.3     .06       0  5022.4     .11       0
Bank Sta=4986.3,5022.4
XS Rating Curve= 0 ,0
Exp/Cntr=0.3,0.1

Type RM Length L Ch R = 1 ,16468   ,594,594,594
BEGIN DESCRIPTION:
CCLC 030 25.0
END DESCRIPTION:
XS GIS Cut Line= 3
      3704612.17     10123478.51      3705070.51     10123389.97
      3705317.86     10122861.06
#Sta/Elev= 30
  4541.2  296.29  4713.6  293.76  4852.5  289.25  4964.6   287.3  4972.7  285.47
  4977.8  281.53  4984.9  276.72  4993.1  275.42  4993.4  274.92  4996.9  274.92
  4997.1  275.42  5004.1  276.18  5010.2  276.18  5012.9  279.57  5018.4  281.21
  5028.9  283.37  5035.8   283.7  5038.2  284.81  5041.3  286.25    5051  286.49
  5058.6   285.6  5064.1  287.32    5073  286.46  5095.1  286.62  5127.1  285.54
  5141.2  285.91  5178.3   287.2  5275.2   287.1    5395  288.87  5591.9  295.78
#Mann= 5 ,-1 , 0
  4541.2     .11       0  4977.8     .07       0  5018.4     .11       0
  5038.2     .15       0  5141.2     .11       0
Bank Sta=4977.8,5018.4
XS Rating Curve= 0 ,0
Exp/Cntr=0.3,0.1

Type RM Length L Ch R = 1 ,15874   ,499,499,499
BEGIN DESCRIPTION:
CCLC 030 24.0
END DESCRIPTION:
XS GIS Cut Line= 3
      3705226.76     10123921.22      3705509.93       10123625.
      3705917.82      10123211.1
#Sta/Elev= 30
  4590.2  296.79  4711.4  291.47  4803.2  289.63  4810.5  288.81  4845.7  289.16
  4880.9  288.43  4909.2  286.49  4930.6  286.03  4958.9  281.36    4980   279.5
 4983.58277.6653  4987.2  275.81  4997.2  272.69  5001.3  272.69  5008.3  274.19
  5015.5  277.69  5043.8  278.31  5064.9  281.39  5079.1  282.14  5149.8  282.52
  5227.6  283.97  5262.9  283.73  5298.3  284.64  5388.4     285  5432.6  285.27
  5475.1  287.22  5496.3  288.65  5524.6  291.73  5545.8  292.51  5581.1   295.3
#Mann= 4 ,-1 , 0
  4590.2     .11       0 4983.58     .09       0  5015.5     .15       0
  5388.4     .11       0
Bank Sta=4983.58,5015.5
XS Rating Curve= 0 ,0
Exp/Cntr=0.3,0.1

Type RM Length L Ch R = 1 ,15375   ,499,499,499
BEGIN DESCRIPTION:
CCLC 030 23.0
END DESCRIPTION:
XS GIS Cut Line= 3
      3705789.25     10124192.09      3705904.11     10123717.91
      3706117.86     10123111.05
#Sta/Elev= 30
  4512.1  296.62  4569.8   293.2  4595.5  293.35  4667.5  289.88  4708.6  289.04
  4737.1  287.12  4755.3  287.04  4778.9  285.61  4914.6  282.38  4945.3  280.66
    4958  277.78  4965.9  276.07  4986.5  274.48  4993.1  272.38  4995.2  270.48
  4999.4  270.48  5007.2  273.55  5017.8  276.31  5024.7  281.02    5030  282.26
  5179.5  280.84  5288.2  283.56  5390.9  287.13  5516.2  296.15  5526.8  297.15
    5535  299.08  5540.3  297.95    5548  298.55  5596.9  303.46  5643.4  306.85
#Mann= 5 ,-1 , 0
  4512.1     .11       0  4755.3     .15       0    4958     .09       0
  5017.8     .15       0  5288.2     .11       0
Bank Sta=4958,5017.8
XS Rating Curve= 0 ,0
Exp/Cntr=0.3,0.1

Type RM Length L Ch R = 1 ,14876   ,469,469,469
BEGIN DESCRIPTION:
CCLC 030 22.0
END DESCRIPTION:
XS GIS Cut Line= 3
      3706167.85     10124261.08      3706351.25      10123860.8
      3706617.86     10123461.05
#Sta/Elev= 30
  4559.7   292.8    4769  283.72  4944.7  280.82    4953  278.08  4958.5  279.72
    4976  274.94  4981.5  274.41  4988.7  271.36    4995  266.69  5004.3  267.99
  5011.7  272.02  5019.3  272.52  5025.3  270.81  5034.3  270.56  5040.3  276.38
  5055.4  277.41  5061.4  279.12  5112.4  277.89  5127.5  279.18  5133.5  278.25
    5192  278.56  5349.8  282.82  5394.9  285.86  5400.9  285.56  5415.9  288.31
  5421.9  288.07  5430.9  289.42  5436.9  288.58  5457.9  292.62  5480.5   294.1
#Mann= 3 , 0 , 0
  4559.7     .11       0    4976     .06       0  5040.3     .15       0
Bank Sta=4976,5040.3
XS Rating Curve= 0 ,0
Exp/Cntr=0.3,0.1

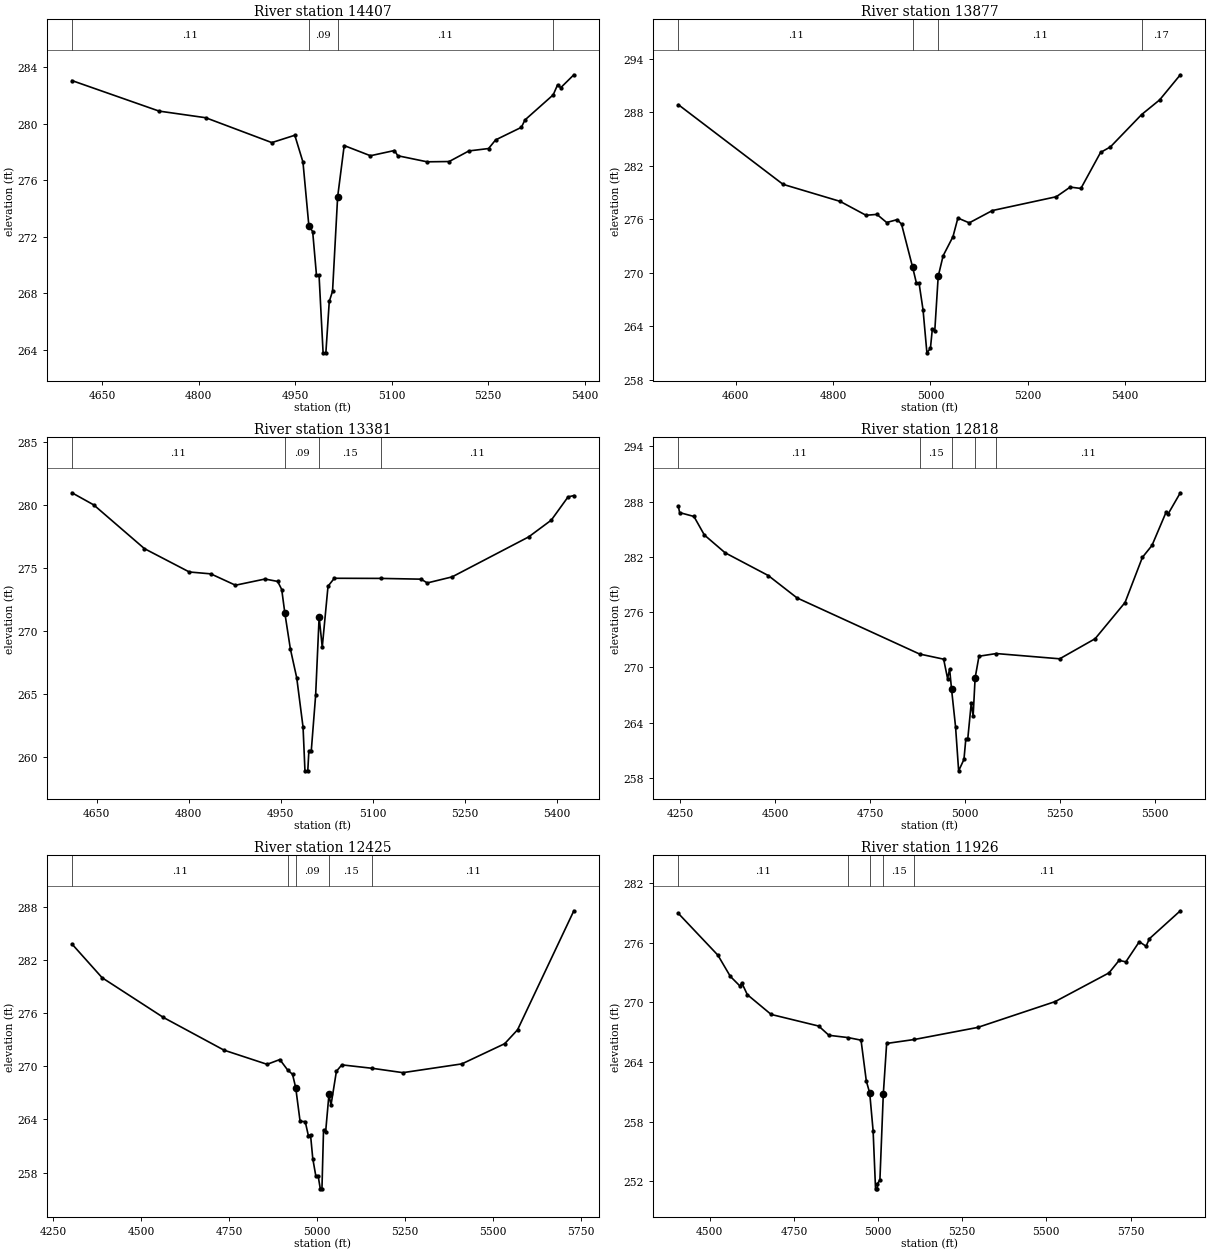
Type RM Length L Ch R = 1 ,14407   ,530,530,530
BEGIN DESCRIPTION:
CCLC 030 21.0
END DESCRIPTION:
XS GIS Cut Line= 3
      3706580.95     10124322.23      3706789.26     10123999.34
      3706867.85     10123611.07
#Sta/Elev= 30
  4602.9  283.04  4738.3  280.88  4810.9  280.41  4913.7  278.65  4949.4  279.17
  4962.1  277.27  4971.3  272.75  4977.2  272.35  4983.1  269.27  4987.1  269.27
  4993.4  263.77  4997.7  263.77    5003  267.41  5008.1  268.13    5016   274.8
  5026.2  278.44    5067  277.72  5104.4  278.09  5109.5  277.72  5155.1  277.29
  5189.4  277.31  5220.1  278.06  5250.7  278.23  5261.6  278.84  5301.7  279.73
  5307.2  280.25  5351.2  282.03  5357.9  282.73    5363  282.54  5383.3  283.45
#Mann= 4 ,-1 , 0
  4602.9     .11       0  4971.3     .09       0    5016     .11       0
  5351.2     .17       0
Bank Sta=4971.3,5016
XS Rating Curve= 0 ,0
Exp/Cntr=0.3,0.1

Type RM Length L Ch R = 1 ,13877   ,496,496,496
BEGIN DESCRIPTION:
CCLC 030 20.0
END DESCRIPTION:
XS GIS Cut Line= 3
      3707124.76     10124562.93      3707301.88      10124076.9
      3707374.31     10123569.04
#Sta/Elev= 30
  4482.7  288.83  4697.5   279.9  4814.6  277.99  4867.8  276.43  4890.2  276.53
  4910.2  275.62  4931.7  275.94  4940.7  275.44  4963.6  270.58  4971.3  268.81
  4976.6  268.85  4984.9  265.81  4992.8     261    5000   261.5  5003.9  263.65
  5008.9  263.42    5016  269.58  5026.1  271.89  5046.3  274.03  5056.4  276.12
  5079.7  275.58  5127.1  276.96  5258.4  278.51  5286.9  279.59  5308.9  279.44
  5349.3  283.48  5369.5   284.1  5433.6  287.73  5470.5  289.37    5513  292.19
#Mann= 4 ,-1 , 0
  4482.7     .11       0  4963.6     .07       0    5016     .11       0
  5433.6     .17       0
Bank Sta=4963.6,5016
XS Rating Curve= 0 ,0
Exp/Cntr=0.3,0.1

Type RM Length L Ch R = 1 ,13381   ,563,563,563
BEGIN DESCRIPTION:
CCLC 030 19.0
END DESCRIPTION:
XS GIS Cut Line= 3
       3707685.1     10124525.36      3707784.84     10124148.12
      3707721.76     10123724.69
#Sta/Elev= 30
  4609.8  280.98  4645.3  280.02    4728  276.55  4801.1   274.7  4836.2  274.55
  4876.4  273.65  4924.5  274.14  4945.2  273.95  4951.8  273.31  4956.9  271.44
  4965.9   268.6  4976.3   266.3  4986.6  262.39  4989.7  258.93  4994.3  258.93
  4996.1  260.52    5000  260.52  5007.1  264.92  5012.8  271.13  5017.9  268.74
  5027.3  273.57  5037.5   274.2  5113.1  274.19    5179  274.13  5189.1  273.83
  5229.6  274.31  5354.4  277.48  5391.3  278.81  5418.6  280.65  5428.1  280.76
#Mann= 4 ,-1 , 0
  4609.8     .11       0  4956.9     .09       0  5012.8     .15       0
  5113.1     .11       0
Bank Sta=4956.9,5012.8
XS Rating Curve= 0 ,0
Exp/Cntr=0.3,0.1

Type RM Length L Ch R = 1 ,12818   ,393,393,393
BEGIN DESCRIPTION:
CCLC 030 18.0
END DESCRIPTION:
XS GIS Cut Line= 3
      3708101.78     10124978.47      3708325.72     10124254.55
      3708237.19     10123697.31
#Sta/Elev= 30
  4244.8  287.48  4247.9   286.8  4285.7  286.38  4313.1  284.37  4367.7  282.44
  4481.4  279.97  4557.2  277.54  4879.9  271.45  4943.4  270.89  4953.8  268.78
  4959.1  269.82  4964.3   267.6  4974.8  263.54  4982.9  258.77  4996.9  260.01
  5001.8  262.22  5006.9  262.22    5016  266.08  5021.1  264.73  5026.3  268.85
  5036.5  271.21  5082.1   271.5  5249.1  270.93  5342.4  273.11  5421.2  277.04
  5466.9  281.94  5492.1  283.23  5529.1  286.82  5534.2  286.62  5566.8  288.95
#Mann= 5 ,-1 , 0
  4244.8     .11       0  4879.9     .15       0  4964.3     .09       0
  5026.3     .15       0  5082.1     .11       0
Bank Sta=4964.3,5026.3
XS Rating Curve= 0 ,0
Exp/Cntr=0.3,0.1

Type RM Length L Ch R = 1 ,12425   ,499,499,499
BEGIN DESCRIPTION:
CCLC 030 17.0
END DESCRIPTION:
XS GIS Cut Line= 3
      3708317.84     10124911.08      3708703.22     10124331.15
      3708317.84     10123711.05
#Sta/Elev= 30
  4303.7  283.81  4389.4     280  4563.8  275.51  4735.9  271.82  4858.4  270.22
  4894.5  270.76  4916.3   269.6  4930.6  269.09  4939.6  267.59  4952.1  263.77
  4966.6  263.76  4975.7  262.15  4981.7  262.28  4988.1  259.58  4996.7  257.63
  5003.3  257.63  5009.5  256.16  5014.2  256.16  5018.7  262.83  5024.6  262.56
  5034.1  266.82  5039.9  265.61  5055.3  269.44  5070.7  270.16  5157.5  269.77
  5244.2  269.28  5411.9  270.27  5533.5  272.55  5570.1  274.12  5730.1  287.56
#Mann= 5 ,-1 , 0
  4303.7     .11       0  4916.3     .15       0  4939.6     .09       0
  5034.1     .15       0  5157.5     .11       0
Bank Sta=4939.6,5034.1
XS Rating Curve= 0 ,0
Exp/Cntr=0.3,0.1

Type RM Length L Ch R = 1 ,11926   ,495,495,495
BEGIN DESCRIPTION:
CCLC 030 16.0
END DESCRIPTION:
XS GIS Cut Line= 3
      3709096.55     10124983.72      3709180.04     10124396.63
      3709143.43     10123499.38
#Sta/Elev= 30
    4407  278.94  4524.3  274.74  4561.2  272.61  4590.1  271.63  4595.2  271.96
  4611.7  270.77  4682.4  268.78  4823.8  267.61  4854.1  266.68    4911  266.45
  4949.5  266.19  4965.2  262.08  4975.3  260.87  4985.4  257.06  4992.6  251.23
  4997.8  251.23  4998.3  251.73  5005.6  252.14  5015.6  260.73  5025.6  265.86
  5108.2  266.26  5295.8  267.47    5526  270.07  5686.1  272.96  5716.2  274.22
  5736.2  274.07  5776.2   276.1  5796.2  275.64  5806.2   276.4    5898  279.21
#Mann= 5 ,-1 , 0
    4407     .11       0    4911     .15       0  4975.3     .09       0
  5015.6     .15       0  5108.2     .11       0
Bank Sta=4975.3,5015.6
XS Rating Curve= 0 ,0
Exp/Cntr=0.3,0.1

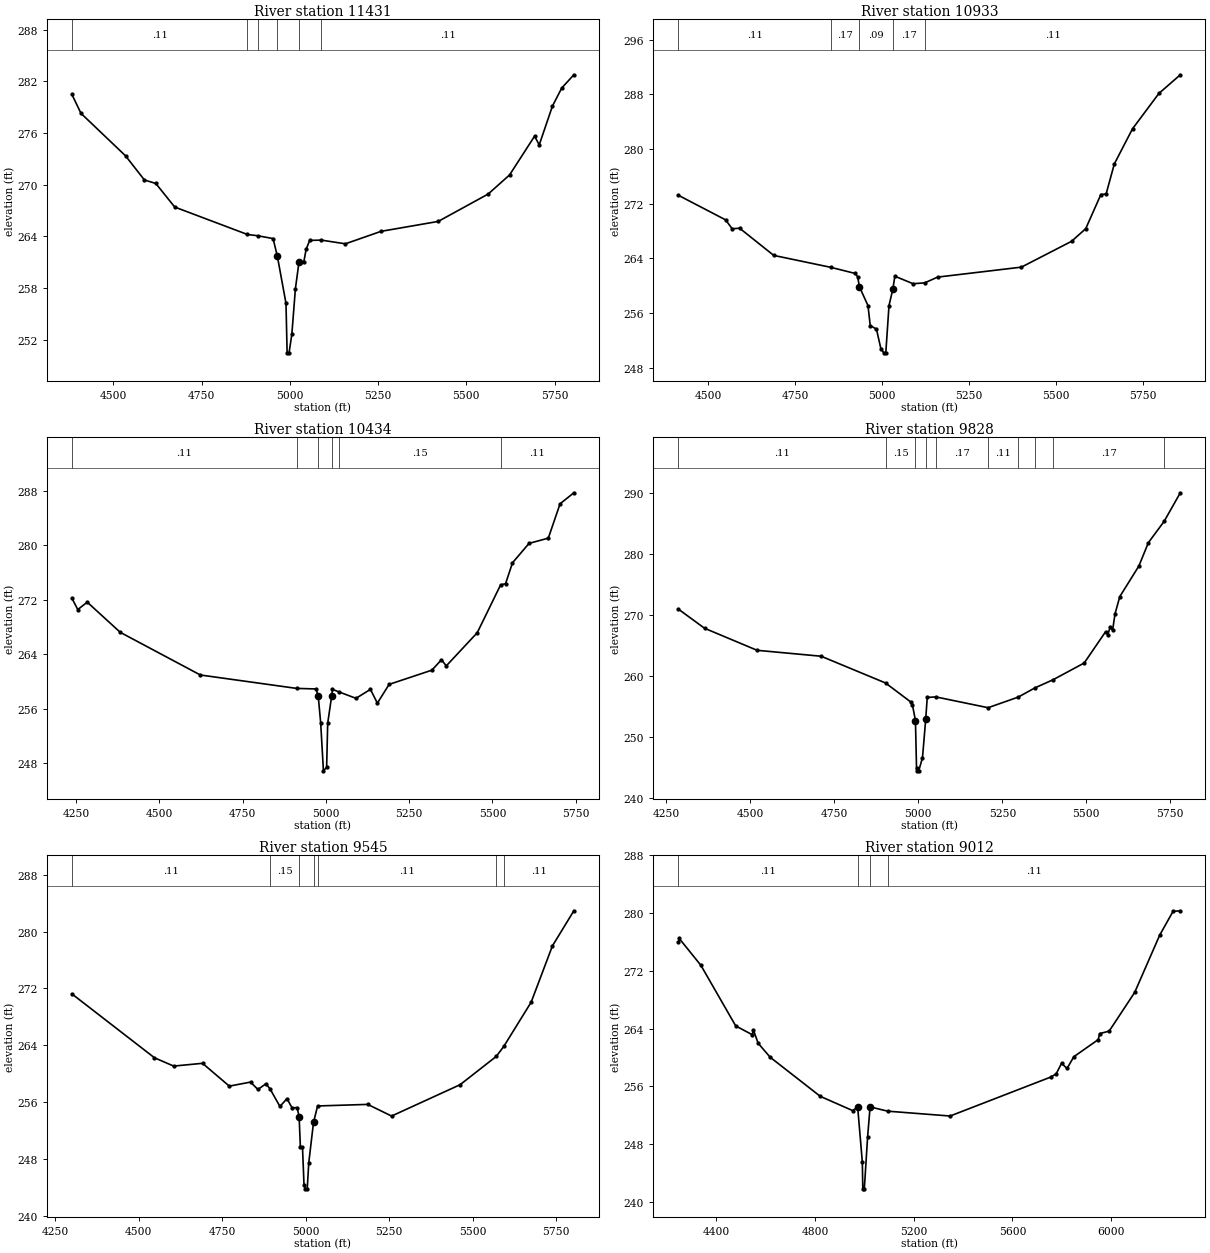
Type RM Length L Ch R = 1 ,11431   ,498,498,498
BEGIN DESCRIPTION:
CCLC 030 15.0
END DESCRIPTION:
XS GIS Cut Line= 3
      3709424.68     10125082.68      3709647.12     10124506.63
      3709767.86     10123711.04
#Sta/Elev= 30
  4382.5  280.47  4408.1  278.28  4534.3  273.35  4587.9  270.54  4620.1  270.14
  4673.7   267.4  4879.3  264.22  4909.9  264.06  4952.4  263.74  4964.4  261.72
    4989  256.22  4992.2  250.47  4997.7  250.47  5005.6  252.63  5015.7  257.92
  5025.9  261.03  5039.6  261.05  5046.1   262.5  5056.2  263.53  5089.2  263.56
  5157.3  263.13  5258.5  264.58  5420.3  265.73  5561.9  268.91  5622.6  271.13
  5693.4  275.63  5706.6  274.62    5744  279.12  5770.3  281.22  5804.7  282.76
#Mann= 6 ,-1 , 0
  4382.5     .11       0  4879.3     .17       0  4909.9     .11       0
  4964.4     .09       0  5025.9     .17       0  5089.2     .11       0
Bank Sta=4964.4,5025.9
XS Rating Curve= 0 ,0
Exp/Cntr=0.3,0.1

Type RM Length L Ch R = 1 ,10933   ,499,499,499
BEGIN DESCRIPTION:
CCLC 030 14.0
END DESCRIPTION:
XS GIS Cut Line= 3
      3709914.27     10125145.15      3710128.16     10124599.15
      3710467.86     10123811.04
#Sta/Elev= 30
  4413.6  273.22  4549.5  269.62  4568.3  268.32  4589.8   268.4  4687.9  264.42
  4853.2  262.66  4922.8  261.77  4929.4  261.29  4934.7  259.81  4959.2  257.07
  4965.7  254.15  4983.6  253.62  4996.3  250.77  5004.8  250.15  5010.5  250.15
  5019.7  257.07  5030.6  259.45  5036.6  261.37  5089.1  260.27  5122.6   260.4
  5159.6  261.24  5400.8   262.7  5545.1  266.48  5585.9  268.33  5629.5  273.33
  5644.6  273.41  5668.2  277.81  5720.6  282.96  5796.6  288.14  5858.2  290.87
#Mann= 5 ,-1 , 0
  4413.6     .11       0  4853.2     .17       0  4934.7     .09       0
  5030.6     .17       0  5122.6     .11       0
Bank Sta=4934.7,5030.6
XS Rating Curve= 0 ,0
Exp/Cntr=0.3,0.1

Type RM Length L Ch R = 1 ,10434   ,606,606,606
BEGIN DESCRIPTION:
CCLC 030 13.0
END DESCRIPTION:
XS GIS Cut Line= 3
      3710091.33     10125249.36      3710608.93     10124689.73
       3711069.5     10124104.79
#Sta/Elev= 30
  4237.7  272.24  4255.2  270.58  4283.6  271.67  4382.8  267.23  4623.2  260.96
  4912.2  258.99  4970.2  258.91    4977  257.91  4984.4  253.94  4992.7  246.87
  5002.3  247.37  5005.5  253.86 5017.28257.8314  5019.9  258.85  5038.9  258.48
  5090.5  257.53  5133.8  258.85  5154.6  256.82  5189.9  259.58  5318.2  261.67
  5347.1   263.2  5361.5   262.3  5454.5  267.18  5524.6  274.21  5539.5  274.39
  5560.3  277.46    5610  280.31  5667.8  281.08  5703.1  286.13  5744.5  287.75
#Mann= 6 ,-1 , 0
  4237.7     .11       0  4912.2     .17       0    4977     .09       0
 5017.28     .17       0  5038.9     .15       0  5524.6     .11       0
Bank Sta=4977,5017.28
XS Rating Curve= 0 ,0
Exp/Cntr=0.3,0.1

Type RM Length L Ch R = 1 ,9828    ,283,283,283
BEGIN DESCRIPTION:
CCLC 030 12.0
END DESCRIPTION:
XS GIS Cut Line= 3
       3710299.7     10125520.16      3710924.68     10125176.43
      3711497.09     10124645.64
#Sta/Elev= 30
  4285.9  270.93  4363.7   267.8  4520.2  264.19  4710.6  263.22  4902.4  258.84
  4976.7  255.76  4982.4  255.27  4991.4  252.69  4994.6  244.95  4995.1  244.45
  5001.2  244.45  5012.4  246.61 5022.01252.9269  5026.5  256.47  5051.9  256.56
  5207.6  254.79  5297.1  256.52  5347.2  258.04  5400.7  259.36  5493.7  262.11
  5557.2  267.22    5564  266.75  5571.4  268.06  5578.2  267.47  5585.5  270.18
  5599.7  272.99  5656.4  277.99  5684.7  281.82  5731.5   285.3  5779.8  289.99
#Mann= 10 ,-1 , 0
  4285.9     .11       0  4902.4     .15       0  4991.4     .09       0
 5022.01     .15       0  5051.9     .17       0  5207.6     .11       0
  5297.1     .17       0  5347.2     .11       0  5400.7     .17       0
  5731.5     .11       0
Bank Sta=4991.4,5022.01
XS Rating Curve= 0 ,0
Exp/Cntr=0.3,0.1

Type RM Length L Ch R = 1 ,9545    ,533,533,533
BEGIN DESCRIPTION:
CCLC 030 11.0
END DESCRIPTION:
XS GIS Cut Line= 3
      3710417.88     10125811.06       3710997.6     10125442.05
      3711617.86     10124911.06
#Sta/Elev= 30
  4299.5  271.23  4546.7  262.25  4604.2  261.08  4690.7  261.47    4771  258.26
  4834.5  258.83  4856.6  257.79  4880.2  258.58  4892.4  257.92  4922.6   255.4
  4943.7   256.5    4959   255.2  4974.2  255.24  4980.1  253.95  4983.9  249.69
  4990.2  249.69  4994.8  244.32  4998.3  243.81  5004.4  243.81    5009  247.49
  5023.3  253.18  5035.5  255.47  5185.7  255.69  5257.1  254.05  5462.4  258.46
  5570.7  262.44  5593.2  263.84  5675.3  270.07    5739  277.99  5803.2  282.93
#Mann= 7 ,-1 , 0
  4299.5     .11       0  4892.4     .15       0  4980.1     .09       0
  5023.3     .15       0  5035.5     .11       0  5570.7     .17       0
  5593.2     .11       0
Bank Sta=4980.1,5023.3
XS Rating Curve= 0 ,0
Exp/Cntr=0.3,0.1

Type RM Length L Ch R = 1 ,9012    ,544,544,544
BEGIN DESCRIPTION:
CCLC 030 10.0
END DESCRIPTION:
XS GIS Cut Line= 3
      3710247.58     10126046.22      3711174.68     10125921.22
       3711685.1     10124947.25
#Sta/Elev= 30
  4245.8  275.95    4249  276.49  4336.9  272.77  4478.2  264.38    4545  263.17
  4550.1   263.8    4569  261.99  4617.7  260.05  4821.2  254.63  4952.4  252.66
  4972.6  253.16  4991.5  245.55  4993.5  241.83  4999.6  241.83    5013  249.05
    5023  253.17  5094.5  252.58  5347.4  251.91  5755.3   257.3  5777.4  257.74
  5799.4  259.21  5821.5  258.49  5849.2  260.12  5948.2  262.49  5953.9  263.32
  5992.3  263.66  6095.9  269.02  6197.6  276.97  6251.4  280.24  6280.9  280.32
#Mann= 4 ,-1 , 0
  4245.8     .11       0  4972.6     .09       0    5023     .15       0
  5094.5     .11       0
Bank Sta=4972.6,5023
XS Rating Curve= 0 ,0
Exp/Cntr=0.3,0.1

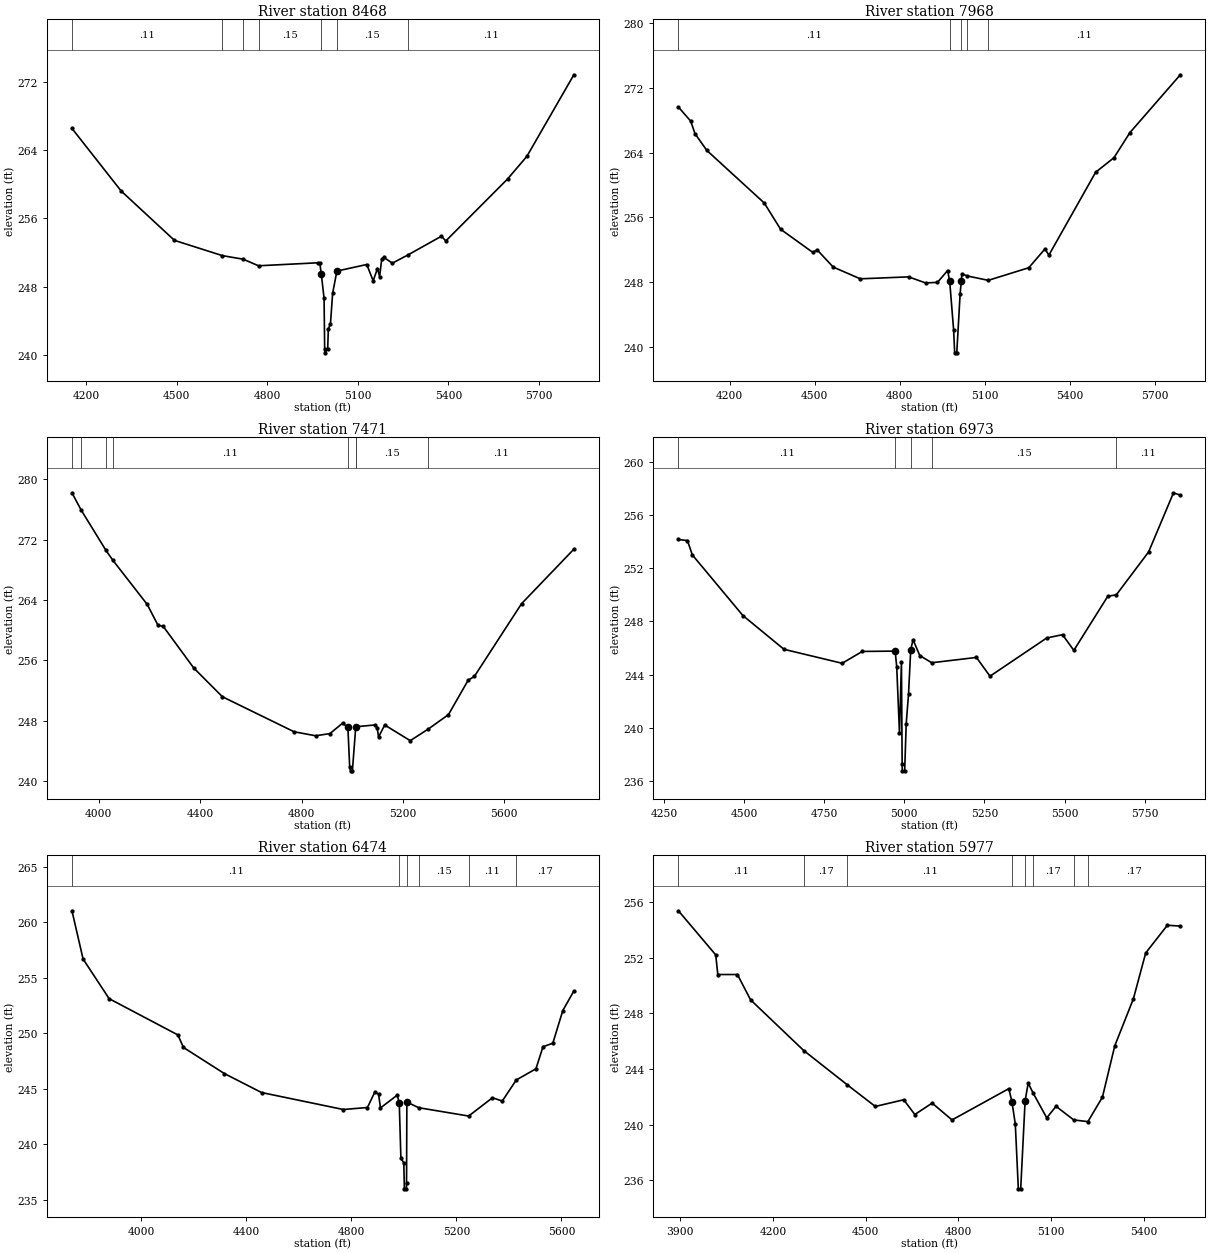
Type RM Length L Ch R = 1 ,8468    ,500,500,500
BEGIN DESCRIPTION:
CCLC 030 9.0
END DESCRIPTION:
XS GIS Cut Line= 3
      3710817.87     10126911.05      3711391.09     10126287.35
      3711967.84     10125711.09
#Sta/Elev= 30
  4152.9  266.55  4315.9  259.21  4492.4  253.42  4651.2  251.63  4720.1  251.21
  4770.8  250.44    4967  250.79  4973.8  250.75 4978.92249.4355    4988  246.61
  4989.9  240.73  4990.4  240.23    5000  240.73  5002.1  243.02  5009.2  243.66
  5016.3   247.2  5030.4  249.82  5129.4  250.59  5150.6  248.68  5164.8  250.11
  5171.9  249.17  5178.9  251.21    5186  251.42  5214.3  250.75  5265.7  251.71
  5376.9  253.91  5391.1  253.35  5596.1  260.63  5659.8  263.28  5815.3  272.84
#Mann= 7 ,-1 , 0
  4152.9     .11       0  4651.2     .15       0  4720.1     .11       0
  4770.8     .15       0 4978.92     .09       0  5030.4     .15       0
  5265.7     .11       0
Bank Sta=4978.92,5030.4
XS Rating Curve= 0 ,0
Exp/Cntr=0.3,0.1

Type RM Length L Ch R = 1 ,7968    ,497,497,497
BEGIN DESCRIPTION:
CCLC 030 8.0
END DESCRIPTION:
XS GIS Cut Line= 3
      3711217.84     10127411.08      3711771.31     10126601.12
       3712242.4     10125968.07
#Sta/Elev= 30
    4019  269.64  4062.4   267.9  4077.3  266.36  4119.2  264.28  4321.8  257.78
  4379.3  254.54  4493.1  251.67    4508     252  4564.9  249.86  4660.4  248.41
    4831  248.65  4890.7   247.9  4932.6  247.97  4968.5  249.43  4975.8  248.08
  4989.5  242.13  4993.3  239.26  5000.7  239.26  5012.5  246.53 5016.56248.0978
    5019  249.04  5036.8  248.77  5111.6  248.22  5254.7  249.78  5311.7   252.1
  5325.6  251.34  5490.4  261.58  5555.1  263.38  5611.3  266.48  5789.1  273.63
#Mann= 5 ,-1 , 0
    4019     .11       0  4975.8     .06       0 5016.56     .11       0
  5036.8     .15       0  5111.6     .11       0
Bank Sta=4975.8,5016.56
XS Rating Curve= 0 ,0
Exp/Cntr=0.3,0.1

Type RM Length L Ch R = 1 ,7471    ,498,498,498
BEGIN DESCRIPTION:
CCLC 030 7.0
END DESCRIPTION:
XS GIS Cut Line= 3
      3711367.86     10127711.07        3712145.     10126924.12
      3712467.85     10126111.08
#Sta/Elev= 30
    3894   278.2  3930.1  275.92  4028.3  270.56  4055.7  269.24    4191   263.4
  4233.4  260.64  4254.6  260.47  4374.8  254.96    4488  251.15  4770.8  246.51
  4855.7  245.98  4912.2  246.27  4961.8  247.64    4983  247.11  4990.1  241.84
  4993.4  241.33  5000.8  241.33    5014  247.15  5014.6  247.18  5089.4  247.41
  5098.7  247.05    5104  245.82  5128.3  247.41  5229.2  245.33    5301  246.89
  5379.9  248.78  5457.7  253.35    5482  253.84  5668.3  263.49  5874.8  270.72
#Mann= 8 ,-1 , 0
    3894     .17       0  3930.1     .11       0  4028.3     .17       0
  4055.7     .11       0    4983     .06       0    5014     .11       0
  5014.6     .15       0    5301     .11       0
Bank Sta=4983,5014
XS Rating Curve= 0 ,0
Exp/Cntr=0.3,0.1

Type RM Length L Ch R = 1 ,6973    ,499,499,499
BEGIN DESCRIPTION:
CCLC 030 6.0
END DESCRIPTION:
XS GIS Cut Line= 3
      3711967.89     10127611.05      3712547.37     10127208.82
      3713167.87     10126611.05
#Sta/Elev= 30
  4294.6  254.16  4322.9  254.08  4337.8  253.01  4495.8  248.45  4624.2  245.91
  4805.8  244.86  4868.6  245.75 4971.34245.7758  4976.2  244.58  4984.8  239.61
  4990.9  244.97  4993.1  237.28  4993.6  236.78    5001  236.78  5005.8  240.32
    5013  242.54  5019.9  245.87  5027.1  246.63  5048.2  245.44  5085.5   244.9
    5225   245.3  5267.4  243.89  5444.4  246.76  5493.8  247.01  5529.1  245.83
  5635.3   249.9  5661.7     250  5762.7  253.23  5840.3  257.67  5861.6  257.49
#Mann= 5 ,-1 , 0
  4294.6     .11       0 4971.34     .06       0  5019.9     .11       0
  5085.5     .15       0  5661.7     .11       0
Bank Sta=4971.34,5019.9
XS Rating Curve= 0 ,0
Exp/Cntr=0.3,0.1

Type RM Length L Ch R = 1 ,6474    ,497,497,497
BEGIN DESCRIPTION:
CCLC 030 5.0
END DESCRIPTION:
XS GIS Cut Line= 3
      3712117.83     10128211.09       3713019.2     10127326.95
      3713217.84      10126711.1
#Sta/Elev= 30
  3737.4  261.04  3779.8  256.69  3878.8  253.12  4140.5  249.85  4161.7  248.72
  4317.3  246.37  4458.7  244.66  4769.9  243.13  4861.7  243.31    4890  244.71
  4904.2   244.5  4911.3  243.27  4974.9  244.42 4982.76243.7411    4989  238.74
    5000  238.32  5002.3  235.98    5010  235.98  5010.5  236.48  5011.7   243.8
    5057  243.29  5246.9  242.54  5337.4  244.19  5374.7  243.89    5428  245.79
  5502.9   246.8  5529.7  248.79    5567   249.1  5605.1  252.05  5647.1  253.81
#Mann= 6 ,-1 , 0
  3737.4     .11       0 4982.76     .06       0  5011.7     .11       0
    5057     .15       0  5246.9     .11       0    5428     .17       0
Bank Sta=4982.76,5011.7
XS Rating Curve= 0 ,0
Exp/Cntr=0.3,0.1

Type RM Length L Ch R = 1 ,5977    ,470,470,470
BEGIN DESCRIPTION:
CCLC 030 4.0
END DESCRIPTION:
XS GIS Cut Line= 3
      3712767.85     10128211.07      3713505.81     10127386.86
      3713528.84     10126869.17
#Sta/Elev= 30
  3893.7  255.36  4014.5  252.19  4021.2  250.78  4084.7  250.78  4127.3  248.96
  4299.2  245.32  4440.5  242.85    4531   241.3    4623  241.78  4658.8  240.72
    4715  241.54  4779.3  240.33  4963.2  242.58 4973.29241.6302  4984.1  240.03
  4993.9  235.38  5001.6  235.38  5015.8   241.7  5025.8  242.98  5041.3  242.28
  5085.9  240.48  5115.9  241.31  5173.3  240.33  5219.1  240.21  5266.1  241.97
  5306.1  245.66  5366.2  249.03  5406.2  252.33  5476.3  254.32  5518.2  254.26
#Mann= 8 ,-1 , 0
  3893.7     .11       0  4299.2     .17       0  4440.5     .11       0
 4973.29     .06       0  5015.8     .11       0  5041.3     .17       0
  5173.3     .11       0  5219.1     .17       0
Bank Sta=4973.29,5015.8
XS Rating Curve= 0 ,0
Exp/Cntr=0.3,0.1