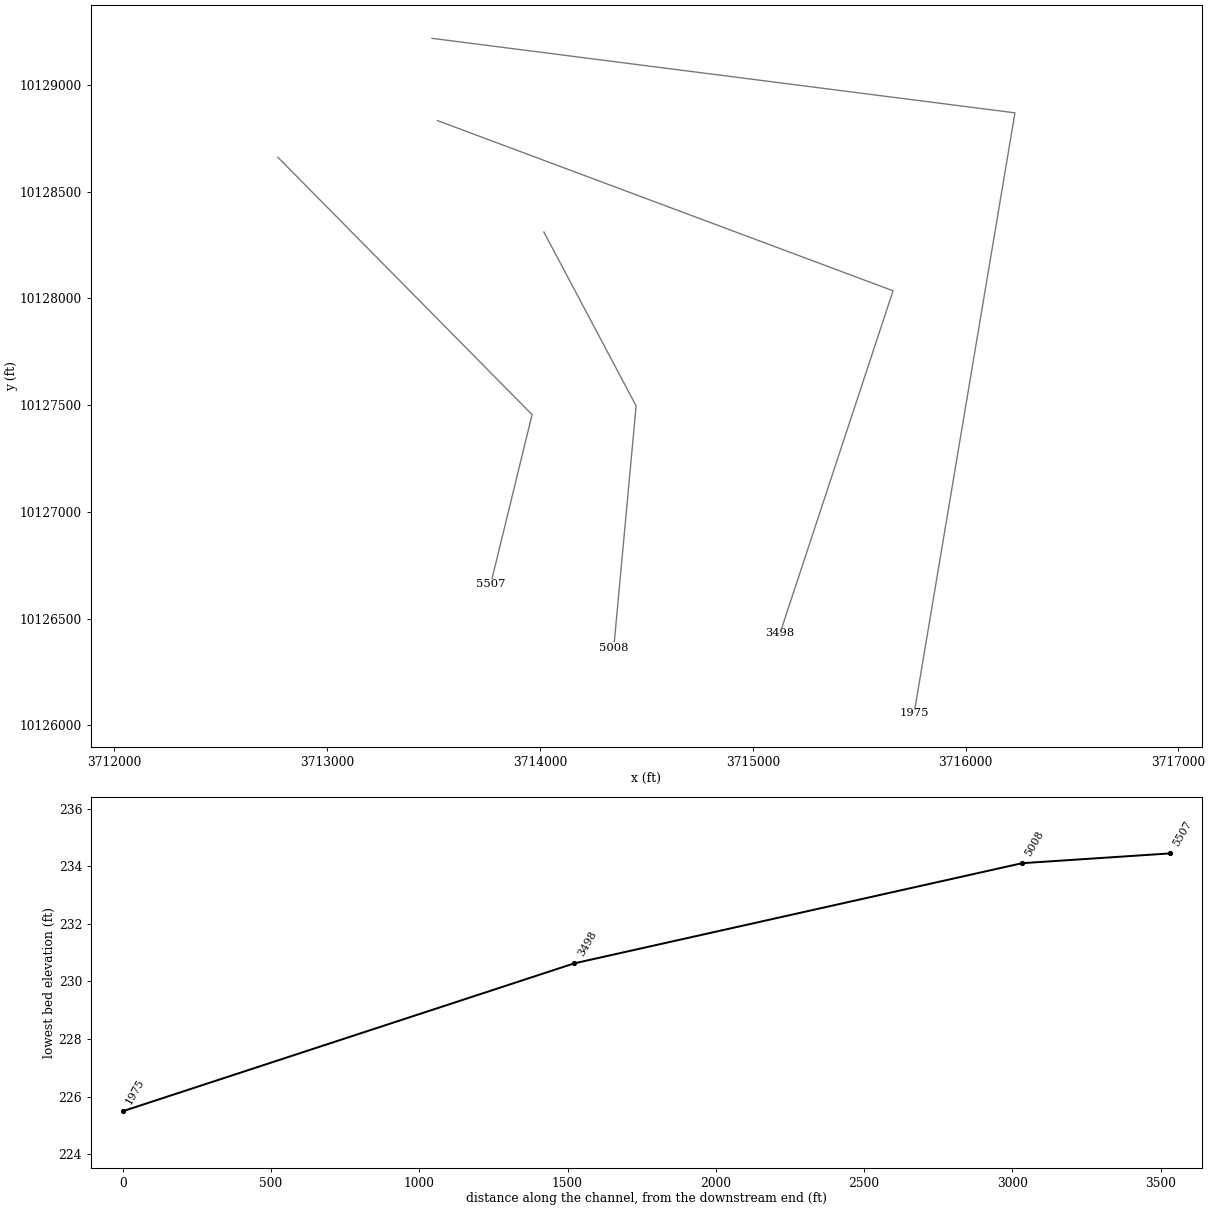
HEC-RAS study CCLC 030.prj: CCLC 030 Base Level Engineering

--- CCLC 030.g01 (geometry) --- (continued)

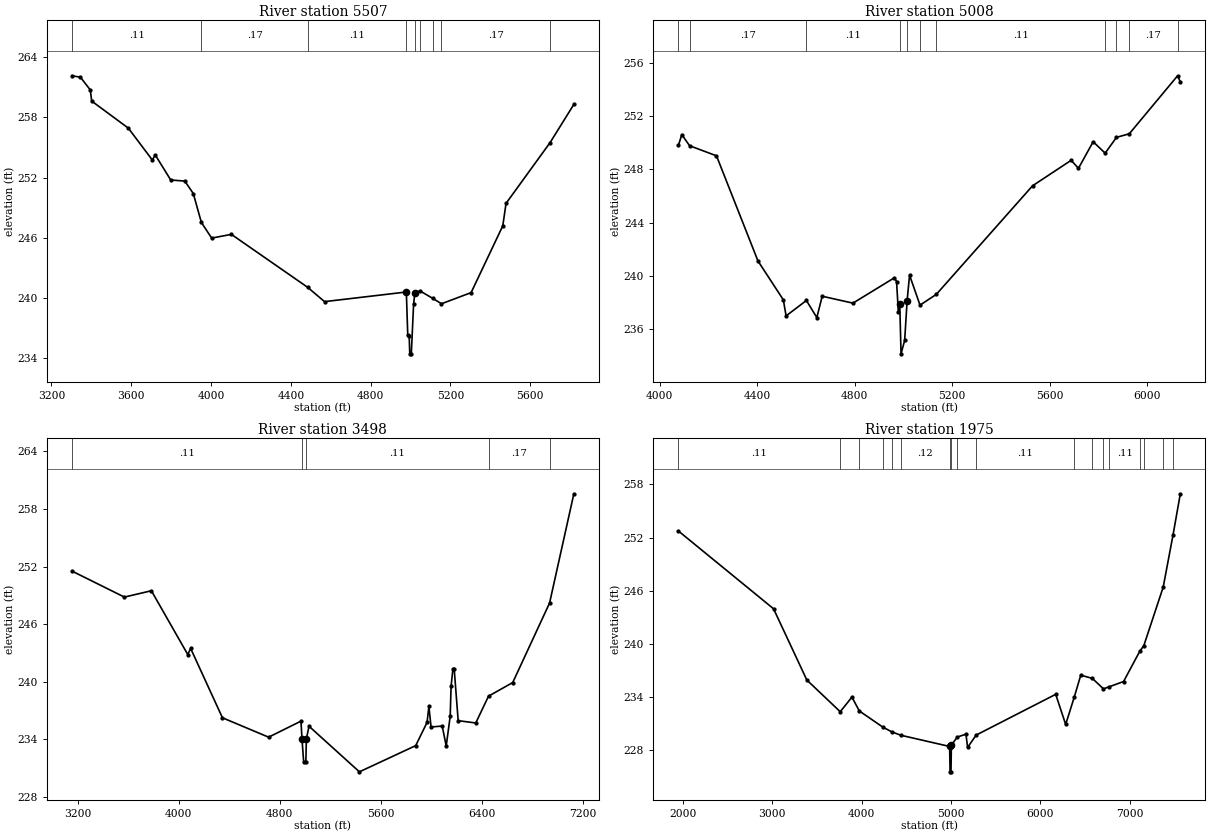
Type RM Length L Ch R = 1 ,5507    ,499,499,499
BEGIN DESCRIPTION:
CCLC 030 3.0
END DESCRIPTION:
XS GIS Cut Line= 3
      3712767.84     10128661.08      3713962.56     10127455.76
      3713767.85     10126661.06
#Sta/Elev= 30
  3302.9  262.15  3345.3  262.01  3394.8  260.74  3401.9  259.63  3585.7  256.93
    3706  253.75  3720.1  254.27  3797.9  251.77  3868.6  251.66    3911  250.42
  3951.5  247.54    4003  245.98    4102  246.35  4484.6  241.07  4568.7  239.65
  4978.7  240.61  4985.8  236.31  4992.9  236.24  4995.9  234.45  5003.6  234.45
  5015.1  239.41 5021.66240.5564    5047  240.72  5109.8  239.99  5154.9  239.44
  5303.4  240.55    5462   247.2  5478.4  249.44  5699.3   255.5  5818.2   259.3
#Mann= 9 ,-1 , 0
  3302.9     .11       0  3951.5     .17       0  4484.6     .11       0
  4978.7     .06       0 5021.66     .11       0    5047     .17       0
  5109.8     .11       0  5154.9     .17       0  5699.3     .11       0
Bank Sta=4978.7,5021.66
XS Rating Curve= 0 ,0
Exp/Cntr=0.3,0.1

Type RM Length L Ch R = 1 ,5008    ,1510,1510,1510
BEGIN DESCRIPTION:
CCLC 030 2.0
END DESCRIPTION:
XS GIS Cut Line= 3
      3714017.87     10128311.03      3714451.54     10127496.71
      3714346.65     10126364.96
#Sta/Elev= 30
  4077.4  249.81  4091.2  250.63  4123.2  249.79  4233.6  249.03  4403.7  241.11
  4507.8  238.18  4519.2  236.97  4602.5  238.13  4645.3  236.84  4667.3  238.45
  4793.4  237.93  4963.5  239.84  4972.4  239.56  4979.8  237.23  4985.5  237.85
  4990.8  234.11  5005.7  235.13  5015.7  238.11  5025.7  240.04  5068.6  237.78
  5135.5  238.59  5530.3  246.77  5688.6  248.69  5718.7  248.09    5779  250.09
  5828.2  249.23  5874.7  250.42  5927.3  250.69  6125.4  255.06  6136.6   254.6
#Mann= 11 ,-1 , 0
  4077.4     .11       0  4123.2     .17       0  4602.5     .11       0
  4985.5     .06       0  5015.7     .11       0  5068.6     .17       0
  5135.5     .11       0  5828.2     .17       0  5874.7     .11       0
  5927.3     .17       0  6125.4     .11       0
Bank Sta=4985.5,5015.7
XS Rating Curve= 0 ,0
Exp/Cntr=0.3,0.1

Type RM Length L Ch R = 1 ,3498    ,1523,1523,1523
BEGIN DESCRIPTION:
Mapping XS f29b7a24
END DESCRIPTION:
XS GIS Cut Line= 3
      3713518.45     10128832.67      3715659.05      10128035.8
      3715127.79      10126431.6
#Sta/Elev= 30
  3154.8  251.54    3570  248.83  3783.7  249.49  4071.8  242.85  4094.7  243.48
  4346.4  236.26    4712  234.24  4968.1  235.91  4976.5  234.02  4989.5  231.64
  5006.8  231.66 5010.87  234.05  5031.8  235.38  5430.8  230.63  5876.6  233.36
  5966.5  235.78  5981.1  237.44  5998.2   235.3  6086.5   235.4  6118.1  233.32
  6149.7  236.42  6156.7  239.54  6170.8   241.3  6181.3  241.36  6212.9  235.96
  6352.2  235.72  6453.1  238.51  6644.8  239.93  6936.5  248.21  7128.8  259.59
#Mann= 5 ,-1 , 0
  3154.8     .11       0  4976.5     .06       0 5010.87     .11       0
  6453.1     .17       0  6936.5     .11       0
Bank Sta=4976.5,5010.87
XS Rating Curve= 0 ,0
Exp/Cntr=0.3,0.1

Type RM Length L Ch R = 1 ,1975    ,0,0,0
BEGIN DESCRIPTION:
CCLC 030 1.0
END DESCRIPTION:
XS GIS Cut Line= 3
      3713492.36      10129218.1      3716231.97     10128869.13
      3715758.01     10126056.63
#Sta/Elev= 30
    1952  252.74    3016  243.94  3388.3  235.88  3762.1  232.29    3893  233.95
  3975.1  232.38  4239.7  230.54  4339.7  230.01  4439.7  229.63  4985.6  228.36
  4990.7  225.49  5000.8  225.49  5005.1  228.52    5072  229.43  5168.1  229.75
  5186.6  228.25  5282.5  229.65  6172.1  234.26  6283.6  230.85  6381.3     234
  6452.3  236.43    6582  236.06  6706.2  234.88  6772.4  235.12  6931.3  235.71
  7113.9  239.16  7157.4  239.76  7374.4  246.39  7485.2  252.34  7565.9  256.95
#Mann= 18 ,-1 , 0
    1952     .11       0  3762.1     .15       0  3975.1     .11       0
  4239.7     .15       0  4339.7     .11       0  4439.7     .12       0
  4985.6     .07       0  5005.1     .12       0    5072     .12       0
  5282.5     .11       0  6381.3     .17       0    6582     .11       0
  6706.2     .17       0  6772.4     .11       0  7113.9     .17       0
  7157.4     .11       0  7374.4     .17       0  7485.2     .11       0
Bank Sta=4985.6,5005.1
XS Rating Curve= 0 ,0
Exp/Cntr=0.3,0.1

Chan Stop Cuts=-1
Use User Specified Reach Order=0
Composite Channel Slope=5