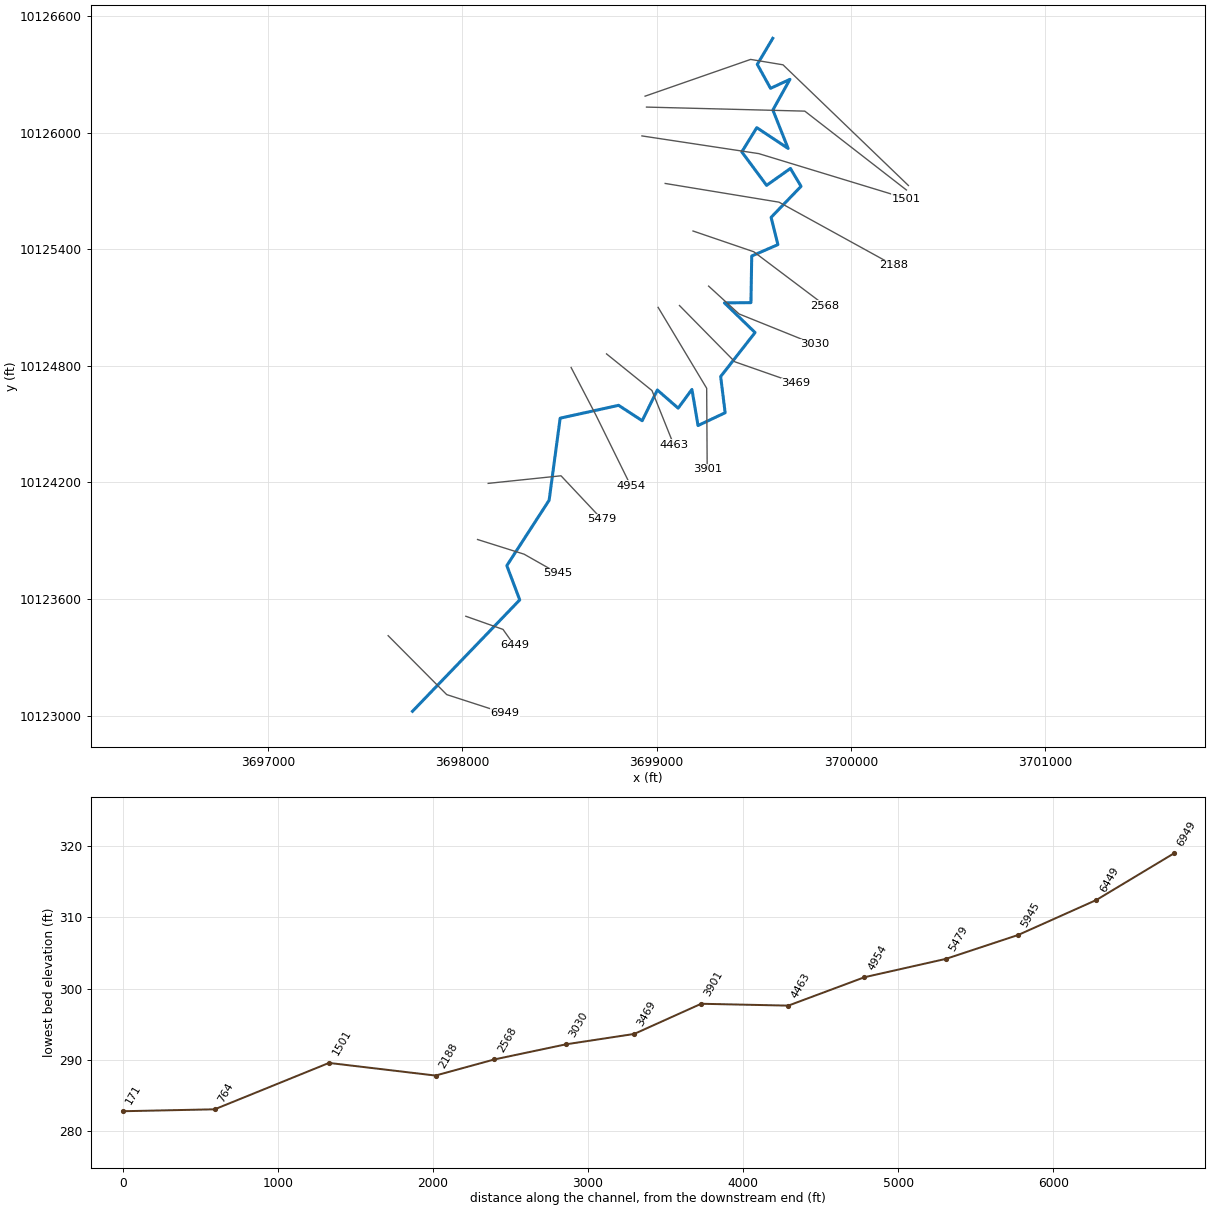
--- CCLC 031.prj (project) ---

Proj Title=CCLC 031 Base Level Engineering
Current Plan=p01
Default Exp/Contr=0.3,0.1
English Units
Geom File=g01
Flow File=f01
Flow File=f02
Plan File=p01
Y Axis Title=Elevation
X Axis Title(PF)=Main Channel Distance
X Axis Title(XS)=Station
BEGIN DESCRIPTION:
CCLC 031
END DESCRIPTION:
DSS Export Rating Curves= 0
DSS Export Rating Curve Sorted= 0
DSS Export Volume Flow Curves= 0
DXF OffsetX= 0
DXF OffsetY= 0
DXF ScaleX= 1
DXF ScaleY= 10

--- CCLC 031.p01 (plan) ---

Plan Title=Multiple Run
Short Identifier=Multiple
Geom File=g01
Flow File=f01
Subcritical Flow
K Sum by GR= 0
Std Step Tol= 0.01
Critical Tol= 0.01
Num of Std Step Trials= 20
Max Error Tol= 0.3
Flow Tol Ratio= 0.001
Split Flow NTrial= 30
Split Flow Tol= 0.02
Split Flow Ratio= 0.02
Log Output Level= 0
Friction Slope Method= 1
Unsteady Friction Slope Method= 2
Unsteady Bridges Friction Slope Method= 1
Parabolic Critical Depth
Global Vel Dist=  1 , 1 , 1
Global Log Level= 0
CheckData=True
Encroach Param= -1, 0, 0, 0
BEGIN DESCRIPTION:
Multiple Run
END DESCRIPTION:

--- CCLC 031.f01 (steady flow) ---

Flow Title=Multiple
Program Version=4.10
Number of Profiles= 7
Profile Names=10-year,25-year,50-year,1pct_min,100-year,1pct_plu,500-year
River Rch & RM=CCLC 031,Reach-1         ,6949
     655     896    1217     545    1645    4968    3106
Boundary for River Rch & Prof#=CCLC 031,Reach-1         , 1
Up Type= 0
Dn Type= 3
Dn Slope=0.005
Boundary for River Rch & Prof#=CCLC 031,Reach-1         , 2
Up Type= 0
Dn Type= 3
Dn Slope=0.005
Boundary for River Rch & Prof#=CCLC 031,Reach-1         , 3
Up Type= 0
Dn Type= 3
Dn Slope=0.005
Boundary for River Rch & Prof#=CCLC 031,Reach-1         , 4
Up Type= 0
Dn Type= 3
Dn Slope=0.005
Boundary for River Rch & Prof#=CCLC 031,Reach-1         , 5
Up Type= 0
Dn Type= 3
Dn Slope=0.005
Boundary for River Rch & Prof#=CCLC 031,Reach-1         , 6
Up Type= 0
Dn Type= 3
Dn Slope=0.005
Boundary for River Rch & Prof#=CCLC 031,Reach-1         , 7
Up Type= 0
Dn Type= 3
Dn Slope=0.005
DSS Import GetInterval= 0
DSS Import GetPeak= 0
DSS Import FillOption= 0

--- CCLC 031.f02 (steady flow) ---

Flow Title=Orig_BLE_Flows
Program Version=4.10
Number of Profiles= 7
Profile Names=10-year,25-year,50-year,1pct_min,100-year,1pct_plu,500-year
River Rch & RM=CCLC 031,Reach-1         ,6949
     655     878    1058     419    1265    3820    1806
Boundary for River Rch & Prof#=CCLC 031,Reach-1         , 1
Up Type= 0
Dn Type= 3
Dn Slope=0.005
Boundary for River Rch & Prof#=CCLC 031,Reach-1         , 2
Up Type= 0
Dn Type= 3
Dn Slope=0.005
Boundary for River Rch & Prof#=CCLC 031,Reach-1         , 3
Up Type= 0
Dn Type= 3
Dn Slope=0.005
Boundary for River Rch & Prof#=CCLC 031,Reach-1         , 4
Up Type= 0
Dn Type= 3
Dn Slope=0.005
Boundary for River Rch & Prof#=CCLC 031,Reach-1         , 5
Up Type= 0
Dn Type= 3
Dn Slope=0.005
Boundary for River Rch & Prof#=CCLC 031,Reach-1         , 6
Up Type= 0
Dn Type= 3
Dn Slope=0.005
Boundary for River Rch & Prof#=CCLC 031,Reach-1         , 7
Up Type= 0
Dn Type= 3
Dn Slope=0.005
DSS Import GetInterval= 0
DSS Import GetPeak= 0
DSS Import FillOption= 0

--- CCLC 031.g01 (geometry) ---

Geom Title=Existing Conditions
Program Version=4.10

River Reach=CCLC 031        ,Reach-1
Reach XY= 30
      3697743.23     10123021.84      3698295.36     10123595.44
      3698228.83     10123771.73      3698446.65      10124108.4
      3698503.48     10124531.07      3698804.42     10124597.19
      3698925.88     10124517.97      3699003.83     10124676.12
      3699111.06     10124582.67      3699181.89     10124679.07
      3699213.37     10124493.14      3699353.06     10124559.06
       3699329.8     10124745.24      3699507.04     10124971.94
      3699349.35     10125124.72      3699485.82     10125125.94
      3699489.88     10125366.05      3699624.62     10125424.59
      3699589.71     10125565.05      3699743.79      10125724.9
      3699689.07      10125816.8       3699566.5     10125729.75
      3699438.69     10125902.11      3699515.91      10126026.9
      3699677.26     10125919.95      3699598.68     10126117.79
      3699686.63     10126275.62      3699586.71     10126229.44
      3699518.42     10126352.85      3699598.23     10126486.84

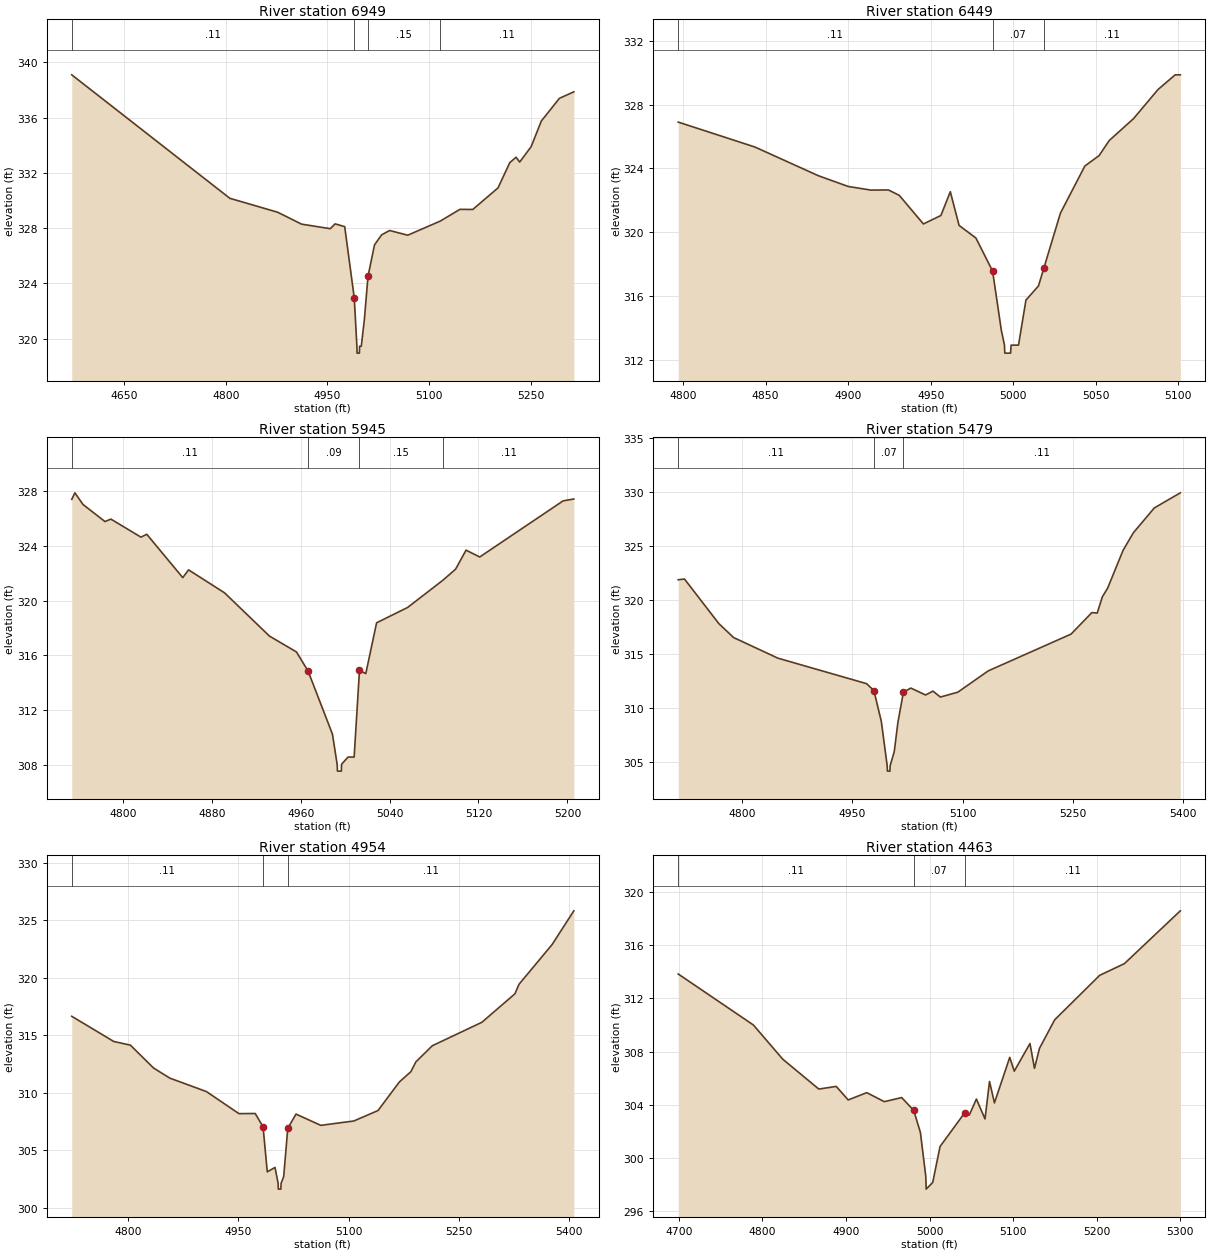
Type RM Length L Ch R = 1 ,6949    ,500,500,500
BEGIN DESCRIPTION:
CCLC 031 11.0
END DESCRIPTION:
XS GIS Cut Line= 3
      3697617.85     10123411.07      3697919.26     10123107.77
      3698217.89     10123011.06
#Sta/Elev= 30
  4572.4  339.09  4805.8  330.16  4876.5  329.15  4911.8  328.29  4954.2  327.96
  4961.3  328.31  4975.5  328.11  4989.6  322.96  4993.5  319.46  4993.7  318.96
  4997.2  318.96  4997.5  319.46    5000  319.46  5004.6  321.42  5009.9  324.51
  5019.5  326.79  5030.1  327.52  5041.9  327.83  5068.6  327.49  5116.6  328.51
  5145.7  329.36  5164.6  329.35  5201.9  330.91  5219.3  332.74  5228.6  333.13
  5233.9  332.78  5250.8  333.89  5265.9  335.75  5292.6  337.39  5313.9  337.86
#Mann= 4 ,-1 , 0
  4572.4     .11       0  4989.6     .07       0  5009.9     .15       0
  5116.6     .11       0
Bank Sta=4989.6,5009.9
XS Rating Curve= 0 ,0
Exp/Cntr=0.3,0.1

Type RM Length L Ch R = 1 ,6449    ,504,504,504
BEGIN DESCRIPTION:
CCLC 031 10.0
END DESCRIPTION:
XS GIS Cut Line= 3
      3698017.83     10123511.08      3698209.15     10123443.49
      3698267.86     10123361.06
#Sta/Elev= 30
  4797.1   326.9  4843.5  325.34    4882  323.54    4900  322.87  4913.8  322.64
  4924.4  322.65    4931  322.31  4945.6  320.52  4956.2  321.05  4961.9  322.54
  4967.2  320.43  4977.4  319.64  4987.5  317.57  4992.8  313.86  4994.7  312.93
  4994.9  312.43  4998.4  312.43  4998.7  312.93  5003.2  312.93  5007.7  315.75
  5015.3  316.64 5018.51317.7405  5028.6   321.2  5043.4  324.15    5052   324.8
  5058.2  325.75  5072.9  327.12  5087.7  328.94  5098.1  329.86  5101.2  329.86
#Mann= 3 , 0 , 0
  4797.1     .11       0  4987.5     .07       0 5018.51     .11       0
Bank Sta=4987.5,5018.51
XS Rating Curve= 0 ,0
Exp/Cntr=0.3,0.1

Type RM Length L Ch R = 1 ,5945    ,466,466,466
BEGIN DESCRIPTION:
CCLC 031 9.0
END DESCRIPTION:
XS GIS Cut Line= 3
      3698078.18     10123906.29      3698317.79     10123830.76
      3698492.25     10123731.81
#Sta/Elev= 30
    4754  327.39  4756.8  327.87  4764.1  327.02  4783.9  325.77  4789.2  325.95
  4816.3  324.63  4821.5  324.84  4853.9  321.67  4859.1  322.24  4891.5  320.56
  4931.9   317.4  4956.2  316.24 4966.62314.8478  4988.6  310.23  4992.8  308.03
  4993.1  307.53  4996.6  307.53  4996.8  308.03  5002.6  308.56  5008.1  308.56
  5012.9  314.89  5018.6  314.66  5028.3  318.37  5056.2  319.49  5088.1  321.49
  5099.4  322.29  5108.8  323.68  5121.1  323.18  5196.1  327.28  5205.8  327.42
#Mann= 4 ,-1 , 0
    4754     .11       0 4966.62     .09       0  5012.9     .15       0
  5088.1     .11       0
Bank Sta=4966.62,5012.9
XS Rating Curve= 0 ,0
Exp/Cntr=0.3,0.1

Type RM Length L Ch R = 1 ,5479    ,525,525,525
BEGIN DESCRIPTION:
CCLC 031 8.0
END DESCRIPTION:
XS GIS Cut Line= 3
      3698132.87     10124195.34       3698507.9      10124234.4
      3698717.87     10124011.06
#Sta/Elev= 30
  4712.9   321.9  4721.4  321.97  4768.2  317.84  4788.3  316.55  4848.6  314.64
  4969.3  312.28  4979.3  311.64  4989.4  308.79  4997.4  304.68  4997.7  304.18
  5001.2  304.18  5001.4  304.68    5007  305.98    5012  308.69  5019.5   311.5
  5029.6  311.87  5049.7  311.23  5059.7  311.59  5069.8  311.04  5093.6  311.49
  5134.9  313.46  5247.8  316.87  5276.1  318.86  5283.4  318.82  5290.3  320.31
  5297.6  321.13  5318.6  324.63  5332.7  326.26  5361.1  328.55  5396.5  329.95
#Mann= 3 ,-1 , 0
  4712.9     .11       0  4979.3     .07       0  5019.5     .11       0
Bank Sta=4979.3,5019.5
XS Rating Curve= 0 ,0
Exp/Cntr=0.3,0.1

Type RM Length L Ch R = 1 ,4954    ,491,491,491
BEGIN DESCRIPTION:
CCLC 031 7.0
END DESCRIPTION:
XS GIS Cut Line= 3
      3698559.96     10124791.74      3698687.63     10124546.71
      3698867.29     10124182.29
#Sta/Elev= 30
  4723.7  316.65  4780.8  314.46  4803.4  314.14  4834.9  312.15    4857  311.27
  4906.8   310.1    4951  308.18  4973.1  308.19  4983.8  307.03  4989.5  303.11
    5000   303.5  5004.3  302.11  5004.5  301.61    5008  301.61  5008.3  302.11
  5011.8   302.7  5017.4  306.91  5028.6  308.14  5062.3  307.16  5107.2  307.54
  5140.1  308.45    5169  310.93  5184.7  311.83  5191.5  312.68  5213.9  314.09
  5281.3  316.13  5326.2  318.61  5331.8  319.44  5376.7  322.89  5406.3  325.83
#Mann= 3 ,-1 , 0
  4723.7     .11       0  4983.8     .07       0  5017.4     .11       0
Bank Sta=4983.8,5017.4
XS Rating Curve= 0 ,0
Exp/Cntr=0.3,0.1

Type RM Length L Ch R = 1 ,4463    ,562,562,562
BEGIN DESCRIPTION:
CCLC 031 6.0
END DESCRIPTION:
XS GIS Cut Line= 3
      3698742.27     10124862.01      3698976.28     10124673.17
      3699088.06     10124394.67
#Sta/Elev= 30
  4699.3  313.84  4789.2     310  4824.4  307.42  4867.5  305.17  4888.4  305.37
  4902.7  304.35  4924.9   304.9  4945.9  304.22  4966.7  304.53  4981.1  303.56
  4989.1   301.9  4995.5  298.61    4996  297.63  5003.8  298.13  5012.6  300.84
  5042.2  303.39  5047.6  303.21  5056.1  304.42  5066.4  302.92  5071.8  305.74
  5077.7  304.13    5096  307.56  5101.4  306.52  5120.2   308.6  5125.6  306.73
  5131.6  308.24  5149.8  310.39  5203.6  313.74  5233.2  314.62  5300.1   318.6
#Mann= 3 ,-1 , 0
  4699.3     .11       0  4981.1     .07       0  5042.2     .11       0
Bank Sta=4981.1,5042.2
XS Rating Curve= 0 ,0
Exp/Cntr=0.3,0.1

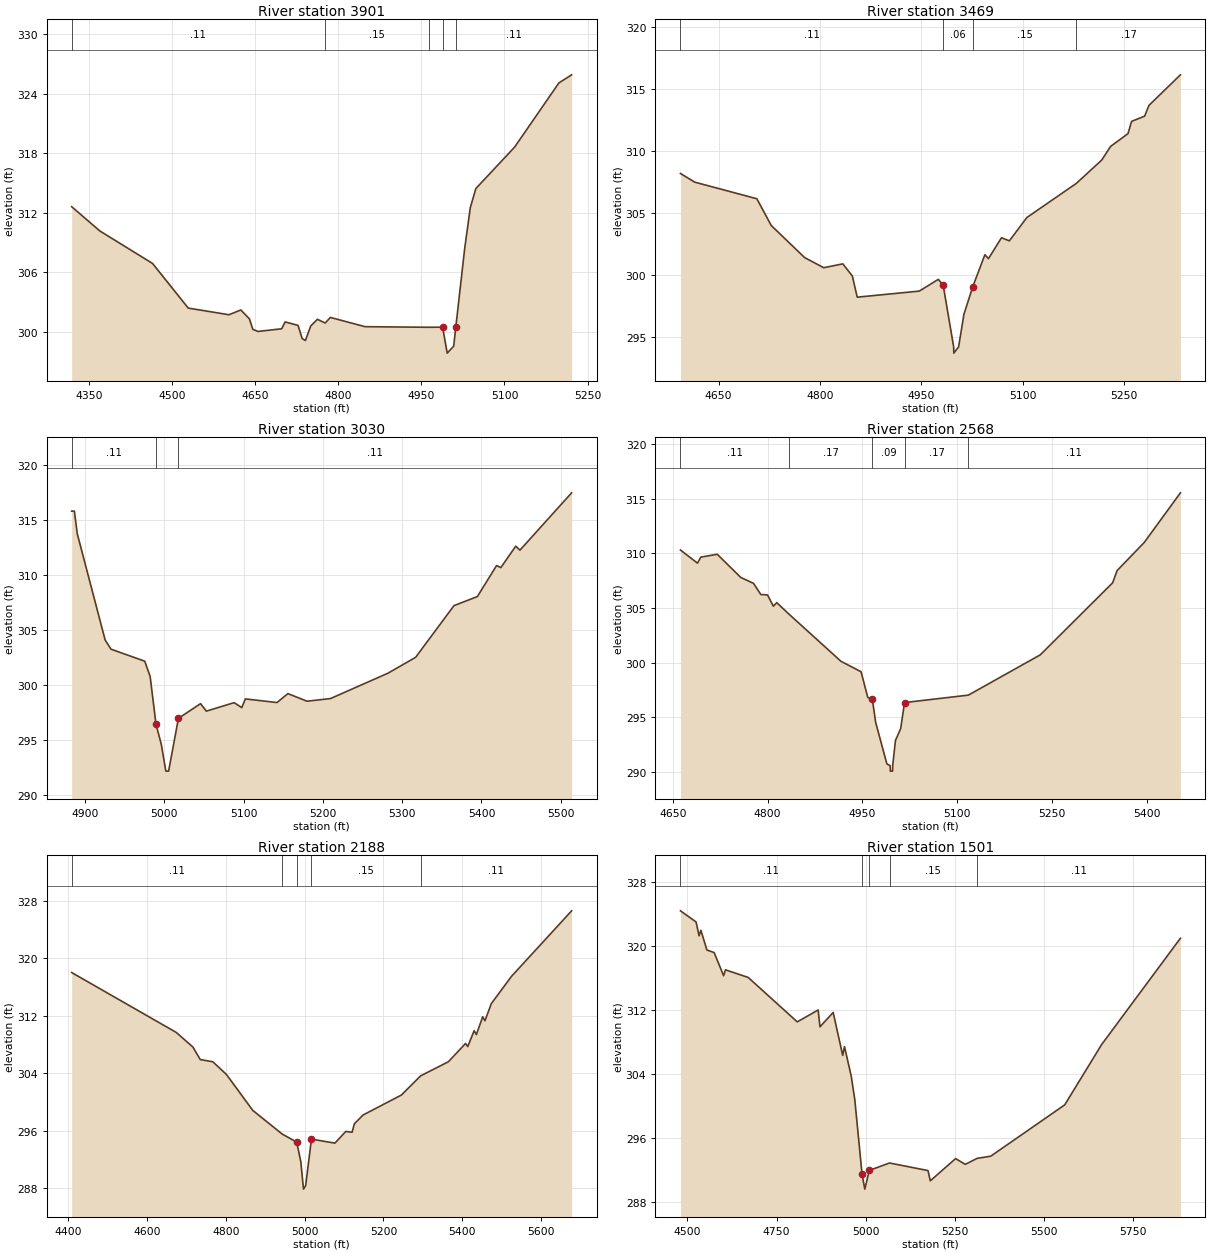
Type RM Length L Ch R = 1 ,3901    ,432,432,432
BEGIN DESCRIPTION:
Mapping XS f576152d
END DESCRIPTION:
XS GIS Cut Line= 3
      3699007.91     10125101.57       3699257.9     10124684.93
       3699260.5     10124268.22
#Sta/Elev= 30
  4318.6  312.62  4369.4  310.18  4464.6  306.91  4529.1  302.42  4602.6  301.75
    4624  302.23  4639.5  301.34  4645.7  300.28  4655.1  300.07  4697.8  300.34
    4704  301.03  4727.3  300.68  4734.8  299.35  4740.6  299.16  4750.3  300.63
  4762.3  301.29  4776.3  300.92  4785.7  301.48  4848.3  300.55  4963.4  300.49
  4988.3   300.5  4996.6  297.89  5008.3  298.59 5012.15300.5305  5028.3  308.48
  5038.3  312.53  5048.3  314.44  5118.3  318.61  5198.3  325.07  5221.2  325.88
#Mann= 5 ,-1 , 0
  4318.6     .11       0  4776.3     .15       0  4963.4     .11       0
  4988.3     .07       0 5012.15     .11       0
Bank Sta=4988.3,5012.15
XS Rating Curve= 0 ,0
Exp/Cntr=0.3,0.1

Type RM Length L Ch R = 1 ,3469    ,439,439,439
BEGIN DESCRIPTION:
CCLC 031 5.0
END DESCRIPTION:
XS GIS Cut Line= 3
      3699117.84     10125111.09      3699402.91      10124821.3
      3699717.87     10124711.06
#Sta/Elev= 30
  4593.5  308.17  4614.7  307.47  4706.6  306.13  4727.9  303.97  4777.3  301.38
  4805.6  300.56  4833.9  300.87    4848  299.89  4855.2  298.18  4947.1  298.67
  4975.3  299.62  4982.5  299.14    4998  294.16  4998.2  293.66  5005.3  294.16
  5013.2   296.8  5026.4  299.04  5044.2  301.61  5049.5  301.29  5068.8  302.98
  5080.5  302.73  5106.3  304.61  5179.6  307.37  5217.1  309.25  5230.4  310.36
  5256.1  311.39  5261.4  312.38  5280.7   312.8  5287.1  313.67  5333.7  316.14
#Mann= 4 ,-1 , 0
  4593.5     .11       0  4982.5     .06       0  5026.4     .15       0
  5179.6     .17       0
Bank Sta=4982.5,5026.4
XS Rating Curve= 0 ,0
Exp/Cntr=0.3,0.1

Type RM Length L Ch R = 1 ,3030    ,462,462,462
BEGIN DESCRIPTION:
CCLC 031 4.0
END DESCRIPTION:
XS GIS Cut Line= 3
      3699267.87     10125211.06      3699424.57     10125067.74
      3699812.63     10124911.47
#Sta/Elev= 30
    4883  315.79  4886.4  315.79  4890.1  313.73  4925.2  304.11  4932.6  303.27
  4975.2  302.18    4982   300.8  4989.4  296.46  4996.1  294.63  5001.8  292.21
  5005.3  292.21  5017.7     297  5045.6  298.33  5052.9  297.65    5088  298.42
  5097.6  297.97  5102.1  298.76    5142  298.43  5155.8  299.24  5179.9  298.55
  5209.5  298.79    5282  301.09  5316.9  302.53  5365.3  307.22  5394.8  308.04
    5419  310.85  5424.4  310.67  5443.2  312.61  5448.5  312.25  5513.7  317.45
#Mann= 3 , 0 , 0
    4883     .11       0  4989.4     .06       0  5017.7     .11       0
Bank Sta=4989.4,5017.7
XS Rating Curve= 0 ,0
Exp/Cntr=0.3,0.1

Type RM Length L Ch R = 1 ,2568    ,380,380,380
BEGIN DESCRIPTION:
CCLC 031 3.0
END DESCRIPTION:
XS GIS Cut Line= 3
      3699187.58     10125494.82      3699500.09     10125388.05
      3699867.82      10125111.1
#Sta/Elev= 30
  4662.2  310.31  4689.1  309.11  4694.4  309.66  4720.4  309.92  4757.6   307.8
  4777.8  307.26  4789.3  306.24  4799.9   306.2  4809.1  305.17  4814.4   305.5
  4834.5  304.41  4916.1  300.13  4947.8  299.18  4958.4  296.83  4965.6  296.67
  4970.9  294.55  4988.6  290.75  4993.8  290.59  4994.1  290.09  4997.6  290.09
  4997.8  290.59  5002.2   292.9  5010.4  293.97  5016.6  296.36  5117.5  297.04
  5231.1  300.72  5345.6  307.31  5352.7  308.43  5395.6     311  5452.8  315.54
#Mann= 5 ,-1 , 0
  4662.2     .11       0  4834.5     .17       0  4965.6     .09       0
  5016.6     .17       0  5117.5     .11       0
Bank Sta=4965.6,5016.6
XS Rating Curve= 0 ,0
Exp/Cntr=0.3,0.1

Type RM Length L Ch R = 1 ,2188    ,687,687,687
BEGIN DESCRIPTION:
CCLC 031 2.0
END DESCRIPTION:
XS GIS Cut Line= 3
      3699044.37     10125739.61      3699630.29     10125643.26
      3700221.41     10125317.76
#Sta/Elev= 30
    4409  318.02  4674.1  309.68  4716.6  307.64  4735.3  305.89  4767.2  305.58
  4801.6  303.82  4868.6   298.8  4943.6  295.49    4980  294.39  4990.4  291.67
  4997.3  287.83  5002.8  288.33  5017.4   294.8    5077  294.24  5104.5  295.87
  5120.6  295.76  5126.3  296.93  5148.4  298.16  5245.6  300.94  5294.5  303.62
  5364.9  305.58  5408.4  308.13  5414.1   307.7  5430.2  309.91  5435.9  309.37
    5452  311.85  5457.7  311.29  5473.8  313.68  5525.1  317.49  5677.6  326.62
#Mann= 5 ,-1 , 0
    4409     .11       0  4943.6     .15       0    4980     .09       0
  5017.4     .15       0  5294.5     .11       0
Bank Sta=4980,5017.4
XS Rating Curve= 0 ,0
Exp/Cntr=0.3,0.1

Type RM Length L Ch R = 1 ,1501    ,737,737,737
BEGIN DESCRIPTION:
Mapping XS 3da24e2f
END DESCRIPTION:
XS GIS Cut Line= 3
      3698924.55     10125984.41      3699526.13     10125893.26
      3700284.73     10125662.04
#Sta/Elev= 30
  4480.6  324.41  4524.4  323.02  4532.8  321.29  4537.9  321.98  4554.7  319.51
    4575  319.19  4601.6  316.29  4606.7  317.03  4670.4  316.08    4808  310.52
  4866.6  312.01  4871.7   309.9  4908.7   311.7  4935.4  306.33  4940.4  307.43
  4959.3  303.74  4969.4  300.76  4989.6  291.48  4997.4   289.6  5009.9  291.94
  5066.6  292.87  5174.5  291.92    5181  290.64  5251.9  293.42    5279   292.7
  5312.5  293.45  5350.4  293.72  5557.8  300.14  5661.5   307.7  5882.1  320.98
#Mann= 5 ,-1 , 0
  4480.6     .11       0  4989.6     .06       0  5009.9     .11       0
  5066.6     .15       0  5312.5     .11       0
Bank Sta=4989.6,5009.9
XS Rating Curve= 0 ,0
Exp/Cntr=0.3,0.1

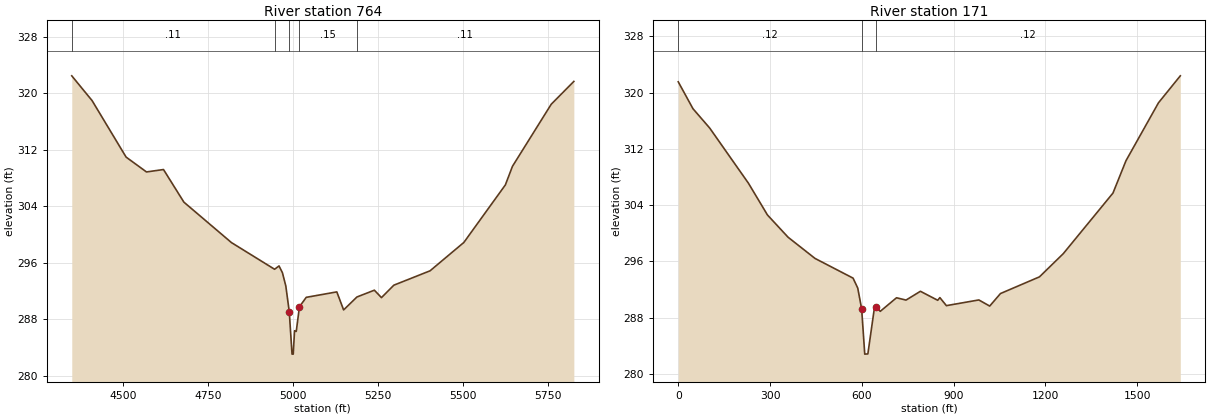
Type RM Length L Ch R = 1 ,764     ,593,593,593
BEGIN DESCRIPTION:
CCLC 031 1.0
END DESCRIPTION:
XS GIS Cut Line= 3
      3698948.01     10126132.84      3699763.11     10126112.01
      3700286.34     10125705.91
#Sta/Elev= 30
  4349.1  322.45    4409  318.94    4509  310.96    4569  308.86  4619.1   309.2
  4679.1  304.59  4819.1  298.87    4946   295.1  4959.1  295.57  4969.1  294.61
  4979.1  292.73  4989.2  289.12  4997.4   283.1  5000.9   283.1  5004.8  286.41
  5009.8  286.31  5019.2   289.8  5039.2  291.13  5129.2   291.9  5149.2  289.35
  5188.4  291.18  5239.7  292.14  5260.6  291.09  5297.1  292.85  5403.6  294.88
  5503.1  298.89  5625.3  307.03  5646.1  309.65  5760.2  318.43  5826.8  321.66
#Mann= 5 ,-1 , 0
  4349.1     .11       0    4946     .15       0  4989.2     .09       0
  5019.2     .15       0  5188.4     .11       0
Bank Sta=4989.2,5019.2
XS Rating Curve= 0 ,0
Exp/Cntr=0.3,0.1

Type RM Length L Ch R = 1 ,171     ,0,0,0
XS GIS Cut Line= 4
      3698940.79     10126189.06      3699484.19      10126378.3
      3699650.86     10126350.52      3700296.69     10125728.99
#Sta/Elev= 30
       0  321.53    48.1  317.71   102.8  314.96   229.4  307.12   291.5  302.61
     359  299.44     447  296.43   571.3  293.63   586.6  292.22   599.4  289.25
   609.5  282.83   619.7  282.86   639.9  289.04   647.4  289.52   660.2  288.91
   713.3  290.84   744.4  290.51   791.4  291.76     848  290.48     855  290.86
   876.3  289.72   982.3  290.53  1017.8  289.66  1053.1  291.44  1180.4  293.81
  1258.1   297.1  1420.7  305.72  1463.1  310.31  1569.4  318.55  1640.7  322.38
#Mann= 3 , 0 , 0
       0     .12       0   599.4     .07       0   647.4     .12       0
Bank Sta=599.4,647.4
XS Rating Curve= 0 ,0
Exp/Cntr=0.3,0.1

Chan Stop Cuts=-1
Use User Specified Reach Order=0
Composite Channel Slope=5