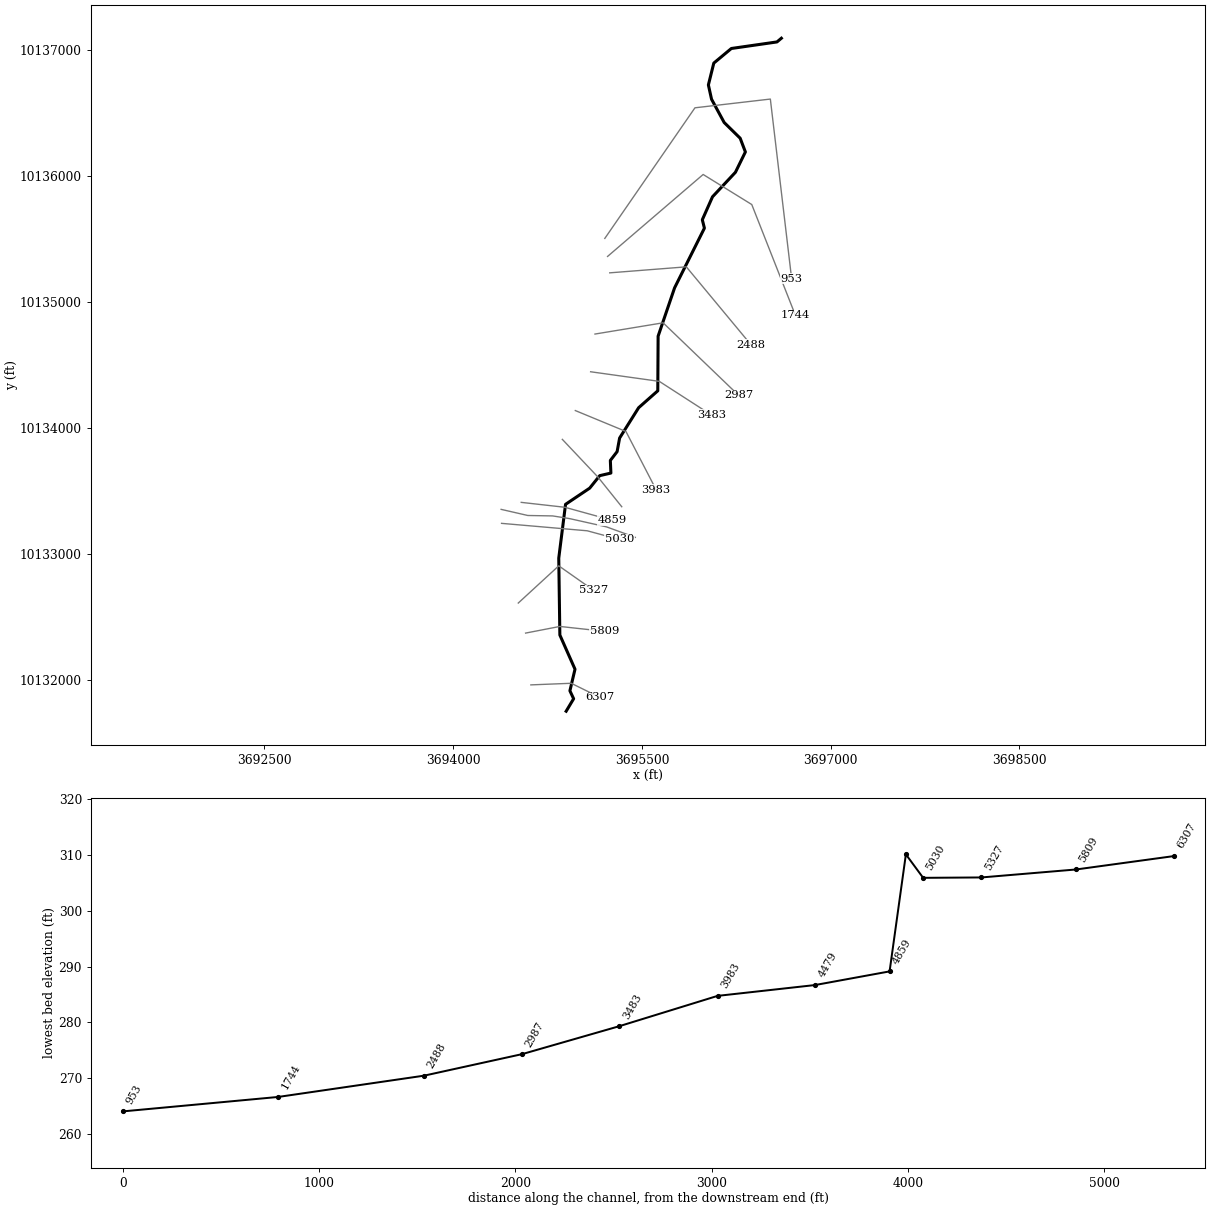
--- CCLC 033.prj (project) ---

Proj Title=CCLC 033 Base Level Engineering
Current Plan=p01
Default Exp/Contr=0.3,0.1
English Units
Geom File=g01
Flow File=f01
Flow File=f02
Plan File=p01
Y Axis Title=Elevation
X Axis Title(PF)=Main Channel Distance
X Axis Title(XS)=Station
BEGIN DESCRIPTION:
CCLC 033
END DESCRIPTION:
DSS Export Rating Curves= 0
DSS Export Rating Curve Sorted= 0
DSS Export Volume Flow Curves= 0
DXF OffsetX= 0
DXF OffsetY= 0
DXF ScaleX= 1
DXF ScaleY= 10

--- CCLC 033.p01 (plan) ---

Plan Title=Multiple Run
Short Identifier=Multiple
Geom File=g01
Flow File=f01
Subcritical Flow
K Sum by GR= 0
Std Step Tol= 0.01
Critical Tol= 0.01
Num of Std Step Trials= 20
Max Error Tol= 0.3
Flow Tol Ratio= 0.001
Split Flow NTrial= 30
Split Flow Tol= 0.02
Split Flow Ratio= 0.02
Log Output Level= 0
Friction Slope Method= 1
Unsteady Friction Slope Method= 2
Unsteady Bridges Friction Slope Method= 1
Parabolic Critical Depth
Global Vel Dist=  1 , 1 , 1
Global Log Level= 0
CheckData=True
Encroach Param= -1, 0, 0, 0
BEGIN DESCRIPTION:
Multiple Run
END DESCRIPTION:

--- CCLC 033.f01 (steady flow) ---

Flow Title=Multiple
Program Version=4.10
Number of Profiles= 7
Profile Names=10-year,25-year,50-year,1pct_min,100-year,1pct_plu,500-year
River Rch & RM=CCLC 033,Reach-1         ,6307
     386     514     688     304     917    2769    1684
River Rch & RM=CCLC 033,Reach-1         ,4859
     687     946    1293     582    1758    5309    3361
Boundary for River Rch & Prof#=CCLC 033,Reach-1         , 1
Up Type= 0
Dn Type= 3
Dn Slope=0.005
Boundary for River Rch & Prof#=CCLC 033,Reach-1         , 2
Up Type= 0
Dn Type= 3
Dn Slope=0.005
Boundary for River Rch & Prof#=CCLC 033,Reach-1         , 3
Up Type= 0
Dn Type= 3
Dn Slope=0.005
Boundary for River Rch & Prof#=CCLC 033,Reach-1         , 4
Up Type= 0
Dn Type= 3
Dn Slope=0.005
Boundary for River Rch & Prof#=CCLC 033,Reach-1         , 5
Up Type= 0
Dn Type= 3
Dn Slope=0.005
Boundary for River Rch & Prof#=CCLC 033,Reach-1         , 6
Up Type= 0
Dn Type= 3
Dn Slope=0.005
Boundary for River Rch & Prof#=CCLC 033,Reach-1         , 7
Up Type= 0
Dn Type= 3
Dn Slope=0.005
DSS Import GetInterval= 0
DSS Import GetPeak= 0
DSS Import FillOption= 0

--- CCLC 033.f02 (steady flow) ---

Flow Title=Orig_BLE_Flows
Program Version=4.10
Number of Profiles= 7
Profile Names=10-year,25-year,50-year,1pct_min,100-year,1pct_plu,500-year
River Rch & RM=CCLC 033,Reach-1         ,6307
     386     504     598     234     705    2130     979
River Rch & RM=CCLC 033,Reach-1         ,4859
     687     927    1124     448    1352    4084    1954
Boundary for River Rch & Prof#=CCLC 033,Reach-1         , 1
Up Type= 0
Dn Type= 3
Dn Slope=0.005
Boundary for River Rch & Prof#=CCLC 033,Reach-1         , 2
Up Type= 0
Dn Type= 3
Dn Slope=0.005
Boundary for River Rch & Prof#=CCLC 033,Reach-1         , 3
Up Type= 0
Dn Type= 3
Dn Slope=0.005
Boundary for River Rch & Prof#=CCLC 033,Reach-1         , 4
Up Type= 0
Dn Type= 3
Dn Slope=0.005
Boundary for River Rch & Prof#=CCLC 033,Reach-1         , 5
Up Type= 0
Dn Type= 3
Dn Slope=0.005
Boundary for River Rch & Prof#=CCLC 033,Reach-1         , 6
Up Type= 0
Dn Type= 3
Dn Slope=0.005
Boundary for River Rch & Prof#=CCLC 033,Reach-1         , 7
Up Type= 0
Dn Type= 3
Dn Slope=0.005
DSS Import GetInterval= 0
DSS Import GetPeak= 0
DSS Import FillOption= 0

--- CCLC 033.g01 (geometry) ---

Geom Title=Existing Conditions
Program Version=4.10

River Reach=CCLC 033        ,Reach-1
Reach XY= 30
      3694898.23     10131751.84      3694957.62     10131850.97
      3694928.04     10131914.07      3694968.58     10132085.59
       3694848.2     10132357.18      3694839.48     10132967.51
      3694893.34     10133394.91      3695085.38     10133523.72
      3695165.02     10133622.83       3695253.7     10133643.33
      3695249.32      10133743.5       3695303.1     10133813.61
      3695322.97     10133921.52      3695474.06     10134162.29
      3695626.22      10134296.7       3695628.9     10134730.67
      3695759.69     10135114.34      3695996.67     10135588.48
      3695980.07     10135655.22      3696061.01     10135837.61
      3696243.04     10136032.09      3696322.27     10136193.73
      3696280.76     10136302.76      3696153.72     10136427.54
      3696053.35      10136612.5      3696028.24     10136725.98
      3696071.25     10136899.35      3696210.66     10137015.36
      3696573.14     10137067.43      3696608.23     10137096.84

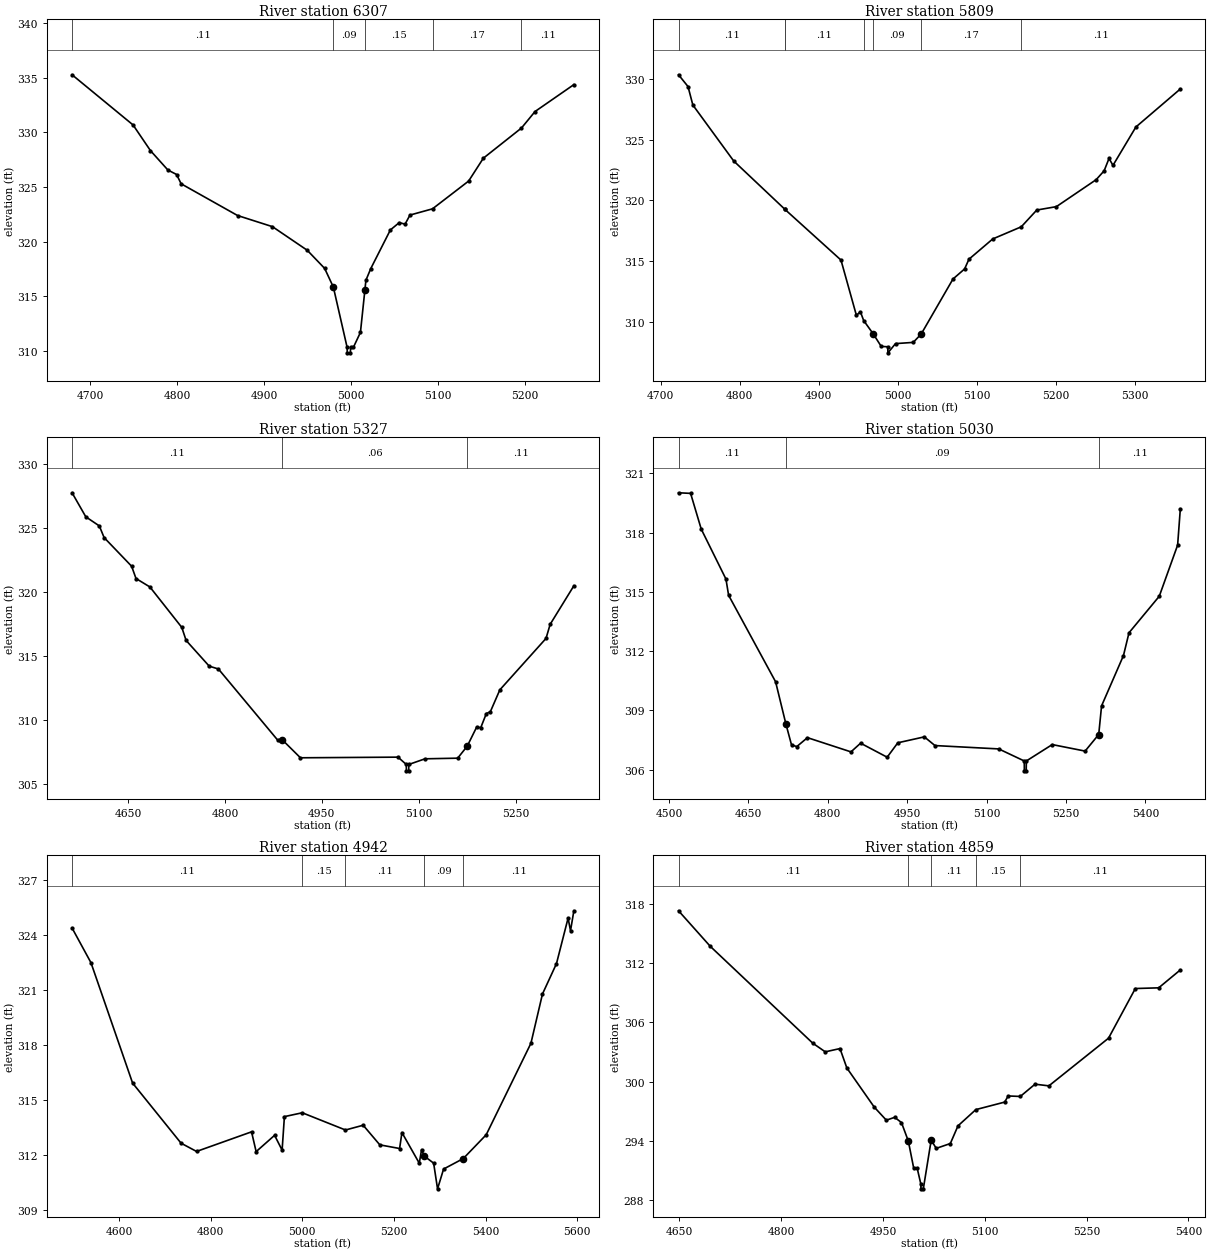
Type RM Length L Ch R = 1 ,6307    ,498,498,498
BEGIN DESCRIPTION:
CCLC 033 10.0
END DESCRIPTION:
XS GIS Cut Line= 3
      3694617.85     10131961.07       3694938.3     10131973.84
      3695167.89     10131861.05
#Sta/Elev= 30
  4679.3  335.27  4749.4  330.68  4769.4  328.33  4789.4  326.56  4799.4  326.15
  4804.6   325.3  4869.4   322.4  4909.5  321.38  4949.5  319.22  4969.5  317.56
  4979.5  315.85  4995.3  310.34  4995.5  309.84    4999  309.84  4999.3  310.34
  5002.5  310.34  5010.6  311.71 5015.77315.6245  5016.9  316.48  5022.5  317.55
    5045  321.08  5055.2  321.75  5061.9  321.61  5067.5  322.44  5093.4  323.01
  5134.9  325.55  5151.8  327.64  5195.6   330.4  5211.2  331.91  5255.8  334.37
#Mann= 5 ,-1 , 0
  4679.3     .11       0  4979.5     .09       0 5015.77     .15       0
  5093.4     .17       0  5195.6     .11       0
Bank Sta=4979.5,5015.77
XS Rating Curve= 0 ,0
Exp/Cntr=0.3,0.1

Type RM Length L Ch R = 1 ,5809    ,482,482,482
BEGIN DESCRIPTION:
CCLC 033 9.0
END DESCRIPTION:
XS GIS Cut Line= 3
       3694576.1     10132372.43      3694848.23     10132425.21
      3695203.72     10132386.41
#Sta/Elev= 30
  4722.8  330.34  4734.8  329.37  4740.9  327.85  4792.6  323.24  4857.2  319.27
  4857.3  319.26  4928.3  315.08  4947.8  310.53  4952.9  310.82    4957   310.1
  4969.1     309  4979.2  307.97  4987.4  307.94  4987.7  307.44  4997.3   308.2
  5019.7   308.3  5029.8  308.99    5070  313.52  5084.7  314.35  5090.2  315.15
  5120.3  316.82  5156.4  317.82    5176   319.2  5200.8  319.48  5251.1   321.7
  5261.2  322.43  5267.4  323.45  5272.4  322.88  5301.4  326.04  5357.6  329.17
#Mann= 7 ,-1 , 0
  4722.8     .11       0  4857.2     .15       0  4857.3     .11       0
    4957     .17       0  4969.1     .09       0  5029.8     .17       0
  5156.4     .11       0
Bank Sta=4969.1,5029.8
XS Rating Curve= 0 ,0
Exp/Cntr=0.3,0.1

Type RM Length L Ch R = 1 ,5327    ,297,297,297
BEGIN DESCRIPTION:
CCLC 033 8.0
END DESCRIPTION:
XS GIS Cut Line= 3
      3694517.85     10132611.07      3694839.48     10132906.63
      3695117.86     10132711.07
#Sta/Elev= 30
  4563.2  327.74  4584.5  325.86  4605.4  325.15  4612.8  324.24  4655.4     322
  4662.2  321.04  4683.7  320.38  4733.1  317.22  4739.8   316.2  4775.6  314.19
  4789.8  313.97  4881.6  308.41    4889  308.42  4916.8  307.03  5067.9  307.08
  5080.7  306.51  5080.9  306.01  5084.4  306.01  5084.7  306.51  5109.7  306.95
  5160.3     307  5175.1  307.94  5189.9  309.45    5196  309.38  5204.7  310.49
  5210.8  310.62  5225.6  312.34  5297.1  316.36  5303.5  317.46  5340.2  320.47
#Mann= 3 , 0 , 0
  4563.2     .11       0    4889     .06       0  5175.1     .11       0
Bank Sta=4889,5175.1
XS Rating Curve= 0 ,0
Exp/Cntr=0.3,0.1

Type RM Length L Ch R = 1 ,5030    ,88,88,88
BEGIN DESCRIPTION:
Mapping XS 9919deca
END DESCRIPTION:
XS GIS Cut Line= 3
      3694385.15     10133243.95      3695065.67     10133184.93
      3695321.52     10133115.78
#Sta/Elev= 30
    4518  320.02  4540.8  319.99  4560.9  318.18  4607.6  315.65  4612.6  314.83
  4701.4  310.45  4720.7  308.33  4731.5  307.25  4741.5  307.17  4761.6  307.62
  4843.8   306.9    4862  307.34  4912.2  306.63  4932.3  307.36  4982.4  307.66
  5002.5  307.22    5123  307.05  5171.2  306.44  5171.4  305.94  5174.9  305.94
  5175.2  306.44  5224.1  307.27  5286.2  306.94  5311.9  307.78  5317.3  309.23
  5358.7  311.78  5369.1  312.93  5426.3  314.78    5461  317.37  5466.1  319.21
#Mann= 3 , 0 , 0
    4518     .11       0  4720.7     .09       0  5311.9     .11       0
Bank Sta=4720.7,5311.9
XS Rating Curve= 0 ,0
Exp/Cntr=0.3,0.1

Type RM Length L Ch R = 1 ,4942    ,83,83,83
BEGIN DESCRIPTION:
Mapping XS d64c00e2
END DESCRIPTION:
XS GIS Cut Line= 6
      3694381.68     10133355.06      3694593.45     10133306.45
      3694791.36     10133302.98      3694923.31     10133282.15
      3695218.45     10133216.18      3695447.64     10133132.83
#Sta/Elev= 30
  4497.6  324.38  4538.8  322.49  4629.7  315.92  4735.5  312.64  4769.3  312.19
  4889.3  313.26  4899.3  312.18  4939.6  313.07    4956  312.26    4961  314.09
    5000   314.3  5094.3  313.36  5132.9  313.62  5169.2  312.55  5212.4  312.35
  5217.5  313.22  5255.3  311.55  5260.4  312.29  5266.1  311.94  5286.7  311.55
  5295.2  310.15  5308.4  311.23  5351.3   311.8  5401.4   313.1    5499  318.09
  5524.2  320.78  5554.8  322.44  5580.1  324.92  5585.4  324.23  5592.7  325.32
#Mann= 5 ,-1 , 0
  4497.6     .11       0    5000     .15       0  5094.3     .11       0
  5266.1     .09       0  5351.3     .11       0
Bank Sta=5266.1,5351.3
XS Rating Curve= 0 ,0
Exp/Cntr=0.3,0.1

Type RM Length L Ch R = 1 ,4859    ,380,380,380
BEGIN DESCRIPTION:
CCLC 033 7.0
END DESCRIPTION:
XS GIS Cut Line= 3
       3694541.4     10133410.62      3694888.58     10133371.56
      3695264.56     10133267.84
#Sta/Elev= 30
  4648.6  317.27  4695.3  313.68  4846.3  303.89  4864.8  303.01  4886.5  303.34
  4896.6  301.38  4936.9  297.43  4954.8   296.1  4967.1  296.39  4977.1  295.86
  4987.2  293.99  4995.1  291.26  5000.2  291.26  5005.6  289.66  5005.8  289.16
  5009.3  289.16  5020.9  294.09  5028.3  293.25  5049.1  293.74  5060.4  295.53
  5086.7  297.17  5129.2  297.93  5134.3  298.55  5152.2   298.5  5173.9  299.74
  5194.3  299.57  5282.2  304.39  5321.7  309.41  5356.1  309.48    5388  311.29
#Mann= 5 ,-1 , 0
  4648.6     .11       0  4987.2     .06       0  5020.9     .11       0
  5086.7     .15       0  5152.2     .11       0
Bank Sta=4987.2,5020.9
XS Rating Curve= 0 ,0
Exp/Cntr=0.3,0.1

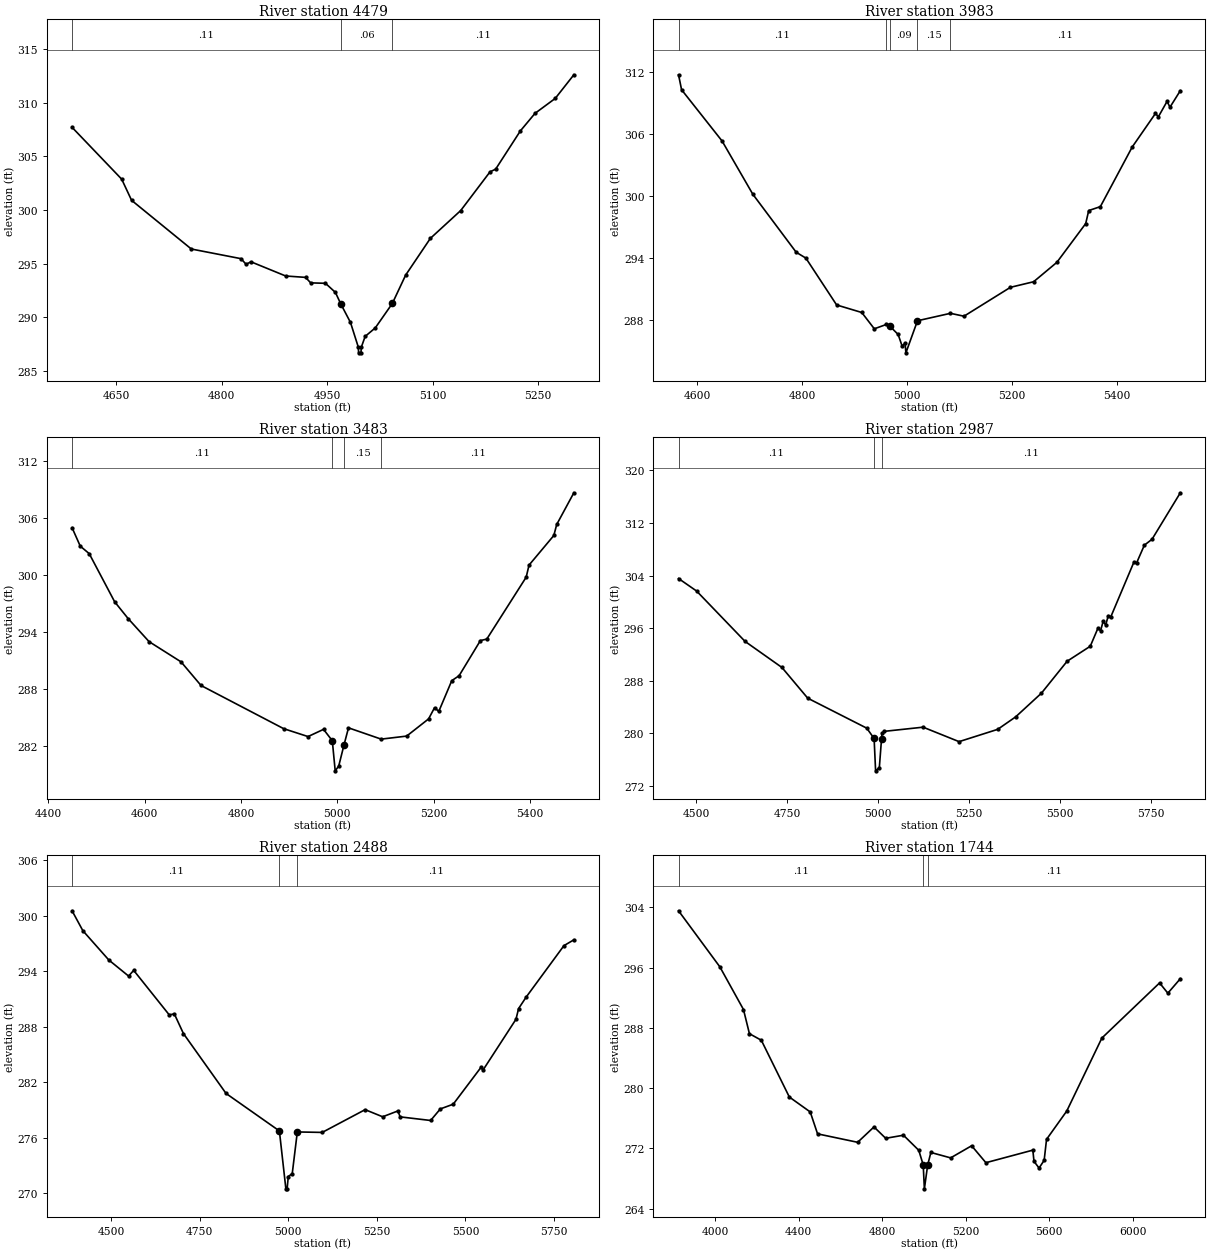
Type RM Length L Ch R = 1 ,4479    ,496,496,496
BEGIN DESCRIPTION:
CCLC 033 6.0
END DESCRIPTION:
XS GIS Cut Line= 3
      3694867.88     10133911.05      3695151.57     10133610.77
      3695339.91     10133375.97
#Sta/Elev= 30
  4586.9  307.69  4657.5  302.87  4671.6   300.9  4756.6  296.37  4827.4  295.47
  4834.5  294.95  4841.5  295.18  4890.9  293.86  4919.2  293.73  4926.5  293.22
  4947.5  293.18  4961.7  292.33    4969   291.3  4983.1  289.54  4994.4  287.21
  4994.6  286.71  4998.1  286.71  4998.4  287.21    5004  288.24  5018.4  289.03
 5042.68291.3047  5061.6  293.94  5096.8  297.36    5140  299.95  5181.7  303.55
  5189.7   303.8  5224.9  307.36  5245.7  308.99  5274.5  310.38    5301  312.58
#Mann= 3 , 0 , 0
  4586.9     .11       0    4969     .06       0 5042.68     .11       0
Bank Sta=4969,5042.68
XS Rating Curve= 0 ,0
Exp/Cntr=0.3,0.1

Type RM Length L Ch R = 1 ,3983    ,500,500,500
BEGIN DESCRIPTION:
CCLC 033 5.0
END DESCRIPTION:
XS GIS Cut Line= 3
      3694971.06     10134139.78      3695373.37     10133973.56
      3695613.13       10133511.
#Sta/Elev= 30
  4564.7  311.72  4570.5  310.27  4647.7   305.3  4706.3  300.14  4788.9  294.52
  4807.4  293.95    4866  289.41  4913.9  288.68  4937.8   287.1  4960.7  287.52
  4967.1  287.37  4983.2  286.55    4991   285.4  4996.4  285.73    4998  284.77
  5020.1  287.88  5082.9   288.6  5108.7  288.32  5197.2  291.12  5241.4  291.66
  5285.7  293.54  5340.7   297.3  5346.4  298.56  5368.6  298.94  5429.3  304.72
  5473.6  307.97  5479.2  307.65  5495.7  309.14  5501.3  308.58    5521  310.18
#Mann= 5 ,-1 , 0
  4564.7     .11       0  4960.7     .15       0  4967.1     .09       0
  5020.1     .15       0  5082.9     .11       0
Bank Sta=4967.1,5020.1
XS Rating Curve= 0 ,0
Exp/Cntr=0.3,0.1

Type RM Length L Ch R = 1 ,3483    ,496,496,496
BEGIN DESCRIPTION:
CCLC 033 4.0
END DESCRIPTION:
XS GIS Cut Line= 3
      3695092.61     10134447.94      3695638.21     10134371.67
      3696050.97     10134105.58
#Sta/Elev= 30
  4449.1  304.95  4466.1  303.01  4484.7  302.22  4537.5  297.15  4565.5  295.38
    4609  292.95  4675.4  290.82  4716.9  288.33  4888.6  283.78  4939.1  282.95
  4971.3  283.71  4989.5  282.51  4995.5  279.34  5002.8  279.84  5013.9  282.09
  5023.1  283.87    5091  282.68  5143.9     283  5189.4  284.81  5201.8  285.99
  5210.6   285.6  5237.6  288.84  5252.8  289.36    5297  293.06  5310.3  293.22
  5392.1  299.74    5398  301.01  5449.5  304.13  5455.5  305.29  5491.1  308.63
#Mann= 4 ,-1 , 0
  4449.1     .11       0  4989.5     .06       0  5013.9     .15       0
    5091     .11       0
Bank Sta=4989.5,5013.9
XS Rating Curve= 0 ,0
Exp/Cntr=0.3,0.1

Type RM Length L Ch R = 1 ,2987    ,499,499,499
BEGIN DESCRIPTION:
CCLC 033 3.0
END DESCRIPTION:
XS GIS Cut Line= 3
       3695127.3     10134747.43      3695668.58     10134836.76
      3696267.86     10134261.07
#Sta/Elev= 30
  4451.4  303.57    4501  301.67  4634.4     294  4735.7  290.04  4806.6  285.37
  4968.9  280.81  4989.1  279.24  4993.2  274.32  5003.5  274.82 5009.59 279.235
  5010.7  280.04  5017.6  280.33  5123.8  280.96  5222.7  278.76  5328.9  280.63
  5378.3  282.53  5449.1  286.13  5519.8  290.99  5583.4  293.27  5604.7  296.04
  5611.7  295.61  5618.9  297.08  5625.8   296.5    5633  297.93    5640  297.76
  5703.8  306.12  5710.7  305.93  5732.1  308.64  5753.2  309.54    5831  316.61
#Mann= 3 , 0 , 0
  4451.4     .11       0  4989.1     .06       0 5009.59     .11       0
Bank Sta=4989.1,5009.59
XS Rating Curve= 0 ,0
Exp/Cntr=0.3,0.1

Type RM Length L Ch R = 1 ,2488    ,744,744,744
BEGIN DESCRIPTION:
CCLC 033 2.0
END DESCRIPTION:
XS GIS Cut Line= 3
      3695244.49     10135233.54      3695852.92     10135281.27
      3696367.85     10134661.07
#Sta/Elev= 30
  4389.7  300.52  4420.1  298.37  4493.4   295.2  4549.3  293.46  4563.6  294.08
  4663.9  289.27  4678.4  289.37    4704  287.25  4824.4  280.77  4974.9  276.72
  4993.2  270.46  4996.7  270.46    5000  271.79  5011.2  272.11  5025.5  276.61
  5095.8  276.56  5216.9  279.02  5266.4  278.25  5309.3  278.88  5315.8  278.24
  5401.8  277.85  5429.2   279.1  5465.6  279.61  5543.7  283.58  5550.2  283.33
  5642.7  288.79  5650.1  289.95  5671.3  291.18  5778.1  296.75  5806.1  297.38
#Mann= 3 , 0 , 0
  4389.7     .11       0  4974.9     .06       0  5025.5     .11       0
Bank Sta=4974.9,5025.5
XS Rating Curve= 0 ,0
Exp/Cntr=0.3,0.1

Type RM Length L Ch R = 1 ,1744    ,791,791,791
BEGIN DESCRIPTION:
Mapping XS 7235bd52
END DESCRIPTION:
XS GIS Cut Line= 4
      3695227.14     10135363.76      3695986.67     10136014.79
      3696372.96     10135776.07      3696719.97     10134895.54
#Sta/Elev= 30
  3825.7  303.56  4023.3  296.12  4136.4  290.45  4164.9  287.24  4221.8  286.37
  4355.9  278.83  4455.8  276.85  4490.9  273.94  4682.7  272.82  4760.9  274.86
  4816.9  273.35  4901.8  273.76  4975.1  271.76  4996.4  269.82    5002  266.64
  5017.6  269.78    5033  271.47  5127.6  270.75  5228.1  272.36  5296.3  270.11
    5521  271.78  5526.4  270.29  5550.7   269.4  5575.1  270.43  5586.5  273.21
  5683.2  276.97  5851.2  286.66  6127.3  293.98  6166.9  292.62  6226.6  294.54
#Mann= 3 , 0 , 0
  3825.7     .11       0  4996.4     .06       0  5017.6     .11       0
Bank Sta=4996.4,5017.6
XS Rating Curve= 0 ,0
Exp/Cntr=0.3,0.1

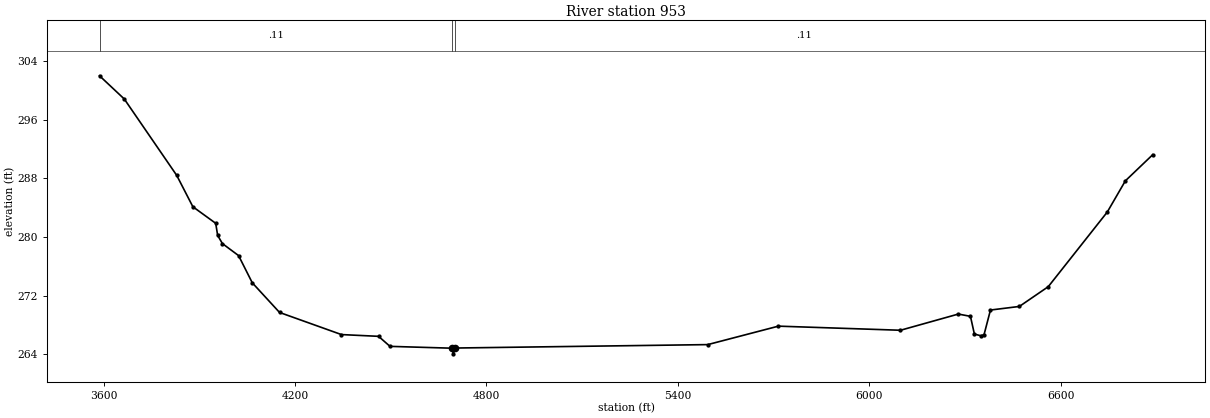
Type RM Length L Ch R = 1 ,953     ,0,0,0
BEGIN DESCRIPTION:
CCLC 033 1.0
END DESCRIPTION:
XS GIS Cut Line= 4
      3695205.45     10135507.01      3695921.57      10136544.3
      3696520.53     10136613.75      3696689.79     10135185.89
#Sta/Elev= 30
  3587.2  302.01  3664.8  298.84  3829.1  288.42  3879.8  284.13  3951.4  281.87
  3957.5  280.22  3972.4   279.1  4023.1  277.46    4066  273.75  4151.5   269.7
  4345.5  266.68  4461.8  266.44  4497.7  265.07  4691.7  264.82  4696.2  264.05
 4702.75264.8435  5493.6  265.31  5715.2  267.83  6097.8  267.27  6279.1  269.48
  6317.1  269.17  6329.4  266.75  6349.6  266.52  6359.6  266.65  6379.8  270.03
  6470.4  270.52    6561  273.22    6746  283.41  6802.7  287.67  6888.5  291.24
#Mann= 3 ,-1 , 0
  3587.2     .11       0  4691.7     .06       0 4702.75     .11       0
Bank Sta=4691.7,4702.75
XS Rating Curve= 0 ,0
Exp/Cntr=0.3,0.1

Chan Stop Cuts=-1
Use User Specified Reach Order=0
Composite Channel Slope=5