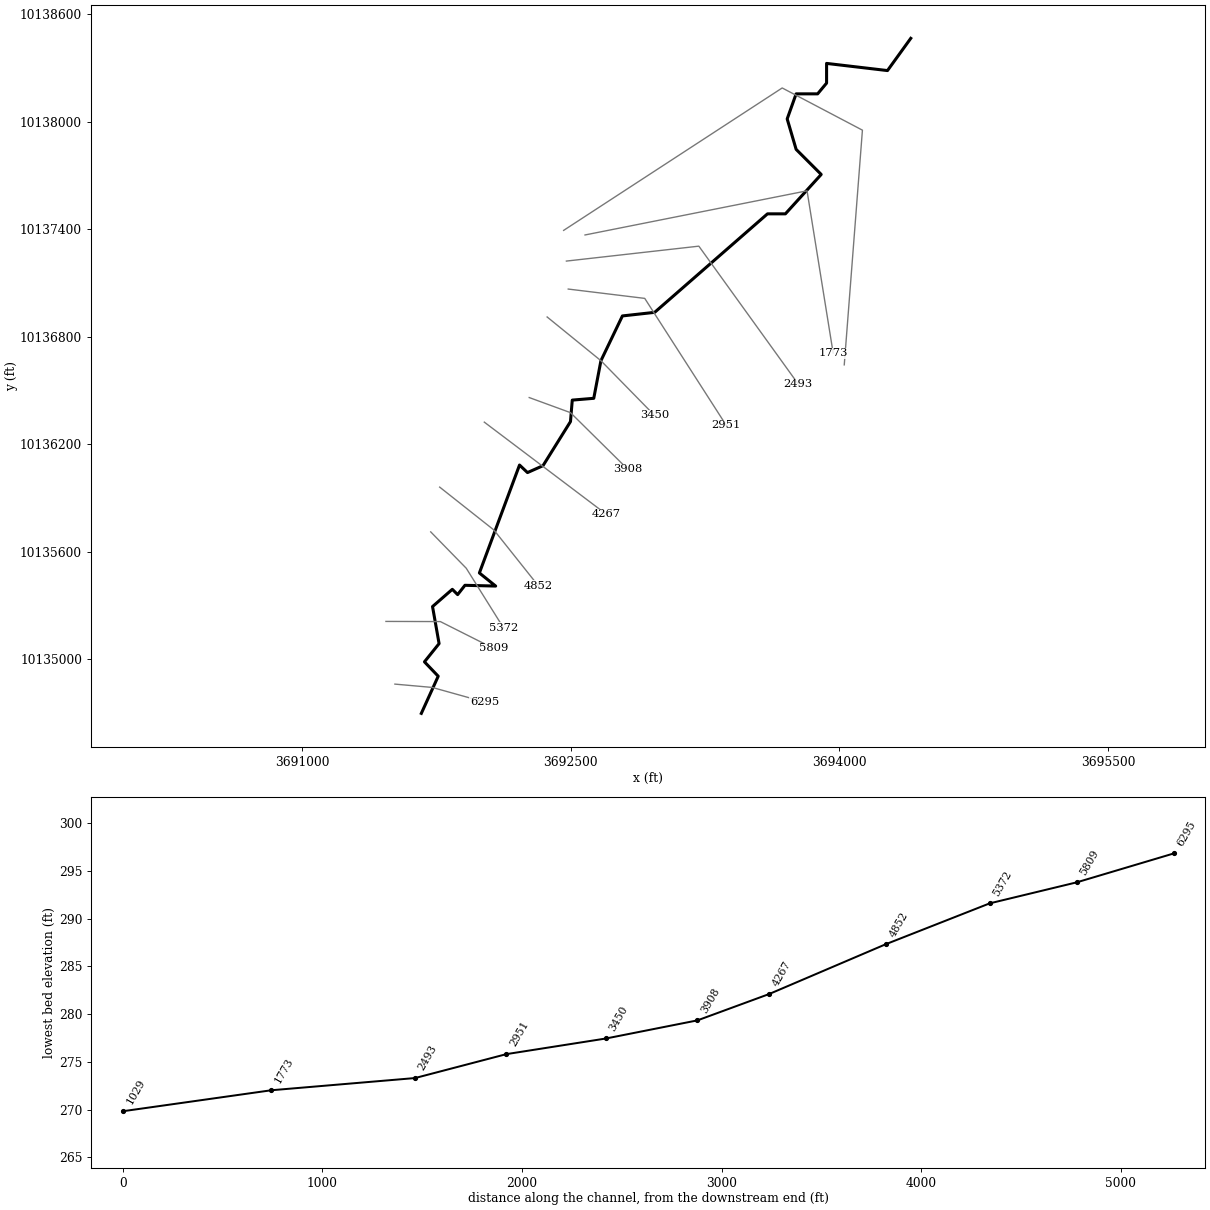
--- CCLC 034.prj (project) ---

Proj Title=CCLC 034 Base Level Engineering
Current Plan=p01
Default Exp/Contr=0.3,0.1
English Units
Geom File=g01
Flow File=f01
Flow File=f02
Plan File=p01
Y Axis Title=Elevation
X Axis Title(PF)=Main Channel Distance
X Axis Title(XS)=Station
BEGIN DESCRIPTION:
CCLC 034
END DESCRIPTION:
DSS Export Rating Curves= 0
DSS Export Rating Curve Sorted= 0
DSS Export Volume Flow Curves= 0
DXF OffsetX= 0
DXF OffsetY= 0
DXF ScaleX= 1
DXF ScaleY= 10

--- CCLC 034.p01 (plan) ---

Plan Title=Multiple Run
Short Identifier=Multiple
Geom File=g01
Flow File=f01
Subcritical Flow
K Sum by GR= 0
Std Step Tol= 0.01
Critical Tol= 0.01
Num of Std Step Trials= 20
Max Error Tol= 0.3
Flow Tol Ratio= 0.001
Split Flow NTrial= 30
Split Flow Tol= 0.02
Split Flow Ratio= 0.02
Log Output Level= 0
Friction Slope Method= 1
Unsteady Friction Slope Method= 2
Unsteady Bridges Friction Slope Method= 1
Parabolic Critical Depth
Global Vel Dist=  1 , 1 , 1
Global Log Level= 0
CheckData=True
Encroach Param= -1, 0, 0, 0
BEGIN DESCRIPTION:
Multiple Run
END DESCRIPTION:

--- CCLC 034.f01 (steady flow) ---

Flow Title=Multiple
Program Version=4.10
Number of Profiles= 7
Profile Names=10-year,25-year,50-year,1pct_min,100-year,1pct_plu,500-year
River Rch & RM=CCLC 034,Reach-1         ,6295
     591     802    1086     484    1461    4412    2738
Boundary for River Rch & Prof#=CCLC 034,Reach-1         , 1
Up Type= 0
Dn Type= 3
Dn Slope=0.005
Boundary for River Rch & Prof#=CCLC 034,Reach-1         , 2
Up Type= 0
Dn Type= 3
Dn Slope=0.005
Boundary for River Rch & Prof#=CCLC 034,Reach-1         , 3
Up Type= 0
Dn Type= 3
Dn Slope=0.005
Boundary for River Rch & Prof#=CCLC 034,Reach-1         , 4
Up Type= 0
Dn Type= 3
Dn Slope=0.005
Boundary for River Rch & Prof#=CCLC 034,Reach-1         , 5
Up Type= 0
Dn Type= 3
Dn Slope=0.005
Boundary for River Rch & Prof#=CCLC 034,Reach-1         , 6
Up Type= 0
Dn Type= 3
Dn Slope=0.005
Boundary for River Rch & Prof#=CCLC 034,Reach-1         , 7
Up Type= 0
Dn Type= 3
Dn Slope=0.005
DSS Import GetInterval= 0
DSS Import GetPeak= 0
DSS Import FillOption= 0

--- CCLC 034.f02 (steady flow) ---

Flow Title=Orig_BLE_Flows
Program Version=4.10
Number of Profiles= 7
Profile Names=10-year,25-year,50-year,1pct_min,100-year,1pct_plu,500-year
River Rch & RM=CCLC 034,Reach-1         ,6295
     591     786     944     372    1124    3395    1592
Boundary for River Rch & Prof#=CCLC 034,Reach-1         , 1
Up Type= 0
Dn Type= 3
Dn Slope=0.005
Boundary for River Rch & Prof#=CCLC 034,Reach-1         , 2
Up Type= 0
Dn Type= 3
Dn Slope=0.005
Boundary for River Rch & Prof#=CCLC 034,Reach-1         , 3
Up Type= 0
Dn Type= 3
Dn Slope=0.005
Boundary for River Rch & Prof#=CCLC 034,Reach-1         , 4
Up Type= 0
Dn Type= 3
Dn Slope=0.005
Boundary for River Rch & Prof#=CCLC 034,Reach-1         , 5
Up Type= 0
Dn Type= 3
Dn Slope=0.005
Boundary for River Rch & Prof#=CCLC 034,Reach-1         , 6
Up Type= 0
Dn Type= 3
Dn Slope=0.005
Boundary for River Rch & Prof#=CCLC 034,Reach-1         , 7
Up Type= 0
Dn Type= 3
Dn Slope=0.005
DSS Import GetInterval= 0
DSS Import GetPeak= 0
DSS Import FillOption= 0

--- CCLC 034.g01 (geometry) ---

Geom Title=Existing Conditions
Program Version=4.10

River Reach=CCLC 034        ,Reach-1
Reach XY= 30
      3691665.44     10134697.64      3691759.72     10134905.12
      3691682.85     10134985.41      3691764.57      10135087.2
        3691728.     10135293.98      3691838.49     10135390.32
      3691868.18     10135360.79        3691909.     10135412.78
      3692080.49      10135408.5      3691989.62     10135481.67
      3692213.74     10136084.29      3692258.21     10136042.19
      3692344.76     10136080.62      3692498.23     10136326.84
      3692508.23     10136446.84      3692628.23     10136456.84
      3692668.23     10136666.84      3692788.23     10136916.84
      3692968.23     10136936.84      3693598.23     10137486.84
      3693698.23     10137486.84      3693898.23     10137706.84
      3693758.23     10137846.84      3693708.23     10138016.84
      3693758.23     10138156.84      3693878.23     10138156.84
      3693928.23     10138216.84      3693928.23     10138326.84
      3694268.23     10138286.84      3694398.23     10138466.84

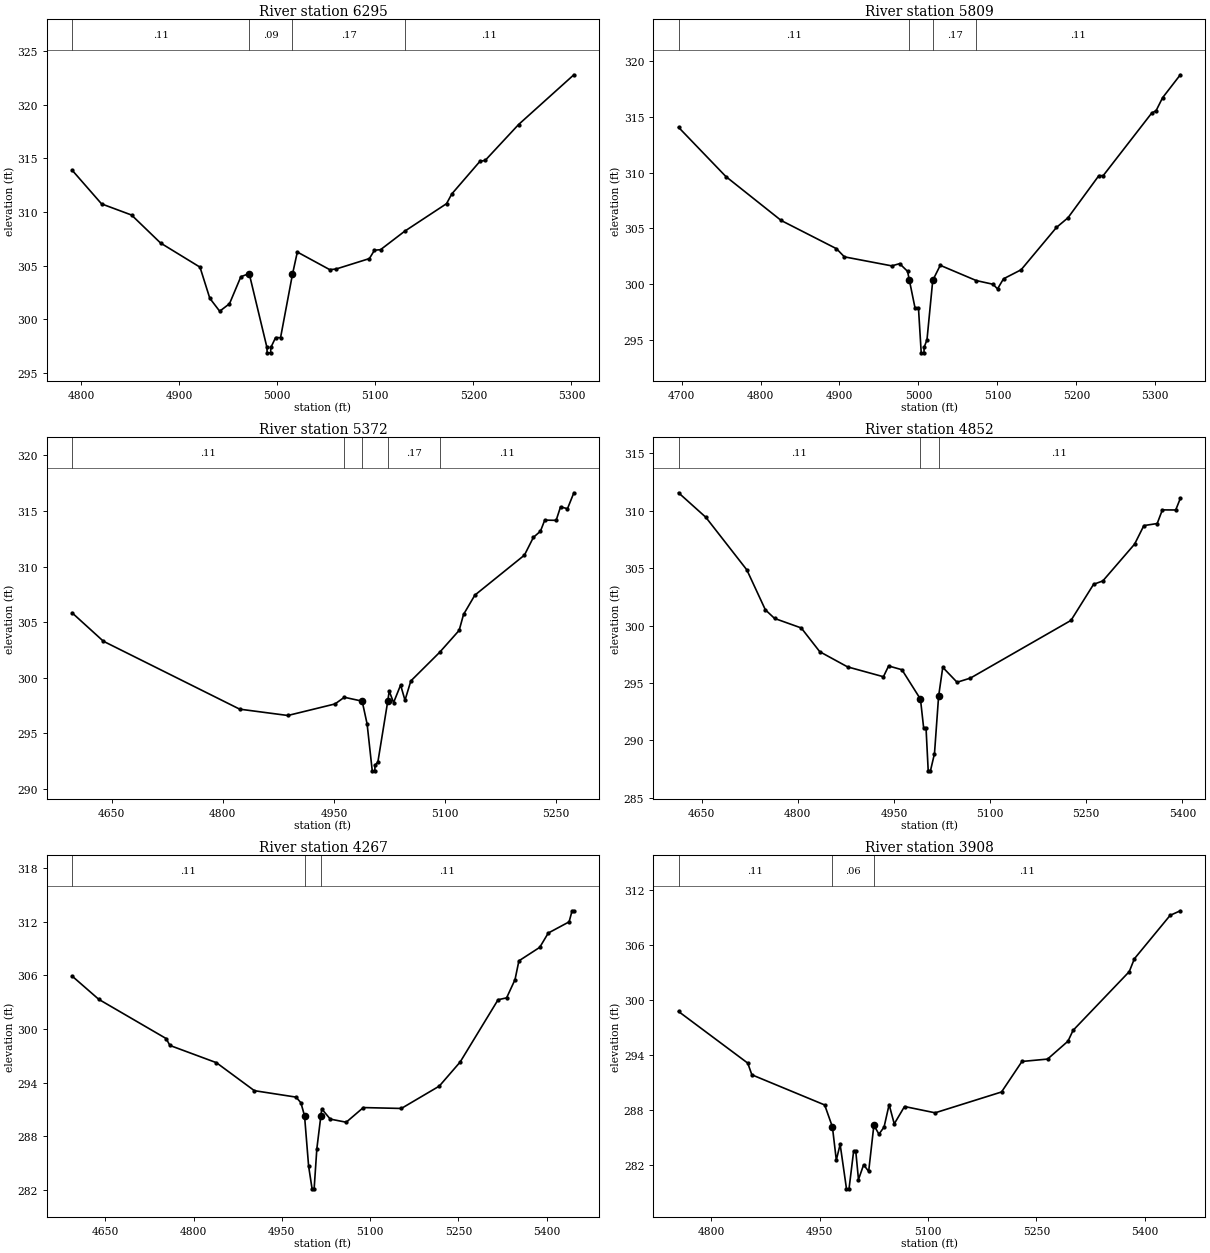
Type RM Length L Ch R = 1 ,6295    ,486,486,486
BEGIN DESCRIPTION:
CCLC 034 8.0
END DESCRIPTION:
XS GIS Cut Line= 3
      3691517.89     10134861.07      3691726.46     10134842.46
      3692017.81     10134761.08
#Sta/Elev= 30
  4790.6   313.9  4820.7  310.75  4851.3  309.71  4880.9   307.1  4921.1  304.85
  4931.1  301.95  4941.2  300.74  4951.2  301.44  4962.8  303.96  4971.3  304.25
  4989.4  297.36  4989.6  296.86  4993.1  296.86  4993.4  297.36  4998.2  298.28
  5003.3  298.28 5015.42304.1754  5020.4  306.26  5053.4  304.62  5059.7  304.67
  5093.9  305.65  5099.1  306.43  5105.3  306.48  5129.9   308.2  5172.6  310.77
    5178  311.68  5206.8  314.73    5212   314.8  5246.1  318.15  5302.5  322.79
#Mann= 4 ,-1 , 0
  4790.6     .11       0  4971.3     .09       0 5015.42     .17       0
  5129.9     .11       0
Bank Sta=4971.3,5015.42
XS Rating Curve= 0 ,0
Exp/Cntr=0.3,0.1

Type RM Length L Ch R = 1 ,5809    ,437,437,437
BEGIN DESCRIPTION:
CCLC 034 7.0
END DESCRIPTION:
XS GIS Cut Line= 3
       3691467.9     10135211.07       3691771.7     10135210.21
      3692067.87     10135061.06
#Sta/Elev= 30
  4696.2  314.06  4756.2  309.64  4826.2   305.7  4896.2  303.17  4906.2  302.44
  4966.2  301.63  4976.2  301.83  4986.2  301.14 4988.52300.3355  4995.6  297.88
    5000  297.88  5003.5  293.83    5007  293.83  5007.2  294.33  5010.8     295
  5018.1  300.33  5027.6  301.68  5073.3  300.31  5094.5  299.98  5100.1  299.56
  5107.7  300.47    5130  301.28  5174.8  305.08  5189.3  305.94  5228.4  309.72
    5234  309.73  5295.3  315.33  5300.9  315.55  5309.2  316.72  5331.6  318.77
#Mann= 4 ,-1 , 0
  4696.2     .11       0 4988.52     .06       0  5018.1     .17       0
  5073.3     .11       0
Bank Sta=4988.52,5018.1
XS Rating Curve= 0 ,0
Exp/Cntr=0.3,0.1

Type RM Length L Ch R = 1 ,5372    ,520,520,520
BEGIN DESCRIPTION:
CCLC 034 6.0
END DESCRIPTION:
XS GIS Cut Line= 3
      3691717.86     10135711.07      3691916.36     10135507.84
      3692124.71     10135174.48
#Sta/Elev= 30
  4596.6  305.84  4638.9  303.28  4822.8  297.17  4887.8   296.6  4951.5  297.64
    4964  298.24  4988.1  297.89  4994.8  295.83  5001.7  291.62  5005.2  291.62
  5005.4  292.12  5009.3  292.41 5022.62297.8803  5024.6   298.8  5030.5  297.76
    5040  299.34  5045.9  297.97  5053.8  299.71  5092.6  302.28    5119  304.26
  5124.9  305.69  5140.2  307.43  5207.1  311.03  5219.2  312.63  5228.7  313.18
  5234.5  314.18  5249.9  314.16  5255.8  315.37  5265.2  315.21  5273.8  316.64
#Mann= 5 ,-1 , 0
  4596.6     .11       0    4964     .17       0  4988.1     .09       0
 5022.62     .17       0  5092.6     .11       0
Bank Sta=4988.1,5022.62
XS Rating Curve= 0 ,0
Exp/Cntr=0.3,0.1

Type RM Length L Ch R = 1 ,4852    ,585,585,585
BEGIN DESCRIPTION:
CCLC 034 5.0
END DESCRIPTION:
XS GIS Cut Line= 3
      3691767.84     10135961.08      3692070.75     10135721.51
      3692317.87     10135411.05
#Sta/Elev= 30
  4613.8  311.57  4656.3  309.44  4720.4  304.85  4749.3  301.37  4763.7  300.62
  4805.3  299.79  4834.2  297.72  4877.5   296.4  4933.5  295.54  4941.6  296.48
  4962.4  296.15  4991.3  293.59  4996.3  291.07    5000  291.07  5003.4  287.34
  5006.9  287.34  5013.2  288.85  5019.6  293.83  5026.1  296.36  5048.4  295.06
  5069.2  295.42  5226.2  300.45  5261.4  303.59  5275.9  303.89  5325.5   307.1
  5339.9  308.71  5360.7  308.89  5368.8  310.08  5389.6  310.07  5396.8  311.08
#Mann= 3 , 0 , 0
  4613.8     .11       0  4991.3     .06       0  5019.6     .11       0
Bank Sta=4991.3,5019.6
XS Rating Curve= 0 ,0
Exp/Cntr=0.3,0.1

Type RM Length L Ch R = 1 ,4267    ,359,359,359
BEGIN DESCRIPTION:
Mapping XS 95ebb0bd
END DESCRIPTION:
XS GIS Cut Line= 2
      3692017.05     10136323.82      3692697.62     10135809.92
#Sta/Elev= 30
  4593.5  305.91    4639   303.3  4753.4  298.92  4759.7  298.15  4838.8  296.22
  4903.3  293.09  4974.1  292.37  4982.4  291.74  4988.6  290.27  4995.5  284.66
  5001.4  282.11  5004.9  282.11  5009.5   286.6 5016.25290.2191  5017.8  291.05
  5032.3  289.91  5059.4  289.56  5088.5   291.2  5153.1   291.1  5217.6   293.6
    5253  296.29  5317.5  303.26    5332  303.47  5346.3  305.51  5352.9  307.61
  5388.3  309.12  5402.8  310.72  5438.2  311.97  5443.3  313.21  5446.3  313.21
#Mann= 3 , 0 , 0
  4593.5     .11       0  4988.6     .06       0 5016.25     .11       0
Bank Sta=4988.6,5016.25
XS Rating Curve= 0 ,0
Exp/Cntr=0.3,0.1

Type RM Length L Ch R = 1 ,3908    ,458,458,458
BEGIN DESCRIPTION:
CCLC 034 4.0
END DESCRIPTION:
XS GIS Cut Line= 3
      3692267.84     10136461.07      3692498.23     10136376.84
      3692817.85     10136061.07
#Sta/Elev= 30
  4754.7  298.76  4850.5  293.11  4856.2  291.83    4957  288.53  4967.7  286.13
  4973.1   282.5  4978.4  284.22  4987.2  279.35  4990.7  279.35  4997.1  283.49
    5000  283.49  5003.8  280.37  5010.9  281.98  5017.9  281.26  5025.1  286.31
  5032.1  285.33  5039.2  286.11  5046.2  288.57  5053.3  286.46  5067.5  288.36
  5109.9  287.67  5201.8  289.95  5230.1  293.29  5265.5  293.55  5293.8  295.51
  5300.8  296.69  5378.6  303.12  5385.7  304.53  5435.2  309.28  5449.3  309.78
#Mann= 3 , 0 , 0
  4754.7     .11       0  4967.7     .06       0  5025.1     .11       0
Bank Sta=4967.7,5025.1
XS Rating Curve= 0 ,0
Exp/Cntr=0.3,0.1

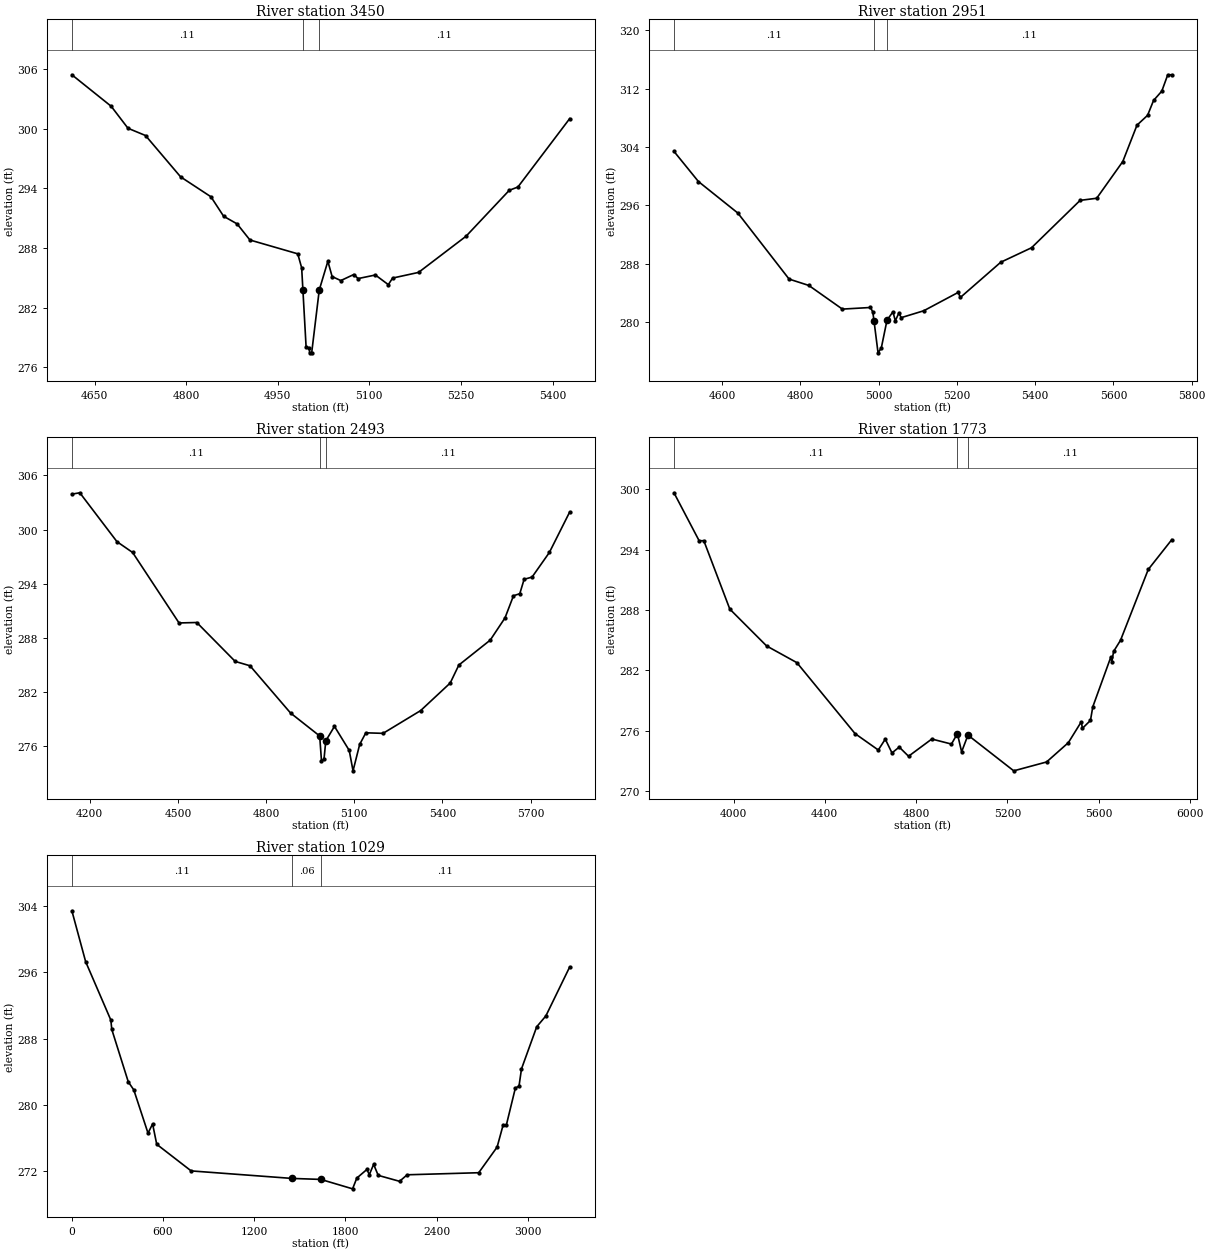
Type RM Length L Ch R = 1 ,3450    ,499,499,499
BEGIN DESCRIPTION:
CCLC 034 3.0
END DESCRIPTION:
XS GIS Cut Line= 3
      3692367.88     10136911.05      3692668.23     10136666.84
      3692967.85     10136361.07
#Sta/Elev= 30
  4612.9  305.42  4677.3  302.25  4704.8  300.04  4733.5  299.31    4791  295.15
  4840.6  293.15  4861.4  291.19  4883.5  290.42  4904.5   288.8  4982.8  287.41
  4989.2     286 4991.24283.7643  4996.5     278  5001.8  277.95  5002.1  277.45
  5005.6  277.45    5018  283.77  5032.1  286.66  5039.1  285.12  5053.3  284.72
  5074.6  285.33  5081.6  284.92  5109.9  285.28  5131.1  284.31  5138.1  284.97
  5180.6  285.54  5258.4  289.18  5329.2   293.8  5343.3  294.13  5428.1  301.01
#Mann= 3 , 0 , 0
  4612.9     .11       0 4991.24     .06       0    5018     .11       0
Bank Sta=4991.24,5018
XS Rating Curve= 0 ,0
Exp/Cntr=0.3,0.1

Type RM Length L Ch R = 1 ,2951    ,458,458,458
BEGIN DESCRIPTION:
CCLC 034 2.0
END DESCRIPTION:
XS GIS Cut Line= 3
      3692485.78     10137066.87      3692912.89     10137014.79
      3693367.76     10136306.43
#Sta/Elev= 30
  4477.1   303.4  4539.6  299.27  4640.4  294.95  4771.3  285.91  4821.7  285.04
  4907.4   281.8  4979.2  282.02  4985.2  281.41 4988.27280.1887  4998.6  275.81
  5006.9  276.47  5021.5  280.28  5036.7  281.43  5042.7   280.2  5051.9  281.27
  5057.8  280.63  5115.3  281.57  5203.2  284.08  5209.1   283.4  5312.2  288.22
  5390.8   290.2    5515  296.69  5557.3  296.98    5624  302.01  5660.3  306.99
  5687.4  308.34  5702.6  310.37  5723.7  311.65  5738.9  313.89  5749.2  313.89
#Mann= 3 , 0 , 0
  4477.1     .11       0 4988.27     .06       0  5021.5     .11       0
Bank Sta=4988.27,5021.5
XS Rating Curve= 0 ,0
Exp/Cntr=0.3,0.1

Type RM Length L Ch R = 1 ,2493    ,720,720,720
BEGIN DESCRIPTION:
Mapping XS 639f2baf
END DESCRIPTION:
XS GIS Cut Line= 3
      3692475.42     10137223.12      3693214.97     10137306.45
      3693770.35     10136535.86
#Sta/Elev= 30
  4139.1  303.93  4166.1  304.08  4292.5  298.67  4345.9  297.47  4503.8  289.67
  4564.2  289.72    4695  285.41  4745.3  284.93  4883.3   279.7  4982.4  277.16
  4988.6  274.38  4997.1  274.58  5003.2  276.62  5032.7  278.22    5083  275.56
  5095.9   273.3  5118.6  276.23  5139.5  277.51  5198.1  277.45    5326  279.97
  5426.6  283.02    5456  285.01  5562.8  287.77  5613.1  290.23  5641.9  292.68
  5663.4  292.91  5678.1   294.5  5705.2  294.75    5764  297.47  5833.2  301.95
#Mann= 3 , 0 , 0
  4139.1     .11       0  4982.4     .06       0  5003.2     .11       0
Bank Sta=4982.4,5003.2
XS Rating Curve= 0 ,0
Exp/Cntr=0.3,0.1

Type RM Length L Ch R = 1 ,1773    ,744,744,744
BEGIN DESCRIPTION:
CCLC 034 1.0
END DESCRIPTION:
XS GIS Cut Line= 3
      3692579.52     10137368.95      3693819.14     10137615.48
      3693964.97     10136709.23
#Sta/Elev= 30
    3739  299.65  3849.4  294.88  3869.8  294.89  3983.8  288.09  4145.1  284.43
  4277.7  282.77  4532.6  275.72  4634.5  274.09  4665.1  275.17  4694.5   273.8
  4726.3  274.38  4767.1  273.47    4869  275.18  4955.2  274.68  4981.2  275.72
  4999.7  273.91 5027.56  275.57  5228.2  272.02    5372   272.9  5467.5  274.82
  5523.9  276.88  5529.4  276.25  5564.4  277.03  5574.6  278.38  5653.1  283.29
  5658.2  282.86  5665.7  283.88  5696.1  284.99  5817.7  292.03  5920.8  294.99
#Mann= 3 , 0 , 0
    3739     .11       0  4981.2     .06       0 5027.56     .11       0
Bank Sta=4981.2,5027.56
XS Rating Curve= 0 ,0
Exp/Cntr=0.3,0.1

Type RM Length L Ch R = 1 ,1029    ,0,0,0
XS GIS Cut Line= 4
      3692460.06     10137394.52      3693680.43     10138189.77
      3694128.35     10137954.09       3694026.9     10136643.66
#Sta/Elev= 30
       0  303.46    90.7   297.3   256.6  290.23   262.6  289.11   371.3  282.76
   407.5  281.79     501  276.56   531.3  277.67   558.4  275.21   784.8  271.99
  1448.7  271.08  1638.3  270.96  1847.3  269.82    1875  271.12  1941.1  272.16
  1957.5  271.54  1985.8  272.78  2015.9  271.45  2156.4  270.73  2206.5  271.52
  2677.3  271.77  2798.3  274.87  2838.4  277.58  2858.5  277.49  2918.6  282.03
  2942.3  282.23  2958.7  284.33    3059  289.43  3119.2  290.74  3275.9  296.66
#Mann= 3 , 0 , 0
       0     .11       0  1448.7     .06       0  1638.3     .11       0
Bank Sta=1448.7,1638.3
XS Rating Curve= 0 ,0
Exp/Cntr=0.3,0.1

Chan Stop Cuts=-1
Use User Specified Reach Order=0
Composite Channel Slope=5