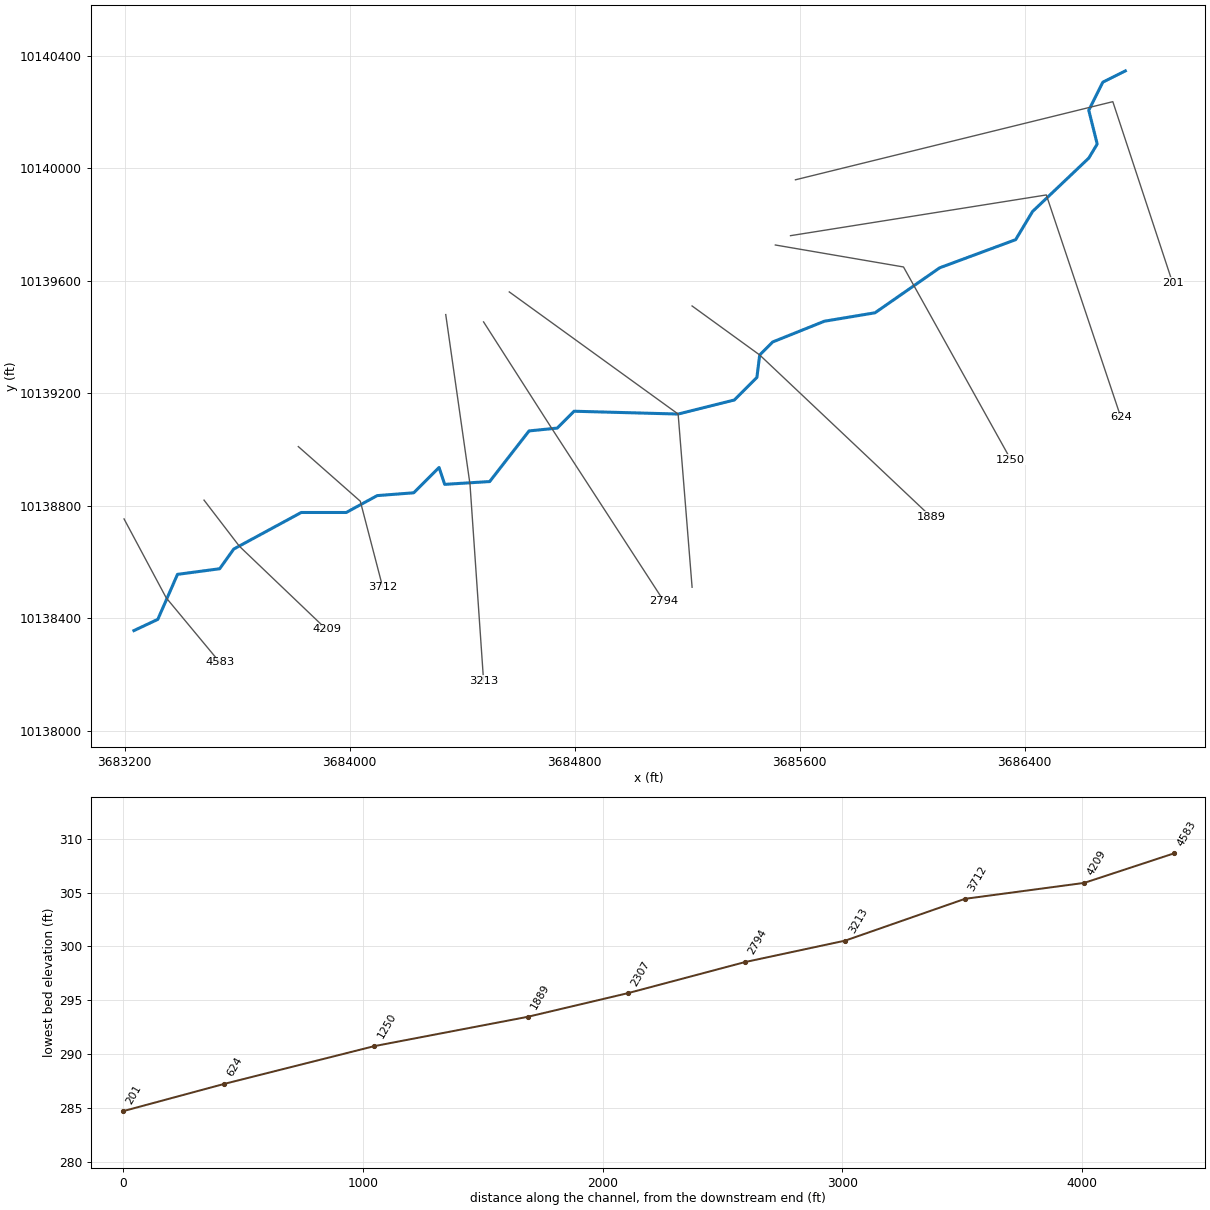
--- CCLC 035.prj (project) ---

Proj Title=CCLC 035 Base Level Engineering
Current Plan=p01
Default Exp/Contr=0.3,0.1
English Units
Geom File=g01
Flow File=f01
Flow File=f02
Plan File=p01
Y Axis Title=Elevation
X Axis Title(PF)=Main Channel Distance
X Axis Title(XS)=Station
BEGIN DESCRIPTION:
CCLC 035
END DESCRIPTION:
DSS File=dss
DSS Export Rating Curves= 0
DSS Export Rating Curve Sorted= 0
DSS Export Volume Flow Curves= 0
DXF OffsetX= 0
DXF OffsetY= 0
DXF ScaleX= 1
DXF ScaleY= 10

--- CCLC 035.p01 (plan) ---

Plan Title=Multiple Run
Short Identifier=Multiple
Geom File=g01
Flow File=f01
Subcritical Flow
K Sum by GR= 0
Std Step Tol= 0.01
Critical Tol= 0.01
Num of Std Step Trials= 20
Max Error Tol= 0.3
Flow Tol Ratio= 0.001
Split Flow NTrial= 30
Split Flow Tol= 0.02
Split Flow Ratio= 0.02
Log Output Level= 0
Friction Slope Method= 1
Unsteady Friction Slope Method= 2
Unsteady Bridges Friction Slope Method= 1
Parabolic Critical Depth
Global Vel Dist=  1 , 1 , 1
Global Log Level= 0
CheckData=True
Encroach Param= -1, 0, 0, 0
BEGIN DESCRIPTION:
Multiple Run
END DESCRIPTION:

--- CCLC 035.f01 (steady flow) ---

Flow Title=Multiple
Program Version=4.10
Number of Profiles= 7
Profile Names=10-year,25-year,50-year,1pct_min,100-year,1pct_plu,500-year
River Rch & RM=CCLC 035,Reach-1         ,4583
     706     971    1325     595    1798    5430    3421
Boundary for River Rch & Prof#=CCLC 035,Reach-1         , 1
Up Type= 0
Dn Type= 3
Dn Slope=0.006
Boundary for River Rch & Prof#=CCLC 035,Reach-1         , 2
Up Type= 0
Dn Type= 3
Dn Slope=0.006
Boundary for River Rch & Prof#=CCLC 035,Reach-1         , 3
Up Type= 0
Dn Type= 3
Dn Slope=0.006
Boundary for River Rch & Prof#=CCLC 035,Reach-1         , 4
Up Type= 0
Dn Type= 3
Dn Slope=0.006
Boundary for River Rch & Prof#=CCLC 035,Reach-1         , 5
Up Type= 0
Dn Type= 3
Dn Slope=0.006
Boundary for River Rch & Prof#=CCLC 035,Reach-1         , 6
Up Type= 0
Dn Type= 3
Dn Slope=0.006
Boundary for River Rch & Prof#=CCLC 035,Reach-1         , 7
Up Type= 0
Dn Type= 3
Dn Slope=0.006
DSS Import GetInterval= 0
DSS Import GetPeak= 0
DSS Import FillOption= 0

--- CCLC 035.f02 (steady flow) ---

Flow Title=Orig_BLE_Flows
Program Version=4.10
Number of Profiles= 7
Profile Names=10-year,25-year,50-year,1pct_min,100-year,1pct_plu,500-year
River Rch & RM=CCLC 035,Reach-1         ,4583
     706     952    1152     458    1383    4175    1989
Boundary for River Rch & Prof#=CCLC 035,Reach-1         , 1
Up Type= 0
Dn Type= 3
Dn Slope=0.006
Boundary for River Rch & Prof#=CCLC 035,Reach-1         , 2
Up Type= 0
Dn Type= 3
Dn Slope=0.006
Boundary for River Rch & Prof#=CCLC 035,Reach-1         , 3
Up Type= 0
Dn Type= 3
Dn Slope=0.006
Boundary for River Rch & Prof#=CCLC 035,Reach-1         , 4
Up Type= 0
Dn Type= 3
Dn Slope=0.006
Boundary for River Rch & Prof#=CCLC 035,Reach-1         , 5
Up Type= 0
Dn Type= 3
Dn Slope=0.006
Boundary for River Rch & Prof#=CCLC 035,Reach-1         , 6
Up Type= 0
Dn Type= 3
Dn Slope=0.006
Boundary for River Rch & Prof#=CCLC 035,Reach-1         , 7
Up Type= 0
Dn Type= 3
Dn Slope=0.006
DSS Import GetInterval= 0
DSS Import GetPeak= 0
DSS Import FillOption= 0

--- CCLC 035.g01 (geometry) ---

Geom Title=Existing Conditions
Program Version=4.10

River Reach=CCLC 035        ,Reach-1
Reach XY= 30
      3683233.23     10138356.84      3683318.23     10138396.84
      3683388.23     10138556.84      3683538.23     10138576.84
      3683588.23     10138646.84      3683828.23     10138776.84
      3683988.23     10138776.84      3684098.23     10138836.84
      3684228.23     10138846.84      3684318.23     10138936.84
      3684338.23     10138876.84      3684498.23     10138886.84
      3684638.23     10139066.84      3684738.23     10139076.84
      3684798.23     10139136.84      3685168.23     10139126.84
      3685368.23     10139176.84      3685448.23     10139256.84
      3685458.23     10139336.84      3685504.58     10139383.19
      3685688.23     10139456.84      3685868.23     10139486.84
      3686098.23     10139646.84      3686368.23     10139746.84
      3686428.23     10139846.84      3686628.23     10140036.84
      3686658.23     10140086.84      3686628.23     10140206.84
      3686678.23     10140306.84      3686758.23     10140346.84

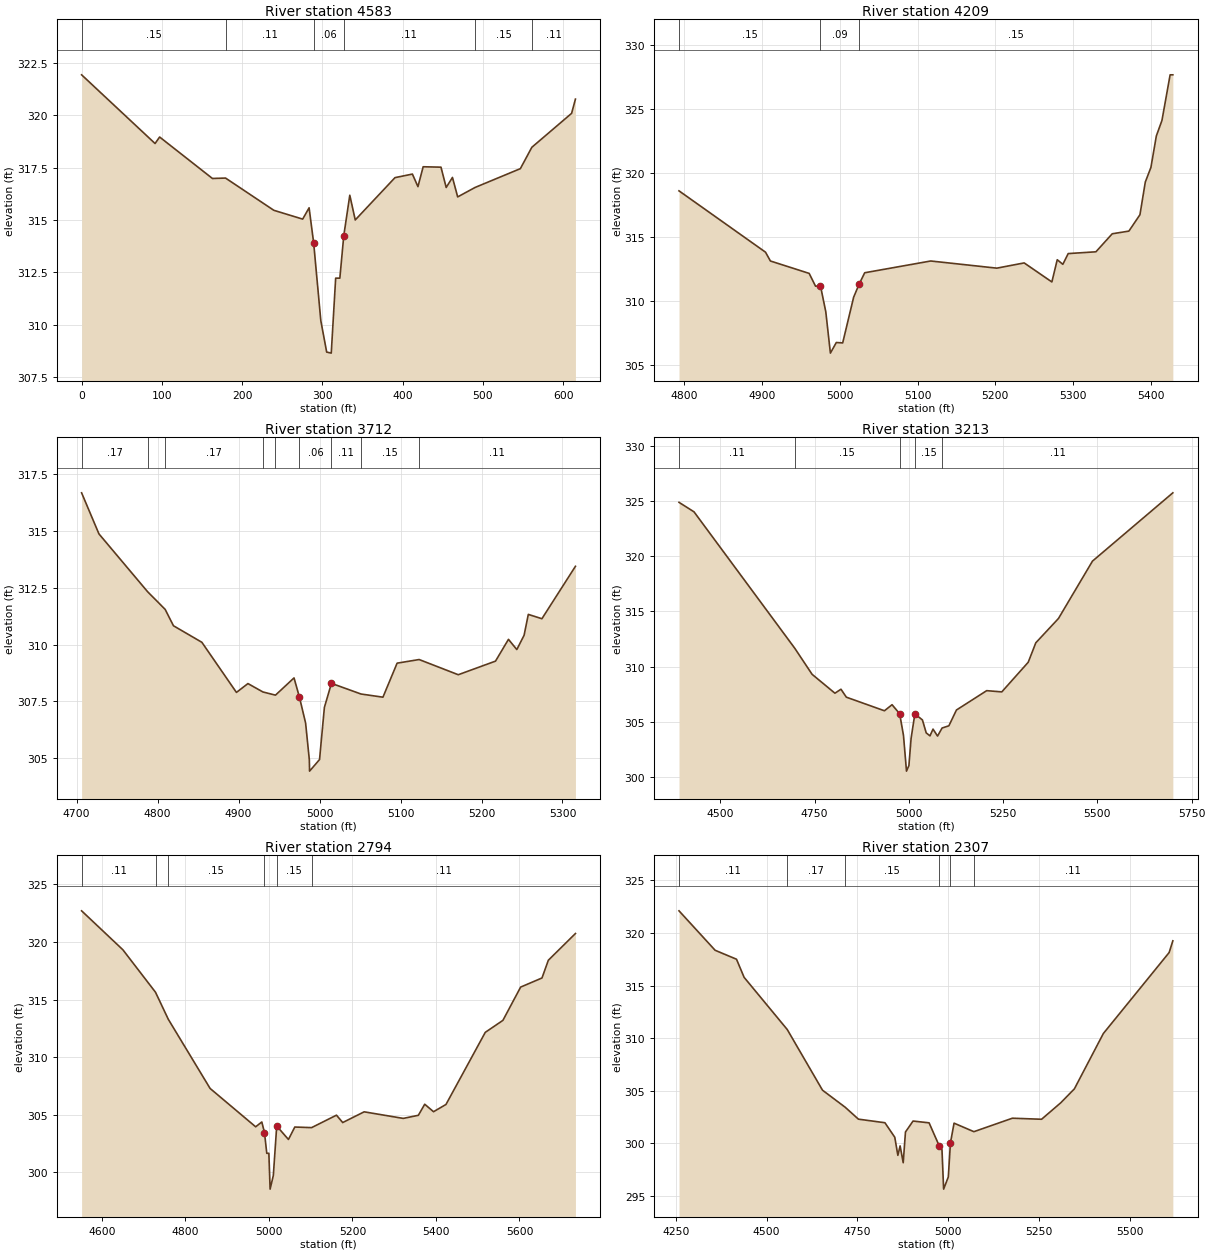
Type RM Length L Ch R = 1 ,4583    ,374,374,374
BEGIN DESCRIPTION:
CCLC 035 8.0
END DESCRIPTION:
XS GIS Cut Line= 3
      3683198.22     10138753.95        3683348.     10138473.55
      3683538.98     10138243.52
#Sta/Elev= 30
       0  321.93    91.5  318.65    97.2  318.96     163  316.98   179.3     317
   239.5  315.46   275.4  315.04   283.4  315.58   289.1   313.9     298  310.19
   305.3  308.69     311  308.64   316.5  312.22   321.7  312.22   326.6  314.25
   334.1  316.18   340.9     315   390.4  317.02   412.1  317.19     419  316.59
   425.5  317.54   447.7  317.52   454.2  316.55     462  317.03   468.5   316.1
   490.1  316.55   546.6  317.45   560.9  318.47   610.4  320.09   615.2  320.77
#Mann= 6 ,-1 , 0
       0     .15       0   179.3     .11       0   289.1     .06       0
   326.6     .11       0   490.1     .15       0   560.9     .11       0
Bank Sta=289.1,326.6
XS Rating Curve= 0 ,0
Exp/Cntr=0.3,0.1

Type RM Length L Ch R = 1 ,4209    ,497,497,497
BEGIN DESCRIPTION:
CCLC 035 7.0
END DESCRIPTION:
XS GIS Cut Line= 3
      3683482.53      10138820.8      3683608.23     10138656.84
      3683917.86     10138361.07
#Sta/Elev= 30
  4793.4   318.6  4904.6   313.8  4910.9  313.11  4960.7  312.14  4968.9  311.14
  4975.2  311.18  4982.1  309.13    4988   305.9  4995.6  306.73  5003.8   306.7
  5017.9  310.28  5025.1  311.32  5032.1  312.19    5117  313.11  5201.9  312.55
  5237.1  312.96  5272.7  311.47  5279.6  313.21  5286.8  312.85  5293.7  313.69
  5329.3  313.83  5350.3  315.24  5371.7  315.45  5385.9  316.73  5392.8  319.29
    5400  320.43    5407   322.9  5414.2  324.11  5424.7  327.68  5428.2  327.68
#Mann= 3 , 0 , 0
  4793.4     .15       0  4975.2     .09       0  5025.1     .15       0
Bank Sta=4975.2,5025.1
XS Rating Curve= 0 ,0
Exp/Cntr=0.3,0.1

Type RM Length L Ch R = 1 ,3712    ,499,499,499
BEGIN DESCRIPTION:
CCLC 035 6.0
END DESCRIPTION:
XS GIS Cut Line= 3
      3683817.82      10139011.1      3684038.23     10138816.84
      3684117.86     10138511.04
#Sta/Elev= 30
  4706.2  316.69  4727.6  314.88  4787.7  312.33  4809.4  311.55  4819.6  310.83
  4854.7   310.1  4897.4  307.89  4911.6  308.28  4930.1  307.91  4945.6  307.77
  4968.5  308.53  4975.2  307.68  4982.8  306.54  4987.4  304.92  4987.7  304.42
    5000  304.93    5006  307.23  5014.7  308.29  5051.2  307.82  5078.3  307.68
  5095.8  309.18    5123  309.34  5171.3  308.67  5217.3  309.27  5233.3  310.23
  5243.6  309.78  5252.6  310.41  5257.8  311.33  5274.6  311.14    5316  313.45
#Mann= 9 ,-1 , 0
  4706.2     .17       0  4787.7     .15       0  4809.4     .17       0
  4930.1     .15       0  4945.6     .11       0  4975.2     .06       0
  5014.7     .11       0  5051.2     .15       0    5123     .11       0
Bank Sta=4975.2,5014.7
XS Rating Curve= 0 ,0
Exp/Cntr=0.3,0.1

Type RM Length L Ch R = 1 ,3213    ,419,419,419
BEGIN DESCRIPTION:
CCLC 035 5.0
END DESCRIPTION:
XS GIS Cut Line= 3
      3684341.93     10139480.51      3684428.23     10138876.84
      3684476.48     10138178.41
#Sta/Elev= 30
  4390.2  324.86    4430     324  4697.4  311.65  4743.2   309.3  4803.8  307.59
  4819.8  307.95  4834.1  307.23  4935.1     306  4955.3  306.55  4975.5  305.73
  4985.6  303.78  4993.6  300.54    5000  301.04  5005.8   303.5  5015.8  305.72
  5035.9  305.17  5045.9     304  5055.9  303.73    5064  304.34    5076  303.71
    5088  304.44    5106  304.64  5126.1  306.07  5206.3  307.82  5246.4  307.71
  5316.5  310.39  5336.6  312.15  5396.7  314.35  5486.9  319.54  5700.1  325.72
#Mann= 5 ,-1 , 0
  4390.2     .11       0  4697.4     .15       0  4975.5     .09       0
  5015.8     .15       0    5088     .11       0
Bank Sta=4975.5,5015.8
XS Rating Curve= 0 ,0
Exp/Cntr=0.3,0.1

Type RM Length L Ch R = 1 ,2794    ,487,487,487
BEGIN DESCRIPTION:
CCLC 035 4.0
END DESCRIPTION:
XS GIS Cut Line= 3
      3684476.46     10139454.48      3684718.23     10139076.84
      3685117.86     10138461.06
#Sta/Elev= 30
  4551.6   322.7  4650.4  319.32  4728.6  315.63  4759.1  313.29  4859.3  307.28
  4968.4  303.95  4983.1  304.37  4989.5  303.45    4995  301.65    5000  301.65
    5003  298.54  5010.7  299.73  5018.8  304.02  5046.9  302.85  5062.1  303.93
  5102.4  303.88  5161.9  304.96  5176.8  304.32  5228.2  305.25  5321.8  304.68
    5358  304.95  5373.2  305.91  5394.3  305.26  5424.1  305.89  5518.2  312.15
  5560.4  313.19  5602.9  316.08    5654  316.87  5669.2  318.41  5734.1  320.73
#Mann= 6 ,-1 , 0
  4551.6     .11       0  4728.6     .17       0  4759.1     .15       0
  4989.5     .09       0  5018.8     .15       0  5102.4     .11       0
Bank Sta=4989.5,5018.8
XS Rating Curve= 0 ,0
Exp/Cntr=0.3,0.1

Type RM Length L Ch R = 1 ,2307    ,418,418,418
BEGIN DESCRIPTION:
CCLC 035 3.0
END DESCRIPTION:
XS GIS Cut Line= 3
      3684567.81      10139561.1      3685168.23     10139126.84
      3685217.85     10138511.04
#Sta/Elev= 30
    4259  322.11  4358.4  318.36  4417.2  317.51  4438.1  315.79  4556.8  310.83
  4653.9  305.06    4716  303.45  4752.7  302.31  4825.6  301.97  4852.7  300.59
  4861.2  298.87  4867.4  299.77  4875.9  298.17  4882.1  301.09    4903  302.13
  4947.1  301.96  4974.9  299.78  4982.6   299.4  4987.1  295.66    5000  296.82
  5005.8  300.04  5015.8  301.93  5070.4  301.12  5176.3   302.4  5256.6   302.3
  5309.2  303.86  5346.9  305.19  5426.6  310.45  5607.7  318.15  5617.8  319.26
#Mann= 6 ,-1 , 0
    4259     .11       0  4556.8     .17       0    4716     .15       0
  4974.9     .09       0  5005.8     .15       0  5070.4     .11       0
Bank Sta=4974.9,5005.8
XS Rating Curve= 0 ,0
Exp/Cntr=0.3,0.1

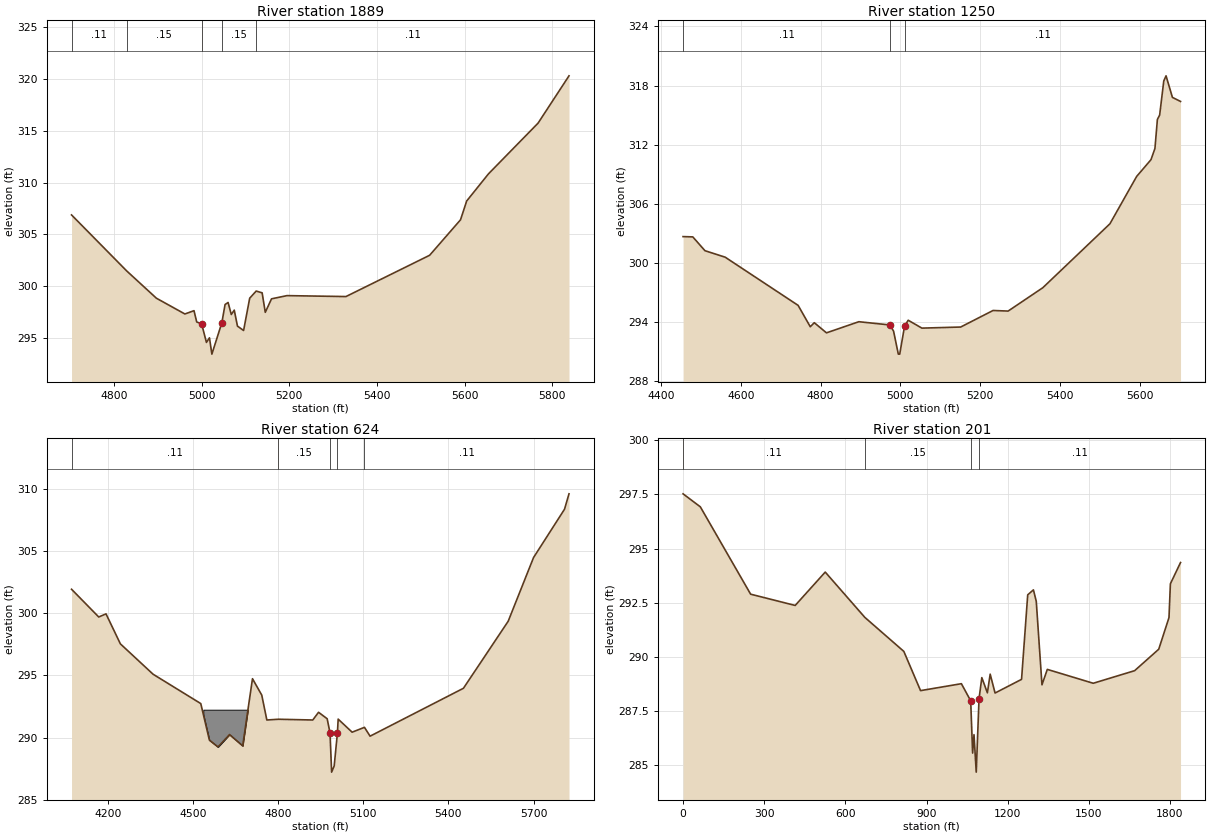
Type RM Length L Ch R = 1 ,1889    ,639,639,639
BEGIN DESCRIPTION:
CCLC 035 2.0
END DESCRIPTION:
XS GIS Cut Line= 3
      3685217.83     10139511.08      3685458.23     10139336.84
      3686067.82      10138761.1
#Sta/Elev= 30
  4703.1  306.88    4829  301.48  4896.8  298.85  4961.8  297.33  4982.6  297.65
  4988.8  296.56    5000  296.38    5011  294.59  5017.9  295.03  5023.4  293.46
  5046.2  296.49  5053.5  298.24  5060.4  298.44  5067.7  297.28  5074.5   297.7
  5081.8  296.16  5095.8  295.74  5109.7  298.85  5124.5  299.54  5138.1  299.37
  5145.3  297.49  5159.5  298.79  5194.7   299.1  5329.4  299.01  5520.4  302.99
  5590.9  306.41  5604.9  308.22  5654.7  310.84  5767.9  315.73  5838.5  320.29
#Mann= 5 ,-1 , 0
  4703.1     .11       0    4829     .15       0    5000     .09       0
  5046.2     .15       0  5124.5     .11       0
Bank Sta=5000,5046.2
XS Rating Curve= 0 ,0
Exp/Cntr=0.3,0.1

Type RM Length L Ch R = 1 ,1250    ,626,626,626
BEGIN DESCRIPTION:
Mapping XS 640385d9
END DESCRIPTION:
XS GIS Cut Line= 3
      3685513.84     10139727.89      3685969.53     10139649.77
       3686350.9     10138965.05
#Sta/Elev= 30
  4455.6  302.67    4480  302.64  4510.4  301.24  4561.1  300.58  4743.8  295.69
  4774.2  293.52  4784.3  293.93  4814.8   292.9  4895.9  294.03  4973.7   293.7
  4982.9  293.07  4994.8  290.74  4998.3  290.74  5010.4  293.58  5019.5  294.18
  5053.8  293.38    5151  293.49  5232.1  295.17  5269.8  295.11  5356.7  297.48
  5524.8  303.97  5591.8  308.78  5627.7  310.48  5637.6  311.62  5643.7  314.56
  5649.4  315.01  5659.7  318.47  5665.4  318.99  5681.4   316.8  5701.7  316.39
#Mann= 3 , 0 , 0
  4455.6     .11       0  4973.7     .06       0  5010.4     .11       0
Bank Sta=4973.7,5010.4
XS Rating Curve= 0 ,0
Exp/Cntr=0.3,0.1

Type RM Length L Ch R = 1 ,624     ,423,423,423
BEGIN DESCRIPTION:
CCLC 035 1.0
END DESCRIPTION:
XS GIS Cut Line= 3
      3685567.81     10139761.06      3686477.34     10139905.85
      3686742.07     10139116.02
#Sta/Elev= 30
  4071.2  301.93  4167.1   299.7  4192.8  299.95  4243.4  297.54  4358.7   295.1
  4526.9  292.74  4557.3   289.8  4587.7  289.25  4628.2  290.25  4674.6  289.34
  4709.2  294.74  4741.9  293.42  4759.8  291.42  4800.3  291.48  4921.8  291.42
  4942.1  292.04  4972.5  291.52  4982.6  290.38  4988.2  287.23  4997.3  287.73
 5008.66290.3743  5011.3  291.49  5060.5  290.44    5104  290.83  5123.8  290.12
    5453  293.97  5610.8  299.36  5700.2  304.48  5809.3  308.36  5825.2   309.6
#Mann= 5 ,-1 , 0
  4071.2     .11       0  4800.3     .15       0  4982.6     .06       0
 5008.66     .15       0    5104     .11       0
#Block Obstruct= 1 ,-1
 4535.71 4701.86  292.25
Bank Sta=4982.6,5008.66
XS Rating Curve= 0 ,0
Exp/Cntr=0.3,0.1

Type RM Length L Ch R = 1 ,201     ,0,0,0
BEGIN DESCRIPTION:
CCLC 035 1.0
END DESCRIPTION:
XS GIS Cut Line= 3
      3685585.32     10139959.73      3686713.79     10140237.51
      3686926.47     10139592.98
#Sta/Elev= 30
       0  297.53    63.8  296.93   249.8   292.9   414.5  292.38   525.6  293.92
     672  291.83   816.2  290.26     878  288.45    1029  288.77  1063.4  287.98
  1070.5  285.57  1075.6  286.42  1083.9  284.69  1094.2  288.07  1104.5  289.05
  1125.1  288.35  1135.4  289.21  1153.5  288.34  1251.4  288.97  1274.2  292.87
  1295.3   293.1  1305.8  292.57  1326.9  288.72  1346.7  289.43  1516.4  288.79
  1669.4  289.37  1758.6  290.36  1796.5  291.82  1801.7  293.38  1839.2  294.36
#Mann= 4 ,-1 , 0
       0     .11       0     672     .15       0  1063.4     .06       0
  1094.2     .11       0
Bank Sta=1063.4,1094.2
XS Rating Curve= 0 ,0
Exp/Cntr=0.3,0.1

Chan Stop Cuts=-1
Use User Specified Reach Order=0
Composite Channel Slope=5