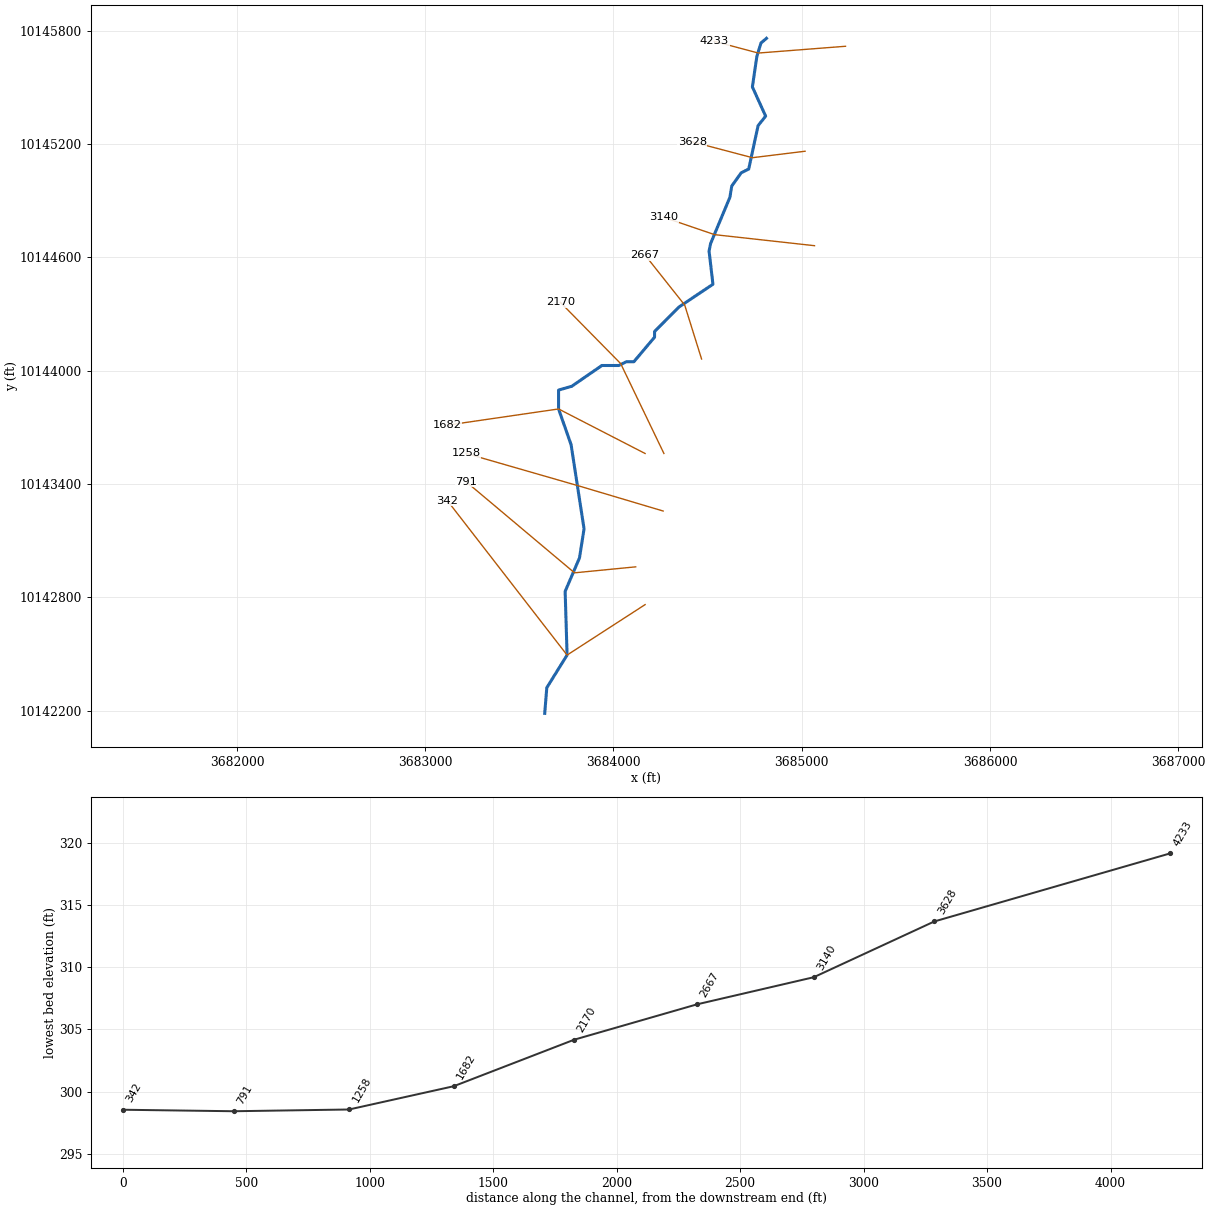
--- CCLC 036.prj (project) ---

Proj Title=CCLC 036 Base Level Engineering
Current Plan=p01
Default Exp/Contr=0.3,0.1
English Units
Geom File=g01
Flow File=f01
Flow File=f02
Plan File=p01
Y Axis Title=Elevation
X Axis Title(PF)=Main Channel Distance
X Axis Title(XS)=Station
BEGIN DESCRIPTION:
CCLC 036
END DESCRIPTION:
DSS Export Rating Curves= 0
DSS Export Rating Curve Sorted= 0
DSS Export Volume Flow Curves= 0
DXF OffsetX= 0
DXF OffsetY= 0
DXF ScaleX= 1
DXF ScaleY= 10

--- CCLC 036.p01 (plan) ---

Plan Title=Multiple Run
Program Version=4.10
Short Identifier=Multiple
Geom File=g01
Flow File=f01
Subcritical Flow
K Sum by GR= 0
Std Step Tol= 0.01
Critical Tol= 0.01
Num of Std Step Trials= 20
Max Error Tol= 0.3
Flow Tol Ratio= 0.001
Split Flow NTrial= 30
Split Flow Tol= 0.02
Split Flow Ratio= 0.02
Log Output Level= 0
Friction Slope Method= 1
Unsteady Friction Slope Method= 2
Unsteady Bridges Friction Slope Method= 1
Parabolic Critical Depth
Global Vel Dist= 1 , 1 , 1
Global Log Level= 0
CheckData=True
Encroach Param=-1 ,0,0, 0
BEGIN DESCRIPTION:
Multiple Run
END DESCRIPTION:
Computation Interval=1HOUR
Output Interval=1HOUR
Run HTab= 0
Run UNet= 0
Run PostProcess= 0
Run WQNet= 0
UNET Theta= 1
UNET Theta Warmup= 1
UNET ZTol= 0.02
UNET ZSATol= 0.05
UNET MxIter= 20
UNET MaxInSteps= 0
UNET DtIC= 0
UNET DtMin= 0
UNET MaxCRTS= 20
UNET WFStab= 2
UNET SFStab= 1
UNET WFX= 1
UNET SFX= 1
UNET DSS MLevel= 4
UNET DZMax Abort= 100
UNET Convert EG Bridges= 0
UNET Use Existing IB Tables=-1
UNET Froude Reduction=False
UNET Froude Limit= 1
UNET Froude Power= 10
UNET Time Slicing=0,0, 5
UNET Junction Losses=0
Instantaneous Interval=1HOUR
Write IC File= 0
Write IC File at Sim End=0
Echo Input=False
Echo Parameters=False
Echo Output=False
Write Detailed= 0
WQ AD Non Conservative
WQ ULTIMATE=-1
WQ Max Comp Step=1HOUR
WQ Output Interval=15MIN
WQ Output Selected Increments= 0
WQ Output face flow=0
WQ Output face velocity=0
WQ Output face area=0
WQ Output face dispersion=0
WQ Output cell volume=0
WQ Output cell surface area=0
WQ Output cell continuity=0
WQ Output cumulative cell continuity=0
WQ Output face conc=0
WQ Output face dconc_dx=0
WQ Output face courant=0
WQ Output face peclet=0
WQ Output face adv mass=0
WQ Output face disp mass=0
WQ Output cell mass=0
WQ Output cell source sink temp=0
WQ Output cell source sink nsm=0
WQ Output MaxMinRange=-1
WQ Daily Max Min Mean=-1
WQ Daily Range=0
WQ Daily Time=0
WQ Create Restart=0
WQ Fixed Restart=0
WQ System Summary=0
WQ Use Fixed Temperature=0
Sorting and Armoring Iterations= 10
XS Update Threshold= 0.02
Hydraulics Update Threshold= 0.02
Energy Slope Method= 1
Volume Change Method= 0
XS Weighting Method= 0
Number of US Weighted Cross Sections= 1
Number of DS Weighted Cross Sections= 1
Upstream XS Weight=0.25
Main XS Weight=0.5
Downstream XS Weight=0.25
Number of DS XS's Weighted with US Boundary= 1
Upstream Boundary Weight= 1
Weight of XSs Associated with US Boundary= 0
Number of US XS's Weighted with DS Boundary= 1
Downstream Boundary Weight= 0.5
Weight of XSs Associated with DS Boundary= 0.5
Sediment Output Level= 4
Mass or Volume Output= 0
Output Increment Type= 1
Profile and TS Output Increment= 10
XS Output Flag= 0
XS Output Increment= 10
Disregard all LS=0
Disregard all Conn=0
Disregard all Breaches=0
Disregard all Pumps=0

--- CCLC 036.f01 (steady flow) ---

Flow Title=Multiple
Program Version=4.10
Number of Profiles= 7
Profile Names=10-year,25-year,50-year,1pct_min,100-year,1pct_plu,500-year
River Rch & RM=CCLC 036,Reach-1         ,4233
     555     754    1019     454    1372    4143    2570
River Rch & RM=CCLC 036,Reach-1         ,1682
    1331    1875    2598    1180    3565   10766    6954
Boundary for River Rch & Prof#=CCLC 036,Reach-1         , 1
Up Type= 0
Dn Type= 3
Dn Slope=0.005
Boundary for River Rch & Prof#=CCLC 036,Reach-1         , 2
Up Type= 0
Dn Type= 3
Dn Slope=0.005
Boundary for River Rch & Prof#=CCLC 036,Reach-1         , 3
Up Type= 0
Dn Type= 3
Dn Slope=0.005
Boundary for River Rch & Prof#=CCLC 036,Reach-1         , 4
Up Type= 0
Dn Type= 3
Dn Slope=0.005
Boundary for River Rch & Prof#=CCLC 036,Reach-1         , 5
Up Type= 0
Dn Type= 3
Dn Slope=0.005
Boundary for River Rch & Prof#=CCLC 036,Reach-1         , 6
Up Type= 0
Dn Type= 3
Dn Slope=0.005
Boundary for River Rch & Prof#=CCLC 036,Reach-1         , 7
Up Type= 0
Dn Type= 3
Dn Slope=0.005
DSS Import GetInterval= 0
DSS Import GetPeak= 0
DSS Import FillOption= 0

--- CCLC 036.f02 (steady flow) ---

Flow Title=Orig_BLE_Flows
Program Version=4.10
Number of Profiles= 7
Profile Names=10-year,25-year,50-year,1pct_min,100-year,1pct_plu,500-year
River Rch & RM=CCLC 036,Reach-1         ,4233
     555     739     886     350    1055    3188    1494
River Rch & RM=CCLC 036,Reach-1         ,1682
    1331    1838    2259     908    2742    8282    4043
Boundary for River Rch & Prof#=CCLC 036,Reach-1         , 1
Up Type= 0
Dn Type= 3
Dn Slope=0.005
Boundary for River Rch & Prof#=CCLC 036,Reach-1         , 2
Up Type= 0
Dn Type= 3
Dn Slope=0.005
Boundary for River Rch & Prof#=CCLC 036,Reach-1         , 3
Up Type= 0
Dn Type= 3
Dn Slope=0.005
Boundary for River Rch & Prof#=CCLC 036,Reach-1         , 4
Up Type= 0
Dn Type= 3
Dn Slope=0.005
Boundary for River Rch & Prof#=CCLC 036,Reach-1         , 5
Up Type= 0
Dn Type= 3
Dn Slope=0.005
Boundary for River Rch & Prof#=CCLC 036,Reach-1         , 6
Up Type= 0
Dn Type= 3
Dn Slope=0.005
Boundary for River Rch & Prof#=CCLC 036,Reach-1         , 7
Up Type= 0
Dn Type= 3
Dn Slope=0.005
DSS Import GetInterval= 0
DSS Import GetPeak= 0
DSS Import FillOption= 0

--- CCLC 036.g01 (geometry) ---

Geom Title=Existing Conditions
Program Version=4.10

River Reach=CCLC 036        ,Reach-1
Reach XY= 30
      3684812.62     10145758.68      3684783.32     10145733.72
      3684761.62     10145663.19      3684737.75     10145501.52
      3684808.23     10145346.84      3684768.23     10145296.84
      3684718.23     10145066.84      3684678.23     10145046.84
      3684628.23     10144976.84      3684618.23     10144916.84
       3684516.1     10144673.17      3684507.68     10144633.16
      3684528.23     10144456.84      3684348.23     10144336.84
      3684218.23     10144206.84      3684218.23     10144176.84
      3684108.23     10144046.84      3684068.23     10144046.84
      3684028.23     10144026.84      3683938.23     10144026.84
      3683778.23     10143916.84      3683708.23     10143896.84
      3683708.23     10143796.84      3683774.77     10143607.64
      3683843.61     10143162.21      3683819.32     10143008.33
      3683743.18     10142830.95      3683753.46     10142493.98
      3683645.69      10142321.4       3683634.7      10142185.4

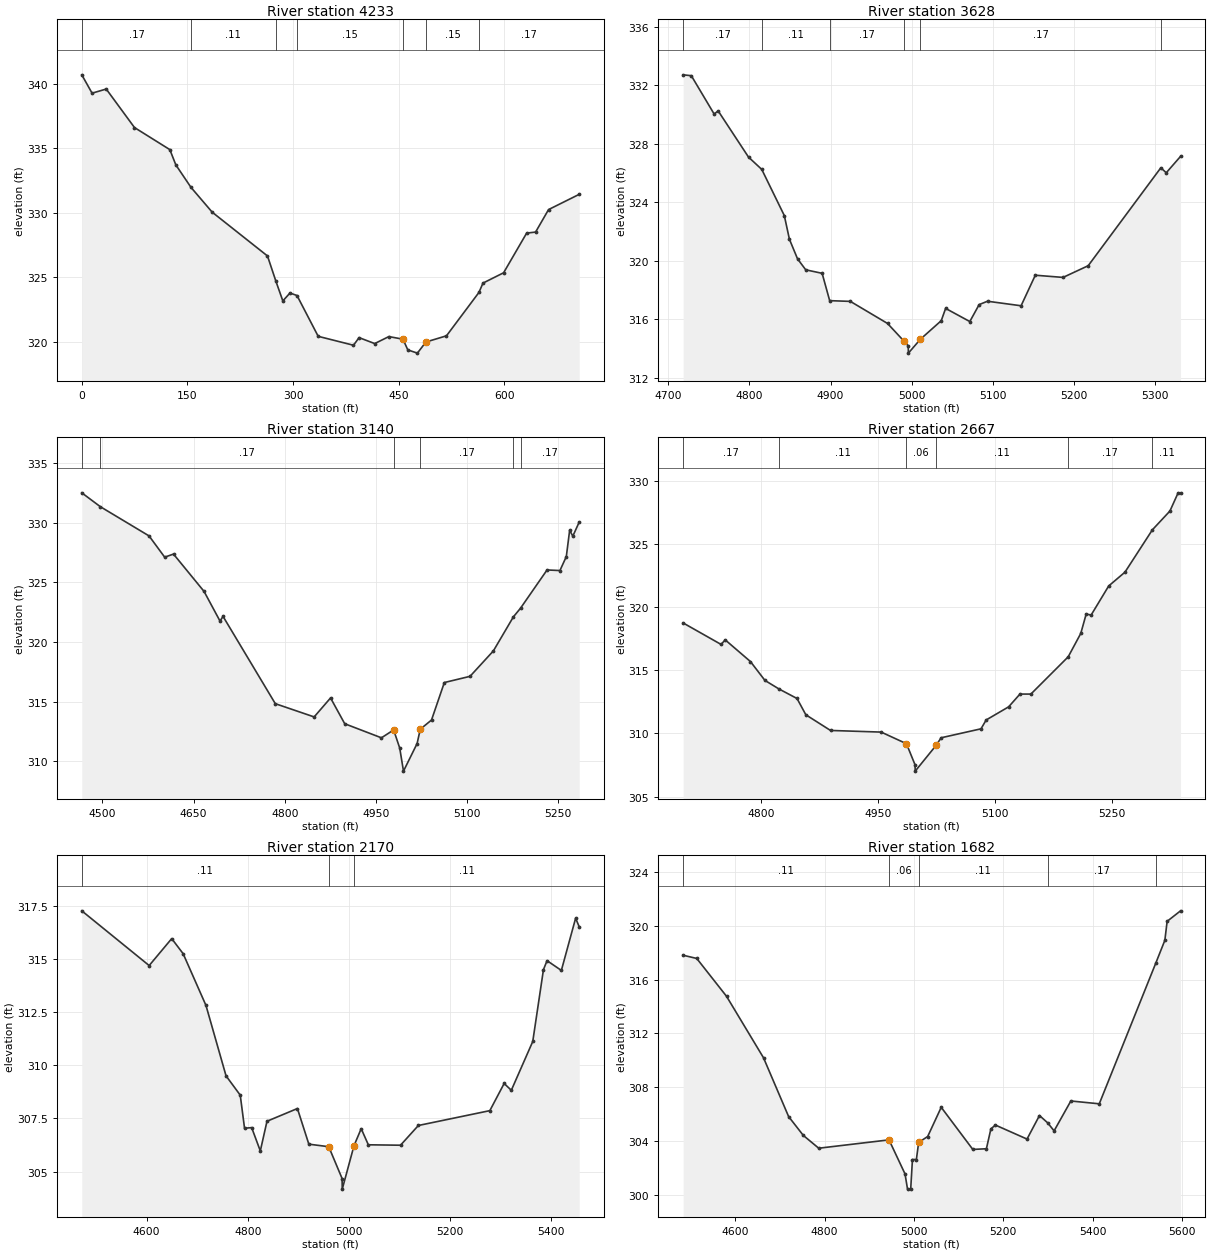
Type RM Length L Ch R = 1 ,4233    ,955,955,955
BEGIN DESCRIPTION:
CCLC 036 9.0
END DESCRIPTION:
XS GIS Cut Line= 3
      3685232.43     10145716.63      3684769.11     10145680.82
      3684535.82     10145742.67
#Sta/Elev= 30
       0  340.68    14.6  339.26    34.7  339.58    74.8   336.6     125  334.89
   133.5  333.71     155  331.97   185.1  330.05   263.6  326.66   275.4  324.73
   285.4  323.18   295.5  323.79   305.5   323.6   335.6  320.44   385.7  319.75
   393.6  320.34   415.8  319.88   435.9  320.42   455.9  320.22   462.8  319.39
   476.4  319.14   488.5     320   517.7  320.48   563.8  323.84   569.5  324.56
   598.8  325.36   631.5  328.43   644.2  328.51   662.6  330.25   706.1  331.43
#Mann= 7 ,-1 , 0
       0     .17       0     155     .11       0   275.4     .17       0
   305.5     .15       0   455.9     .09       0   488.5     .15       0
   563.8     .17       0
Bank Sta=455.9,488.5
XS Rating Curve= 0 ,0
Exp/Cntr=0.3,0.1

Type RM Length L Ch R = 1 ,3628    ,488,488,488
BEGIN DESCRIPTION:
CCLC 036 8.0
END DESCRIPTION:
XS GIS Cut Line= 3
      3685017.84     10145161.07      3684738.23     10145126.84
      3684417.82     10145211.08
#Sta/Elev= 30
  4718.3  332.71  4728.4  332.65  4756.5  330.03  4761.5  330.24  4798.9  327.08
  4815.2  326.24    4843  323.08  4849.3  321.46  4859.3  320.12  4869.4  319.37
  4889.6  319.13  4898.9  317.26  4924.4  317.21  4970.2   315.7  4990.3   314.5
  4995.7  314.17  4995.9  313.67  5010.7  314.62  5036.4  315.89  5041.8  316.73
  5071.6  315.83  5083.1  316.99  5093.4  317.22  5134.8  316.91  5152.3     319
  5186.5  318.85  5217.5  319.65    5307  326.35  5313.7  326.01  5331.3  327.13
#Mann= 6 ,-1 , 0
  4718.3     .17       0  4815.2     .11       0  4898.9     .17       0
  4990.3     .09       0  5010.7     .17       0    5307     .11       0
Bank Sta=4990.3,5010.7
XS Rating Curve= 0 ,0
Exp/Cntr=0.3,0.1

Type RM Length L Ch R = 1 ,3140    ,473,473,473
BEGIN DESCRIPTION:
CCLC 036 7.0
END DESCRIPTION:
XS GIS Cut Line= 3
      3685067.86     10144661.07      3684537.16      10144719.5
      3684267.81     10144811.09
#Sta/Elev= 30
  4466.1   332.5  4496.6  331.34  4576.8  328.89  4602.5  327.11    4617  327.37
  4667.3  324.24  4693.5  321.76  4698.5  322.15  4784.5  314.84  4848.4  313.73
  4875.4  315.32  4898.7  313.16  4959.1  311.98  4979.2  312.64  4989.2  311.12
  4995.4  309.19  5017.8   311.5    5023   312.7  5041.5  313.47  5062.6  316.61
  5104.9  317.13  5143.3  319.26  5176.2  322.11    5188  322.84  5231.6  326.04
  5252.8  325.99  5263.3  327.16  5268.8  329.37    5274  328.87  5284.5  330.05
#Mann= 6 ,-1 , 0
  4466.1     .11       0  4496.6     .17       0  4979.2     .09       0
    5023     .17       0  5176.2     .11       0    5188     .17       0
Bank Sta=4979.2,5023
XS Rating Curve= 0 ,0
Exp/Cntr=0.3,0.1

Type RM Length L Ch R = 1 ,2667    ,497,497,497
BEGIN DESCRIPTION:
CCLC 036 6.0
END DESCRIPTION:
XS GIS Cut Line= 3
      3684467.85     10144061.07      3684378.23     10144346.84
      3684167.88     10144611.03
#Sta/Elev= 30
  4700.5  318.74  4749.1  317.04  4754.4   317.4  4786.8  315.68  4805.3  314.19
  4823.4  313.51  4846.4  312.76  4857.7  311.47  4889.3  310.23  4954.2   310.1
  4986.6  309.18  4997.6  307.51  4997.8  307.01  5024.6  309.05    5031  309.65
  5082.1  310.36  5088.7  311.06  5117.5   312.1    5132  313.11    5146  313.11
  5193.8  316.06  5209.9  317.91  5216.8  319.44  5223.2  319.37  5245.7  321.67
  5266.5  322.76  5301.6  326.11  5324.1   327.6  5334.6  329.04  5337.7  329.04
#Mann= 6 ,-1 , 0
  4700.5     .17       0  4823.4     .11       0  4986.6     .06       0
  5024.6     .11       0  5193.8     .17       0  5301.6     .11       0
Bank Sta=4986.6,5024.6
XS Rating Curve= 0 ,0
Exp/Cntr=0.3,0.1

Type RM Length L Ch R = 1 ,2170    ,488,488,488
BEGIN DESCRIPTION:
CCLC 036 5.0
END DESCRIPTION:
XS GIS Cut Line= 3
      3684267.86     10143561.06      3684038.23     10144036.84
      3683717.86     10144361.06
#Sta/Elev= 30
  4471.7  317.29    4605  314.71  4649.6  315.98  4672.2  315.27  4717.4  312.83
  4757.1  309.51  4785.2   308.6  4793.7  307.04  4807.8  307.07  4824.9  305.97
  4838.1  307.37  4898.3  307.97  4920.9  306.29  4960.3  306.17  4986.7  304.67
    4987  304.17  5010.3  306.22  5024.5  307.02  5038.6  306.26  5102.3  306.24
  5137.6  307.17    5279  307.87  5307.3  309.15  5321.5  308.83  5363.9  311.13
  5385.1  314.52  5392.2  314.94  5420.5  314.48  5448.7  316.94  5455.8  316.54
#Mann= 3 , 0 , 0
  4471.7     .11       0  4960.3     .06       0  5010.3     .11       0
Bank Sta=4960.3,5010.3
XS Rating Curve= 0 ,0
Exp/Cntr=0.3,0.1

Type RM Length L Ch R = 1 ,1682    ,424,424,424
BEGIN DESCRIPTION:
CCLC 036 4.0
END DESCRIPTION:
XS GIS Cut Line= 3
      3684167.88     10143561.06      3683708.23     10143796.84
      3683117.83     10143711.07
#Sta/Elev= 30
  4483.4  317.81  4513.9  317.57  4580.5  314.76  4663.3  310.19  4719.5  305.82
  4752.4  304.42  4786.9  303.47  4944.2  304.09    4980  301.56  4985.6  300.43
  4992.7  300.43  4996.6  302.63  5005.4  302.63  5010.5   303.9  5030.7  304.34
    5061  306.51  5131.7  303.38  5162.1  303.43  5172.2  304.91  5182.3  305.19
    5253  304.15  5280.9   305.9  5299.1  305.36  5313.6  304.76  5351.1  306.98
  5414.7  306.77  5541.5  317.25  5561.5  318.92  5566.6  320.33  5596.6  321.11
#Mann= 5 ,-1 , 0
  4483.4     .11       0  4944.2     .06       0  5010.5     .11       0
  5299.1     .17       0  5541.5     .11       0
Bank Sta=4944.2,5010.5
XS Rating Curve= 0 ,0
Exp/Cntr=0.3,0.1

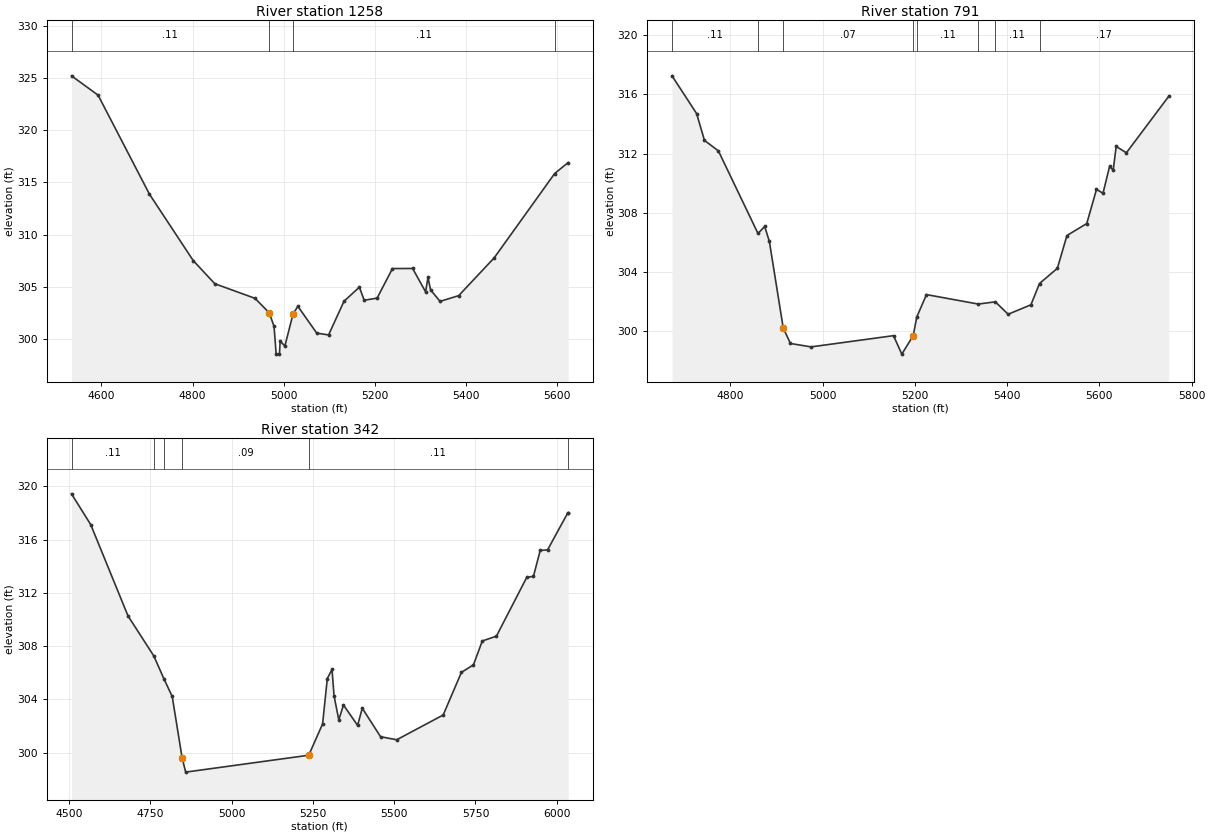
Type RM Length L Ch R = 1 ,1258    ,467,467,467
BEGIN DESCRIPTION:
CCLC 036 3.0
END DESCRIPTION:
XS GIS Cut Line= 3
      3684263.77     10143256.55      3683817.29     10143388.97
      3683217.81     10143561.08
#Sta/Elev= 30
  4534.3   325.2  4592.6  323.35  4705.3  313.87  4801.2  307.52  4848.6   305.3
  4936.8   303.9  4968.1  302.51  4978.6  301.21  4983.2  298.56  4990.4  298.56
    4992  299.82  5002.3  299.33  5020.2   302.4  5030.8  303.14  5072.2  300.57
  5098.2   300.4    5132  303.62  5165.7  304.97  5176.3  303.72  5204.6  303.92
  5238.3  306.75  5282.5  306.76    5311  304.52  5316.2  305.92  5321.9  304.71
  5342.7  303.61  5383.6  304.16  5461.5  307.78  5594.1  315.85  5623.7   316.9
#Mann= 4 ,-1 , 0
  4534.3     .11       0  4968.1     .07       0  5020.2     .11       0
  5594.1     .17       0
Bank Sta=4968.1,5020.2
XS Rating Curve= 0 ,0
Exp/Cntr=0.3,0.1

Type RM Length L Ch R = 1 ,791     ,449,449,449
BEGIN DESCRIPTION:
CCLC 036 2.0
END DESCRIPTION:
XS GIS Cut Line= 3
      3684117.85     10142961.07      3683792.99     10142929.36
      3683217.87     10143411.06
#Sta/Elev= 30
  4673.6  317.26    4727   314.7  4743.9  312.89  4774.1  312.18  4859.9  306.59
  4874.5  307.06  4884.6  306.05  4914.7  300.18  4930.4  299.14    4975  298.91
  5153.7  299.67  5171.7  298.42  5196.6  299.68  5204.1  300.93  5225.2  302.45
  5337.2  301.81  5374.4  301.96  5402.2  301.12  5451.6  301.76  5470.2   303.2
  5508.9  304.23  5529.7  306.45  5572.6  307.26  5593.7  309.57  5607.8  309.31
  5622.1  311.13  5629.9  310.87  5636.4  312.48  5658.5  312.05  5750.2  315.87
#Mann= 8 ,-1 , 0
  4673.6     .11       0  4859.9     .15       0  4914.7     .07       0
  5196.6     .15       0  5204.1     .11       0  5337.2     .17       0
  5374.4     .11       0  5470.2     .17       0
Bank Sta=4914.7,5196.6
XS Rating Curve= 0 ,0
Exp/Cntr=0.3,0.1

Type RM Length L Ch R = 1 ,342     ,0,0,0
BEGIN DESCRIPTION:
CCLC 036 1.0
END DESCRIPTION:
XS GIS Cut Line= 3
      3684167.85     10142761.07      3683753.46     10142493.98
      3683117.85     10143311.07
#Sta/Elev= 30
    4507  319.44  4566.1  317.13  4680.9  310.27  4760.4  307.26  4791.3  305.55
  4816.9  304.22  4847.3  299.62  4858.3  298.54    5237  299.81  5279.6  302.16
  5294.1  305.57  5308.6  306.25  5314.9  304.26  5329.4  302.47  5343.9  303.58
  5387.3  302.05  5401.7  303.34  5457.9   301.2  5507.6  300.97  5650.6  302.83
  5706.7  306.03  5743.8   306.6    5771  308.39  5814.4  308.75  5907.6  313.16
  5928.4  313.25  5949.2  315.19  5971.8  315.23  6033.8     318  6035.2     318
#Mann= 6 ,-1 , 0
    4507     .11       0  4760.4     .15       0  4791.3     .11       0
  4847.3     .09       0    5237     .11       0  6033.8     .17       0
Bank Sta=4847.3,5237
XS Rating Curve= 0 ,0
Exp/Cntr=0.3,0.1

Chan Stop Cuts=-1
Use User Specified Reach Order=0
Composite Channel Slope=5