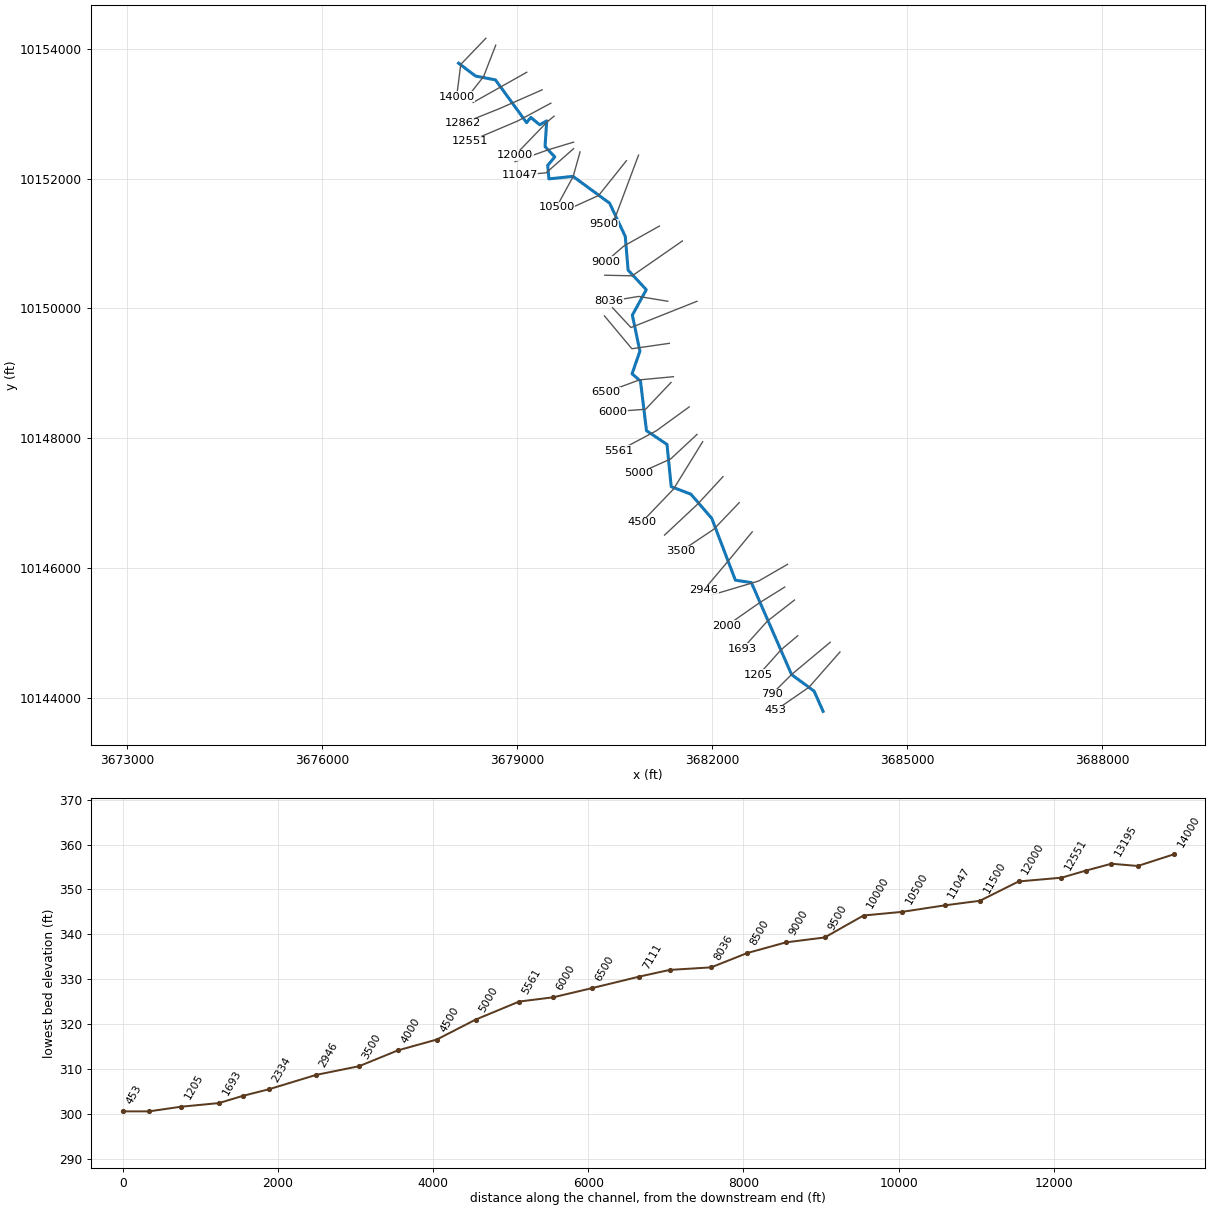
--- CCLC 037.prj (project) ---

Proj Title=CCLC 037 Base Level Engineering
Current Plan=p01
Default Exp/Contr=0.3,0.1
English Units
Geom File=g01
Flow File=f01
Flow File=f02
Plan File=p01
Y Axis Title=Elevation
X Axis Title(PF)=Main Channel Distance
X Axis Title(XS)=Station
BEGIN DESCRIPTION:
CCLC 037
END DESCRIPTION:
DSS Export Rating Curves= 0
DSS Export Rating Curve Sorted= 0
DSS Export Volume Flow Curves= 0
DXF OffsetX= 0
DXF OffsetY= 0
DXF ScaleX= 1
DXF ScaleY= 10

--- CCLC 037.p01 (plan) ---

Plan Title=Multiple Run
Short Identifier=Multiple
Geom File=g01
Flow File=f01
Subcritical Flow
K Sum by GR= 0
Std Step Tol= 0.01
Critical Tol= 0.01
Num of Std Step Trials= 20
Max Error Tol= 0.3
Flow Tol Ratio= 0.001
Split Flow NTrial= 30
Split Flow Tol= 0.02
Split Flow Ratio= 0.02
Log Output Level= 0
Friction Slope Method= 1
Unsteady Friction Slope Method= 2
Unsteady Bridges Friction Slope Method= 1
Parabolic Critical Depth
Global Vel Dist=  1 , 1 , 1
Global Log Level= 0
CheckData=True
Encroach Param= -1, 0, 0, 0
BEGIN DESCRIPTION:
Multiple Run
END DESCRIPTION:

--- CCLC 037.f01 (steady flow) ---

Flow Title=Multiple
Program Version=4.10
Number of Profiles= 7
Profile Names=10-year,25-year,50-year,1pct_min,100-year,1pct_plu,500-year
River Rch & RM=CCLC 037,Reach-1         ,14000
     718     984    1340     600    1812    5472    3431
River Rch & RM=CCLC 037,Reach-1         ,8036
    1057    1472    2025     914    2761    8338    5317
Boundary for River Rch & Prof#=CCLC 037,Reach-1         , 1
Up Type= 0
Dn Type= 3
Dn Slope=0.005
Boundary for River Rch & Prof#=CCLC 037,Reach-1         , 2
Up Type= 0
Dn Type= 3
Dn Slope=0.005
Boundary for River Rch & Prof#=CCLC 037,Reach-1         , 3
Up Type= 0
Dn Type= 3
Dn Slope=0.005
Boundary for River Rch & Prof#=CCLC 037,Reach-1         , 4
Up Type= 0
Dn Type= 3
Dn Slope=0.005
Boundary for River Rch & Prof#=CCLC 037,Reach-1         , 5
Up Type= 0
Dn Type= 3
Dn Slope=0.005
Boundary for River Rch & Prof#=CCLC 037,Reach-1         , 6
Up Type= 0
Dn Type= 3
Dn Slope=0.005
Boundary for River Rch & Prof#=CCLC 037,Reach-1         , 7
Up Type= 0
Dn Type= 3
Dn Slope=0.005
DSS Import GetInterval= 0
DSS Import GetPeak= 0
DSS Import FillOption= 0

--- CCLC 037.f02 (steady flow) ---

Flow Title=Orig_BLE_Flows
Program Version=4.10
Number of Profiles= 7
Profile Names=10-year,25-year,50-year,1pct_min,100-year,1pct_plu,500-year
River Rch & RM=CCLC 037,Reach-1         ,14000
     718     965    1165     462    1394    4211    1995
River Rch & RM=CCLC 037,Reach-1         ,8036
    1057    1443    1761     703    2124    6414    3091
Boundary for River Rch & Prof#=CCLC 037,Reach-1         , 1
Up Type= 0
Dn Type= 3
Dn Slope=0.005
Boundary for River Rch & Prof#=CCLC 037,Reach-1         , 2
Up Type= 0
Dn Type= 3
Dn Slope=0.005
Boundary for River Rch & Prof#=CCLC 037,Reach-1         , 3
Up Type= 0
Dn Type= 3
Dn Slope=0.005
Boundary for River Rch & Prof#=CCLC 037,Reach-1         , 4
Up Type= 0
Dn Type= 3
Dn Slope=0.005
Boundary for River Rch & Prof#=CCLC 037,Reach-1         , 5
Up Type= 0
Dn Type= 3
Dn Slope=0.005
Boundary for River Rch & Prof#=CCLC 037,Reach-1         , 6
Up Type= 0
Dn Type= 3
Dn Slope=0.005
Boundary for River Rch & Prof#=CCLC 037,Reach-1         , 7
Up Type= 0
Dn Type= 3
Dn Slope=0.005
DSS Import GetInterval= 0
DSS Import GetPeak= 0
DSS Import FillOption= 0

--- CCLC 037.g01 (geometry) ---

Geom Title=Existing Conditions
Program Version=4.10

River Reach=CCLC 037        ,Reach-1
Reach XY= 30
      3678098.23     10153776.84       3678358.3     10153579.28
      3678665.25     10153519.94      3679144.64     10152861.36
      3679209.03      10152941.6      3679346.83     10152828.85
      3679454.79      10152889.2      3679428.62     10152492.99
      3679578.72     10152333.74      3679469.49     10152203.49
      3679489.01     10151995.79      3679859.02     10152034.19
      3680422.53     10151621.55      3680663.68     10151109.43
      3680707.32      10150590.9      3680986.73     10150289.22
      3680772.64     10149897.48      3680888.55      10149341.9
       3680767.9     10148994.42      3680897.56     10148882.66
      3680990.08     10148118.58      3681305.58     10147907.55
      3681370.32      10147256.8      3681674.49     10147140.41
      3681995.51     10146767.43      3682358.23     10145816.84
      3682604.19     10145780.04      3683222.85     10144364.01
      3683569.96     10144108.69      3683708.23     10143796.84

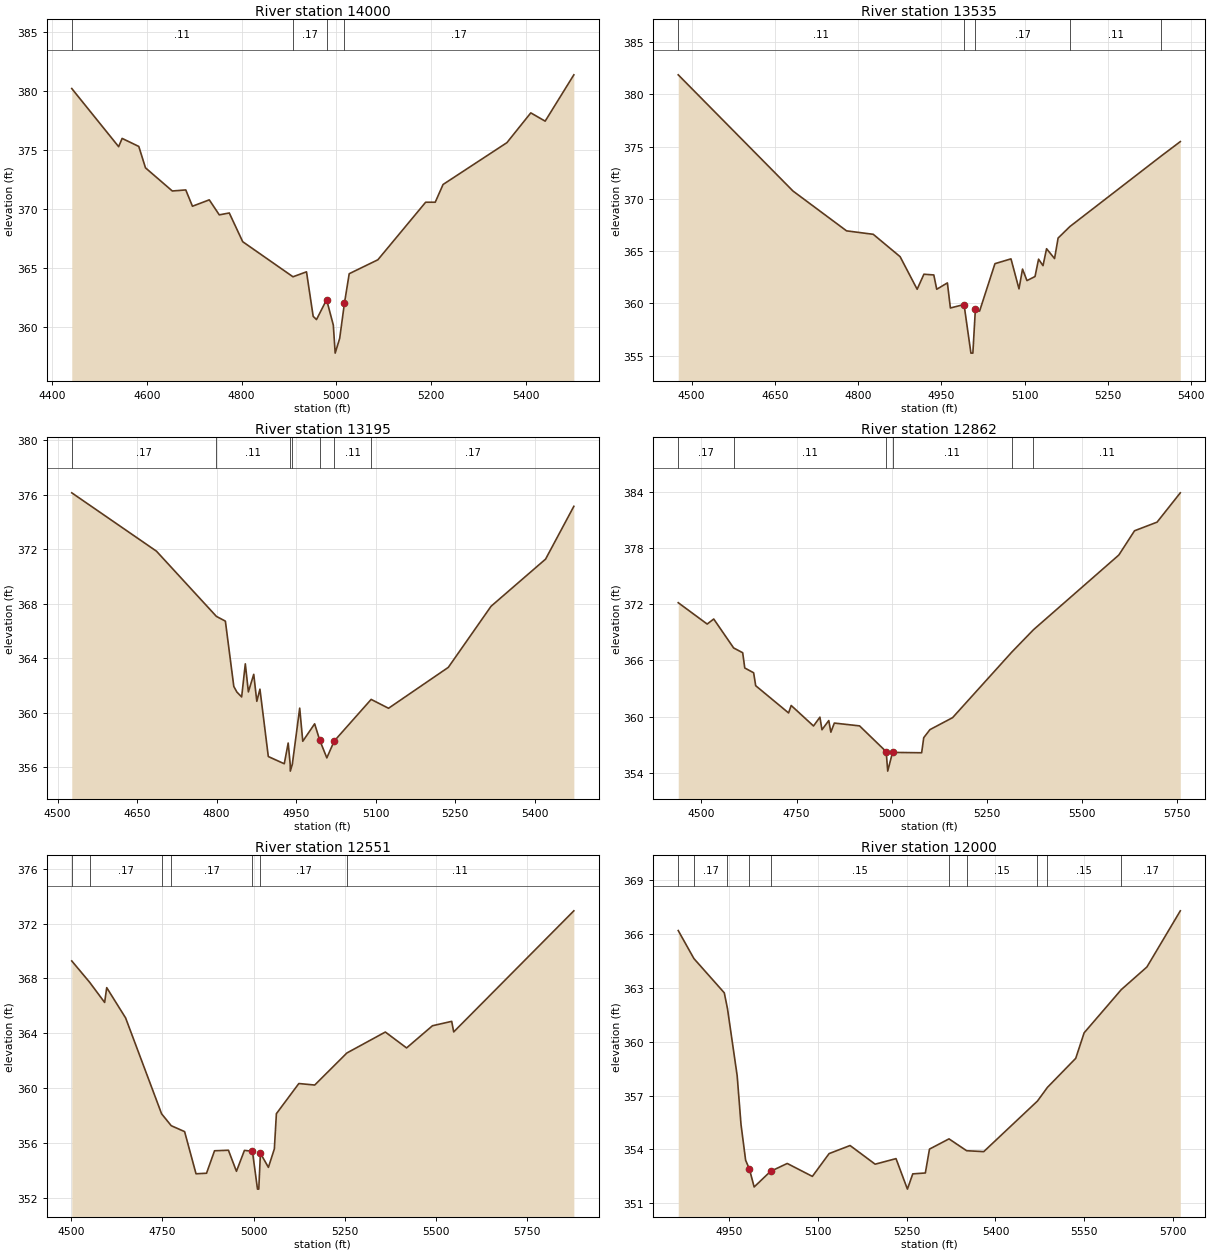
Type RM Length L Ch R = 1 ,14000   ,465,465,465
BEGIN DESCRIPTION:
CCLC 037 28.0
END DESCRIPTION:
XS GIS Cut Line= 3
      3678517.87     10154161.09      3678131.71     10153757.87
      3678067.85     10153261.06
#Sta/Elev= 30
  4441.7  380.22  4540.6   375.3  4547.9     376  4583.1  375.32  4597.2  373.51
  4653.8  371.55  4682.2  371.64  4696.3  370.26  4731.8   370.8  4752.9  369.53
    4774  369.69  4802.3  367.26  4908.4  364.29  4936.9  364.71    4951  360.94
    4958  360.67  4979.3  362.35  4993.5   360.2  4997.4  357.83  5006.9  359.08
  5016.9  362.04    5027  364.55  5087.5  365.73  5188.3   370.6  5208.5   370.6
    5225   372.1  5359.7  375.64  5410.1  378.16  5440.4  377.46  5500.9  381.38
#Mann= 4 ,-1 , 0
  4441.7     .11       0  4908.4     .17       0  4979.3     .09       0
  5016.9     .17       0
Bank Sta=4979.3,5016.9
XS Rating Curve= 0 ,0
Exp/Cntr=0.3,0.1

Type RM Length L Ch R = 1 ,13535   ,340,340,340
BEGIN DESCRIPTION:
CCLC 037 27.0
END DESCRIPTION:
XS GIS Cut Line= 3
      3678669.69      10154053.9       3678482.2     10153569.55
      3678242.76     10153267.65
#Sta/Elev= 30
  4475.9  381.86  4682.7  370.74  4779.2  366.93  4827.3   366.6  4875.7  364.46
  4906.4  361.34  4918.6  362.78  4936.4  362.71  4941.7  361.34  4960.9  361.95
  4966.3  359.55  4990.9  359.88  5003.3  355.23  5006.8  355.23  5011.4  359.49
  5018.9  359.25  5046.6  363.79  5075.5  364.25  5089.9  361.38  5096.3  363.27
  5104.3  362.17  5118.8  362.56  5125.2  364.22  5133.2   363.6  5139.6  365.22
    5154  364.28  5160.4  366.24  5181.6  367.34  5345.9  374.08  5380.6  375.47
#Mann= 5 ,-1 , 0
  4475.9     .11       0  4990.9     .06       0  5011.4     .17       0
  5181.6     .11       0  5345.9     .17       0
Bank Sta=4990.9,5011.4
XS Rating Curve= 0 ,0
Exp/Cntr=0.3,0.1

Type RM Length L Ch R = 1 ,13195   ,333,333,333
BEGIN DESCRIPTION:
Mapping XS c10a2298
END DESCRIPTION:
XS GIS Cut Line= 2
      3679147.15     10153637.27      3678321.78     10153172.57
#Sta/Elev= 30
  4526.7  376.14  4686.5  371.86  4799.5  367.08  4816.5  366.73  4832.4  361.94
  4838.2  361.53  4847.2  361.17  4854.1   363.6  4859.9  361.54    4870  362.83
  4875.8  360.85  4881.7  361.74  4897.5   356.8  4927.6  356.27    4935  357.79
  4938.8  356.23    4939  355.73  4942.8  356.23  4956.7  360.35  4962.5  357.92
  4984.9   359.2  4994.3  358.02  5007.9   356.7  5021.7  357.93  5091.5  360.99
  5124.3  360.34  5237.1  363.34  5317.7  367.82  5420.6  371.28  5473.9  375.15
#Mann= 7 ,-1 , 0
  4526.7     .17       0  4799.5     .11       0  4938.8     .11       0
  4942.8     .11       0  4994.3     .07       0  5021.7     .11       0
  5091.5     .17       0
Bank Sta=4994.3,5021.7
XS Rating Curve= 0 ,0
Exp/Cntr=0.3,0.1

Type RM Length L Ch R = 1 ,12862   ,311,311,311
BEGIN DESCRIPTION:
CCLC 037 26.0
END DESCRIPTION:
XS GIS Cut Line= 3
      3679383.26     10153366.43      3678737.41      10153081.7
      3678167.92     10152852.52
#Sta/Elev= 30
  4438.9  372.16    4515  369.88  4532.2  370.42  4584.5  367.33  4608.3  366.82
  4613.8  365.19  4637.1  364.68  4642.5   363.3    4729  360.39  4735.8  361.19
  4794.5     359  4811.3  359.94  4816.7   358.6  4834.6  359.58  4840.1  358.34
  4849.2  359.31  4915.5  359.01  4985.5  356.26  4989.5  354.18  5002.2  356.18
  5078.7  356.14  5084.2  357.75  5100.5  358.61  5160.1  359.89  5315.7  366.89
  5372.5  369.27    5597  377.25  5638.3  379.84  5697.5  380.76  5758.6  383.89
#Mann= 6 ,-1 , 0
  4438.9     .17       0  4584.5     .11       0  4985.5     .07       0
  5002.2     .11       0  5315.7     .17       0  5372.5     .11       0
Bank Sta=4985.5,5002.2
XS Rating Curve= 0 ,0
Exp/Cntr=0.3,0.1

Type RM Length L Ch R = 1 ,12551   ,551,551,551
BEGIN DESCRIPTION:
CCLC 037 25.0
END DESCRIPTION:
XS GIS Cut Line= 3
      3679517.88     10153161.09      3679008.24     10152887.26
      3678274.01     10152575.56
#Sta/Elev= 30
  4501.4  369.28  4550.2  367.73  4591.5  366.25  4597.2  367.33    4649  365.12
  4747.6  358.12  4774.1  357.25  4810.7  356.82    4842  353.74  4870.8  353.78
  4892.7  355.42  4930.8  355.46  4952.8  353.92  4974.7  355.45  4996.6  355.38
  5010.5  352.62    5014  352.62  5018.5  355.24  5040.4  354.21  5056.7  355.56
  5062.3  358.13  5123.8  360.33  5167.3  360.22  5255.5  362.56  5360.9  364.09
  5419.1  362.93  5490.1  364.55  5542.8  364.87  5548.3   364.1  5877.6  372.94
#Mann= 7 ,-1 , 0
  4501.4     .11       0  4550.2     .17       0  4747.6     .11       0
  4774.1     .17       0  4996.6     .09       0  5018.5     .17       0
  5255.5     .11       0
Bank Sta=4996.6,5018.5
XS Rating Curve= 0 ,0
Exp/Cntr=0.3,0.1

Type RM Length L Ch R = 1 ,12000   ,500,500,500
BEGIN DESCRIPTION:
CCLC 037 24.0
END DESCRIPTION:
XS GIS Cut Line= 3
      3679567.88      10152961.1      3679462.59     10152874.08
      3678967.85     10152361.07
#Sta/Elev= 30
  4863.4   366.2  4889.9  364.64  4941.3  362.73  4946.7  361.85  4963.1  358.11
  4969.6  355.39  4977.4   353.4  4983.9   352.9  4991.8  351.91  5019.5  352.78
  5047.8  353.22  5090.3   352.5  5118.6  353.77  5154.1  354.22  5196.5  353.18
  5231.8  353.49  5251.1  351.79  5260.1  352.64  5281.4  352.69  5288.4  354.02
  5321.4  354.59  5351.3  353.93  5380.2  353.88  5471.1   356.7  5487.9  357.46
  5535.8  359.08    5550   360.5  5612.9  362.91  5656.2  364.17  5712.7   367.3
#Mann= 10 ,-1 , 0
  4863.4     .15       0  4889.9     .17       0  4946.7     .15       0
  4983.9     .09       0  5019.5     .15       0  5321.4     .11       0
  5351.3     .15       0  5471.1     .11       0  5487.9     .15       0
  5612.9     .17       0
Bank Sta=4983.9,5019.5
XS Rating Curve= 0 ,0
Exp/Cntr=0.3,0.1

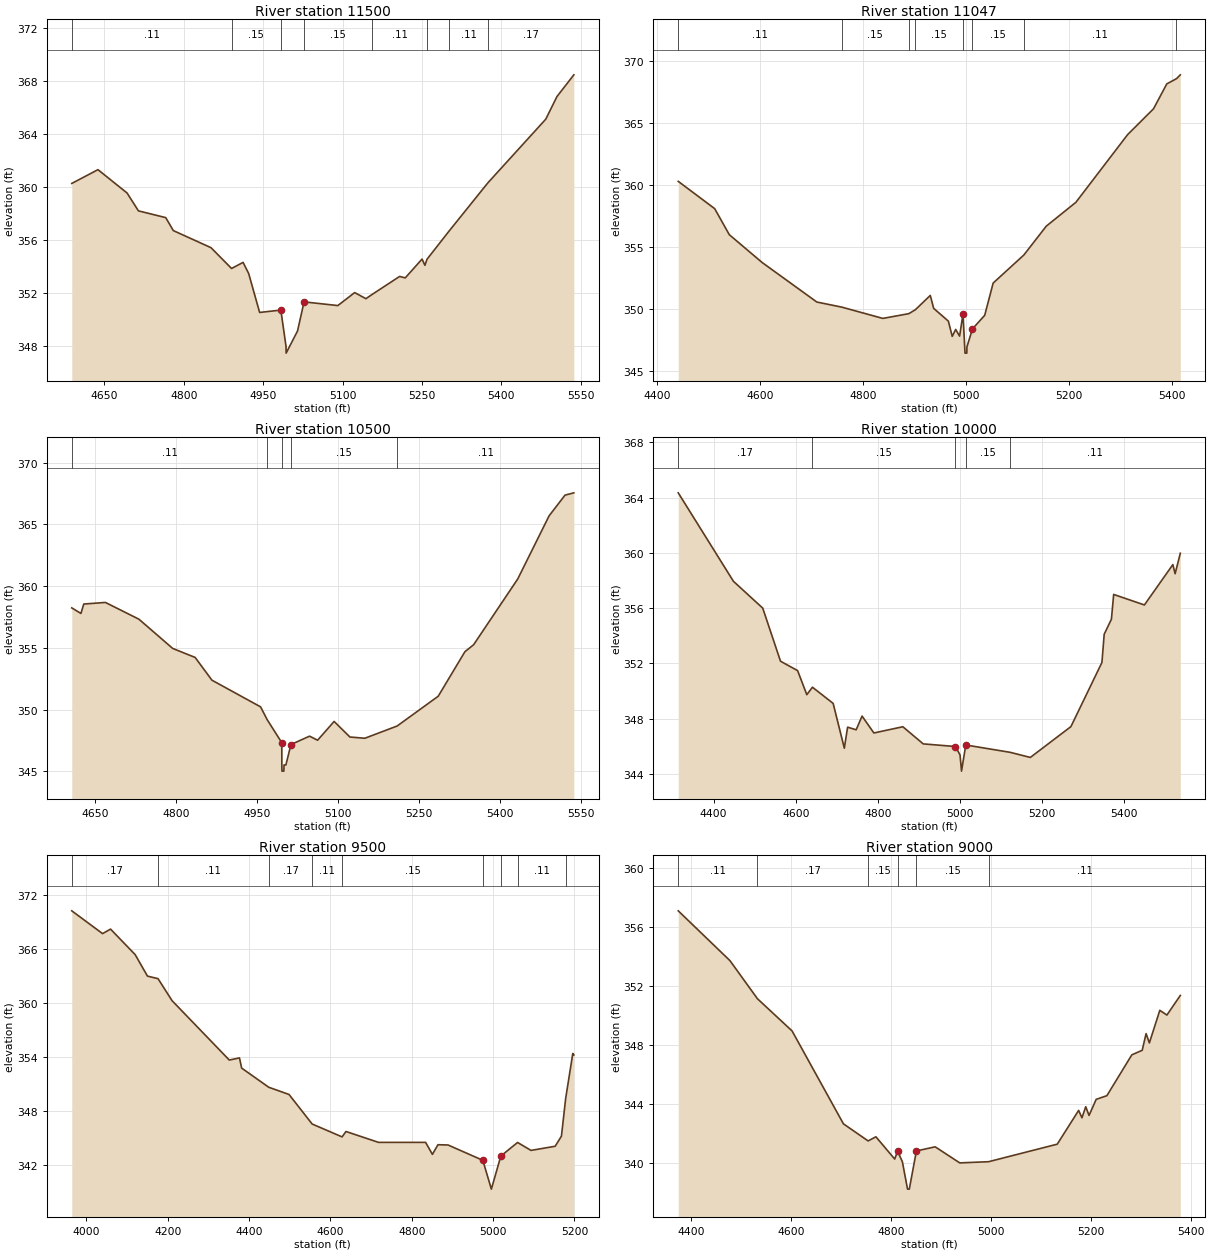
Type RM Length L Ch R = 1 ,11500   ,453,453,453
BEGIN DESCRIPTION:
CCLC 037 23.0
END DESCRIPTION:
XS GIS Cut Line= 3
      3679867.86     10152561.08      3679473.56     10152442.31
      3678967.86     10152261.07
#Sta/Elev= 30
  4588.2   360.3  4637.7  361.34  4692.7  359.58  4714.2  358.23  4765.8  357.72
  4780.2  356.74  4851.4  355.45  4890.2  353.88    4912  354.34  4922.6   353.5
  4943.3  350.56  4983.4  350.74  4993.2  347.99  4993.4  347.49  5014.9  349.16
  5027.3  351.36  5091.1  351.08  5122.9  352.06  5144.2   351.6  5156.3  351.93
  5207.9  353.28  5218.5  353.17  5250.3  354.59  5255.7  354.12  5259.7  354.58
  5301.7  356.72  5374.6  360.34  5484.1  365.15  5505.3  366.86  5537.2   368.5
#Mann= 8 ,-1 , 0
  4588.2     .11       0  4890.2     .15       0  4983.4     .09       0
  5027.3     .15       0  5156.3     .11       0  5259.7     .15       0
  5301.7     .11       0  5374.6     .17       0
Bank Sta=4983.4,5027.3
XS Rating Curve= 0 ,0
Exp/Cntr=0.3,0.1

Type RM Length L Ch R = 1 ,11047   ,547,547,547
BEGIN DESCRIPTION:
CCLC 037 22.0
END DESCRIPTION:
XS GIS Cut Line= 3
      3679867.83     10152461.05      3679445.74     10152088.65
        3679036.     10152053.92
#Sta/Elev= 30
  4441.4  360.32  4512.1  358.12  4540.5  356.02  4604.1  353.78  4710.3  350.59
  4758.6  350.18  4838.3  349.27  4888.6  349.65  4901.2  349.96  4930.4  351.12
    4937  350.08  4965.5  349.05    4973  347.82  4979.7  348.38  4987.3  347.84
  4993.9  349.64  4997.8  346.47  5001.3  346.47  5001.5  346.97  5012.2  348.42
    5036  349.52  5052.4  352.12  5111.9  354.38  5155.5  356.71  5212.9  358.63
  5313.3  364.09  5363.5  366.17  5389.3  368.18  5408.1   368.6  5415.5  368.91
#Mann= 8 ,-1 , 0
  4441.4     .11       0  4758.6     .15       0  4888.6     .11       0
  4901.2     .15       0  4993.9     .09       0  5012.2     .15       0
  5111.9     .11       0  5408.1     .17       0
Bank Sta=4993.9,5012.2
XS Rating Curve= 0 ,0
Exp/Cntr=0.3,0.1

Type RM Length L Ch R = 1 ,10500   ,500,500,500
BEGIN DESCRIPTION:
CCLC 037 21.0
END DESCRIPTION:
XS GIS Cut Line= 3
      3679967.85     10152411.06      3679861.72     10152032.97
      3679605.44     10151560.84
#Sta/Elev= 30
  4607.3  358.24  4624.3  357.79  4629.5  358.55  4669.6  358.68  4731.8  357.32
  4794.2  354.96  4835.8  354.23  4866.9  352.39    4957  350.23  4969.3  349.19
  4996.3  347.33  4996.4  345.53  4996.6  345.03  5000.1  345.03  5000.4  345.53
  5003.9  345.53  5013.2  347.18  5047.7  347.86  5062.6  347.53  5093.2  349.05
  5122.5  347.79  5150.1  347.69  5209.9  348.68    5286  351.09  5335.4  354.69
  5351.6  355.26  5433.3  360.58  5491.4  365.69  5520.8  367.36  5537.2  367.55
#Mann= 5 ,-1 , 0
  4607.3     .11       0  4969.3     .15       0  4996.3     .09       0
  5013.2     .15       0  5209.9     .11       0
Bank Sta=4996.3,5013.2
XS Rating Curve= 0 ,0
Exp/Cntr=0.3,0.1

Type RM Length L Ch R = 1 ,10000   ,500,500,500
BEGIN DESCRIPTION:
CCLC 037 20.0
END DESCRIPTION:
XS GIS Cut Line= 3
      3680681.82     10152276.11      3680253.76     10151740.05
      3679765.16     10151519.19
#Sta/Elev= 30
    4314  364.34  4448.4  357.94  4519.7     356    4563  352.16  4604.6  351.48
    4627  349.74  4640.7  350.28  4691.1  349.11  4718.3  345.87  4726.3  347.39
  4747.1   347.2  4761.5  348.19  4790.3  346.97  4860.8  347.42  4910.4  346.18
  4988.9  345.99    5000  345.38  5003.6  344.21 5013.98346.1007    5122  345.57
  5171.1   345.2  5269.9  347.43  5345.4  352.07  5350.9  354.11  5368.5   355.2
    5374  356.99  5448.8  356.23  5518.1  359.15  5523.6  358.49  5536.2  359.97
#Mann= 5 ,-1 , 0
    4314     .17       0  4640.7     .15       0  4988.9     .09       0
 5013.98     .15       0    5122     .11       0
Bank Sta=4988.9,5013.98
XS Rating Curve= 0 ,0
Exp/Cntr=0.3,0.1

Type RM Length L Ch R = 1 ,9500    ,500,500,500
BEGIN DESCRIPTION:
CCLC 037 19.0
END DESCRIPTION:
XS GIS Cut Line= 3
      3680867.86      10152361.1      3680504.37     10151391.39
      3680331.25     10151294.47
#Sta/Elev= 30
  3964.4  370.23  4040.1   367.7  4059.7   368.2  4120.2  365.37  4150.5  362.98
  4176.4   362.7    4211  360.25  4351.6  353.66  4376.6   353.9  4381.9  352.77
  4448.6  350.64  4498.4  349.84  4555.2  346.56  4628.8  345.13  4638.3  345.73
  4718.4  344.52  4834.1  344.52  4850.8  343.19  4864.4  344.26  4889.3  344.23
  4974.7  342.53  4995.7  339.33  5018.9     343  5060.1  344.51  5093.1  343.63
  5152.5  344.09  5167.9  345.21  5178.3  349.39  5195.8  354.39  5198.4  354.23
#Mann= 9 ,-1 , 0
  3964.4     .17       0  4176.4     .11       0  4448.6     .17       0
  4555.2     .11       0  4628.8     .15       0  4974.7     .09       0
  5018.9     .15       0  5060.1     .11       0  5178.3     .15       0
Bank Sta=4974.7,5018.9
XS Rating Curve= 0 ,0
Exp/Cntr=0.3,0.1

Type RM Length L Ch R = 1 ,9000    ,500,500,500
BEGIN DESCRIPTION:
CCLC 037 18.0
END DESCRIPTION:
XS GIS Cut Line= 3
      3681188.76     10151269.18      3680642.79     10150962.51
      3680356.84     10150714.84
#Sta/Elev= 30
  4373.8  357.11  4477.3  353.73  4532.2  351.15  4601.6  348.96  4704.3  342.66
  4753.7   341.5  4769.3  341.78  4806.9  340.27  4812.7  340.81  4822.2  340.09
  4832.6  338.23  4836.1  338.23  4850.3  340.82  4887.9   341.1    4937  340.01
  4994.7  340.09  5132.1  341.28  5174.9  343.57  5181.5  343.07  5189.1  343.82
  5195.7  343.23    5210  344.32  5231.4  344.57  5281.3  347.34  5302.1  347.65
  5309.8  348.78  5316.4  348.15  5337.3  350.36  5351.5  350.04  5378.3  351.37
#Mann= 6 ,-1 , 0
  4373.8     .11       0  4532.2     .17       0  4753.7     .15       0
  4812.7     .06       0  4850.3     .15       0  4994.7     .11       0
Bank Sta=4812.7,4850.3
XS Rating Curve= 0 ,0
Exp/Cntr=0.3,0.1

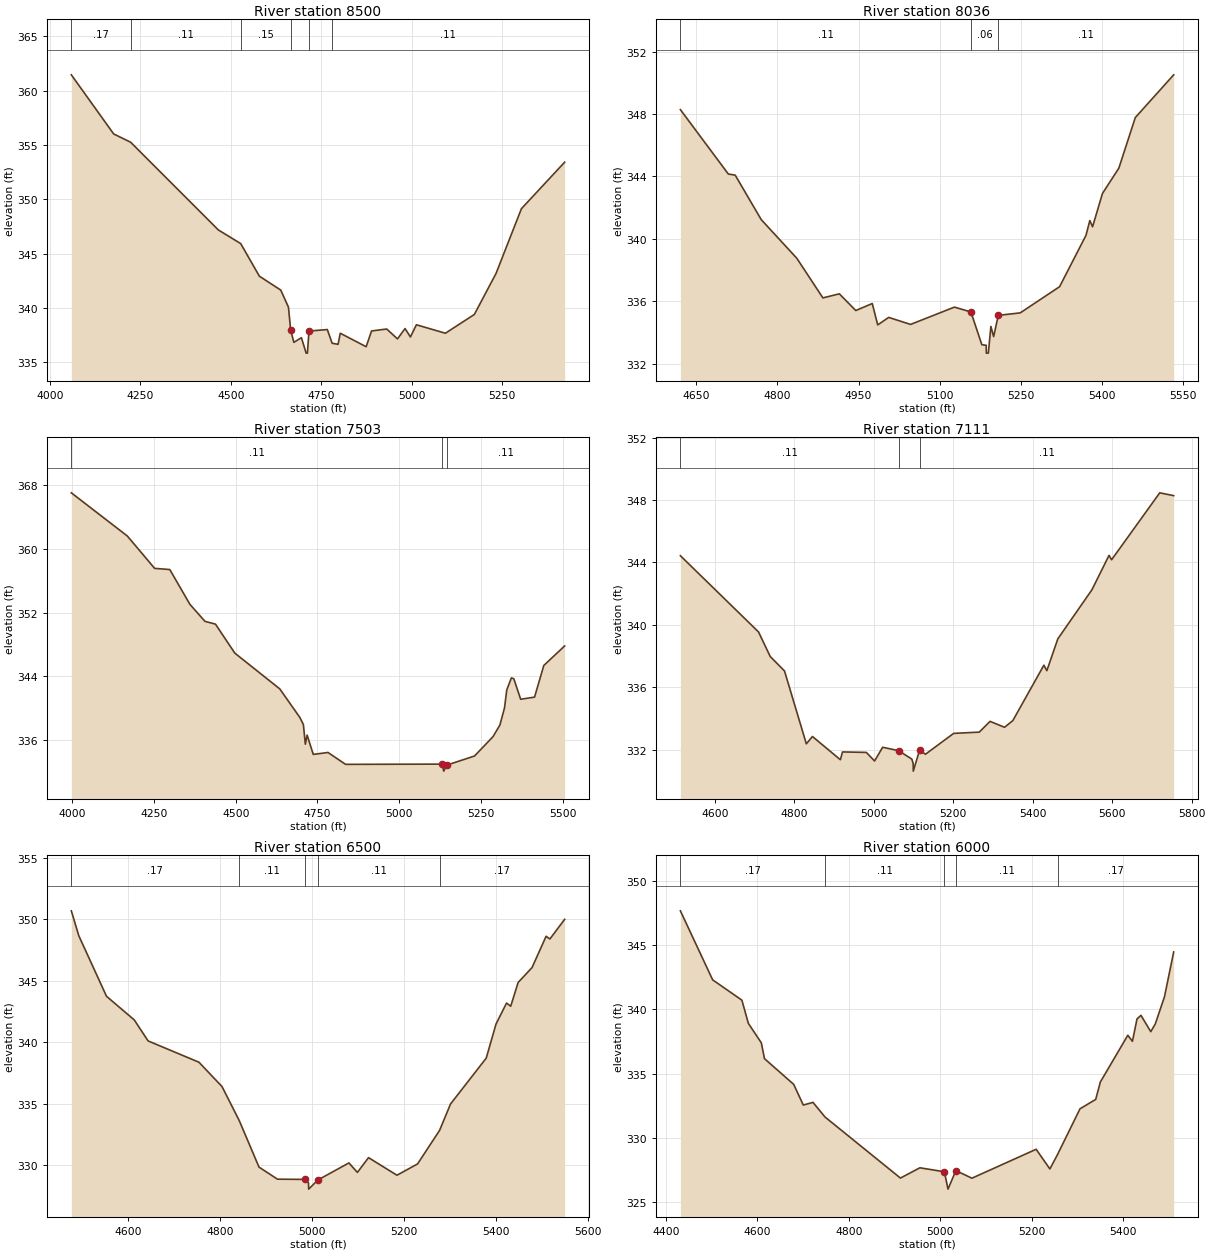
Type RM Length L Ch R = 1 ,8500    ,464,464,464
BEGIN DESCRIPTION:
CCLC 037 17.0
END DESCRIPTION:
XS GIS Cut Line= 3
      3681542.99     10151040.05      3680770.69     10150503.31
      3680348.48     10150512.26
#Sta/Elev= 30
  4059.5  361.46  4176.5  356.02  4223.3  355.26  4465.5  347.19  4527.4  345.93
    4579  342.93  4638.1  341.65  4659.3  340.08  4665.4  337.99  4674.2  336.84
  4695.1  337.27  4708.2  335.85  4711.7  335.85    4716  337.88  4766.7  338.02
    4780  336.76  4796.4  336.66  4802.5  337.68    4874  336.44  4888.9  337.89
  4930.8  338.07  4960.5  337.16  4981.4  338.11  4996.3  337.34  5012.8  338.46
  5092.9  337.68  5172.9  339.41  5232.9  343.19  5302.9  349.14  5422.3  353.42
#Mann= 6 ,-1 , 0
  4059.5     .17       0  4223.3     .11       0  4527.4     .15       0
  4665.4     .06       0    4716     .15       0    4780     .11       0
Bank Sta=4665.4,4716
XS Rating Curve= 0 ,0
Exp/Cntr=0.3,0.1

Type RM Length L Ch R = 1 ,8036    ,533,533,533
BEGIN DESCRIPTION:
CCLC 037 16.0
END DESCRIPTION:
XS GIS Cut Line= 3
      3681317.88     10150111.07      3680869.35     10150185.87
      3680417.83     10150111.07
#Sta/Elev= 30
  4620.5  348.28  4709.2  344.15  4721.9  344.08    4770  341.23  4835.9  338.75
  4884.1  336.21  4914.5  336.47  4944.9   335.4  4975.4  335.85  4985.5  334.48
  5005.8  334.96  5046.3  334.51  5127.4  335.62  5157.8  335.31  5178.1  333.21
  5186.1  333.17  5186.4  332.67  5190.1  332.67  5194.8  334.38  5199.9  333.73
  5208.5  335.09  5249.1  335.25  5321.9  336.93  5370.7  340.22  5377.8  341.17
  5382.9  340.77  5401.1   342.9  5431.5  344.53  5461.9  347.77  5532.9  350.51
#Mann= 3 , 0 , 0
  4620.5     .11       0  5157.8     .06       0  5208.5     .11       0
Bank Sta=5157.8,5208.5
XS Rating Curve= 0 ,0
Exp/Cntr=0.3,0.1

Type RM Length L Ch R = 1 ,7503    ,392,392,392
BEGIN DESCRIPTION:
CCLC 037 15.0
END DESCRIPTION:
XS GIS Cut Line= 3
      3681767.88     10150111.08      3680751.29      10149706.7
      3680467.83      10150011.1
#Sta/Elev= 30
  3996.5  367.04  4167.9  361.62  4251.5  357.56  4297.9  357.41  4359.4  353.05
  4405.5  350.91  4437.7  350.56    4497  346.92  4634.6  342.43  4696.1  338.84
  4706.8  337.96  4712.8  335.49  4718.2  336.63  4737.1  334.21  4782.2  334.45
    4836  332.96  5131.5  332.99  5136.5  332.11  5145.7  332.86  5230.7  334.01
  5287.3  336.44  5308.4   337.9  5322.5  340.06  5329.4  342.31  5343.5  343.81
  5350.9  343.71  5371.9  341.13  5414.4   341.4  5442.7  345.37  5506.5  347.82
#Mann= 3 , 0 , 0
  3996.5     .11       0  5131.5     .06       0  5145.7     .11       0
Bank Sta=5131.5,5145.7
XS Rating Curve= 0 ,0
Exp/Cntr=0.3,0.1

Type RM Length L Ch R = 1 ,7111    ,611,611,611
BEGIN DESCRIPTION:
CCLC 037 14.0
END DESCRIPTION:
XS GIS Cut Line= 3
      3681341.53     10149463.64      3680765.18     10149380.31
      3680342.71      10149885.9
#Sta/Elev= 30
  4513.6  344.43  4710.3  339.54  4739.6  337.97  4775.6  337.04  4830.5  332.37
  4845.9  332.84  4916.2  331.35  4921.5  331.85  4981.4  331.82  5002.3  331.27
  5022.5  332.15  5062.9  331.93  5095.9  331.39  5099.3  331.12  5099.6  330.62
  5115.8  331.99  5130.1   331.7  5201.2  333.04  5265.5  333.12  5292.8  333.81
  5329.2  333.43  5350.1  333.86  5428.2  337.41  5435.7  337.06  5463.3   339.1
  5549.2  342.25  5592.1  344.45  5598.6  344.17  5719.7  348.46  5754.8  348.28
#Mann= 3 , 0 , 0
  4513.6     .11       0  5062.9     .06       0  5115.8     .11       0
Bank Sta=5062.9,5115.8
XS Rating Curve= 0 ,0
Exp/Cntr=0.3,0.1

Type RM Length L Ch R = 1 ,6500    ,500,500,500
BEGIN DESCRIPTION:
CCLC 037 13.0
END DESCRIPTION:
XS GIS Cut Line= 3
      3681404.06     10148949.76      3680883.61     10148901.25
      3680367.86     10148711.07
#Sta/Elev= 30
  4477.3  350.68  4493.6  348.65  4553.8  343.73  4614.1  341.81  4644.2   340.1
  4754.7  338.37  4804.9  336.39  4842.5  333.61  4885.3  329.84  4925.4  328.86
  4985.7  328.84  4992.9  328.55  4993.2  328.05  5013.2  328.79  5080.7  330.18
  5099.2  329.41  5123.4  330.61  5185.2  329.18    5230   330.1  5277.9  332.83
  5301.6  334.97  5379.2   338.7  5400.5  341.47  5423.4  343.18  5432.5  342.92
  5448.5  344.85  5478.9  346.07  5509.4  348.61  5517.7  348.39  5549.7  349.99
#Mann= 5 ,-1 , 0
  4477.3     .17       0  4842.5     .11       0  4985.7     .06       0
  5013.2     .11       0  5277.9     .17       0
Bank Sta=4985.7,5013.2
XS Rating Curve= 0 ,0
Exp/Cntr=0.3,0.1

Type RM Length L Ch R = 1 ,6000    ,439,439,439
BEGIN DESCRIPTION:
CCLC 037 12.0
END DESCRIPTION:
XS GIS Cut Line= 3
      3681367.87     10148861.09      3680976.57     10148448.55
      3680467.85     10148411.07
#Sta/Elev= 30
  4431.4  347.66    4502  342.29  4565.9  340.71  4580.1   338.9  4608.4  337.39
  4615.3  336.16  4679.2  334.16  4700.2  332.55  4721.3  332.76  4747.7  331.62
  4912.6  326.87  4955.1  327.67  5008.7  327.36  5016.6  326.01  5033.8  327.45
  5068.9  326.86  5209.3  329.11  5239.4  327.58  5256.1   328.7  5305.3  332.26
  5339.6  332.99  5349.7  334.34  5409.8  337.98  5419.9  337.51  5429.9  339.25
  5438.5  339.53    5460  338.26    5470  338.87    5490  340.98  5510.1  344.46
#Mann= 5 ,-1 , 0
  4431.4     .17       0  4747.7     .11       0  5008.7     .06       0
  5033.8     .11       0  5256.1     .17       0
Bank Sta=5008.7,5033.8
XS Rating Curve= 0 ,0
Exp/Cntr=0.3,0.1

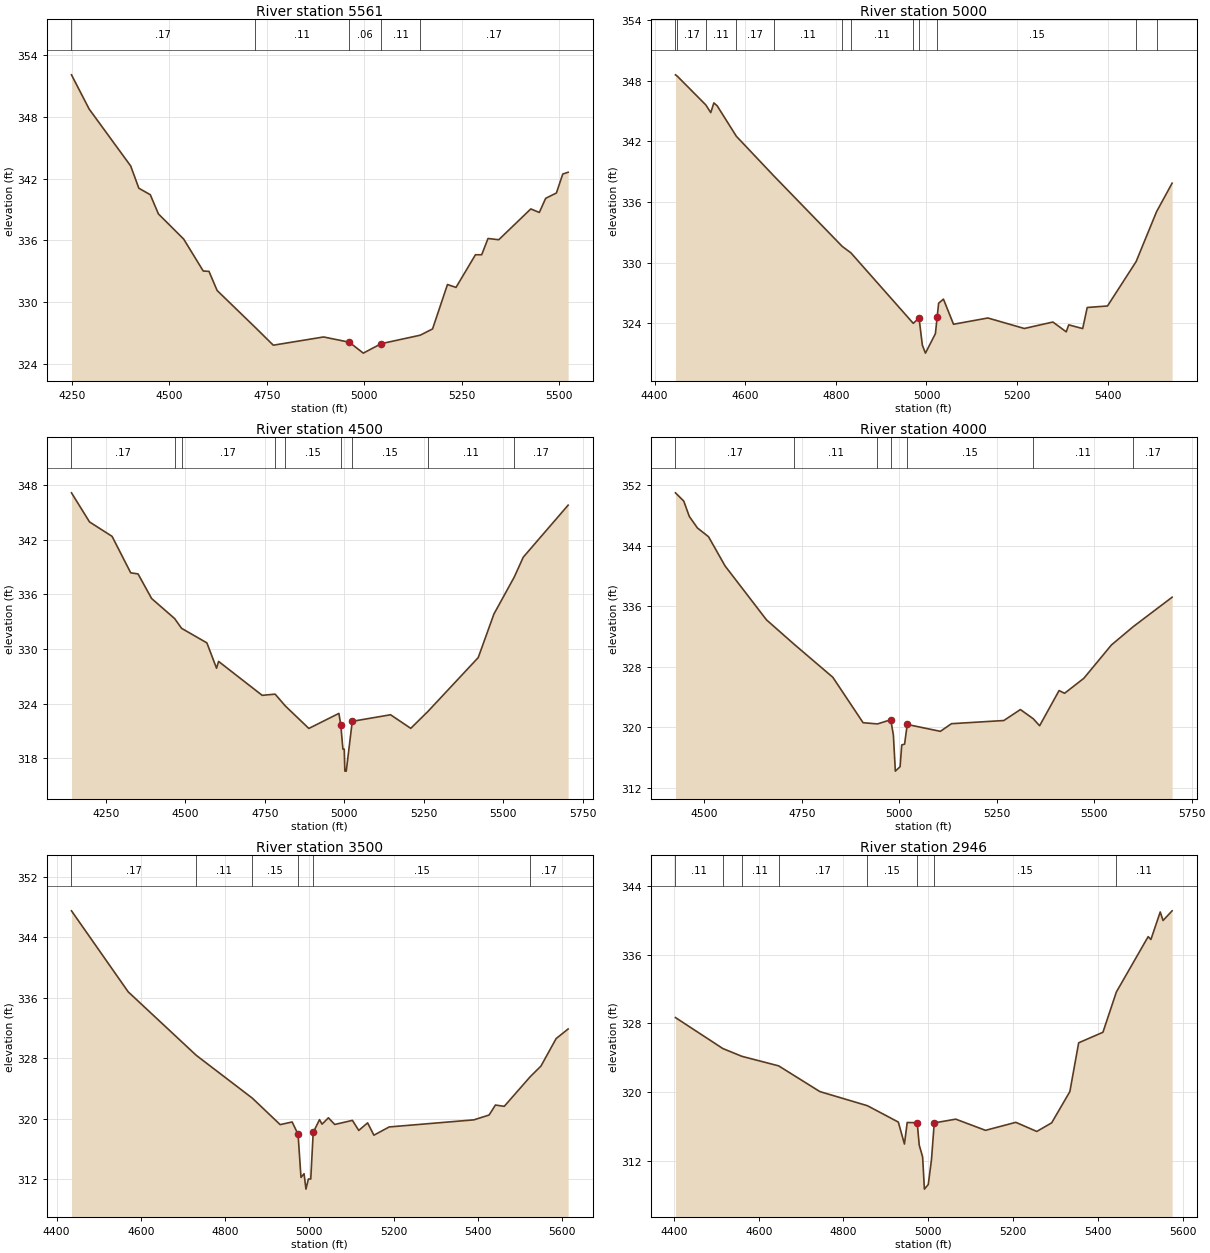
Type RM Length L Ch R = 1 ,5561    ,561,561,561
BEGIN DESCRIPTION:
CCLC 037 11.0
END DESCRIPTION:
XS GIS Cut Line= 3
      3681647.12     10148484.47      3681140.18     10148116.43
      3680567.89     10147811.09
#Sta/Elev= 30
  4248.6  352.08  4293.9  348.76  4400.6  343.23  4421.5  341.07  4450.9  340.44
  4471.7  338.58  4536.7  336.13  4586.9  333.03  4601.6     333  4622.5  331.14
  4720.3  327.56  4766.7  325.83  4895.9  326.63  4961.7  326.12  4997.8  325.06
  5043.9  325.98  5143.9   326.8  5175.6  327.41  5213.9  331.72  5235.8  331.44
  5285.7  334.61  5301.7  334.61    5318  336.19  5345.6  336.07  5427.8  339.06
  5449.7  338.72    5466  340.09  5493.6  340.61  5509.9  342.45  5523.7  342.62
#Mann= 5 ,-1 , 0
  4248.6     .17       0  4720.3     .11       0  4961.7     .06       0
  5043.9     .11       0  5143.9     .17       0
Bank Sta=4961.7,5043.9
XS Rating Curve= 0 ,0
Exp/Cntr=0.3,0.1

Type RM Length L Ch R = 1 ,5000    ,500,500,500
BEGIN DESCRIPTION:
CCLC 037 10.0
END DESCRIPTION:
XS GIS Cut Line= 3
      3681767.85     10148061.07      3681362.36     10147683.58
      3680867.82     10147461.06
#Sta/Elev= 30
    4446   348.6  4450.4  348.45    4513  345.62  4523.9  344.86  4530.8  345.82
  4538.1  345.53  4580.5  342.51  4663.6  338.57  4814.1  331.61  4833.3  330.97
  4970.9  323.99  4983.7  324.51    4991  321.83  4997.8  321.04  5019.8  322.97
 5023.72 324.632  5026.9  325.98  5037.5  326.39  5059.8   323.9  5135.6  324.52
    5216  323.48  5279.1  324.12  5308.6  323.15  5314.1  323.84  5344.9  323.47
  5354.9  325.56  5399.7  325.71  5462.9  330.11    5508  335.05  5542.3  337.87
#Mann= 12 ,-1 , 0
    4446     .11       0  4450.4     .17       0    4513     .11       0
  4580.5     .17       0  4663.6     .11       0  4814.1     .17       0
  4833.3     .11       0  4970.9     .15       0  4983.7     .09       0
 5023.72     .15       0  5462.9     .17       0    5508     .11       0
Bank Sta=4983.7,5023.72
XS Rating Curve= 0 ,0
Exp/Cntr=0.3,0.1

Type RM Length L Ch R = 1 ,4500    ,500,500,500
BEGIN DESCRIPTION:
CCLC 037 9.0
END DESCRIPTION:
XS GIS Cut Line= 3
      3681855.44     10147949.73      3681405.79     10147218.99
      3680917.87     10146711.09
#Sta/Elev= 30
    4142  347.12  4198.7  343.93  4269.6  342.35  4328.3  338.35  4351.4  338.23
  4393.9  335.54  4466.6  333.33  4488.1  332.27  4567.9  330.67  4598.3  327.89
  4604.6  328.64  4741.8  324.92  4782.6  325.05  4814.2  323.77  4888.6  321.29
  4983.2  322.94  4989.1  321.67  4995.8  319.02    5000  319.02  5001.9  316.61
  5006.3  316.61  5025.2  322.07  5145.7  322.79  5209.2   321.3  5263.1  323.15
  5421.5  329.06  5470.8  333.83    5535   337.9    5563  340.06  5704.3  345.77
#Mann= 9 ,-1 , 0
    4142     .17       0  4466.6     .11       0  4488.1     .17       0
  4782.6     .11       0  4814.2     .15       0  4989.1     .09       0
  5025.2     .15       0  5263.1     .11       0    5535     .17       0
Bank Sta=4989.1,5025.2
XS Rating Curve= 0 ,0
Exp/Cntr=0.3,0.1

Type RM Length L Ch R = 1 ,4000    ,500,500,500
BEGIN DESCRIPTION:
CCLC 037 8.0
END DESCRIPTION:
XS GIS Cut Line= 3
      3682167.87     10147411.09        3681779.     10146989.16
      3681267.84     10146511.06
#Sta/Elev= 30
  4426.2     351  4447.5  349.91  4461.7  347.88  4482.6  346.35    4511   345.2
  4553.5  341.33  4659.6  334.21  4729.9  331.01  4829.7  326.62  4907.4  320.61
  4944.3  320.45  4978.3     321  4985.1  318.97  4990.1  314.21  5002.3   314.8
  5006.5  317.67  5013.8  317.78  5020.6  320.38  5105.6  319.47    5134  320.48
  5268.3   320.9  5310.8  322.35  5343.9  321.13  5360.1  320.21    5410  324.86
  5424.1   324.5  5473.5  326.48  5544.3  330.89  5600.5  333.32  5699.9   337.2
#Mann= 7 ,-1 , 0
  4426.2     .17       0  4729.9     .11       0  4944.3     .15       0
  4978.3     .09       0  5020.6     .15       0  5343.9     .11       0
  5600.5     .17       0
Bank Sta=4978.3,5020.6
XS Rating Curve= 0 ,0
Exp/Cntr=0.3,0.1

Type RM Length L Ch R = 1 ,3500    ,554,554,554
BEGIN DESCRIPTION:
CCLC 037 7.0
END DESCRIPTION:
XS GIS Cut Line= 3
      3682417.87     10147011.09      3682028.18     10146602.53
      3681517.88     10146261.09
#Sta/Elev= 30
  4435.4  347.53  4569.9  336.81  4731.3  328.41  4864.6  322.73  4930.6  319.23
    4959  319.58  4973.1  317.95    4980  312.24  4987.3  312.73  4991.8  310.69
  4997.6  312.03  5003.2  312.03    5009  318.19    5024  319.89    5030  319.29
    5045  320.13  5060.1  319.25  5102.1  319.79  5117.1  318.46  5138.1  319.46
  5153.1  317.83  5189.2  318.92  5390.3  319.86  5426.4   320.5  5441.4  321.82
  5462.4  321.65  5523.8  325.56  5549.5  326.98  5585.5  330.62    5614  331.89
#Mann= 6 ,-1 , 0
  4435.4     .17       0  4731.3     .11       0  4864.6     .15       0
  4973.1     .09       0    5009     .15       0  5523.8     .17       0
Bank Sta=4973.1,5009
XS Rating Curve= 0 ,0
Exp/Cntr=0.3,0.1

Type RM Length L Ch R = 1 ,2946    ,612,612,612
BEGIN DESCRIPTION:
CCLC 037 6.0
END DESCRIPTION:
XS GIS Cut Line= 3
      3682617.84     10146561.06      3682251.29     10146116.43
      3681867.87      10145661.1
#Sta/Elev= 30
  4403.7  328.68  4515.5  325.08  4560.2  324.18  4647.1  323.07  4744.4  320.08
  4856.5  318.44  4929.4  316.54  4943.8  313.99  4950.3  316.49 4973.89316.4689
  4978.7  313.87  4986.7  312.49  4990.9  308.75    5000  309.29  5007.6  312.18
  5014.1  316.44  5064.8  316.88    5135  315.58  5206.5  316.51    5256  315.45
  5291.1  316.45    5334  320.08  5354.8  325.75    5412  326.97  5443.7  331.65
  5518.7  338.08  5525.2  337.75  5547.2  340.95  5553.8  339.96  5575.2  341.08
#Mann= 8 ,-1 , 0
  4403.7     .11       0  4515.5     .17       0  4560.2     .11       0
  4647.1     .17       0  4856.5     .15       0 4973.89     .09       0
  5014.1     .15       0  5443.7     .11       0
Bank Sta=4973.89,5014.1
XS Rating Curve= 0 ,0
Exp/Cntr=0.3,0.1

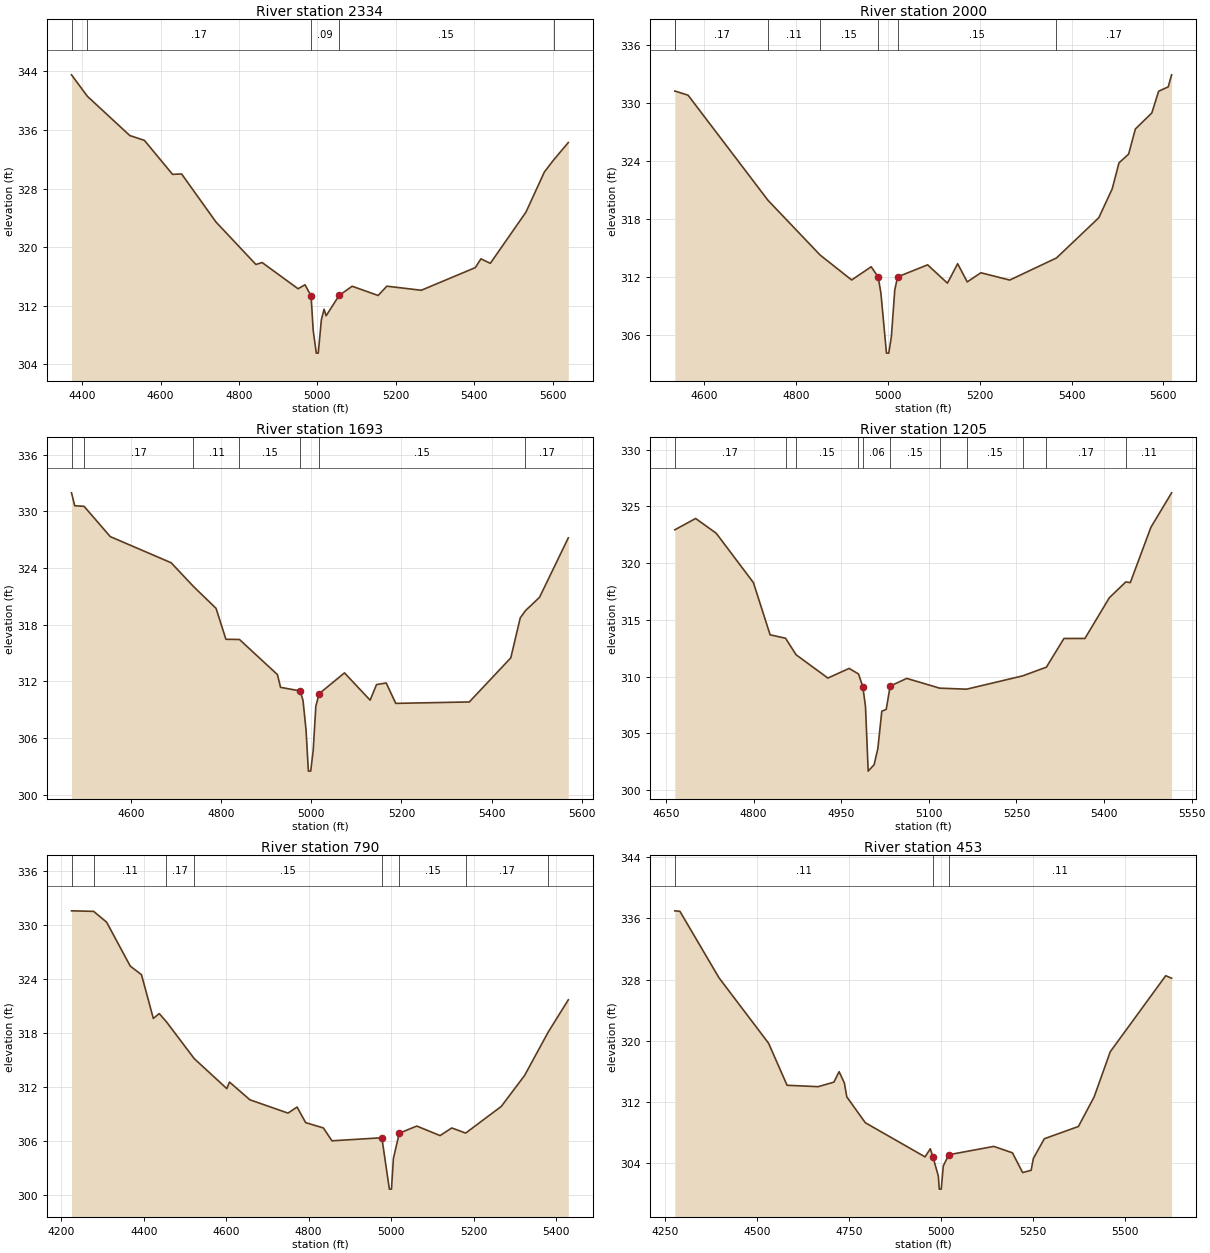
Type RM Length L Ch R = 1 ,2334    ,334,334,334
BEGIN DESCRIPTION:
CCLC 037 5.0
END DESCRIPTION:
XS GIS Cut Line= 3
      3683160.99     10146060.85      3682716.57     10145803.93
      3681994.31     10145588.64
#Sta/Elev= 30
    4373  343.53  4413.5   340.6  4521.7  335.24    4559  334.58  4630.7  329.94
  4653.8     330  4741.3  323.45  4843.3  317.64    4859  317.91  4950.8  314.33
  4968.5  314.87    4984  313.35  4989.3  308.68  4997.3  305.54  5002.3  305.54
  5010.2  310.09  5017.1  311.53  5022.4  310.64  5055.5  313.41  5088.7  314.67
    5155  313.41  5177.2  314.68  5264.9  314.12  5402.7  317.21  5417.2  318.41
  5441.1   317.8    5532  324.79  5578.9  330.26  5602.4   331.9    5640  334.29
#Mann= 5 ,-1 , 0
    4373     .11       0  4413.5     .17       0    4984     .09       0
  5055.5     .15       0  5602.4     .17       0
Bank Sta=4984,5055.5
XS Rating Curve= 0 ,0
Exp/Cntr=0.3,0.1

Type RM Length L Ch R = 1 ,2000    ,307,307,307
BEGIN DESCRIPTION:
CCLC 037 4.1
END DESCRIPTION:
XS GIS Cut Line= 3
      3683117.86     10145711.08      3682724.16     10145465.51
      3682217.89      10145111.1
#Sta/Elev= 30
    4536  331.23    4537  331.23  4564.9  330.81  4739.1  319.91  4852.6  314.24
  4921.2  311.66  4963.7  313.03    4979  311.96  4984.9  310.29    4997  304.08
    5002  304.08  5007.7  305.81  5015.1  310.64  5021.2  311.98  5086.6  313.23
  5129.8  311.33    5152  313.35  5172.9  311.46  5202.6  312.41  5265.4  311.65
  5367.2  313.94  5459.4  318.11  5488.6   321.1  5503.4   323.8  5524.3   324.7
  5539.1  327.31  5574.9  328.97  5589.7  331.22  5610.6  331.67    5618  332.92
#Mann= 7 ,-1 , 0
    4536     .11       0    4537     .17       0  4739.1     .11       0
  4852.6     .15       0    4979     .09       0  5021.2     .15       0
  5367.2     .17       0
Bank Sta=4979,5021.2
XS Rating Curve= 0 ,0
Exp/Cntr=0.3,0.1

Type RM Length L Ch R = 1 ,1693    ,488,488,488
BEGIN DESCRIPTION:
CCLC 037 4.0
END DESCRIPTION:
XS GIS Cut Line= 3
      3683267.85     10145511.07      3682848.78     10145184.65
      3682467.83     10144761.05
#Sta/Elev= 30
  4468.8  331.97    4476   330.6  4496.7  330.54  4554.7  327.33  4689.6  324.56
    4739  322.05  4789.1  319.73    4811  316.45    4841  316.43  4925.1  312.71
    4932  311.36  4975.5  310.98  4981.8  309.97  4988.5  306.86  4993.7  302.48
  4998.8  302.48  5004.4  304.67  5010.2  309.36  5017.7  310.69  5073.7  312.89
  5130.5     310  5144.7  311.65  5166.2  311.82  5187.3  309.66  5350.3  309.81
  5442.2  314.48  5463.2  318.72  5474.8  319.49  5505.8  320.89  5569.7   327.2
#Mann= 7 ,-1 , 0
  4468.8     .11       0  4496.7     .17       0    4739     .11       0
    4841     .15       0  4975.5     .09       0  5017.7     .15       0
  5474.8     .17       0
Bank Sta=4975.5,5017.7
XS Rating Curve= 0 ,0
Exp/Cntr=0.3,0.1

Type RM Length L Ch R = 1 ,1205    ,415,415,415
BEGIN DESCRIPTION:
CCLC 037 3.0
END DESCRIPTION:
XS GIS Cut Line= 3
      3683317.84     10144961.06      3683061.43     10144745.62
      3682717.84     10144361.06
#Sta/Elev= 30
  4665.1  322.93  4700.8  323.93    4736  322.63  4799.7  318.28  4828.3  313.68
  4854.7  313.38  4872.8  311.92  4927.2  309.87  4963.6  310.72  4979.6  310.23
 4986.98309.1246  4991.6  307.36  4996.2  301.67  5006.4  302.24  5012.8  303.68
  5019.5  306.95  5027.1  307.11  5033.8  309.16  5062.2  309.84  5118.7  308.98
  5164.7  308.89  5260.6  310.06  5301.3  310.83  5331.4  313.36  5367.3  313.36
  5409.1  316.95  5437.3  318.34    5445  318.28  5480.2  323.15  5515.7  326.19
#Mann= 11 ,-1 , 0
  4665.1     .17       0  4854.7     .11       0  4872.8     .15       0
  4979.6     .11       0 4986.98     .06       0  5033.8     .15       0
  5118.7     .11       0  5164.7     .15       0  5260.6     .11       0
  5301.3     .17       0  5437.3     .11       0
Bank Sta=4986.98,5033.8
XS Rating Curve= 0 ,0
Exp/Cntr=0.3,0.1

Type RM Length L Ch R = 1 ,790     ,337,337,337
BEGIN DESCRIPTION:
CCLC 037 2.0
END DESCRIPTION:
XS GIS Cut Line= 3
      3683817.85     10144861.07      3683222.85     10144364.01
      3682917.84     10144061.06
#Sta/Elev= 30
  4224.7  331.56  4278.4   331.5  4309.9   330.3  4367.2  325.42  4394.5  324.46
  4423.2   319.6  4437.5  320.14  4454.6  319.25  4522.5  315.13  4601.5   311.8
    4608  312.53  4657.4  310.56  4749.8  309.08  4771.9  309.75  4792.8  308.02
  4835.7  307.43  4856.5     306  4977.6  306.34  4995.8  300.63  5000.9  300.63
  5005.6  304.05  5019.8  306.84  5062.2  307.64  5118.8  306.58  5147.1  307.43
  5180.9  306.86  5267.2  309.82  5323.8  313.26  5381.1  318.08  5429.9  321.67
#Mann= 8 ,-1 , 0
  4224.7     .17       0  4278.4     .11       0  4454.6     .17       0
  4522.5     .15       0  4977.6     .09       0  5019.8     .15       0
  5180.9     .17       0  5381.1     .11       0
Bank Sta=4977.6,5019.8
XS Rating Curve= 0 ,0
Exp/Cntr=0.3,0.1

Type RM Length L Ch R = 1 ,453     ,0,0,0
BEGIN DESCRIPTION:
CCLC 037 1.0
END DESCRIPTION:
XS GIS Cut Line= 3
      3683967.84     10144711.06      3683490.71     10144168.13
      3682974.72     10143812.08
#Sta/Elev= 30
  4277.2  336.98    4291  336.92  4397.2  328.24    4532  319.69  4582.2   314.2
  4666.7  314.02  4709.4  314.61  4723.6  315.98  4737.9  314.49  4744.5  312.68
  4794.8  309.31  4957.1  304.85  4971.3  305.91  4978.9  304.77  4993.1  302.36
  4995.7  300.64  5001.1  300.64  5006.6  303.67  5021.5  305.13  5143.8  306.22
  5194.5  305.38  5222.2   302.8  5245.3   303.1  5251.3  304.65  5281.1  307.22
  5373.7  308.82  5416.6   312.7  5460.2  318.58  5610.9  328.51  5626.9  328.18
#Mann= 3 , 0 , 0
  4277.2     .11       0  4978.9     .06       0  5021.5     .11       0
Bank Sta=4978.9,5021.5
XS Rating Curve= 0 ,0
Exp/Cntr=0.3,0.1

Chan Stop Cuts=-1
Use User Specified Reach Order=0
Composite Channel Slope=5