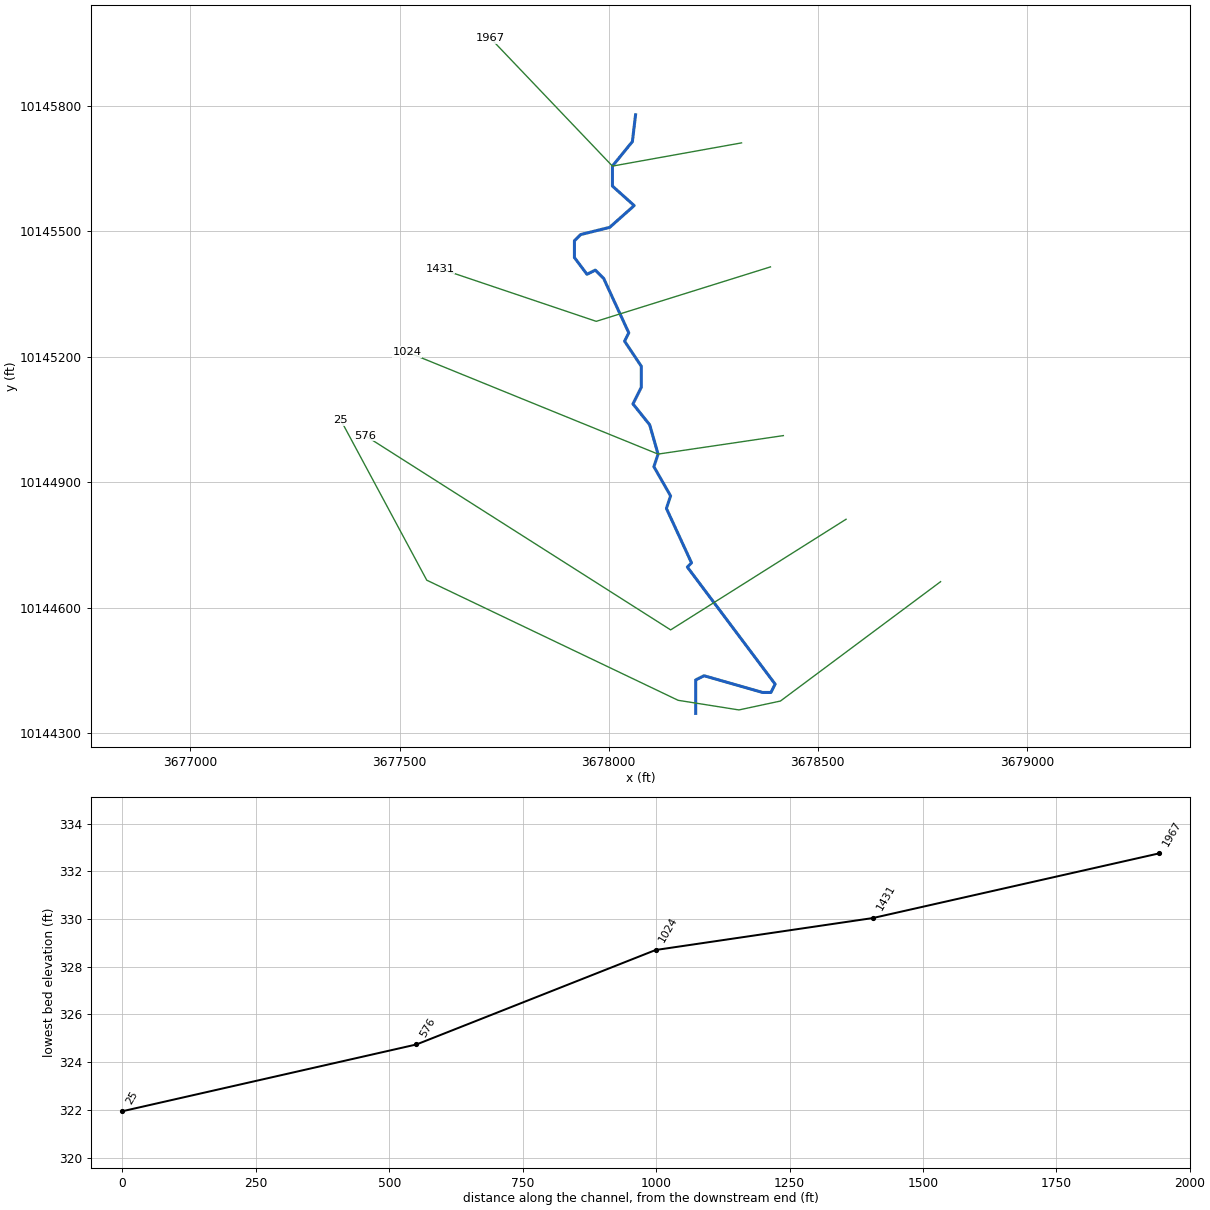
--- CCLC 039.prj (project) ---

Proj Title=CCLC 039 Base Level Engineering
Current Plan=p01
Default Exp/Contr=0.3,0.1
English Units
Geom File=g01
Flow File=f01
Flow File=f02
Plan File=p01
Y Axis Title=Elevation
X Axis Title(PF)=Main Channel Distance
X Axis Title(XS)=Station
BEGIN DESCRIPTION:
CCLC 039
END DESCRIPTION:
DSS Export Rating Curves= 0
DSS Export Rating Curve Sorted= 0
DSS Export Volume Flow Curves= 0
DXF OffsetX= 0
DXF OffsetY= 0
DXF ScaleX= 1
DXF ScaleY= 10

--- CCLC 039.p01 (plan) ---

Plan Title=Multiple Run
Short Identifier=Multiple
Geom File=g01
Flow File=f01
Subcritical Flow
K Sum by GR= 0
Std Step Tol= 0.01
Critical Tol= 0.01
Num of Std Step Trials= 20
Max Error Tol= 0.3
Flow Tol Ratio= 0.001
Split Flow NTrial= 30
Split Flow Tol= 0.02
Split Flow Ratio= 0.02
Log Output Level= 0
Friction Slope Method= 1
Unsteady Friction Slope Method= 2
Unsteady Bridges Friction Slope Method= 1
Parabolic Critical Depth
Global Vel Dist=  1 , 1 , 1
Global Log Level= 0
CheckData=True
Encroach Param= -1, 0, 0, 0
BEGIN DESCRIPTION:
Multiple Run
END DESCRIPTION:

--- CCLC 039.f01 (steady flow) ---

Flow Title=Multiple
Program Version=4.10
Number of Profiles= 7
Profile Names=10-year,25-year,50-year,1pct_min,100-year,1pct_plu,500-year
River Rch & RM=CCLC 039,Reach-1         ,1967
     417     553     736     323     975    2944    1770
Boundary for River Rch & Prof#=CCLC 039,Reach-1         , 1
Up Type= 0
Dn Type= 3
Dn Slope=0.005
Boundary for River Rch & Prof#=CCLC 039,Reach-1         , 2
Up Type= 0
Dn Type= 3
Dn Slope=0.005
Boundary for River Rch & Prof#=CCLC 039,Reach-1         , 3
Up Type= 0
Dn Type= 3
Dn Slope=0.005
Boundary for River Rch & Prof#=CCLC 039,Reach-1         , 4
Up Type= 0
Dn Type= 3
Dn Slope=0.005
Boundary for River Rch & Prof#=CCLC 039,Reach-1         , 5
Up Type= 0
Dn Type= 3
Dn Slope=0.005
Boundary for River Rch & Prof#=CCLC 039,Reach-1         , 6
Up Type= 0
Dn Type= 3
Dn Slope=0.005
Boundary for River Rch & Prof#=CCLC 039,Reach-1         , 7
Up Type= 0
Dn Type= 3
Dn Slope=0.005
DSS Import GetInterval= 0
DSS Import GetPeak= 0
DSS Import FillOption= 0

--- CCLC 039.f02 (steady flow) ---

Flow Title=Orig_BLE_Flows
Program Version=4.10
Number of Profiles= 7
Profile Names=10-year,25-year,50-year,1pct_min,100-year,1pct_plu,500-year
River Rch & RM=CCLC 039,Reach-1         ,1967
     417     542     640     248     750    2264    1029
Boundary for River Rch & Prof#=CCLC 039,Reach-1         , 1
Up Type= 0
Dn Type= 3
Dn Slope=0.005
Boundary for River Rch & Prof#=CCLC 039,Reach-1         , 2
Up Type= 0
Dn Type= 3
Dn Slope=0.005
Boundary for River Rch & Prof#=CCLC 039,Reach-1         , 3
Up Type= 0
Dn Type= 3
Dn Slope=0.005
Boundary for River Rch & Prof#=CCLC 039,Reach-1         , 4
Up Type= 0
Dn Type= 3
Dn Slope=0.005
Boundary for River Rch & Prof#=CCLC 039,Reach-1         , 5
Up Type= 0
Dn Type= 3
Dn Slope=0.005
Boundary for River Rch & Prof#=CCLC 039,Reach-1         , 6
Up Type= 0
Dn Type= 3
Dn Slope=0.005
Boundary for River Rch & Prof#=CCLC 039,Reach-1         , 7
Up Type= 0
Dn Type= 3
Dn Slope=0.005
DSS Import GetInterval= 0
DSS Import GetPeak= 0
DSS Import FillOption= 0

--- CCLC 039.g01 (geometry) ---

Geom Title=Existing Conditions
Program Version=4.10

River Reach=CCLC 039        ,Reach-1
Reach XY= 30
      3678064.45     10145778.16      3678056.85     10145714.14
      3678009.11     10145655.54      3678009.11      10145607.8
      3678061.19     10145561.14       3678002.6     10145509.06
      3677933.23     10145491.84      3677918.23     10145476.84
      3677918.23     10145436.84      3677948.23     10145396.84
      3677968.23     10145406.84      3677988.23     10145386.84
      3678048.23     10145256.84      3678038.23     10145236.84
      3678078.23     10145176.84      3678078.23     10145126.84
      3678058.23     10145086.84      3678098.23     10145036.84
      3678118.23     10144966.84      3678108.23     10144936.84
      3678148.23     10144866.84      3678138.23     10144836.84
      3678198.23     10144706.84      3678188.23     10144696.84
      3678398.23     10144416.84      3678388.23     10144396.84
      3678368.23     10144396.84      3678228.23     10144436.84
      3678208.23     10144426.84      3678208.23     10144346.84

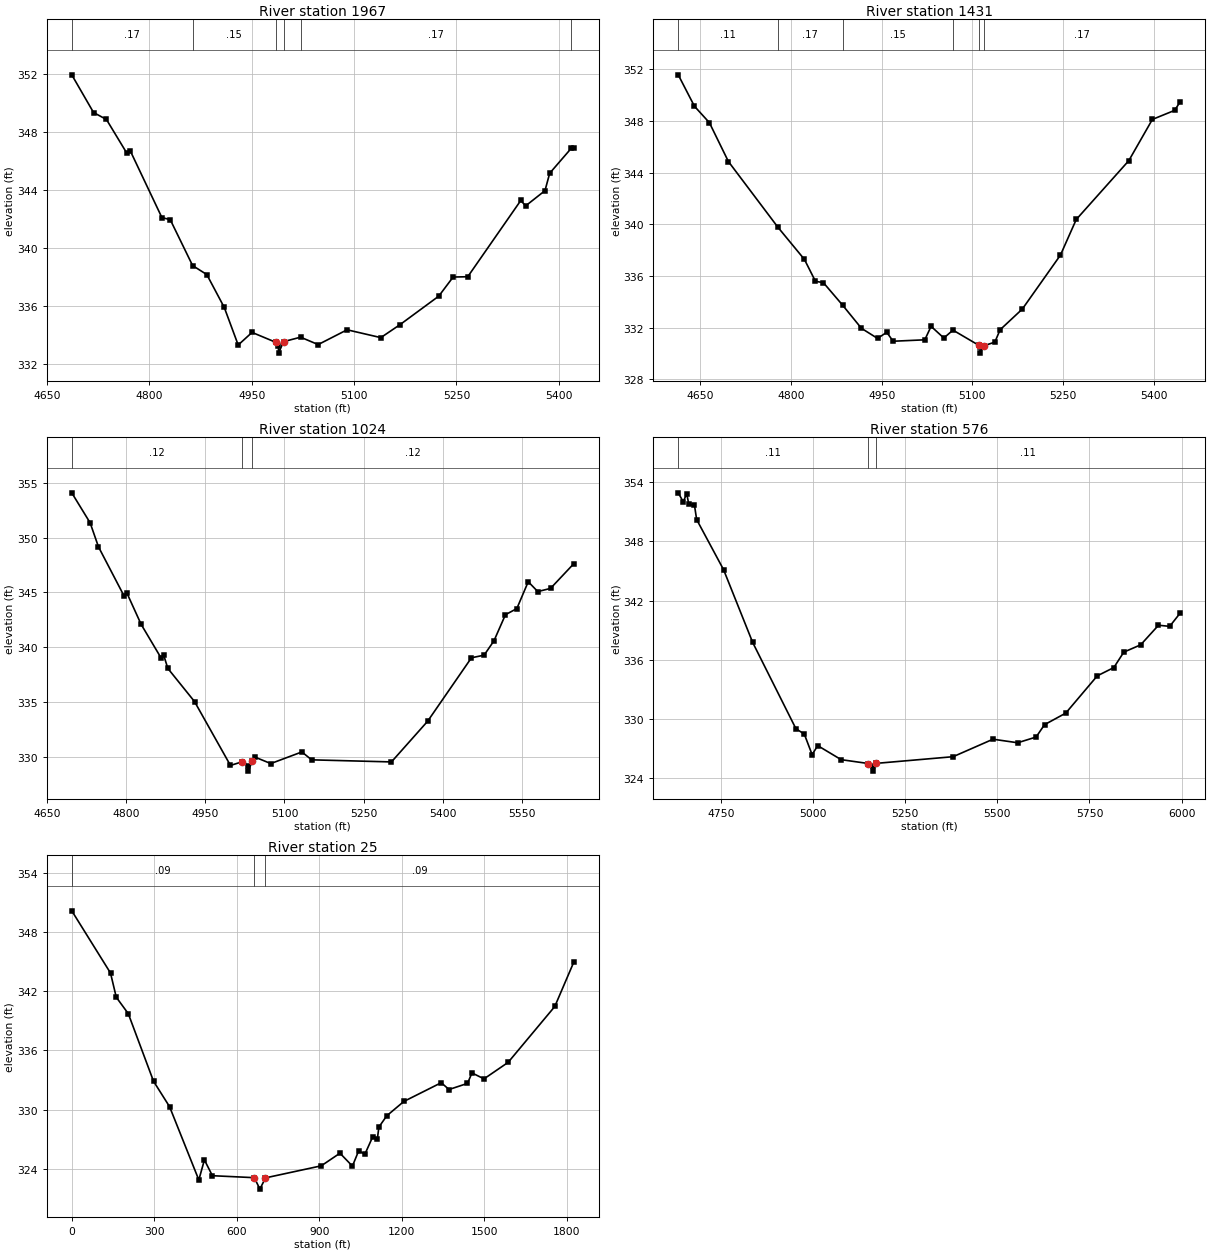
Type RM Length L Ch R = 1 ,1967    ,536,536,536
BEGIN DESCRIPTION:
CCLC 039 4.0
END DESCRIPTION:
XS GIS Cut Line= 3
      3678317.85     10145711.07      3678009.11     10145655.54
      3677717.86     10145961.06
#Sta/Elev= 30
  4686.3  351.95  4718.2  349.35  4737.1  348.87  4766.8  346.56  4771.9  346.72
  4818.4   342.1  4830.6  341.96  4863.4  338.79  4884.2  338.17  4909.8   335.9
  4930.2  333.31  4950.5  334.18 4985.34 333.496  4989.1  333.25  4989.4  332.75
  4996.6  333.54  5021.6  333.85  5047.4  333.34  5089.8  334.36  5139.2  333.82
  5167.5  334.72  5224.1  336.68  5245.2     338  5266.6  338.02  5344.3  343.28
  5351.5  342.91  5379.8  343.96  5386.7  345.16  5418.1  346.87  5422.1  346.91
#Mann= 6 ,-1 , 0
  4686.3     .17       0  4863.4     .15       0 4985.34     .09       0
  4996.6     .15       0  5021.6     .17       0  5418.1     .11       0
Bank Sta=4985.34,4996.6
XS Rating Curve= 0 ,0
Exp/Cntr=0.3,0.1

Type RM Length L Ch R = 1 ,1431    ,407,407,407
BEGIN DESCRIPTION:
CCLC 039 3.0
END DESCRIPTION:
XS GIS Cut Line= 3
      3678387.04     10145414.52       3677970.4     10145284.32
      3677597.16     10145410.18
#Sta/Elev= 30
  4613.6  351.57  4640.4  349.14  4665.1  347.87  4696.6  344.86  4778.6  339.77
  4822.3  337.29  4840.5   335.6  4853.7  335.49  4885.3  333.76  4916.6  331.96
  4943.2  331.18  4958.5  331.65    4969  330.96  5021.4  331.07  5031.8  332.11
  5052.9  331.21    5068  331.82 5110.99330.6385  5112.5  330.54  5112.8  330.04
  5119.8  330.62  5137.2  330.89    5146  331.85  5182.7  333.45  5245.7  337.62
  5271.9  340.38  5358.8  344.93  5397.8  348.12  5434.6  348.82    5444   349.5
#Mann= 6 ,-1 , 0
  4613.6     .11       0  4778.6     .17       0  4885.3     .15       0
    5068     .17       0 5110.99     .09       0  5119.8     .17       0
Bank Sta=5110.99,5119.8
XS Rating Curve= 0 ,0
Exp/Cntr=0.3,0.1

Type RM Length L Ch R = 1 ,1024    ,448,448,448
BEGIN DESCRIPTION:
CCLC 039 2.0
END DESCRIPTION:
XS GIS Cut Line= 3
      3678417.88     10145011.08      3678118.23     10144966.84
      3677517.81     10145211.09
#Sta/Elev= 30
  4697.1  354.09  4731.9  351.35  4747.7  349.16  4796.5  344.65  4801.6  344.94
  4828.5  342.09  4866.1  339.04  4871.2  339.28  4879.1  338.07  4929.6  335.05
  4997.7  329.22  5020.5  329.56  5030.8   329.2    5031   328.7 5039.18329.5932
  5043.6  329.99  5074.1  329.39    5133  330.45  5151.5  329.73  5302.7  329.54
  5371.2  333.25  5454.2  339.04  5478.2  339.28  5496.9  340.59  5518.6  342.97
  5540.2  343.53  5561.8  345.98  5579.9  345.08    5604  345.37  5648.2  347.63
#Mann= 3 , 0 , 0
  4697.1     .12       0  5020.5     .07       0 5039.18     .12       0
Bank Sta=5020.5,5039.18
XS Rating Curve= 0 ,0
Exp/Cntr=0.3,0.1

Type RM Length L Ch R = 1 ,576     ,551,551,551
BEGIN DESCRIPTION:
CCLC 039 1.0
END DESCRIPTION:
XS GIS Cut Line= 3
      3678567.86     10144811.07      3678148.35     10144546.47
      3677417.86     10145011.07
#Sta/Elev= 30
  4634.7   352.9  4648.3  351.99  4657.6  352.83  4663.5  351.72  4678.8  351.62
  4684.7  350.19  4757.7  345.12  4836.6  337.76  4953.9  329.03  4976.6  328.49
  4997.8  326.41    5013  327.32  5076.6   325.9 5150.68325.5081  5162.1  325.24
  5162.3  324.74    5170  325.52  5380.2   326.2  5488.4  327.97  5555.3  327.61
  5605.3  328.19  5628.1  329.44  5685.7  330.61  5771.2  334.38  5816.1  335.22
  5843.1  336.78  5888.9  337.52  5937.2   339.5  5967.6  339.39  5996.4  340.75
#Mann= 3 , 0 , 0
  4634.7     .11       0 5150.68     .06       0    5170     .11       0
Bank Sta=5150.68,5170
XS Rating Curve= 0 ,0
Exp/Cntr=0.3,0.1

Type RM Length L Ch R = 1 ,25      ,0,0,0
XS GIS Cut Line= 6
      3678793.86      10144661.8      3678410.89     10144376.34
       3678311.6     10144355.07      3678166.21     10144378.11
      3677565.15     10144665.34      3677359.48     10145048.32
#Sta/Elev= 30
       0  350.13   140.9  343.83   161.8  341.38   205.6  339.71   297.3  332.87
   355.7  330.29   462.1  322.87   482.4   324.9   511.4   323.3     664   323.1
   684.2  321.94   704.5  323.08   907.3   324.3   975.4  325.58  1020.7  324.27
  1043.4  325.82  1066.1  325.48  1094.3  327.23  1111.4  327.04    1117  328.23
  1145.7  329.37  1207.7  330.82  1343.8  332.72    1372  332.03  1439.2  332.65
  1455.5  333.71  1499.3  333.11    1587  334.78  1756.7  340.44    1826  344.95
#Mann= 3 , 0 , 0
       0     .09       0     664     .06       0   704.5     .09       0
Bank Sta=664,704.5
XS Rating Curve= 0 ,0
Exp/Cntr=0.3,0.1

Chan Stop Cuts=-1
Use User Specified Reach Order=0
Composite Channel Slope=5