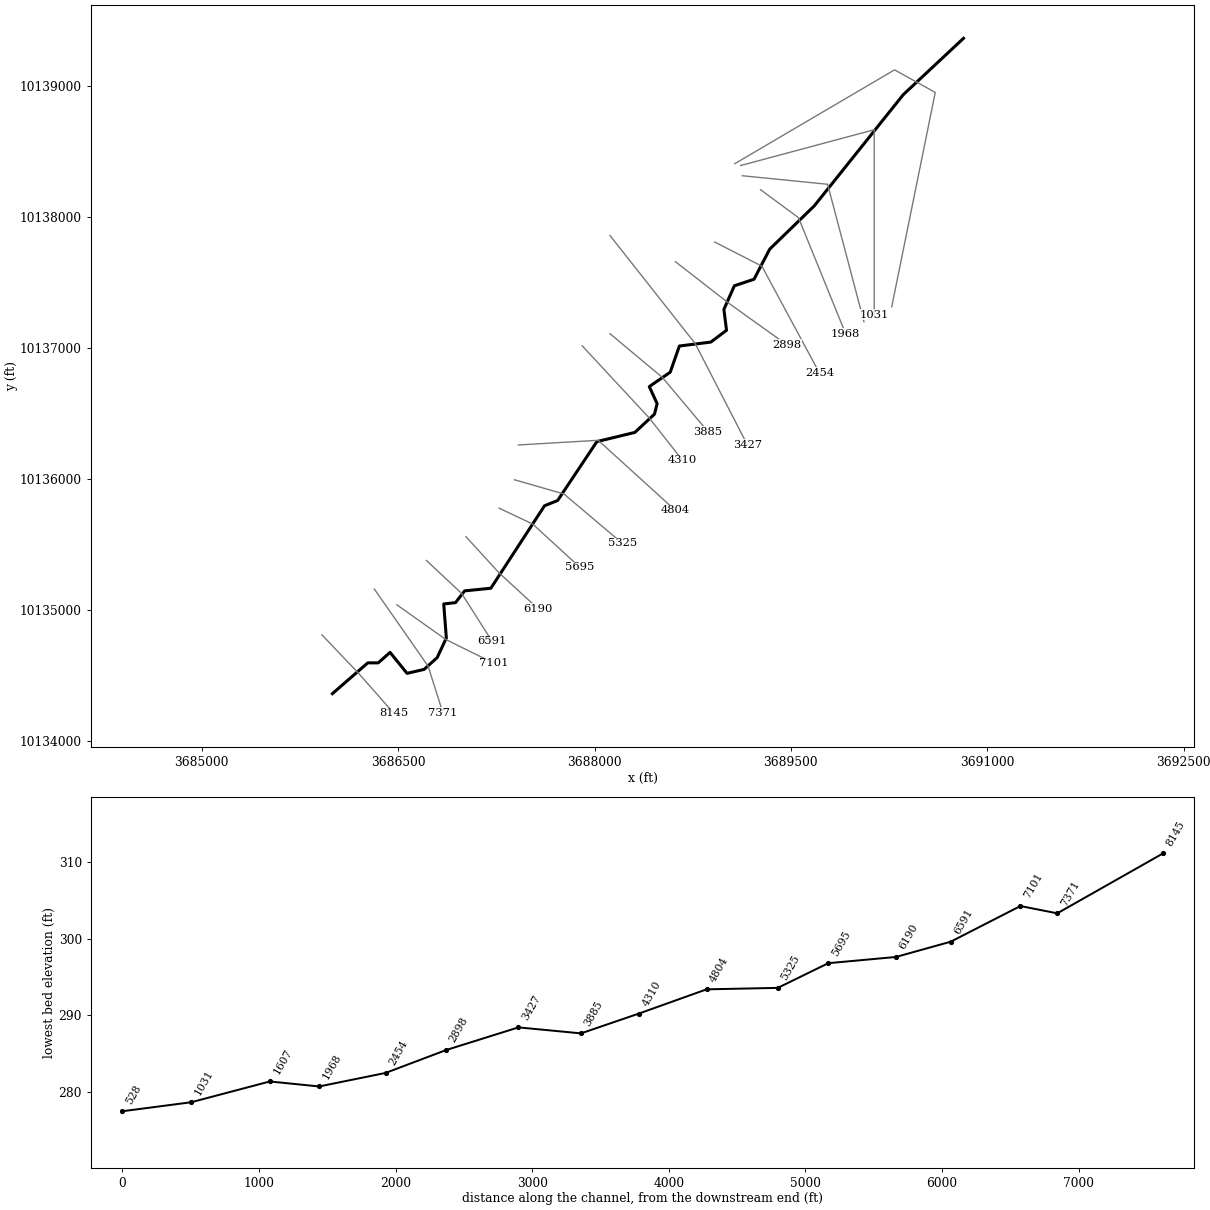
--- CCLC 040.prj (project) ---

Proj Title=CCLC 040 Base Level Engineering
Current Plan=p01
Default Exp/Contr=0.3,0.1
English Units
Geom File=g01
Flow File=f01
Flow File=f02
Plan File=p01
Y Axis Title=Elevation
X Axis Title(PF)=Main Channel Distance
X Axis Title(XS)=Station
BEGIN DESCRIPTION:
CCLC 040
END DESCRIPTION:
DSS Export Rating Curves= 0
DSS Export Rating Curve Sorted= 0
DSS Export Volume Flow Curves= 0
DXF OffsetX= 0
DXF OffsetY= 0
DXF ScaleX= 1
DXF ScaleY= 10

--- CCLC 040.p01 (plan) ---

Plan Title=Multiple Run
Short Identifier=Multiple
Geom File=g01
Flow File=f01
Subcritical Flow
K Sum by GR= 0
Std Step Tol= 0.01
Critical Tol= 0.01
Num of Std Step Trials= 20
Max Error Tol= 0.3
Flow Tol Ratio= 0.001
Split Flow NTrial= 30
Split Flow Tol= 0.02
Split Flow Ratio= 0.02
Log Output Level= 0
Friction Slope Method= 1
Unsteady Friction Slope Method= 2
Unsteady Bridges Friction Slope Method= 1
Parabolic Critical Depth
Global Vel Dist=  1 , 1 , 1
Global Log Level= 0
CheckData=True
Encroach Param= -1, 0, 0, 0
BEGIN DESCRIPTION:
Multiple Run
END DESCRIPTION:

--- CCLC 040.f01 (steady flow) ---

Flow Title=Multiple
Program Version=4.10
Number of Profiles= 7
Profile Names=10-year,25-year,50-year,1pct_min,100-year,1pct_plu,500-year
River Rch & RM=CCLC 040,Reach-1         ,8145
     772    1070    1470     664    2005    6055    3858
River Rch & RM=CCLC 040,Reach-1         ,3885
     811    1120    1532     689    2081    6285    3977
Boundary for River Rch & Prof#=CCLC 040,Reach-1         , 1
Up Type= 0
Dn Type= 3
Dn Slope=0.005
Boundary for River Rch & Prof#=CCLC 040,Reach-1         , 2
Up Type= 0
Dn Type= 3
Dn Slope=0.005
Boundary for River Rch & Prof#=CCLC 040,Reach-1         , 3
Up Type= 0
Dn Type= 3
Dn Slope=0.005
Boundary for River Rch & Prof#=CCLC 040,Reach-1         , 4
Up Type= 0
Dn Type= 3
Dn Slope=0.005
Boundary for River Rch & Prof#=CCLC 040,Reach-1         , 5
Up Type= 0
Dn Type= 3
Dn Slope=0.005
Boundary for River Rch & Prof#=CCLC 040,Reach-1         , 6
Up Type= 0
Dn Type= 3
Dn Slope=0.005
Boundary for River Rch & Prof#=CCLC 040,Reach-1         , 7
Up Type= 0
Dn Type= 3
Dn Slope=0.005
DSS Import GetInterval= 0
DSS Import GetPeak= 0
DSS Import FillOption= 0

--- CCLC 040.f02 (steady flow) ---

Flow Title=Orig_BLE_Flows
Program Version=4.10
Number of Profiles= 7
Profile Names=10-year,25-year,50-year,1pct_min,100-year,1pct_plu,500-year
River Rch & RM=CCLC 040,Reach-1         ,8145
     772    1049    1278     510    1542    4655    2243
River Rch & RM=CCLC 040,Reach-1         ,3885
     811    1098    1332     530    1601    4836    2312
Boundary for River Rch & Prof#=CCLC 040,Reach-1         , 1
Up Type= 0
Dn Type= 3
Dn Slope=0.005
Boundary for River Rch & Prof#=CCLC 040,Reach-1         , 2
Up Type= 0
Dn Type= 3
Dn Slope=0.005
Boundary for River Rch & Prof#=CCLC 040,Reach-1         , 3
Up Type= 0
Dn Type= 3
Dn Slope=0.005
Boundary for River Rch & Prof#=CCLC 040,Reach-1         , 4
Up Type= 0
Dn Type= 3
Dn Slope=0.005
Boundary for River Rch & Prof#=CCLC 040,Reach-1         , 5
Up Type= 0
Dn Type= 3
Dn Slope=0.005
Boundary for River Rch & Prof#=CCLC 040,Reach-1         , 6
Up Type= 0
Dn Type= 3
Dn Slope=0.005
Boundary for River Rch & Prof#=CCLC 040,Reach-1         , 7
Up Type= 0
Dn Type= 3
Dn Slope=0.005
DSS Import GetInterval= 0
DSS Import GetPeak= 0
DSS Import FillOption= 0

--- CCLC 040.g01 (geometry) ---

Geom Title=Existing Conditions
Program Version=4.10

River Reach=CCLC 040        ,Reach-1
Reach XY= 30
      3685998.23     10134361.84      3686268.23     10134596.84
      3686348.23     10134596.84      3686438.23     10134676.84
      3686568.23     10134516.84      3686698.23     10134546.84
      3686798.23     10134636.84      3686868.23     10134786.84
      3686848.23     10135046.84      3686938.23     10135056.84
      3687008.23     10135146.84      3687208.23     10135166.84
      3687618.23     10135796.84      3687718.23     10135836.84
      3688018.23     10136286.84      3688308.23     10136356.84
      3688458.23     10136496.84      3688478.23     10136576.84
      3688418.23     10136706.84      3688578.23     10136816.84
      3688648.23     10137016.84      3688888.23     10137046.84
      3689008.23     10137136.84      3688988.23     10137296.84
      3689068.23     10137476.84      3689218.23     10137526.84
      3689338.23     10137756.84      3689678.23     10138086.84
      3690358.23     10138936.84      3690818.23     10139366.84

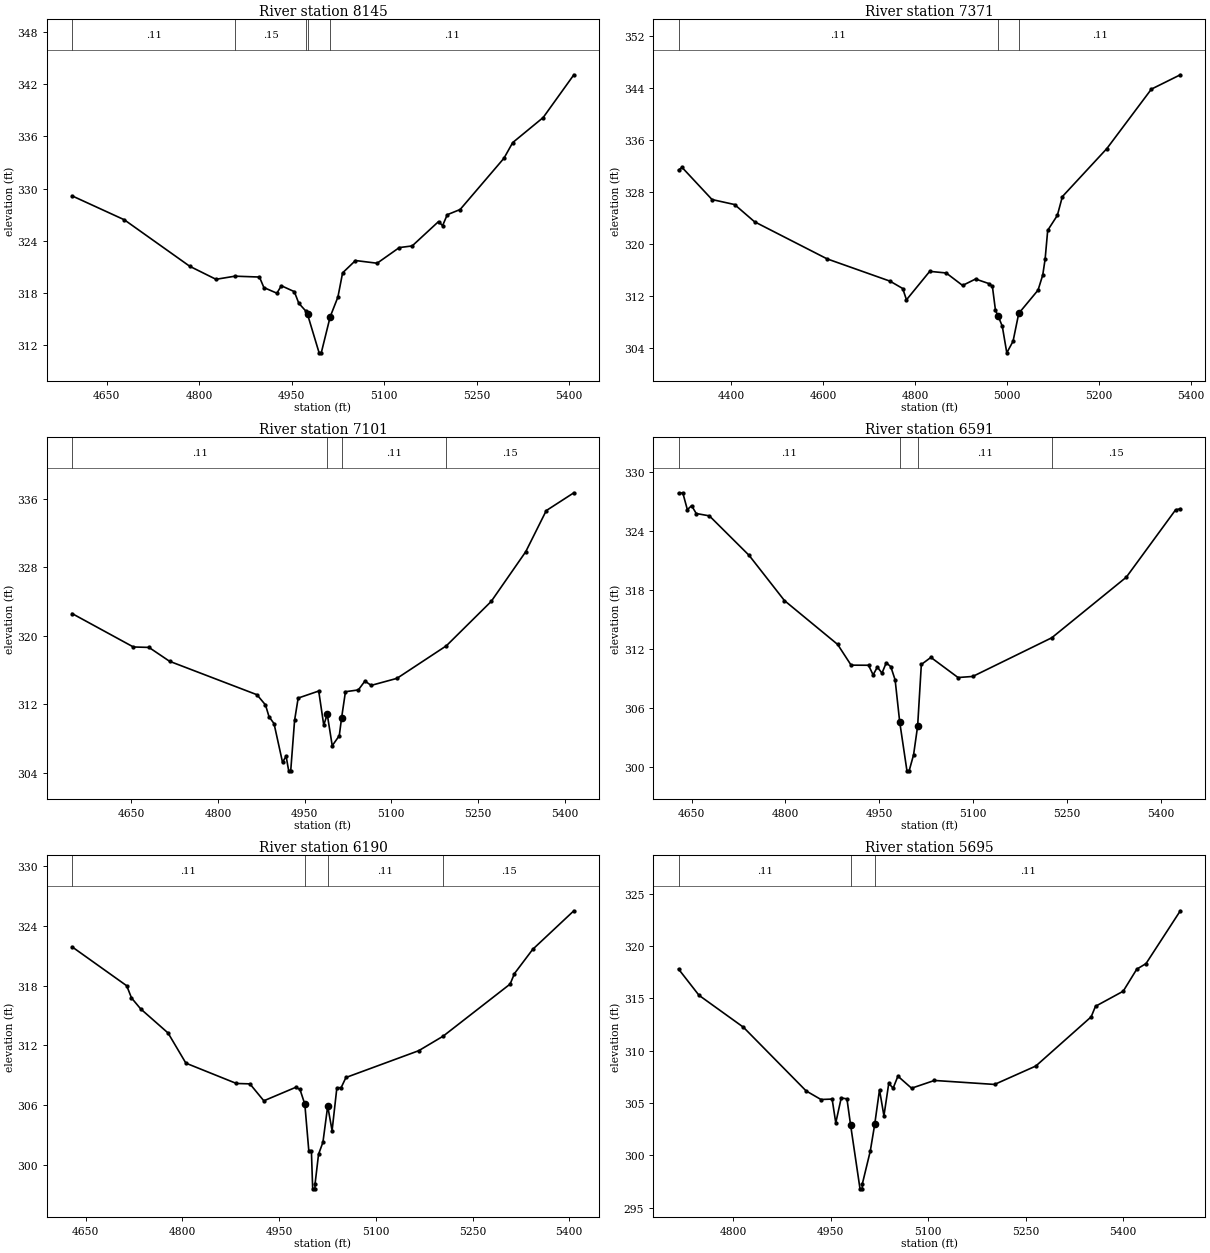
Type RM Length L Ch R = 1 ,8145    ,774,774,774
BEGIN DESCRIPTION:
CCLC 040 15.0
END DESCRIPTION:
XS GIS Cut Line= 3
      3685917.87     10134811.05      3686198.23     10134516.84
      3686467.87     10134211.05
#Sta/Elev= 30
  4593.6  329.16  4678.3  326.41  4784.7  321.05  4827.1  319.56  4857.9  319.92
  4897.6  319.82  4904.8  318.61  4925.9  317.96  4933.1  318.82  4954.2  318.14
  4961.4  316.81  4973.4  315.86  4975.6  315.53  4994.4   311.1  4997.9   311.1
 5012.38315.2555  5024.9  317.52  5032.5   320.3  5053.4  321.72  5088.5  321.41
  5124.5  323.21  5145.4   323.4  5188.1   326.2  5194.7  325.73  5202.3  326.99
  5223.2  327.59  5294.3  333.49  5308.5  335.29  5357.9  338.17  5407.7  343.09
#Mann= 5 ,-1 , 0
  4593.6     .11       0  4857.9     .15       0  4973.4     .11       0
  4975.6     .06       0 5012.38     .11       0
Bank Sta=4975.6,5012.38
XS Rating Curve= 0 ,0
Exp/Cntr=0.3,0.1

Type RM Length L Ch R = 1 ,7371    ,270,270,270
BEGIN DESCRIPTION:
CCLC 040 14.0
END DESCRIPTION:
XS GIS Cut Line= 3
      3686317.83     10135161.11      3686729.08     10134571.64
      3686841.86     10134215.94
#Sta/Elev= 30
  4285.6  331.41  4293.1  331.84  4358.5  326.88  4407.6  326.11    4451  323.46
  4608.9  317.75  4745.8  314.32  4773.4  313.19  4781.6  311.45  4832.2  315.83
    4868  315.58  4903.7  313.66  4931.9  314.65  4960.4  313.96  4968.5  313.54
  4975.3  309.81  4981.4  308.89  4990.1  307.38  4999.9  303.29  5013.5  305.07
  5025.9  309.36  5067.9  312.94  5078.1  315.26  5083.3  317.71  5088.9  322.14
  5109.9  324.44  5120.8  327.33  5217.7  334.73  5314.5  343.87  5377.5  346.08
#Mann= 3 , 0 , 0
  4285.6     .11       0  4981.4     .06       0  5025.9     .11       0
Bank Sta=4981.4,5025.9
XS Rating Curve= 0 ,0
Exp/Cntr=0.3,0.1

Type RM Length L Ch R = 1 ,7101    ,510,510,510
BEGIN DESCRIPTION:
CCLC 040 13.0
END DESCRIPTION:
XS GIS Cut Line= 3
      3686490.36      10135040.4      3686863.63     10134775.64
      3687232.52     10134593.36
#Sta/Elev= 30
  4547.1  322.59  4653.3  318.69  4680.3  318.64    4716  317.02  4867.3  313.12
  4882.1  311.93  4888.2  310.56  4896.9  309.75  4911.6  305.24  4917.8  305.95
  4922.3  304.24  4925.8  304.24  4932.5  310.13  4938.7  312.73  4974.3  313.55
    4983  309.58  4989.1  310.83  4997.7  307.17  5009.9  308.34 5013.98  310.45
  5020.6  313.47  5042.9  313.68  5054.3  314.71  5065.2  314.21  5109.8  315.03
  5195.4  318.83  5273.1  324.01  5332.9  329.81  5368.4   334.6  5416.2  336.68
#Mann= 4 ,-1 , 0
  4547.1     .11       0  4989.1     .06       0 5013.98     .11       0
  5195.4     .15       0
Bank Sta=4989.1,5013.98
XS Rating Curve= 0 ,0
Exp/Cntr=0.3,0.1

Type RM Length L Ch R = 1 ,6591    ,401,401,401
BEGIN DESCRIPTION:
CCLC 040 12.0
END DESCRIPTION:
XS GIS Cut Line= 3
      3686716.04     10135378.95      3686985.16      10135127.2
      3687217.83      10134761.1
#Sta/Elev= 30
    4629  327.83  4635.8   327.9  4643.1  326.18  4649.9  326.59  4657.3  325.79
  4678.3  325.55  4741.8  321.53  4798.4  316.92  4883.4  312.46  4904.9  310.35
  4932.8  310.34  4940.1  309.36  4946.9  310.15  4954.3  309.54  4961.1  310.59
  4968.4  310.19  4975.3  308.85  4982.6  304.58  4994.2  299.59  4997.7  299.59
  5004.8  301.22  5011.3  304.15  5017.2  310.42  5032.5  311.14  5075.9  309.09
  5099.4   309.2  5225.8  313.14    5345  319.31  5423.7  326.16  5431.3  326.27
#Mann= 4 ,-1 , 0
    4629     .11       0  4982.6     .06       0  5011.3     .11       0
  5225.8     .15       0
Bank Sta=4982.6,5011.3
XS Rating Curve= 0 ,0
Exp/Cntr=0.3,0.1

Type RM Length L Ch R = 1 ,6190    ,495,495,495
BEGIN DESCRIPTION:
CCLC 040 11.0
END DESCRIPTION:
XS GIS Cut Line= 3
      3687017.88     10135561.05      3687268.23     10135286.84
      3687567.84     10135011.08
#Sta/Elev= 30
  4628.7   321.9  4713.5  317.99  4720.9  316.77  4735.1  315.67  4777.6  313.25
  4805.3  310.22  4883.7  308.18  4904.6  308.14  4926.2  306.44  4975.6  307.79
  4982.3  307.58  4989.8   306.1    4996  301.41    5000  301.41    5002   297.6
  5005.5   297.6  5005.7   298.1  5011.1  301.07  5017.9  302.28  5025.3  305.91
  5032.1  303.44  5039.5  307.74  5046.2  307.77  5053.6  308.78  5166.5  311.47
  5204.4  312.93  5308.3  318.16  5315.1  319.22  5343.4  321.65  5407.2  325.52
#Mann= 4 ,-1 , 0
  4628.7     .11       0  4989.8     .06       0  5025.3     .11       0
  5204.4     .15       0
Bank Sta=4989.8,5025.3
XS Rating Curve= 0 ,0
Exp/Cntr=0.3,0.1

Type RM Length L Ch R = 1 ,5695    ,370,370,370
BEGIN DESCRIPTION:
CCLC 040 10.0
END DESCRIPTION:
XS GIS Cut Line= 3
       3687271.6     10135778.25      3687528.23     10135656.84
       3687887.9     10135326.88
#Sta/Elev= 30
  4716.1   317.8  4747.6  315.29  4815.9  312.24  4912.4  306.15  4935.2  305.33
  4952.4  305.37    4958   303.1  4966.4  305.48  4975.2  305.39  4980.7  302.94
  4995.3  296.79  4998.8  296.79    4999  297.29  5011.1   300.4  5017.9  302.95
  5025.3  306.26  5032.1  303.77  5039.5  306.86  5046.3  306.42  5053.6  307.56
  5074.6  306.41  5109.8  307.15  5202.3  306.77  5265.8  308.53  5350.9  313.23
  5357.6  314.24  5400.2  315.68  5421.1  317.79  5435.3  318.32  5488.1  323.37
#Mann= 3 , 0 , 0
  4716.1     .11       0  4980.7     .06       0  5017.9     .11       0
Bank Sta=4980.7,5017.9
XS Rating Curve= 0 ,0
Exp/Cntr=0.3,0.1

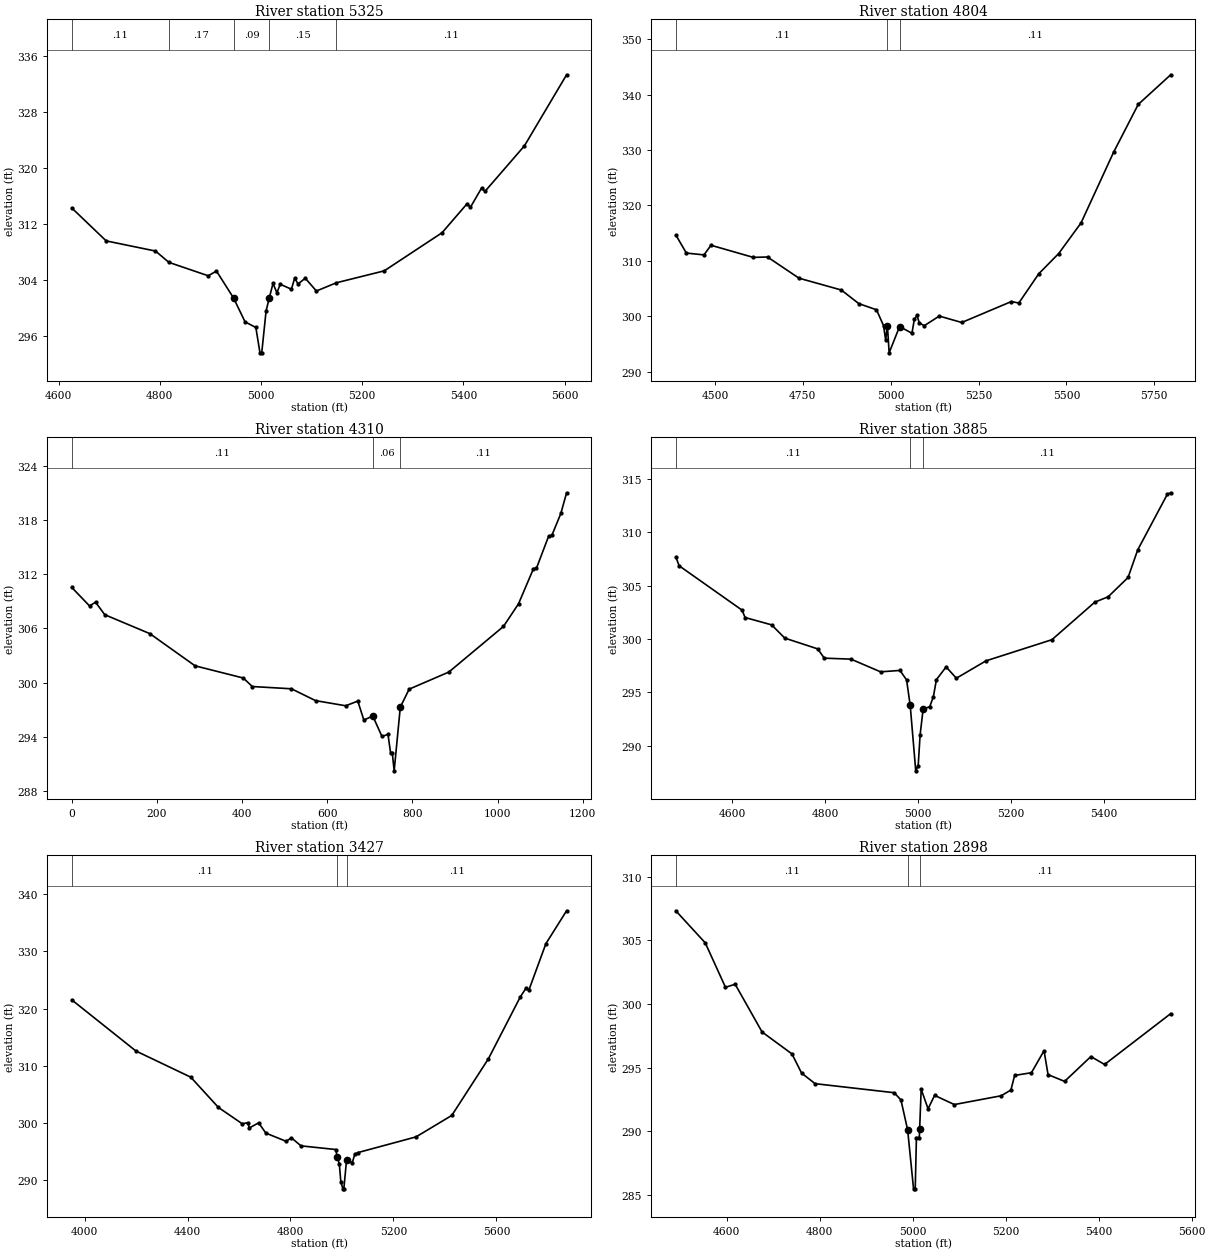
Type RM Length L Ch R = 1 ,5325    ,521,521,521
BEGIN DESCRIPTION:
CCLC 040 9.0
END DESCRIPTION:
XS GIS Cut Line= 3
      3687388.78     10135995.26      3687766.41     10135886.75
      3688213.15      10135509.4
#Sta/Elev= 30
    4626  314.27  4694.1  309.56  4791.5  308.11  4818.1  306.49  4895.6  304.58
    4912  305.25  4945.7  301.41  4968.4     298  4989.8  297.19  4997.9  293.57
  5001.4  293.57    5010  299.55  5016.2  301.39  5023.7  303.48  5031.4  302.14
  5037.9  303.37    5060  302.66  5066.5  304.24  5073.2  303.41  5087.4  304.23
  5109.4   302.4  5148.9  303.58  5243.4  305.28  5357.7  310.73  5407.2  314.88
  5413.7  314.36  5435.8  317.12  5442.3  316.62  5520.3  323.13  5603.7  333.29
#Mann= 5 ,-1 , 0
    4626     .11       0  4818.1     .17       0  4945.7     .09       0
  5016.2     .15       0  5148.9     .11       0
Bank Sta=4945.7,5016.2
XS Rating Curve= 0 ,0
Exp/Cntr=0.3,0.1

Type RM Length L Ch R = 1 ,4804    ,494,494,494
BEGIN DESCRIPTION:
CCLC 040 8.0
END DESCRIPTION:
XS GIS Cut Line= 3
      3687417.88     10136261.07      3688028.23     10136296.84
      3688617.86     10135761.06
#Sta/Elev= 30
  4388.6  314.67  4418.6   311.4  4468.7  311.07  4488.7  312.81    4609  310.62
  4649.5  310.69  4739.2  306.86  4859.4  304.73  4909.5  302.26  4959.6  301.16
  4979.6  298.31  4985.7  295.72  4990.7  298.27  4995.6  293.38  5025.3  298.13
  5060.5  296.92  5067.2  299.41  5074.7  300.17  5081.4  298.79  5095.6  298.28
  5138.2  300.02  5202.2  298.86  5343.6  302.65  5364.5  302.37  5421.3  307.66
  5478.1  311.32  5541.6  316.84  5634.2   329.6  5704.4  338.25  5796.7   343.6
#Mann= 3 , 0 , 0
  4388.6     .11       0  4990.7     .06       0  5025.3     .11       0
Bank Sta=4990.7,5025.3
XS Rating Curve= 0 ,0
Exp/Cntr=0.3,0.1

Type RM Length L Ch R = 1 ,4310    ,425,425,425
BEGIN DESCRIPTION:
CCLC 040 7.0
END DESCRIPTION:
XS GIS Cut Line= 3
      3687905.93     10137018.37      3688418.23     10136466.84
      3688671.73     10136144.48
#Sta/Elev= 30
       0  310.53    41.8  308.48      56  308.89    77.5  307.51   183.5  305.41
   289.6  301.85   402.9   300.5   423.9  299.56   515.8  299.31   572.4     298
   643.3  297.43   671.6  297.95   685.8  295.85   706.8   296.3   728.3  294.04
   742.5  294.26   748.8  292.15   752.7  292.15     757  290.23   771.4  297.28
   792.2  299.27   885.3  301.16  1013.6  306.21  1048.9  308.71  1084.1  312.61
  1090.9  312.63  1119.4  316.17  1127.5  316.32  1148.3  318.71  1161.8     321
#Mann= 3 ,-1 , 0
       0     .11       0   706.8     .06       0   771.4     .11       0
Bank Sta=706.8,771.4
XS Rating Curve= 0 ,0
Exp/Cntr=0.3,0.1

Type RM Length L Ch R = 1 ,3885    ,458,458,458
BEGIN DESCRIPTION:
CCLC 040 6.0
END DESCRIPTION:
XS GIS Cut Line= 3
      3688117.89     10137111.04      3688518.23     10136776.84
      3688867.83      10136361.1
#Sta/Elev= 30
  4478.5   307.7  4485.6  306.86    4621   302.7  4627.5  302.01  4684.7  301.32
  4712.9  300.08  4783.7  299.07    4798   298.2  4855.2  298.11    4919  296.92
  4960.7  297.05    4975  296.16  4982.8  293.77  4994.7  287.64    5000  288.14
  5004.1  291.02  5010.6  293.41  5024.9  293.66  5032.7   294.6  5039.2  296.19
  5060.1  297.38  5082.1  296.32  5145.9  297.95  5287.7  299.93    5380  303.45
  5408.6  303.95  5451.5  305.76  5472.3  308.35  5536.1  313.57  5543.2   313.7
#Mann= 3 , 0 , 0
  4478.5     .11       0  4982.8     .06       0  5010.6     .11       0
Bank Sta=4982.8,5010.6
XS Rating Curve= 0 ,0
Exp/Cntr=0.3,0.1

Type RM Length L Ch R = 1 ,3427    ,529,529,529
BEGIN DESCRIPTION:
CCLC 040 5.0
END DESCRIPTION:
XS GIS Cut Line= 3
      3688117.87     10137861.05      3688768.23     10137036.84
      3689167.87     10136261.03
#Sta/Elev= 30
  3950.1  321.53  4199.4  312.57  4412.6  307.98    4520  302.68  4612.5  299.82
  4633.9  300.01  4640.2  299.09  4676.2  299.98  4704.4  298.18  4782.9  296.75
  4803.8  297.35  4840.7  295.95  4975.3  295.31  4981.9  294.08  4989.8  292.69
  4995.7  289.64  5003.7  288.42  5007.3  288.42  5017.7  293.42  5040.2     293
  5049.8   294.5  5062.7  294.78  5287.7  297.52  5426.7  301.28  5568.9   311.2
  5692.7  322.03  5715.2  323.57  5725.8  323.19  5792.3  331.37  5872.7  337.13
#Mann= 3 , 0 , 0
  3950.1     .11       0  4981.9     .06       0  5017.7     .11       0
Bank Sta=4981.9,5017.7
XS Rating Curve= 0 ,0
Exp/Cntr=0.3,0.1

Type RM Length L Ch R = 1 ,2898    ,444,444,444
BEGIN DESCRIPTION:
CCLC 040 4.0
END DESCRIPTION:
XS GIS Cut Line= 3
      3688617.86     10137661.06      3689029.43     10137340.74
      3689470.64     10137024.97
#Sta/Elev= 30
  4490.8  307.31  4554.1  304.79  4597.6   301.3  4618.4  301.54  4676.3  297.79
  4740.5  296.07  4761.3  294.56  4790.3  293.73  4960.4  293.02  4974.9  292.45
  4989.3   290.1    5002  285.47  5005.6  285.47  5008.2   289.5  5014.4   289.5
 5015.11290.1727  5018.4  293.29  5033.2  291.76  5047.3  292.81  5089.7  292.09
  5190.4  292.78  5211.3  293.23  5219.4  294.38  5255.5  294.59  5282.6  296.32
  5291.2  294.44  5326.8  293.91  5383.3  295.86  5412.8  295.24  5554.9  299.23
#Mann= 3 ,-1 , 0
  4490.8     .11       0  4989.3     .06       0 5015.11     .11       0
Bank Sta=4989.3,5015.11
XS Rating Curve= 0 ,0
Exp/Cntr=0.3,0.1

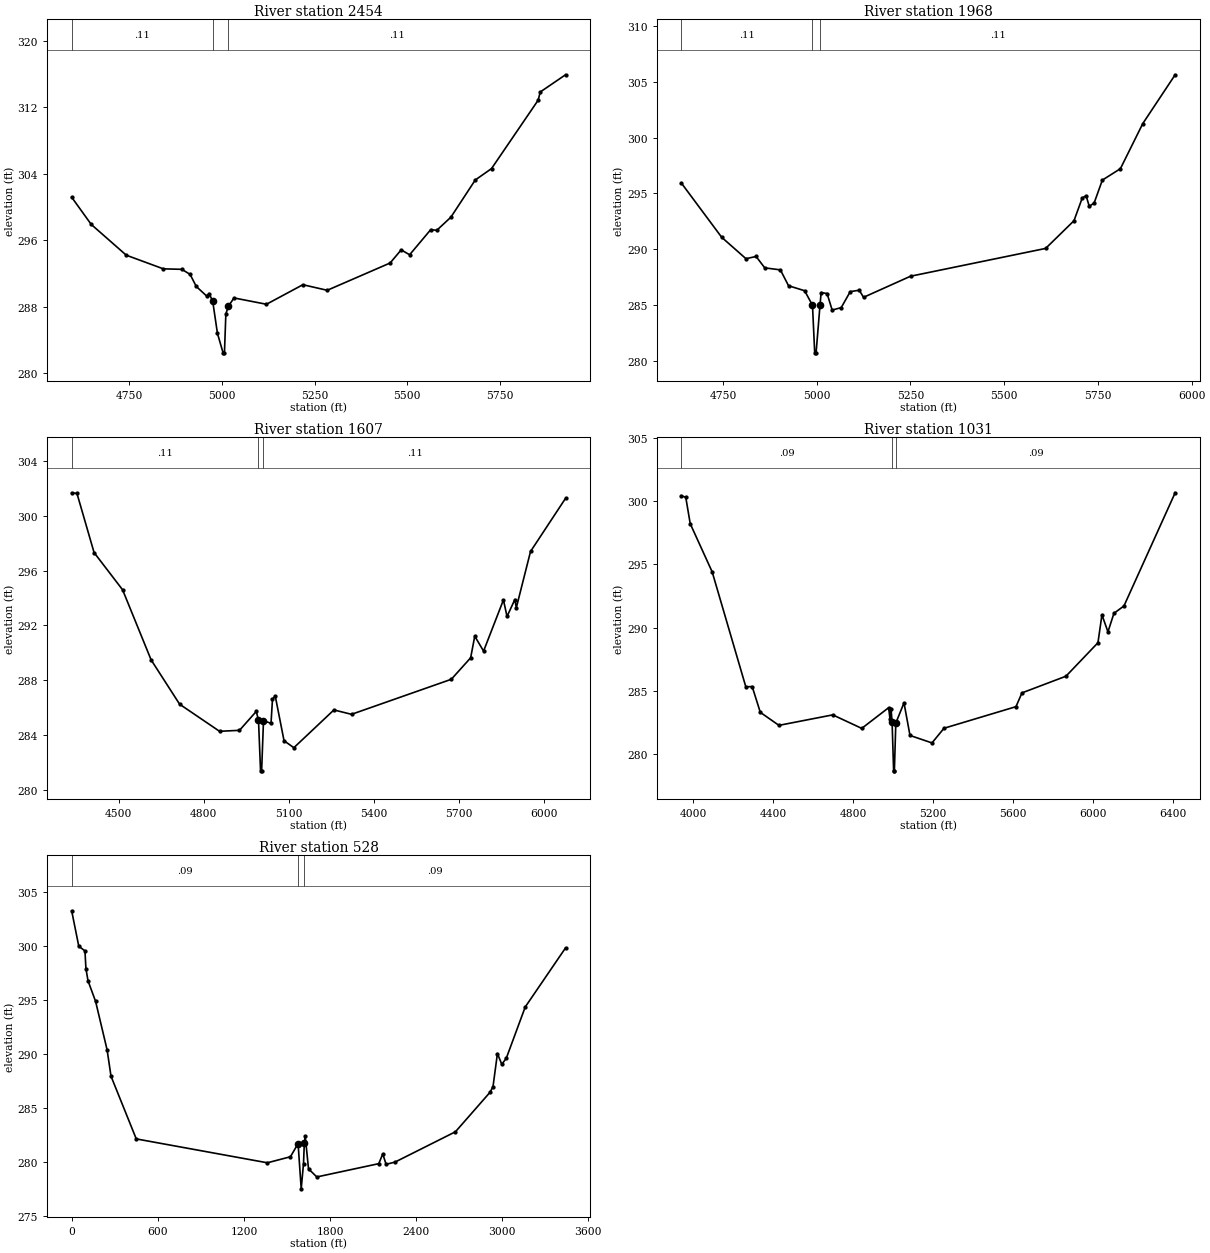
Type RM Length L Ch R = 1 ,2454    ,486,486,486
BEGIN DESCRIPTION:
CCLC 040 3.0
END DESCRIPTION:
XS GIS Cut Line= 3
      3688917.88     10137811.05      3689278.23     10137626.84
      3689717.86     10136811.06
#Sta/Elev= 30
  4595.3  301.19    4648  297.92  4742.5  294.22  4842.3  292.58  4892.4  292.52
  4914.6  291.91  4931.2  290.46    4959  289.32  4965.9  289.61  4975.6  288.67
  4988.3  284.82  5003.5  282.48  5007.2  282.48    5011  287.16  5017.9  288.08
  5032.9  289.08  5120.5  288.32  5218.6  290.67  5284.3     290  5453.8  293.28
  5483.7  294.86  5506.4  294.27  5563.3  297.29  5579.6  297.21  5617.7  298.79
  5683.4  303.26  5727.2  304.63  5852.9  312.85  5858.6  313.84  5926.7  315.91
#Mann= 3 , 0 , 0
  4595.3     .11       0  4975.6     .06       0  5017.9     .11       0
Bank Sta=4975.6,5017.9
XS Rating Curve= 0 ,0
Exp/Cntr=0.3,0.1

Type RM Length L Ch R = 1 ,1968    ,361,361,361
BEGIN DESCRIPTION:
CCLC 040 2.0
END DESCRIPTION:
XS GIS Cut Line= 3
      3689267.81      10138211.1      3689558.23     10137996.84
      3689917.85     10137111.06
#Sta/Elev= 30
  4639.1  295.93  4746.7  291.07  4811.5  289.15  4838.5  289.35  4861.6  288.33
  4903.3  288.15    4925  286.73    4968  286.28  4988.9  284.98  4994.8  280.72
  4998.5  280.72 5008.96 284.993    5012  286.12  5027.8  286.03  5041.4  284.55
  5065.5  284.77  5089.6   286.2  5113.7  286.33    5125  285.69  5250.3  287.58
  5610.6  290.07  5686.2  292.55  5708.3  294.59  5718.6  294.79    5727  293.83
  5740.1  294.15  5761.9  296.19    5810  297.21  5869.7  301.25    5956  305.62
#Mann= 3 , 0 , 0
  4639.1     .11       0  4988.9     .06       0 5008.96     .11       0
Bank Sta=4988.9,5008.96
XS Rating Curve= 0 ,0
Exp/Cntr=0.3,0.1

Type RM Length L Ch R = 1 ,1607    ,576,576,576
BEGIN DESCRIPTION:
Mapping XS 68bdc5ca
END DESCRIPTION:
XS GIS Cut Line= 3
      3689129.21     10138317.31      3689780.29      10138252.2
      3690058.08     10137201.84
#Sta/Elev= 30
  4334.8  301.69  4353.5  301.64  4413.8  297.32  4514.3   294.6  4614.8  289.48
  4715.3  286.24    4856  284.26  4926.4  284.33  4985.4  285.71 4993.36285.0867
  5000.6  281.37  5004.4  281.37    5011  285.04  5037.5  284.84  5042.7  286.61
  5052.4  286.84  5083.4  283.57    5118  283.06  5259.2  285.82  5321.3   285.5
    5673  288.06  5741.2  289.63  5755.7  291.21  5786.8  290.12  5856.8  293.86
  5869.5  292.65    5897  293.89  5902.2  293.29  5952.3   297.4  6075.6  301.28
#Mann= 3 ,-1 , 0
  4334.8     .11       0 4993.36     .06       0    5011     .11       0
Bank Sta=4993.36,5011
XS Rating Curve= 0 ,0
Exp/Cntr=0.3,0.1

Type RM Length L Ch R = 1 ,1031    ,503,503,503
BEGIN DESCRIPTION:
CCLC 040 1.0
END DESCRIPTION:
XS GIS Cut Line= 3
      3689116.27     10138395.44       3690136.2     10138668.87
       3690136.2     10137255.01
#Sta/Elev= 30
    3940  300.44  3962.3  300.31  3984.6  298.22  4094.3  294.41  4262.6  285.31
  4294.4  285.33  4335.1  283.29  4428.2  282.26  4697.4  283.09  4842.4  282.02
    4977  283.66  4983.6  282.77  4988.8  283.59  4994.2  282.51  5001.8  278.66
  5005.6  278.66 5012.74282.4397  5053.7  284.04  5083.7  281.46  5193.7  280.87
  5253.7  282.03  5613.7  283.74  5643.7  284.83  5863.7  286.15  6023.7   288.8
  6043.7  291.01  6073.7  289.66  6103.7  291.13  6153.7  291.71  6409.8  300.67
#Mann= 3 , 0 , 0
    3940     .09       0  4994.2     .06       0 5012.74     .09       0
Bank Sta=4994.2,5012.74
XS Rating Curve= 0 ,0
Exp/Cntr=0.3,0.1

Type RM Length L Ch R = 1 ,528     ,0,0,0
XS GIS Cut Line= 4
      3689072.01     10138409.89      3690291.63     10139126.04
      3690602.46      10138953.6      3690269.93     10137316.14
#Sta/Elev= 30
       0  303.22    49.5  299.94    92.5  299.51    99.5  297.85   113.9  296.74
   166.8  294.83   246.9  290.35   274.1  287.91     450  282.11  1363.6   279.9
  1524.4  280.46  1577.5  281.68  1599.2  277.49  1615.3  279.82    1621  281.76
  1627.3  282.35  1650.2  279.34    1708  278.59  2139.7  279.82  2167.5  280.72
  2190.7  279.76    2252  279.96  2673.8  282.77  2915.2  286.43  2935.6  286.95
  2966.3  290.01  2996.9  289.01  3028.3  289.58  3160.1  294.32  3440.7  299.78
#Mann= 3 , 0 , 0
       0     .09       0  1577.5     .06       0    1621     .09       0
Bank Sta=1577.5,1621
XS Rating Curve= 0 ,0
Exp/Cntr=0.3,0.1

Chan Stop Cuts=-1
Use User Specified Reach Order=0
Composite Channel Slope=5