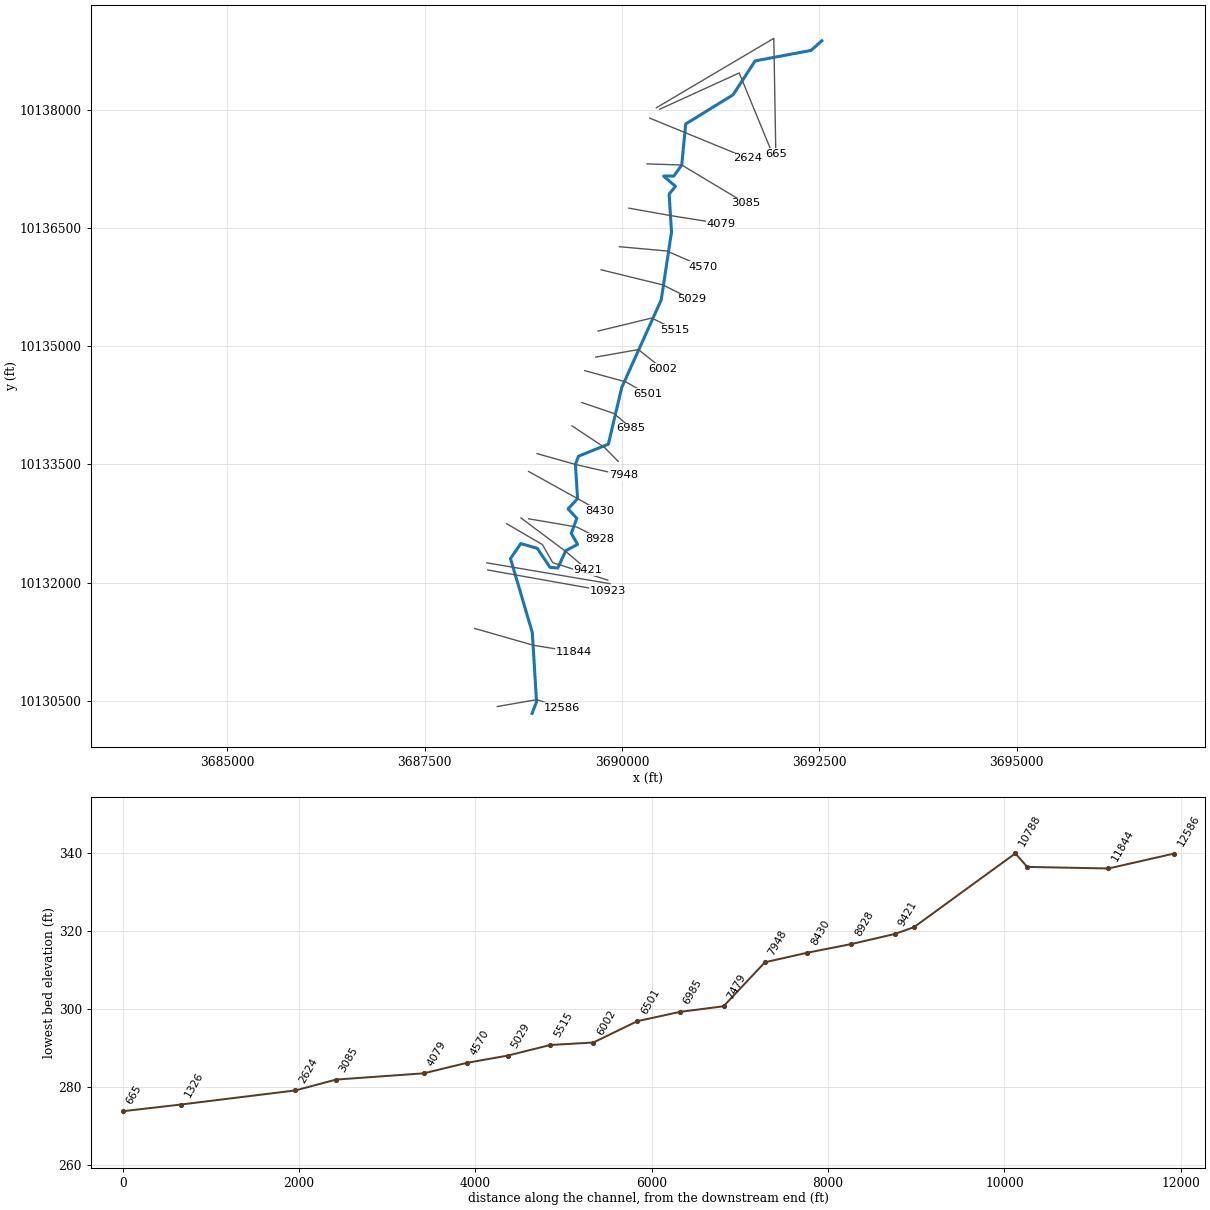
--- CCLC 041.prj (project) ---

Proj Title=CCLC 041 Base Level Engineering
Current Plan=p01
Default Exp/Contr=0.3,0.1
English Units
Geom File=g01
Flow File=f01
Flow File=f02
Plan File=p01
Y Axis Title=Elevation
X Axis Title(PF)=Main Channel Distance
X Axis Title(XS)=Station
BEGIN DESCRIPTION:
CCLC 041
END DESCRIPTION:
DSS Export Rating Curves= 0
DSS Export Rating Curve Sorted= 0
DSS Export Volume Flow Curves= 0
DXF OffsetX= 0
DXF OffsetY= 0
DXF ScaleX= 1
DXF ScaleY= 10

--- CCLC 041.p01 (plan) ---

Plan Title=Multiple Run
Short Identifier=Multiple
Geom File=g01
Flow File=f01
Subcritical Flow
K Sum by GR= 0
Std Step Tol= 0.01
Critical Tol= 0.01
Num of Std Step Trials= 20
Max Error Tol= 0.3
Flow Tol Ratio= 0.001
Split Flow NTrial= 30
Split Flow Tol= 0.02
Split Flow Ratio= 0.02
Log Output Level= 0
Friction Slope Method= 1
Unsteady Friction Slope Method= 2
Unsteady Bridges Friction Slope Method= 1
Parabolic Critical Depth
Global Vel Dist=  1 , 1 , 1
Global Log Level= 0
CheckData=True
Encroach Param= -1, 0, 0, 0
BEGIN DESCRIPTION:
Multiple Run
END DESCRIPTION:

--- CCLC 041.f01 (steady flow) ---

Flow Title=Multiple
Program Version=4.10
Number of Profiles= 7
Profile Names=10-year,25-year,50-year,1pct_min,100-year,1pct_plu,500-year
River Rch & RM=CCLC 041,Reach-1         ,12586
     535     724     980     437    1320    3986    2470
River Rch & RM=CCLC 041,Reach-1         ,10788
     677     921    1250     558    1684    5086    3160
River Rch & RM=CCLC 041,Reach-1         ,4079
     710     970    1317     588    1776    5363    3340
Boundary for River Rch & Prof#=CCLC 041,Reach-1         , 1
Up Type= 0
Dn Type= 3
Dn Slope=0.005
Boundary for River Rch & Prof#=CCLC 041,Reach-1         , 2
Up Type= 0
Dn Type= 3
Dn Slope=0.005
Boundary for River Rch & Prof#=CCLC 041,Reach-1         , 3
Up Type= 0
Dn Type= 3
Dn Slope=0.005
Boundary for River Rch & Prof#=CCLC 041,Reach-1         , 4
Up Type= 0
Dn Type= 3
Dn Slope=0.005
Boundary for River Rch & Prof#=CCLC 041,Reach-1         , 5
Up Type= 0
Dn Type= 3
Dn Slope=0.005
Boundary for River Rch & Prof#=CCLC 041,Reach-1         , 6
Up Type= 0
Dn Type= 3
Dn Slope=0.005
Boundary for River Rch & Prof#=CCLC 041,Reach-1         , 7
Up Type= 0
Dn Type= 3
Dn Slope=0.005
DSS Import GetInterval= 0
DSS Import GetPeak= 0
DSS Import FillOption= 0

--- CCLC 041.f02 (steady flow) ---

Flow Title=Orig_BLE_Flows
Program Version=4.10
Number of Profiles= 7
Profile Names=10-year,25-year,50-year,1pct_min,100-year,1pct_plu,500-year
River Rch & RM=CCLC 041,Reach-1         ,12586
     535     710     852     336    1015    3065    1436
River Rch & RM=CCLC 041,Reach-1         ,10788
     677     903    1087     429    1295    3910    1837
River Rch & RM=CCLC 041,Reach-1         ,4079
     710     951    1145     452    1366    4125    1942
Boundary for River Rch & Prof#=CCLC 041,Reach-1         , 1
Up Type= 0
Dn Type= 3
Dn Slope=0.005
Boundary for River Rch & Prof#=CCLC 041,Reach-1         , 2
Up Type= 0
Dn Type= 3
Dn Slope=0.005
Boundary for River Rch & Prof#=CCLC 041,Reach-1         , 3
Up Type= 0
Dn Type= 3
Dn Slope=0.005
Boundary for River Rch & Prof#=CCLC 041,Reach-1         , 4
Up Type= 0
Dn Type= 3
Dn Slope=0.005
Boundary for River Rch & Prof#=CCLC 041,Reach-1         , 5
Up Type= 0
Dn Type= 3
Dn Slope=0.005
Boundary for River Rch & Prof#=CCLC 041,Reach-1         , 6
Up Type= 0
Dn Type= 3
Dn Slope=0.005
Boundary for River Rch & Prof#=CCLC 041,Reach-1         , 7
Up Type= 0
Dn Type= 3
Dn Slope=0.005
DSS Import GetInterval= 0
DSS Import GetPeak= 0
DSS Import FillOption= 0

--- CCLC 041.g01 (geometry) ---

Geom Title=Existing Conditions
Program Version=4.10

River Reach=CCLC 041        ,Reach-1
Reach XY= 30
      3688861.94     10130344.04      3688918.19     10130491.74
      3688864.81     10131368.58      3688588.23     10132306.84
      3688718.23     10132496.84      3688928.23     10132436.84
      3689088.23     10132196.84      3689188.23     10132186.84
      3689288.23     10132406.84      3689438.23     10132486.84
      3689358.23     10132626.84      3689428.23     10132816.84
      3689318.23     10132936.84      3689438.23     10133066.84
      3689411.09     10133499.91      3689449.58     10133604.88
      3689828.23     10133756.84      3689998.23     10134476.84
      3690498.23     10135586.84      3690628.23     10136446.84
      3690598.23     10136926.84      3690678.23     10137026.84
      3690528.23     10137156.84      3690658.23     10137156.84
      3690758.23     10137296.84      3690808.23     10137816.84
      3691408.23     10138186.84      3691688.23     10138616.84
      3692396.29     10138749.82      3692533.15     10138871.93

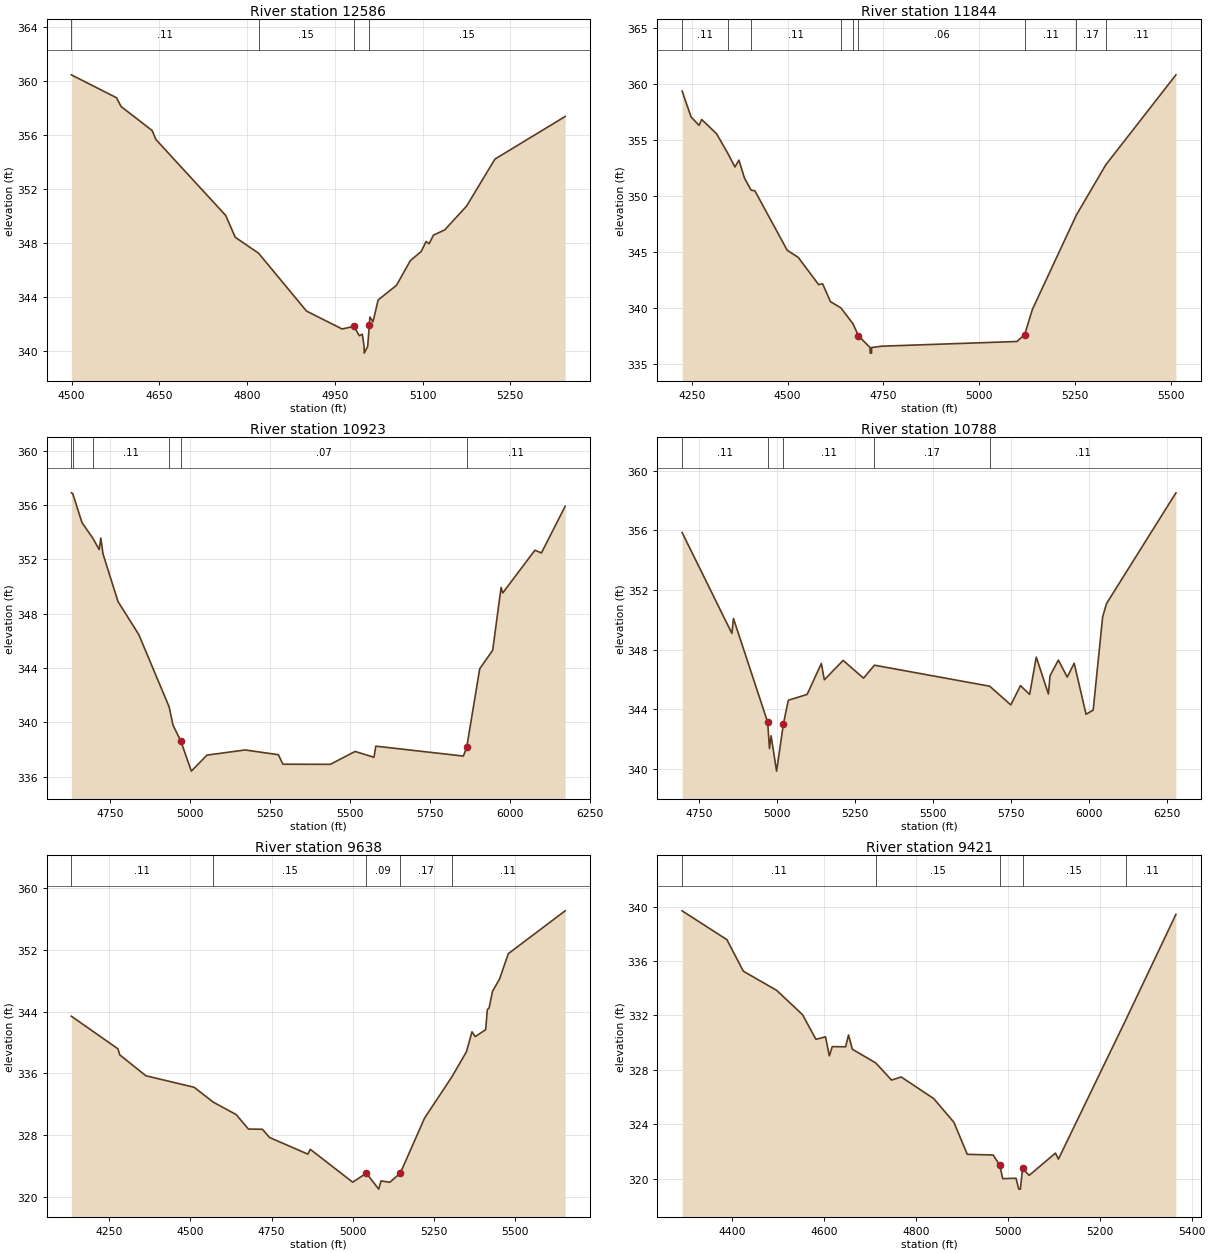
Type RM Length L Ch R = 1 ,12586   ,742,742,742
BEGIN DESCRIPTION:
CCLC 041 18.0
END DESCRIPTION:
XS GIS Cut Line= 3
      3688421.84     10130431.03      3688920.92     10130517.83
      3689242.08     10130413.67
#Sta/Elev= 30
  4499.6  360.45  4576.8  358.75  4584.6   358.1  4637.7  356.32  4644.2  355.65
  4763.5  350.02  4779.8   348.4  4819.7  347.22  4901.6  342.93  4962.5   341.6
  4982.8   341.8  4991.9   341.1    4997  341.21  5000.1  340.31  5000.3  339.81
  5006.2  340.31 5008.97341.8992    5010  342.49  5015.3  342.13    5024  343.75
  5055.5  344.84  5079.2  346.68  5097.6  347.34    5106  348.09  5111.2  347.92
  5118.6  348.56  5137.9  348.95  5175.2  350.71  5223.7   354.2  5343.8  357.36
#Mann= 4 ,-1 , 0
  4499.6     .11       0  4819.7     .15       0  4982.8     .09       0
 5008.97     .15       0
Bank Sta=4982.8,5008.97
XS Rating Curve= 0 ,0
Exp/Cntr=0.3,0.1

Type RM Length L Ch R = 1 ,11844   ,921,921,921
BEGIN DESCRIPTION:
CCLC 041 17.0
END DESCRIPTION:
XS GIS Cut Line= 3
      3688135.31     10131420.61      3688880.43     10131207.12
      3689387.75     10131125.77
#Sta/Elev= 30
  4224.9  359.41  4248.3  357.09  4269.2  356.35    4276  356.87    4315  355.59
  4345.4  353.77  4362.8  352.63  4373.2  353.24  4387.7  351.63    4405  350.56
  4414.8   350.5  4499.4  345.18  4527.9  344.56  4581.2  342.12  4591.6  342.19
  4612.4  340.59  4639.4  340.04    4671  338.62  4685.2  337.54  4715.5   336.5
  4715.8     336  4719.3     336  4719.5   336.5  4746.1  336.62  5098.7  337.04
  5118.9  337.65  5139.2  339.91    5254  348.34  5330.7  352.82  5513.8  360.86
#Mann= 9 ,-1 , 0
  4224.9     .11       0  4345.4     .17       0    4405     .11       0
  4639.4     .15       0    4671     .11       0  4685.2     .06       0
  5118.9     .11       0    5254     .17       0  5330.7     .11       0
Bank Sta=4685.2,5118.9
XS Rating Curve= 0 ,0
Exp/Cntr=0.3,0.1

Type RM Length L Ch R = 1 ,10923   ,135,135,135
BEGIN DESCRIPTION:
Mapping XS ff475485
END DESCRIPTION:
XS GIS Cut Line= 2
      3688300.28     10132161.92      3689821.05      10131891.1
#Sta/Elev= 30
    4629  356.91  4633.2  356.86  4662.2  354.72  4695.5  353.59  4716.1  352.73
  4721.2  353.58  4728.1   352.4  4775.1  348.89  4839.8  346.47  4934.8  341.14
    4947  339.79  4971.9  338.59  5004.3   336.4  5053.1  337.58  5172.8  337.96
  5276.6  337.61  5290.8  336.91  5439.1   336.9  5516.6  337.85  5575.6  337.42
  5581.3  338.24  5855.3  337.51  5865.7  338.15  5906.4  343.94    5947  345.31
  5973.3  349.94  5978.4  349.53    6079  352.68  6099.4  352.48  6173.7  355.92
#Mann= 6 ,-1 , 0
    4629     .11       0  4633.2     .17       0  4695.5     .11       0
  4934.8     .17       0  4971.9     .07       0  5865.7     .11       0
Bank Sta=4971.9,5865.7
XS Rating Curve= 0 ,0
Exp/Cntr=0.3,0.1

Type RM Length L Ch R = 1 ,10788   ,1150,1150,1150
BEGIN DESCRIPTION:
CCLC 041 16.0
END DESCRIPTION:
XS GIS Cut Line= 2
      3688287.22     10132253.07      3689849.75     10131988.31
#Sta/Elev= 30
  4694.7  355.85  4854.4  349.09  4859.5  350.09  4969.2  343.14  4975.1  341.37
  4980.2  342.23  4997.9  339.86  5019.9  343.04  5035.5  344.61  5095.9     345
  5141.6  347.08  5151.1  345.98  5211.5  347.28  5276.9  346.09  5311.9  346.96
  5681.8  345.55  5749.6   344.3  5780.6  345.59    5810     345  5831.3   347.5
  5870.3  345.03  5875.4  346.25  5902.3   347.3  5930.7  346.16    5953  347.09
  5991.1  343.67  6013.9  343.95  6044.3  350.19  6056.5  351.08  6279.5  358.51
#Mann= 5 ,-1 , 0
  4694.7     .11       0  4969.2     .06       0  5019.9     .11       0
  5311.9     .17       0  5681.8     .11       0
Bank Sta=4969.2,5019.9
XS Rating Curve= 0 ,0
Exp/Cntr=0.3,0.1

Type RM Length L Ch R = 1 ,9638    ,217,217,217
BEGIN DESCRIPTION:
CCLC 041 15.0
END DESCRIPTION:
XS GIS Cut Line= 4
      3688539.81     10132748.75      3688993.17     10132483.97
      3689123.18     10132255.67      3689821.12     10132033.44
#Sta/Elev= 30
  4133.5  343.41  4276.8  339.18  4282.6  338.39  4362.8  335.68  4511.6  334.18
  4570.1  332.26  4640.8  330.64  4678.6  328.76  4721.8  328.73  4743.4  327.67
  4861.6   325.5    4869  326.13  4999.6  321.86  5041.6  323.03  5079.8  320.96
  5086.8  322.03  5113.7  321.85    5146  323.02  5220.9  330.19  5304.3  335.49
  5349.8  338.79  5366.9  341.39  5376.8  340.76  5408.9  341.66  5414.2  344.28
  5419.5  344.47  5429.9  346.62  5451.7  348.24  5478.7  351.53  5653.7  357.09
#Mann= 5 ,-1 , 0
  4133.5     .11       0  4570.1     .15       0  5041.6     .09       0
    5146     .17       0  5304.3     .11       0
Bank Sta=5041.6,5146
XS Rating Curve= 0 ,0
Exp/Cntr=0.3,0.1

Type RM Length L Ch R = 1 ,9421    ,493,493,493
BEGIN DESCRIPTION:
CCLC 041 14.0
END DESCRIPTION:
XS GIS Cut Line= 3
      3688721.23     10132821.67      3689288.23     10132396.84
      3689567.89     10132161.04
#Sta/Elev= 30
  4291.5  339.69  4388.9  337.57  4424.7  335.25  4497.2  333.84  4553.5  332.05
  4582.6  330.24  4603.5  330.42  4611.8  329.02  4618.1   329.7  4647.2  329.69
  4653.5  330.56  4661.8  329.51  4712.8   328.5  4747.2  327.24  4768.1  327.47
  4838.9  325.88  4882.7  324.14  4911.9  321.78  4968.1  321.73  4982.7  320.97
  4988.9  319.99  5017.9  320.02  5023.9  319.22  5027.4  319.22  5032.2  320.74
  5046.5  320.23  5103.7  321.87  5110.2  321.43  5256.9  331.68  5365.8  339.43
#Mann= 5 ,-1 , 0
  4291.5     .11       0  4712.8     .15       0  4982.7     .09       0
  5032.2     .15       0  5256.9     .11       0
Bank Sta=4982.7,5032.2
XS Rating Curve= 0 ,0
Exp/Cntr=0.3,0.1

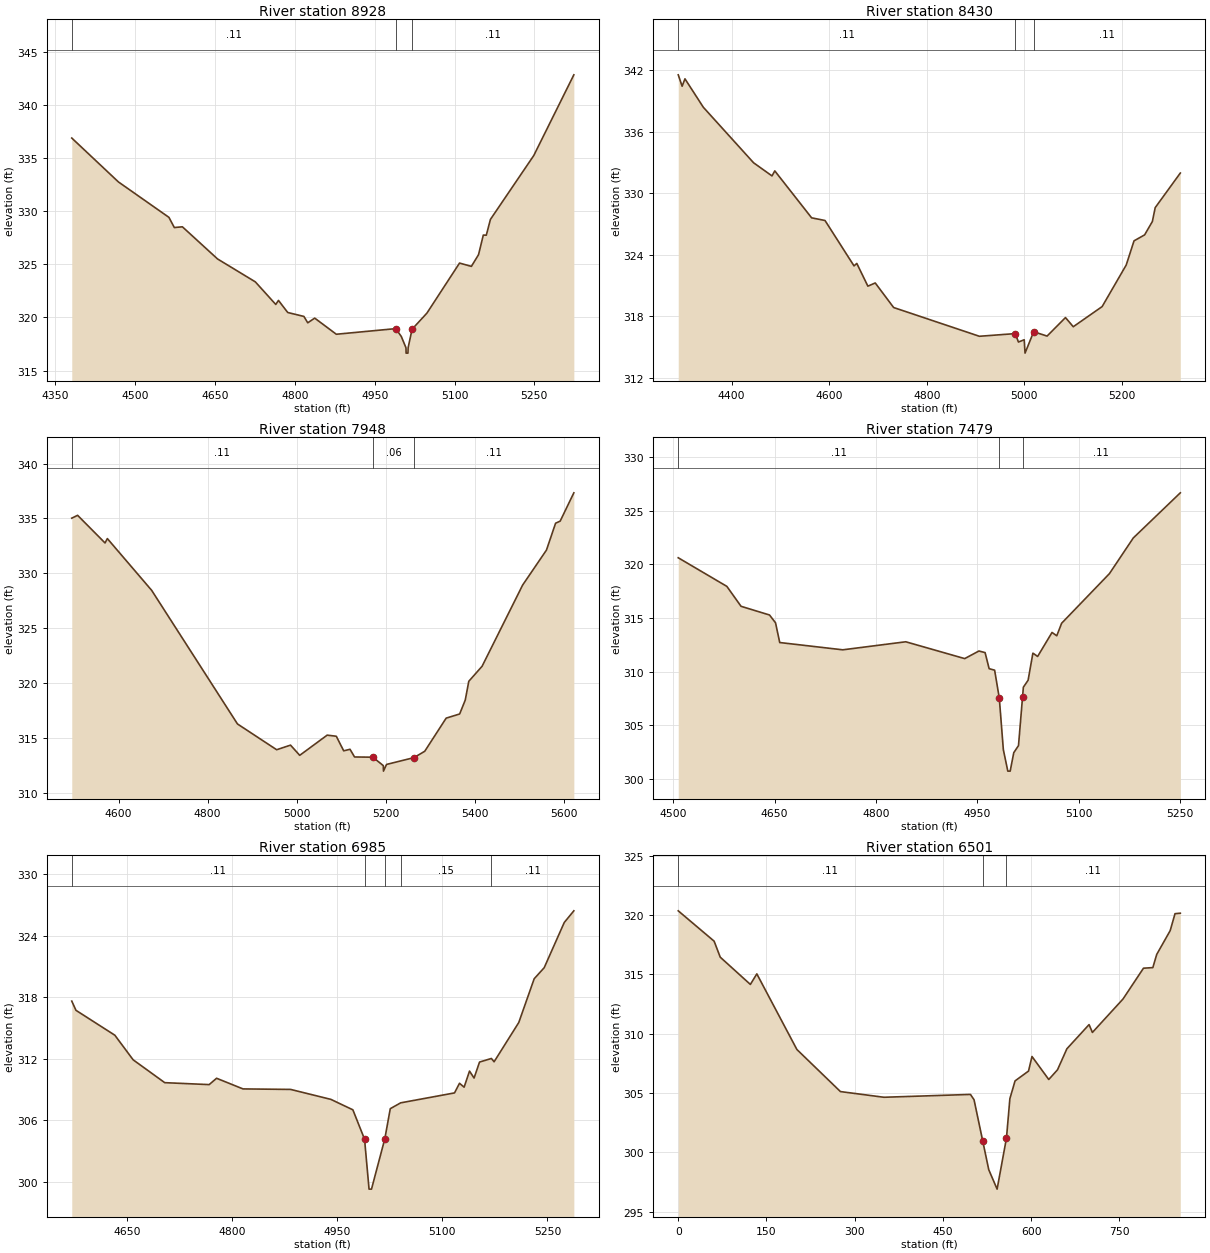
Type RM Length L Ch R = 1 ,8928    ,498,498,498
BEGIN DESCRIPTION:
CCLC 041 13.0
END DESCRIPTION:
XS GIS Cut Line= 3
      3688817.86     10132811.07      3689428.23     10132706.84
      3689717.82     10132561.09
#Sta/Elev= 30
  4380.8  336.92  4468.5  332.78  4563.4  329.44  4573.5  328.48  4588.7  328.55
  4654.7  325.52  4725.7  323.36  4764.1  321.23  4769.2  321.61  4786.6  320.47
    4817   320.1  4824.2   319.5  4837.3  319.94  4877.9  318.42  4989.5  318.95
    5000  318.21  5008.8  317.14    5009  316.64  5012.5  316.64  5012.8  317.14
  5020.2  318.89  5048.1  320.41  5109.4  325.13  5131.7  324.82  5145.1  325.92
  5154.1  327.77  5159.7  327.76  5167.5  329.25  5248.9  335.27  5324.2  342.88
#Mann= 3 , 0 , 0
  4380.8     .11       0  4989.5     .06       0  5020.2     .11       0
Bank Sta=4989.5,5020.2
XS Rating Curve= 0 ,0
Exp/Cntr=0.3,0.1

Type RM Length L Ch R = 1 ,8430    ,482,482,482
BEGIN DESCRIPTION:
CCLC 041 12.0
END DESCRIPTION:
XS GIS Cut Line= 3
      3688817.83     10133411.08      3689438.23     10133066.84
      3689717.87     10132911.06
#Sta/Elev= 30
  4290.5  341.52  4298.5  340.41  4304.3  341.13    4342  338.36    4445  332.96
  4482.8  331.68  4488.5  332.17    4564   327.6  4591.5  327.34    4651  322.92
  4656.7  323.16  4679.4  320.95  4694.5  321.26  4732.2  318.87  4908.1  316.07
  4981.7  316.33  4988.1  315.51    5000  315.73  5001.7  314.43  5019.4  316.51
  5046.9  316.09  5084.6  317.89  5100.6     317  5159.8  318.96  5209.2  323.01
  5225.2  325.36  5246.9  325.94  5262.8  327.24  5268.6  328.59  5320.1  331.96
#Mann= 3 , 0 , 0
  4290.5     .11       0  4981.7     .06       0  5019.4     .11       0
Bank Sta=4981.7,5019.4
XS Rating Curve= 0 ,0
Exp/Cntr=0.3,0.1

Type RM Length L Ch R = 1 ,7948    ,469,469,469
BEGIN DESCRIPTION:
CCLC 041 11.0
END DESCRIPTION:
XS GIS Cut Line= 3
      3688925.23     10133637.63      3689411.09     10133499.91
      3690017.81     10133361.08
#Sta/Elev= 30
    4495  335.03  4508.1  335.29  4569.7  332.77  4574.9  333.17  4674.4  328.45
  4867.1  316.27  4955.1  313.92  4986.2  314.34  5006.9  313.41  5068.5  315.25
    5089  315.15  5105.6  313.82  5119.8  313.96    5130  313.26  5171.1  313.24
  5194.6  312.47  5194.9  311.97  5201.8  312.58  5263.4   313.2  5287.6  313.78
  5335.7   316.8    5366  317.18  5378.6  318.45  5386.5  320.16  5416.4  321.53
  5507.4  328.93  5560.9  332.12  5581.4  334.57  5591.7  334.76  5622.4  337.34
#Mann= 3 , 0 , 0
    4495     .11       0  5171.1     .06       0  5263.4     .11       0
Bank Sta=5171.1,5263.4
XS Rating Curve= 0 ,0
Exp/Cntr=0.3,0.1

Type RM Length L Ch R = 1 ,7479    ,494,494,494
BEGIN DESCRIPTION:
CCLC 041 10.0
END DESCRIPTION:
XS GIS Cut Line= 3
      3689367.99     10133989.17      3689778.23     10133716.84
      3689953.39     10133538.32
#Sta/Elev= 30
  4507.6  320.62  4579.5  317.95  4600.5  316.09  4642.6  315.28  4651.5  314.55
  4657.7  312.71  4750.9  312.03  4844.1  312.78  4931.3  311.21  4952.3  311.92
  4961.4  311.77  4967.4  310.27  4975.5  310.13  4982.4  307.53  4988.4  302.71
    4995  300.71  4998.5  300.71  5003.8  302.43  5010.8  303.09 5016.75307.5938
    5018  308.54    5025  309.19  5032.1  311.72  5039.1  311.41  5060.4  313.65
  5067.4  313.34  5074.6  314.51  5145.3  319.14  5180.6  322.47  5250.1  326.68
#Mann= 3 , 0 , 0
  4507.6     .11       0  4982.4     .06       0 5016.75     .11       0
Bank Sta=4982.4,5016.75
XS Rating Curve= 0 ,0
Exp/Cntr=0.3,0.1

Type RM Length L Ch R = 1 ,6985    ,484,484,484
BEGIN DESCRIPTION:
CCLC 041 9.0
END DESCRIPTION:
XS GIS Cut Line= 3
      3689492.22     10134285.08      3689898.23     10134146.84
      3690117.89     10133961.04
#Sta/Elev= 30
  4571.1  317.62  4577.1  316.72  4632.6  314.29  4658.7  311.89  4703.8  309.66
  4767.2  309.47  4777.8  310.09  4815.5  309.05  4883.5     309  4940.9  308.03
  4972.3  307.01    4989  304.14  4995.4  299.27  4998.9  299.27  5017.9  304.18
  5025.7  307.12  5040.5  307.69  5117.4  308.66  5124.5   309.6  5131.1  309.22
  5138.8  310.79  5145.3  310.11  5153.1  311.67    5170  312.02  5173.9   311.7
  5209.1  315.53  5231.1   319.8  5245.4  320.88    5274  325.29  5287.7  326.43
#Mann= 5 ,-1 , 0
  4571.1     .11       0    4989     .06       0  5017.9     .11       0
  5040.5     .15       0    5170     .11       0
Bank Sta=4989,5017.9
XS Rating Curve= 0 ,0
Exp/Cntr=0.3,0.1

Type RM Length L Ch R = 1 ,6501    ,499,499,499
BEGIN DESCRIPTION:
CCLC 041 8.0
END DESCRIPTION:
XS GIS Cut Line= 3
      3689529.01      10134689.8      3690048.23     10134546.84
      3690322.83     10134392.83
#Sta/Elev= 30
       0  320.37      61  317.81    71.4  316.46   122.6  314.16   133.6  315.05
   201.7  308.67   275.7  305.12   349.7  304.64   496.7  304.88   502.8  304.43
   517.4  300.99   527.8  298.53     542  296.89   557.9  301.19   563.7  304.52
   572.5  306.02   595.4  306.85   601.3  308.08   629.8  306.14   644.7  306.96
   660.6  308.73   698.3  310.77     704  310.11     756  312.93   790.8  315.53
   806.7  315.58   813.3  316.69   836.2   318.7   844.4  320.13   853.4  320.17
#Mann= 3 ,-1 , 0
       0     .11       0   517.4     .06       0   557.9     .11       0
Bank Sta=517.4,557.9
XS Rating Curve= 0 ,0
Exp/Cntr=0.3,0.1

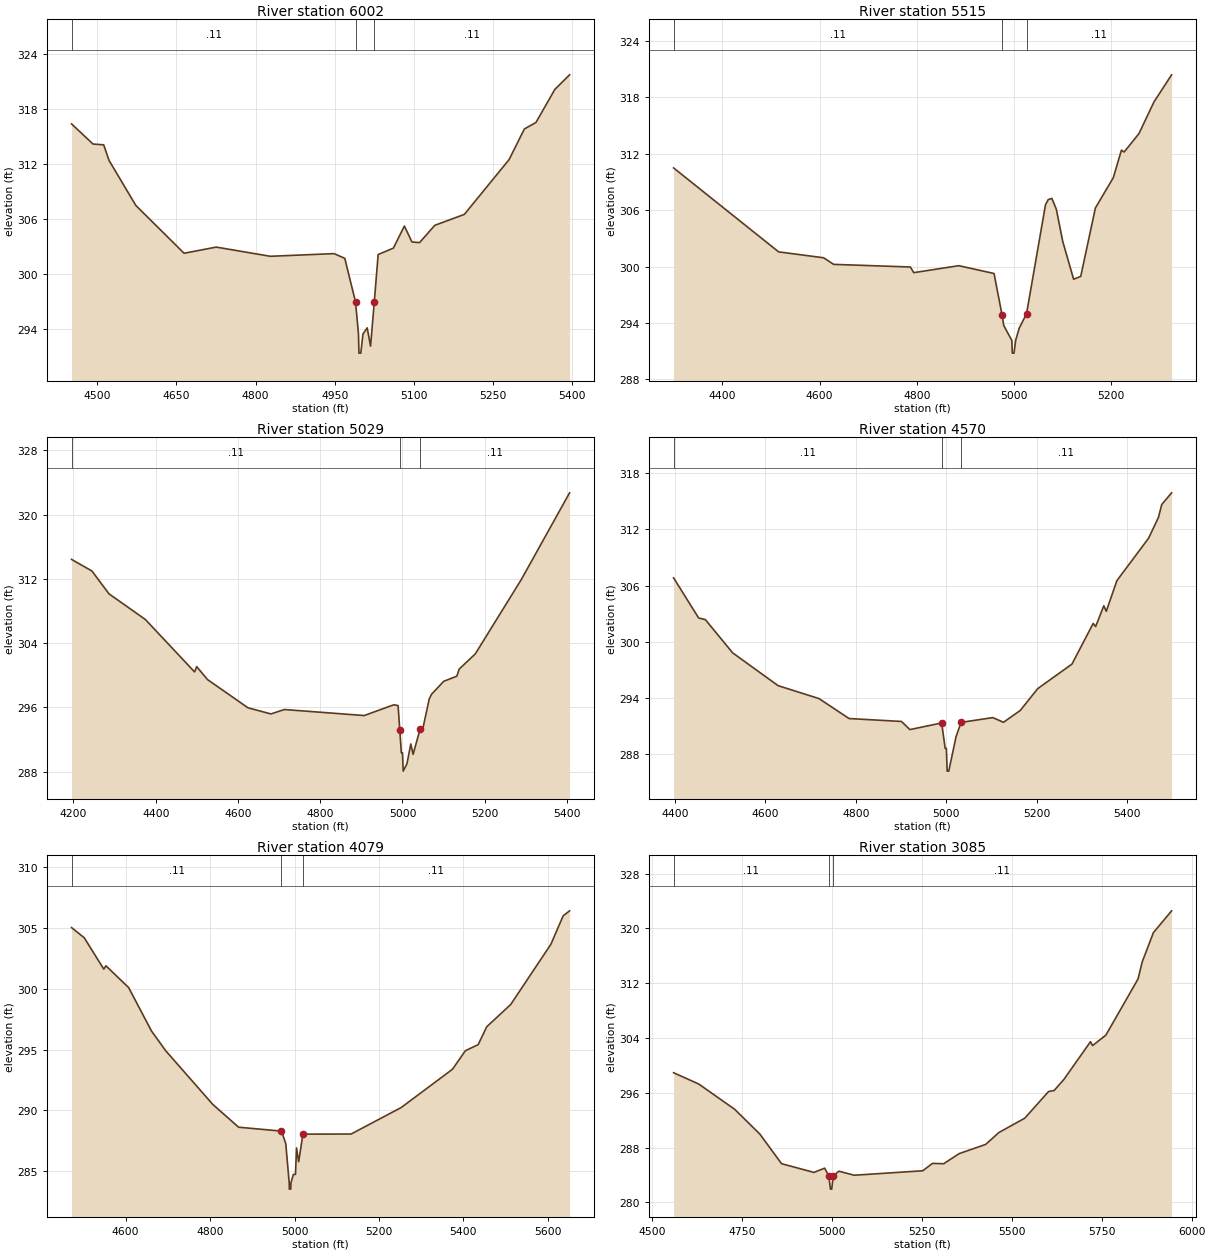
Type RM Length L Ch R = 1 ,6002    ,487,487,487
BEGIN DESCRIPTION:
CCLC 041 7.0
END DESCRIPTION:
XS GIS Cut Line= 3
      3689667.85     10134861.07      3690208.23     10134956.84
      3690517.84     10134711.08
#Sta/Elev= 30
  4451.2  316.37  4491.8  314.18  4512.1  314.09  4522.3  312.39  4573.1  307.49
  4664.5  302.29  4725.4  302.96  4827.9  301.96  4948.8  302.25  4969.1  301.74
  4989.5     297  4995.1   293.5    4996  291.42  4999.5  291.42  5003.6   293.5
  5011.6  294.17    5018  292.18  5025.1  297.02  5032.4  302.15  5061.3  302.85
  5082.1  305.25  5096.5  303.52  5110.9  303.45  5139.8  305.33  5195.8  306.52
  5280.7  312.49  5309.6  315.82  5331.5  316.52  5367.3  320.12  5395.3  321.71
#Mann= 3 , 0 , 0
  4451.2     .11       0  4989.5     .06       0  5025.1     .11       0
Bank Sta=4989.5,5025.1
XS Rating Curve= 0 ,0
Exp/Cntr=0.3,0.1

Type RM Length L Ch R = 1 ,5515    ,486,486,486
BEGIN DESCRIPTION:
CCLC 041 6.0
END DESCRIPTION:
XS GIS Cut Line= 3
      3689697.85     10135191.44      3690378.23     10135356.84
      3690667.82     10135211.09
#Sta/Elev= 30
  4299.8  310.49  4515.9  301.56  4608.5  300.93  4629.1  300.23  4786.9  299.95
  4793.8  299.35  4886.4  300.09    4959  299.26 4975.45 294.847    4979  293.72
  4995.6  292.14  4996.6  290.79  5000.1  290.79  5003.4  292.14  5010.8  293.45
  5025.8  294.97  5064.8  306.56  5070.4  307.12  5077.9  307.25  5087.1   306.1
  5100.3  302.67  5122.7  298.65  5137.3  298.95  5167.5  306.23  5204.3  309.45
    5221  312.38  5226.6  312.18  5257.1  314.14    5288  317.51  5324.2  320.39
#Mann= 3 , 0 , 0
  4299.8     .11       0 4975.45     .06       0  5025.8     .11       0
Bank Sta=4975.45,5025.8
XS Rating Curve= 0 ,0
Exp/Cntr=0.3,0.1

Type RM Length L Ch R = 1 ,5029    ,459,459,459
BEGIN DESCRIPTION:
CCLC 041 5.0
END DESCRIPTION:
XS GIS Cut Line= 3
      3689736.86     10135968.35      3690518.23     10135776.84
      3690881.74     10135595.57
#Sta/Elev= 30
  4195.5  314.42    4245  312.98  4286.6  310.13  4374.9  306.94  4494.6  300.41
  4499.7  301.07    4526  299.46  4624.5  295.94  4680.4  295.18  4712.8  295.73
  4906.9  294.98    4979  296.32  4989.3  296.22 4993.43293.1459  4997.2  290.34
    5000  290.34  5001.7  288.06  5010.8  288.97  5020.2  291.44  5025.8  290.15
  5042.6  293.26  5048.2  293.05    5065  297.05  5070.6  297.63  5100.1  299.24
  5132.1  299.88  5137.7  300.76  5176.9  302.65  5288.8  311.91  5406.2  322.71
#Mann= 3 , 0 , 0
  4195.5     .11       0 4993.43     .06       0  5042.6     .11       0
Bank Sta=4993.43,5042.6
XS Rating Curve= 0 ,0
Exp/Cntr=0.3,0.1

Type RM Length L Ch R = 1 ,4570    ,491,491,491
BEGIN DESCRIPTION:
CCLC 041 4.0
END DESCRIPTION:
XS GIS Cut Line= 3
      3689967.87     10136261.07      3690568.23     10136206.84
      3691024.41     10136008.08
#Sta/Elev= 30
  4397.2  306.84  4452.6  302.56  4467.5  302.38  4527.7  298.84  4628.1  295.34
  4718.5  293.96    4785  291.83  4900.8  291.52  4919.3  290.65  4989.6  291.36
  4997.3  288.65    5000  288.65  5001.7  286.22  5005.2  286.22  5021.4   289.9
  5032.4  291.42  5102.6  291.93  5126.1  291.43  5163.2  292.69  5201.8  295.02
  5277.5  297.64  5324.4  301.98  5329.8  301.64  5347.8  303.86  5353.3  303.27
  5376.7  306.54  5446.8  311.07  5468.6  313.29  5475.8  314.66  5497.6  315.91
#Mann= 3 , 0 , 0
  4397.2     .11       0  4989.6     .06       0  5032.4     .11       0
Bank Sta=4989.6,5032.4
XS Rating Curve= 0 ,0
Exp/Cntr=0.3,0.1

Type RM Length L Ch R = 1 ,4079    ,994,994,994
BEGIN DESCRIPTION:
CCLC 041 3.0
END DESCRIPTION:
XS GIS Cut Line= 3
      3690088.44      10136749.6      3690608.23     10136656.84
      3691251.61     10136554.29
#Sta/Elev= 30
    4472  305.03  4501.9   304.2  4548.3  301.62  4553.4  301.89  4607.2   300.1
  4661.1  296.54  4694.9  294.91  4806.6  290.49  4867.6  288.62  4969.1   288.3
  4979.3  287.28  4987.5  284.03  4987.7  283.53  4991.2  283.53  4991.5  284.03
  4997.3  284.74  5002.3  284.74  5004.8  286.92  5009.9  285.78  5019.9  288.05
  5134.1  288.06  5252.8  290.24  5374.3  293.39  5404.7  294.91    5435  295.41
  5455.3  296.88  5512.1  298.71  5607.2  303.66  5636.3     306  5651.5  306.41
#Mann= 3 , 0 , 0
    4472     .11       0  4969.1     .06       0  5019.9     .11       0
Bank Sta=4969.1,5019.9
XS Rating Curve= 0 ,0
Exp/Cntr=0.3,0.1

Type RM Length L Ch R = 1 ,3085    ,461,461,461
BEGIN DESCRIPTION:
CCLC 041 2.0
END DESCRIPTION:
XS GIS Cut Line= 3
      3690317.86     10137311.07      3690758.23     10137296.84
      3691567.87     10136811.06
#Sta/Elev= 30
  4559.4  298.93  4629.4  297.28  4729.5  293.58  4799.5  289.96  4859.5  285.65
  4949.6  284.37  4979.6  284.99 4991.15283.8279  4995.5  281.93  4999.1  281.93
  5003.4  283.84    5019  284.55  5061.8  283.96  5252.2  284.61  5279.4  285.69
  5310.5  285.64  5353.3  287.11  5427.2  288.46  5464.1   290.2    5536  292.29
  5602.1  296.18  5617.6  296.33  5644.9  297.96  5718.7  303.46  5724.5  302.89
  5761.5  304.42  5850.9  312.62  5862.5  315.11  5893.6  319.38  5944.2  322.57
#Mann= 3 , 0 , 0
  4559.4     .11       0 4991.15     .06       0  5003.4     .11       0
Bank Sta=4991.15,5003.4
XS Rating Curve= 0 ,0
Exp/Cntr=0.3,0.1

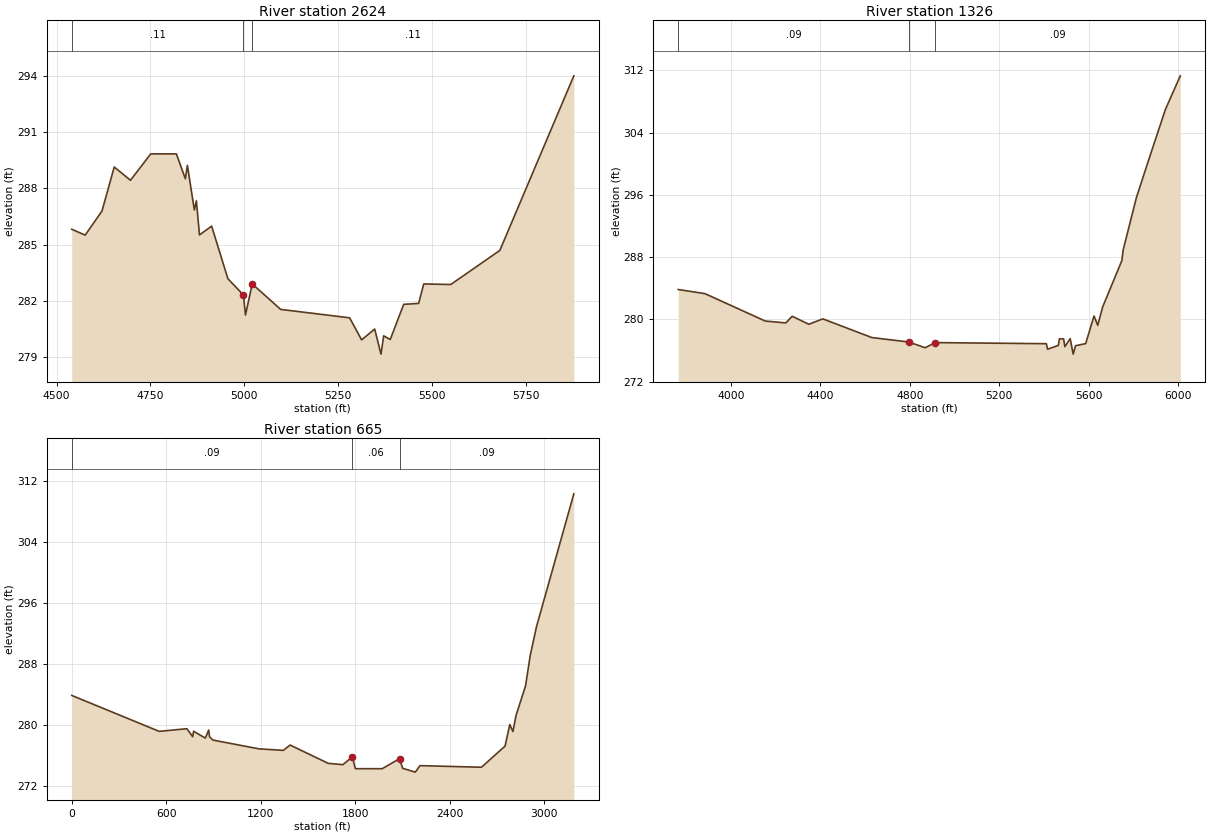
Type RM Length L Ch R = 1 ,2624    ,1298,1298,1298
BEGIN DESCRIPTION:
Mapping XS 4f1a17b8
END DESCRIPTION:
XS GIS Cut Line= 2
      3690353.25     10137891.07      3691590.17     10137383.28
#Sta/Elev= 30
  4540.6  285.82  4576.4  285.51  4621.2   286.8  4653.7  289.15  4696.9  288.44
    4751  289.85  4819.2  289.85  4843.1  288.52  4848.5  289.24  4867.1  286.85
  4872.5  287.34  4880.7  285.52  4913.1  285.99  4956.4  283.18  4997.8  282.31
  5003.2  281.24  5021.2   282.9  5096.9  281.54  5280.6  281.09  5312.5  279.91
  5347.3  280.49  5364.1  279.15  5371.3  280.13  5388.7  279.93  5424.6  281.81
  5464.4  281.86    5478   282.9  5549.9  282.87  5680.6  284.69  5877.7  294.02
#Mann= 3 , 0 , 0
  4540.6     .11       0  4997.8     .06       0  5021.2     .11       0
Bank Sta=4997.8,5021.2
XS Rating Curve= 0 ,0
Exp/Cntr=0.3,0.1

Type RM Length L Ch R = 1 ,1326    ,661,661,661
BEGIN DESCRIPTION:
CCLC 041 1.0
END DESCRIPTION:
XS GIS Cut Line= 3
       3690479.1     10138003.94      3691486.02     10138464.01
      3691920.07     10137409.27
#Sta/Elev= 30
  3763.2  283.84  3882.8  283.31  4152.7  279.79  4244.8  279.55  4273.4   280.4
  4347.9  279.38  4410.5  280.07  4629.7  277.67  4795.3   277.1  4868.5  276.36
  4912.9  277.02  5411.2  276.88  5416.6  276.17  5464.5  276.66  5469.9  277.51
  5488.5   277.5  5493.9   276.5  5517.8  277.53  5531.3  275.54  5541.8  276.62
  5587.1  276.89  5624.5  280.44  5641.2  279.24  5662.8  281.57  5749.3  287.57
    5755  288.92  5814.2  295.64  5868.3  300.41  5944.3  306.99  6010.8  311.29
#Mann= 3 , 0 , 0
  3763.2     .09       0  4795.3     .06       0  4912.9     .09       0
Bank Sta=4795.3,4912.9
XS Rating Curve= 0 ,0
Exp/Cntr=0.3,0.1

Type RM Length L Ch R = 1 ,665     ,0,0,0
XS GIS Cut Line= 3
       3690436.2     10138022.44      3691924.58     10138902.96
      3691950.09     10137442.57
#Sta/Elev= 30
       0  283.87   555.4  279.16     731  279.51     768  278.46   773.8  279.18
     848  278.28   869.4  279.34   875.2  278.45   896.7  278.02  1189.2  276.87
  1343.3  276.67  1386.2  277.37  1628.6  274.97  1721.6   274.8  1781.2  275.81
  1801.2  274.27  1971.3  274.27  2081.3  275.58  2101.3  274.32  2181.3  273.82
  2211.3  274.67  2601.4  274.46  2751.4  277.23  2781.4  280.06  2801.4  279.14
  2821.4  281.28  2881.4  285.11  2911.4  289.12  2951.4  292.91  3188.2  310.29
#Mann= 3 , 0 , 0
       0     .09       0  1781.2     .06       0  2081.3     .09       0
Bank Sta=1781.2,2081.3
XS Rating Curve= 0 ,0
Exp/Cntr=0.3,0.1

Chan Stop Cuts=-1
Use User Specified Reach Order=0
Composite Channel Slope=5