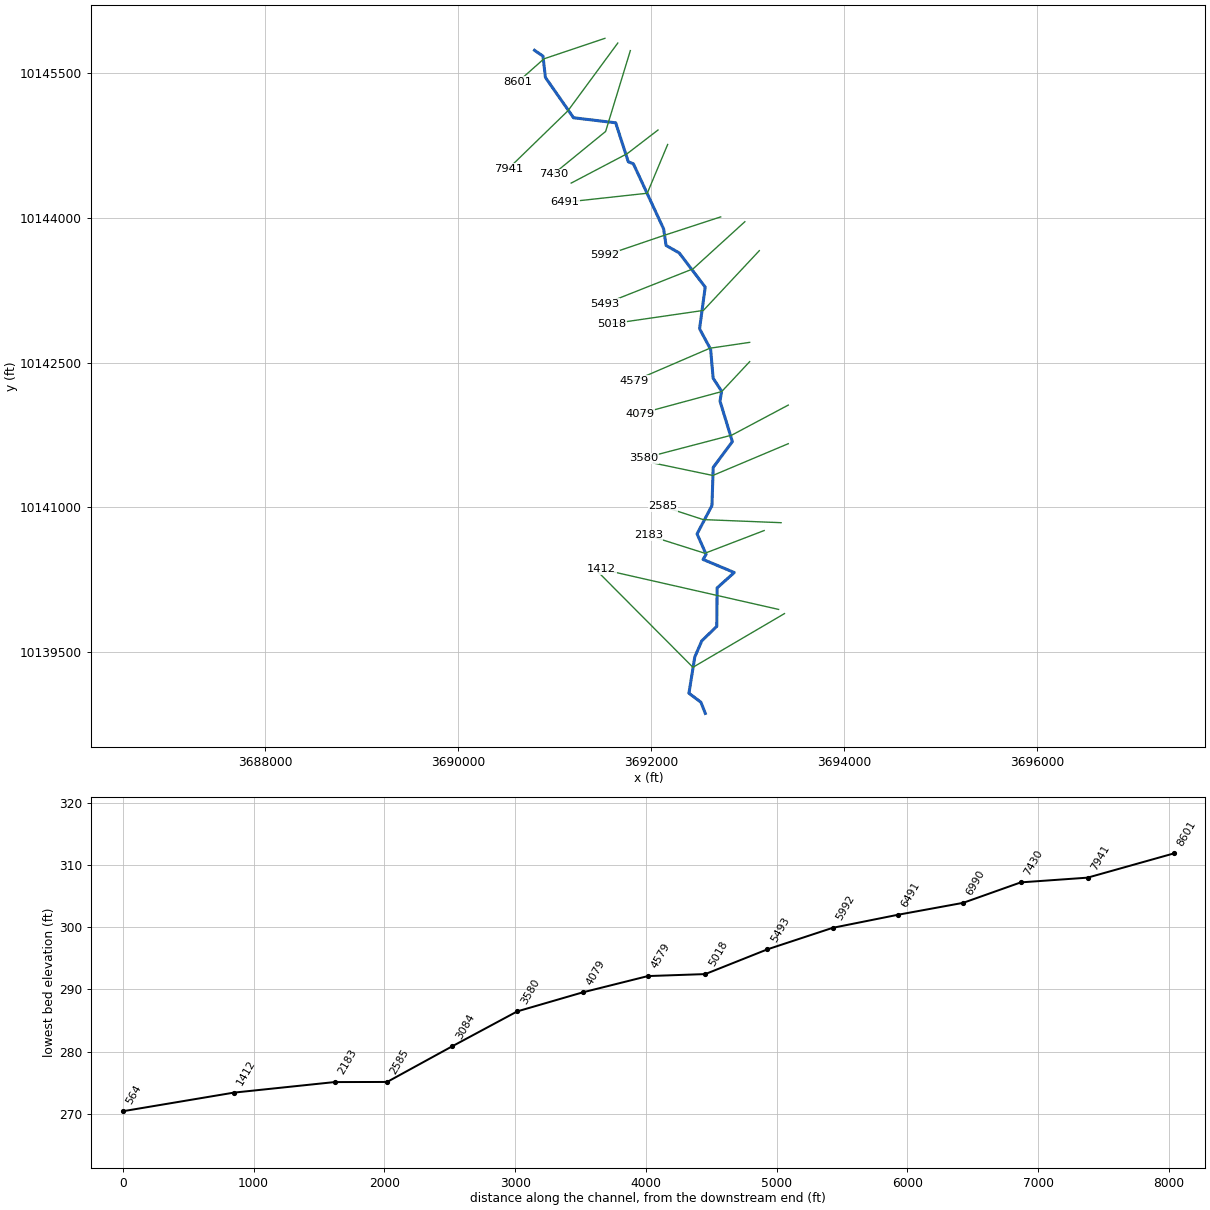
--- CCLC 042.prj (project) ---

Proj Title=CCLC 042 Base Level Engineering
Current Plan=p01
Default Exp/Contr=0.3,0.1
English Units
Geom File=g01
Flow File=f01
Flow File=f02
Plan File=p01
Y Axis Title=Elevation
X Axis Title(PF)=Main Channel Distance
X Axis Title(XS)=Station
BEGIN DESCRIPTION:
CCLC 042
END DESCRIPTION:
DSS Export Rating Curves= 0
DSS Export Rating Curve Sorted= 0
DSS Export Volume Flow Curves= 0
DXF OffsetX= 0
DXF OffsetY= 0
DXF ScaleX= 1
DXF ScaleY= 10

--- CCLC 042.p01 (plan) ---

Plan Title=Multiple Run
Short Identifier=Multiple
Geom File=g01
Flow File=f01
Subcritical Flow
K Sum by GR= 0
Std Step Tol= 0.01
Critical Tol= 0.01
Num of Std Step Trials= 20
Max Error Tol= 0.3
Flow Tol Ratio= 0.001
Split Flow NTrial= 30
Split Flow Tol= 0.02
Split Flow Ratio= 0.02
Log Output Level= 0
Friction Slope Method= 1
Unsteady Friction Slope Method= 2
Unsteady Bridges Friction Slope Method= 1
Parabolic Critical Depth
Global Vel Dist=  1 , 1 , 1
Global Log Level= 0
CheckData=True
Encroach Param= -1, 0, 0, 0
BEGIN DESCRIPTION:
Multiple Run
END DESCRIPTION:

--- CCLC 042.f01 (steady flow) ---

Flow Title=Multiple
Program Version=4.10
Number of Profiles= 7
Profile Names=10-year,25-year,50-year,1pct_min,100-year,1pct_plu,500-year
River Rch & RM=CCLC 042,Reach-1         ,8601
     737    1012    1380     619    1868    5641    3541
River Rch & RM=CCLC 042,Reach-1         ,5018
    1028    1435    1978     896    2705    8169    5236
Boundary for River Rch & Prof#=CCLC 042,Reach-1         , 1
Up Type= 0
Dn Type= 3
Dn Slope=0.005
Boundary for River Rch & Prof#=CCLC 042,Reach-1         , 2
Up Type= 0
Dn Type= 3
Dn Slope=0.005
Boundary for River Rch & Prof#=CCLC 042,Reach-1         , 3
Up Type= 0
Dn Type= 3
Dn Slope=0.005
Boundary for River Rch & Prof#=CCLC 042,Reach-1         , 4
Up Type= 0
Dn Type= 3
Dn Slope=0.005
Boundary for River Rch & Prof#=CCLC 042,Reach-1         , 5
Up Type= 0
Dn Type= 3
Dn Slope=0.005
Boundary for River Rch & Prof#=CCLC 042,Reach-1         , 6
Up Type= 0
Dn Type= 3
Dn Slope=0.005
Boundary for River Rch & Prof#=CCLC 042,Reach-1         , 7
Up Type= 0
Dn Type= 3
Dn Slope=0.005
DSS Import GetInterval= 0
DSS Import GetPeak= 0
DSS Import FillOption= 0

--- CCLC 042.f02 (steady flow) ---

Flow Title=Orig_BLE_Flows
Program Version=4.10
Number of Profiles= 7
Profile Names=10-year,25-year,50-year,1pct_min,100-year,1pct_plu,500-year
River Rch & RM=CCLC 042,Reach-1         ,8601
     737     992    1200     476    1437    4338    2059
River Rch & RM=CCLC 042,Reach-1         ,5018
    1028    1407    1720     689    2081    6283    3044
Boundary for River Rch & Prof#=CCLC 042,Reach-1         , 1
Up Type= 0
Dn Type= 3
Dn Slope=0.005
Boundary for River Rch & Prof#=CCLC 042,Reach-1         , 2
Up Type= 0
Dn Type= 3
Dn Slope=0.005
Boundary for River Rch & Prof#=CCLC 042,Reach-1         , 3
Up Type= 0
Dn Type= 3
Dn Slope=0.005
Boundary for River Rch & Prof#=CCLC 042,Reach-1         , 4
Up Type= 0
Dn Type= 3
Dn Slope=0.005
Boundary for River Rch & Prof#=CCLC 042,Reach-1         , 5
Up Type= 0
Dn Type= 3
Dn Slope=0.005
Boundary for River Rch & Prof#=CCLC 042,Reach-1         , 6
Up Type= 0
Dn Type= 3
Dn Slope=0.005
Boundary for River Rch & Prof#=CCLC 042,Reach-1         , 7
Up Type= 0
Dn Type= 3
Dn Slope=0.005
DSS Import GetInterval= 0
DSS Import GetPeak= 0
DSS Import FillOption= 0

--- CCLC 042.g01 (geometry) ---

Geom Title=Existing Conditions
Program Version=4.10

River Reach=CCLC 042        ,Reach-1
Reach XY= 30
      3690788.23     10145736.84      3690875.84     10145676.81
      3690900.98     10145456.06      3691192.68     10145038.05
      3691629.25     10144985.93      3691759.81     10144581.99
      3691812.87     10144560.94      3692126.03     10143886.77
      3692151.43     10143715.26      3692287.67     10143637.58
      3692557.09     10143283.47       3692498.7     10142852.07
      3692613.31     10142638.56      3692639.35     10142340.17
       3692726.9      10142204.4      3692710.52     10142101.85
      3692838.51     10141682.48      3692639.95     10141415.19
      3692627.06     10141020.31       3692472.7     10140726.38
      3692566.42     10140515.13      3692534.87     10140461.65
      3692858.32     10140326.31      3692680.67     10140166.78
      3692676.84     10139768.45      3692521.45     10139618.12
      3692449.13     10139451.59      3692388.49     10139075.81
      3692512.42     10138982.32      3692558.23     10138866.84

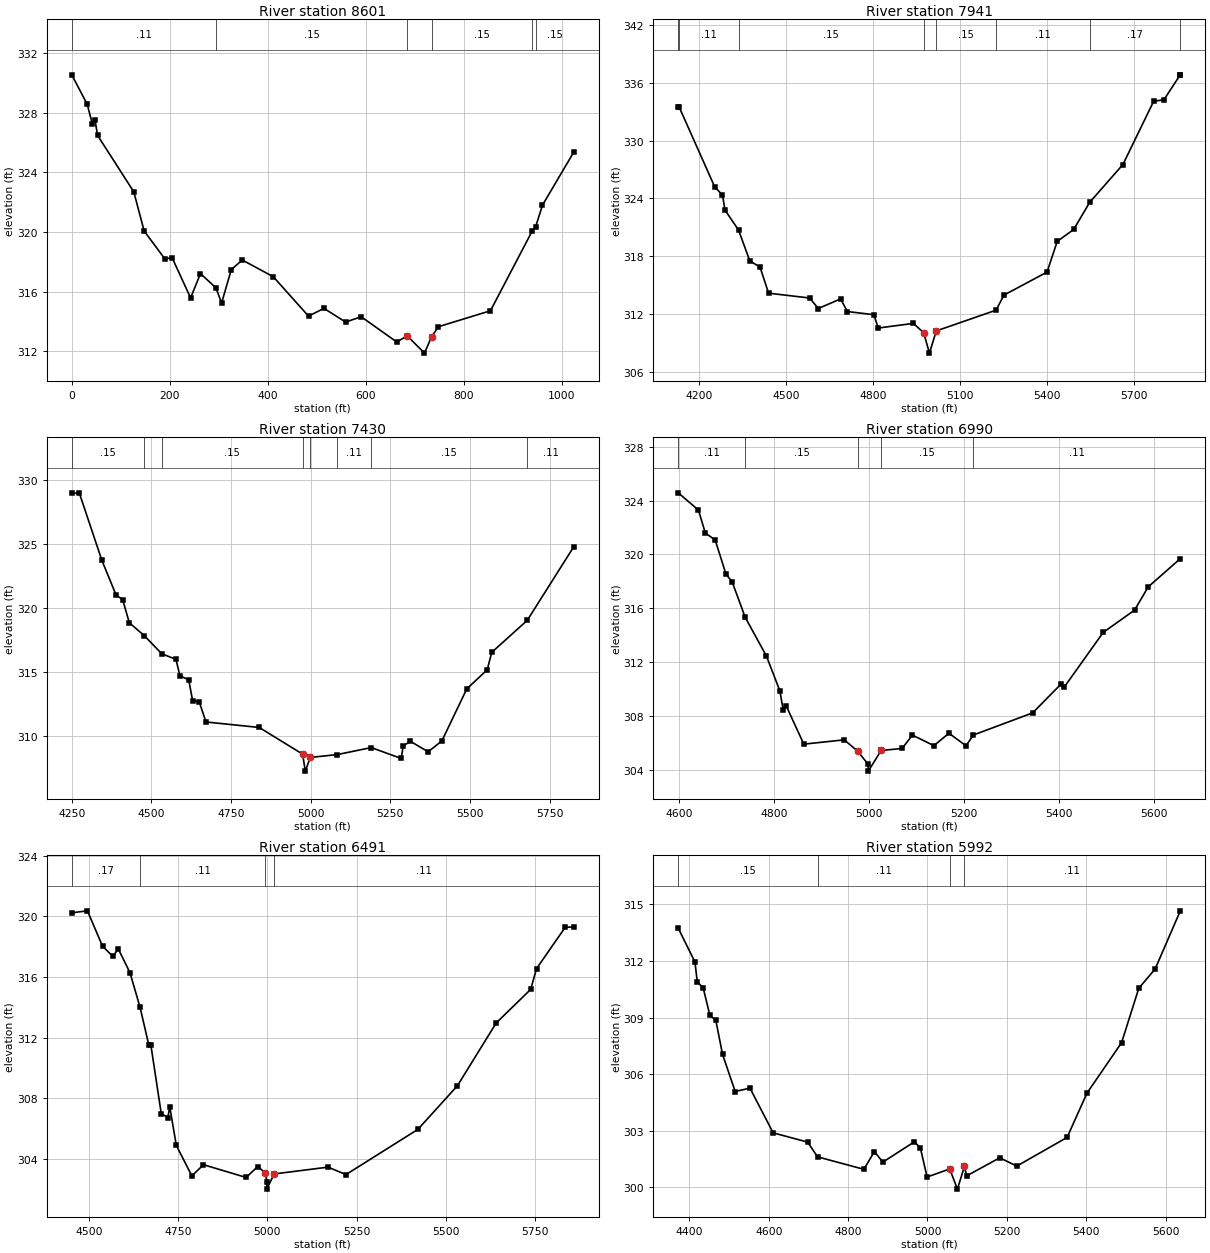
Type RM Length L Ch R = 1 ,8601    ,660,660,660
BEGIN DESCRIPTION:
CCLC 042 15.0
END DESCRIPTION:
XS GIS Cut Line= 3
      3691517.85     10145861.07      3690885.26     10145648.51
      3690617.85     10145411.07
#Sta/Elev= 30
       0  330.53    31.6  328.55      42  327.24    47.3  327.53    52.7  326.47
   126.6  322.69   147.7  320.07   189.9   318.2   204.9  318.27   242.6  315.58
   262.7  317.21   294.2  316.26   305.9  315.24   325.7  317.48   348.1  318.12
   411.4     317   483.3  314.36   514.8  314.88   559.1  313.96   590.8  314.32
   663.3  312.63     685  313.03   720.1  311.88   734.4  312.97   748.6  313.65
   854.8  314.72   940.1  320.07   946.8  320.33     961   321.8    1025  325.36
#Mann= 6 ,-1 , 0
       0     .11       0   294.2     .15       0     685     .09       0
   734.4     .15       0   940.1     .11       0   946.8     .15       0
Bank Sta=685,734.4
XS Rating Curve= 0 ,0
Exp/Cntr=0.3,0.1

Type RM Length L Ch R = 1 ,7941    ,511,511,511
BEGIN DESCRIPTION:
CCLC 042 14.0
END DESCRIPTION:
XS GIS Cut Line= 3
      3691650.98     10145812.13      3691134.38     10145110.12
      3690517.88      10144511.1
#Sta/Elev= 30
  4128.4  333.52  4130.9  333.52  4253.9  325.22    4281  324.35  4289.4  322.81
  4336.5  320.72  4375.1  317.54  4410.6  316.88  4439.9  314.19  4581.8  313.69
  4611.1   312.6  4688.4   313.6  4711.4  312.29  4803.2  311.96  4817.9  310.58
    4939  311.06  4974.5  310.11  4994.6  307.98  5018.1  310.28  5224.3  312.43
  5251.4  313.99  5399.9  316.37  5435.3  319.56  5491.9  320.79  5547.1   323.6
  5661.7  327.52  5767.7  334.07  5803.2  334.23  5859.3  336.81  5859.6  336.81
#Mann= 8 ,-1 , 0
  4128.4     .17       0  4130.9     .11       0  4336.5     .15       0
  4974.5     .09       0  5018.1     .15       0  5224.3     .11       0
  5547.1     .17       0  5859.3     .11       0
Bank Sta=4974.5,5018.1
XS Rating Curve= 0 ,0
Exp/Cntr=0.3,0.1

Type RM Length L Ch R = 1 ,7430    ,440,440,440
BEGIN DESCRIPTION:
CCLC 042 13.0
END DESCRIPTION:
XS GIS Cut Line= 3
      3691781.15     10145733.92      3691525.09      10144896.3
      3690982.57     10144453.61
#Sta/Elev= 30
  4250.3  328.91  4273.8  328.96  4344.6   323.7  4389.2  320.99  4410.1  320.61
    4431  318.81  4478.1   317.8  4532.6  316.39  4577.4  315.95  4589.8  314.67
  4617.4  314.35  4629.7  312.72  4650.2  312.65  4671.6  311.06  4838.9  310.63
  4974.8  308.55  4983.5  307.22    4999  308.29  5083.2  308.51  5190.5  309.06
  5284.3  308.21  5290.8  309.19  5313.1  309.55  5369.1  308.73  5412.1  309.58
  5490.4  313.65  5554.3  315.13  5568.7   316.5  5680.2     319  5826.4  324.76
#Mann= 8 ,-1 , 0
  4250.3     .15       0  4478.1     .11       0  4532.6     .15       0
  4974.8     .09       0    4999     .15       0  5083.2     .11       0
  5190.5     .15       0  5680.2     .11       0
Bank Sta=4974.8,4999
XS Rating Curve= 0 ,0
Exp/Cntr=0.3,0.1

Type RM Length L Ch R = 1 ,6990    ,499,499,499
BEGIN DESCRIPTION:
CCLC 042 12.0
END DESCRIPTION:
XS GIS Cut Line= 3
      3692067.85     10144911.07       3691748.5     10144665.92
      3691167.86     10144361.08
#Sta/Elev= 30
  4597.4  324.57    4640  323.29  4654.5  321.59  4675.3  321.07  4698.1  318.53
  4710.9  317.98  4738.4  315.35  4783.2  312.47  4811.7  309.88  4818.6  308.48
  4824.9  308.78  4862.1  305.93  4947.3  306.25  4975.6  305.41  4997.9  304.43
  4998.1  303.93  5025.1  305.46  5069.2  305.61  5091.2   306.6  5136.3  305.82
  5168.1  306.74    5204  305.81  5219.7  306.61  5344.5  308.25    5405  310.41
  5410.7  310.14  5493.3  314.22  5559.4  315.87    5588  317.59  5655.8  319.69
#Mann= 5 ,-1 , 0
  4597.4     .11       0  4738.4     .15       0  4975.6     .09       0
  5025.1     .15       0  5219.7     .11       0
Bank Sta=4975.6,5025.1
XS Rating Curve= 0 ,0
Exp/Cntr=0.3,0.1

Type RM Length L Ch R = 1 ,6491    ,499,499,499
BEGIN DESCRIPTION:
CCLC 042 11.0
END DESCRIPTION:
XS GIS Cut Line= 3
      3692167.87     10144761.11      3691956.48     10144256.07
      3691104.07     10144162.79
#Sta/Elev= 30
  4452.5  320.23  4496.4  320.36  4538.5  318.03  4567.7  317.35  4582.6  317.85
  4615.2  316.29  4643.6     314  4668.3  311.49  4673.7  311.53  4702.9  306.99
  4721.3  306.73  4726.7  307.43  4745.1  304.89  4788.6  302.88  4821.1  303.62
  4940.4  302.78  4972.9   303.5  4994.6  303.07    4998  302.51  4998.2  302.01
  5018.7  303.01  5169.6  303.46  5219.9  302.97  5421.1  305.95  5531.8  308.83
  5640.4  312.97  5736.7  315.18  5753.1  316.55  5833.6  319.28  5857.5  319.29
#Mann= 4 ,-1 , 0
  4452.5     .17       0  4643.6     .11       0  4994.6     .06       0
  5018.7     .11       0
Bank Sta=4994.6,5018.7
XS Rating Curve= 0 ,0
Exp/Cntr=0.3,0.1

Type RM Length L Ch R = 1 ,5992    ,499,499,499
BEGIN DESCRIPTION:
CCLC 042 10.0
END DESCRIPTION:
XS GIS Cut Line= 3
      3692717.88     10144011.08      3692120.89     10143816.16
      3691517.82     10143611.06
#Sta/Elev= 30
    4372  313.73  4414.1  311.94  4419.9   310.9  4435.1  310.55  4451.8  309.11
  4466.7  308.85  4483.6  307.05  4515.5  305.08  4552.7  305.26  4611.2  302.89
  4698.1   302.4    4723  301.62  4839.7  300.96  4866.3   301.9  4887.5  301.34
  4967.2  302.42  4982.2  302.08    4999  300.55    5056  300.98  5075.4  299.91
  5093.2  301.12  5098.5  300.61  5182.1  301.57    5225  301.13  5351.8  302.65
  5401.7  304.99  5489.1  307.67  5532.4  310.55  5573.6  311.57    5637  314.65
#Mann= 4 ,-1 , 0
    4372     .15       0    4723     .11       0    5056     .06       0
  5093.2     .11       0
Bank Sta=5056,5093.2
XS Rating Curve= 0 ,0
Exp/Cntr=0.3,0.1

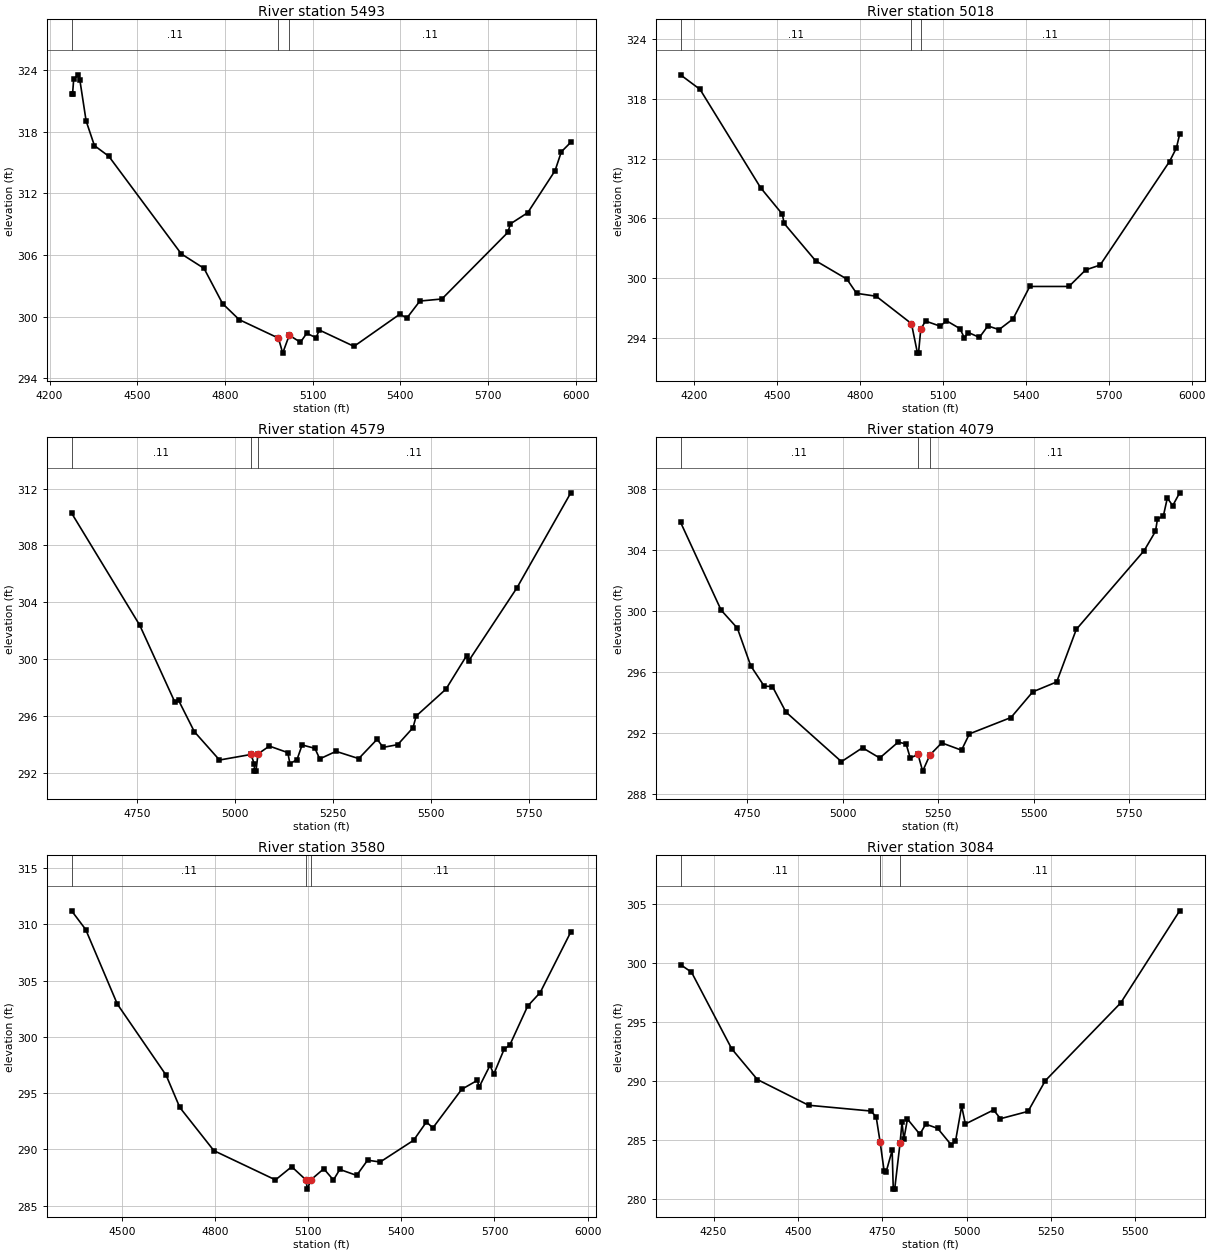
Type RM Length L Ch R = 1 ,5493    ,475,475,475
BEGIN DESCRIPTION:
CCLC 042 9.0
END DESCRIPTION:
XS GIS Cut Line= 3
      3692967.82     10143961.04      3692431.92     10143473.19
      3691517.84     10143111.07
#Sta/Elev= 30
  4275.3  321.72  4278.6  321.72  4282.4  323.12  4296.5  323.54  4303.3  323.07
  4324.9  319.05  4353.3  316.65  4402.6  315.61  4650.6  306.11  4728.3   304.7
  4791.8  301.27  4848.6  299.71    4983  297.91  4997.5  296.45  5019.9  298.19
  5058.2  297.51  5079.7  298.38  5111.9  297.95  5122.6   298.7  5241.5  297.11
  5398.2  300.24  5422.5  299.87  5466.9  301.52  5542.2  301.72  5768.1  308.21
  5776.5  309.03  5835.9  310.12  5929.4  314.21  5950.9  316.05  5983.2  316.97
#Mann= 3 , 0 , 0
  4275.3     .11       0    4983     .06       0  5019.9     .11       0
Bank Sta=4983,5019.9
XS Rating Curve= 0 ,0
Exp/Cntr=0.3,0.1

Type RM Length L Ch R = 1 ,5018    ,439,439,439
BEGIN DESCRIPTION:
CCLC 042 8.0
END DESCRIPTION:
XS GIS Cut Line= 3
      3693117.84     10143661.06      3692538.37      10143041.8
      3691591.51      10142904.3
#Sta/Elev= 30
  4151.9   320.4  4222.5  318.94  4441.8  309.06    4520  306.42  4526.8  305.48
  4640.1  301.75  4753.5   299.9  4788.6  298.47  4859.5  298.18    4987  295.43
  5008.7  292.47  5012.5  292.47  5020.7  294.88  5037.9  295.69  5091.5  295.17
  5113.1  295.73  5162.2  294.93  5178.2  294.01  5192.5  294.54  5232.9  294.05
  5263.3   295.2  5303.7  294.83  5354.2   295.9  5414.8  299.16  5556.3  299.16
  5616.9  300.82  5669.3  301.31  5920.1   311.7  5944.9  313.05  5956.8  314.44
#Mann= 3 , 0 , 0
  4151.9     .11       0    4987     .06       0  5020.7     .11       0
Bank Sta=4987,5020.7
XS Rating Curve= 0 ,0
Exp/Cntr=0.3,0.1

Type RM Length L Ch R = 1 ,4579    ,500,500,500
BEGIN DESCRIPTION:
CCLC 042 7.0
END DESCRIPTION:
XS GIS Cut Line= 3
      3693017.81     10142711.07      3692605.59     10142650.12
      3691817.85     10142311.07
#Sta/Elev= 30
  4583.3  310.27  4757.2   302.4  4846.1  297.04  4856.2  297.13  4896.6  294.92
  4960.8  292.93  5041.1  293.32  5049.7  292.65    5050  292.15  5053.9  292.15
  5059.1  293.36  5088.1  293.91  5135.2  293.45  5140.6  292.67  5158.7  292.96
  5171.7  293.99  5204.4  293.75  5216.7  293.01  5258.3  293.54  5316.2  293.03
  5363.3  294.39  5378.6  293.82  5415.8  294.01  5454.8   295.2  5462.9  296.02
  5538.9  297.91  5591.4  300.25  5596.9  299.89    5720  305.02  5857.6   311.7
#Mann= 3 , 0 , 0
  4583.3     .11       0  5041.1     .06       0  5059.1     .11       0
Bank Sta=5041.1,5059.1
XS Rating Curve= 0 ,0
Exp/Cntr=0.3,0.1

Type RM Length L Ch R = 1 ,4079    ,499,499,499
BEGIN DESCRIPTION:
CCLC 042 6.0
END DESCRIPTION:
XS GIS Cut Line= 3
      3693017.86     10142511.08       3692727.7     10142200.81
       3691876.7     10141970.96
#Sta/Elev= 30
  4575.2  305.82  4681.5  300.06    4724  298.88  4759.1  296.41  4794.3  295.08
  4815.8  295.06    4851  293.39  4996.4  290.14  5051.5  291.05  5096.6  290.38
  5144.9  291.42  5165.6   291.3  5176.4  290.38  5196.7  290.61    5209  289.52
  5227.7  290.57  5258.8  291.37  5310.6  290.89  5331.3  291.96  5440.1  293.03
    5497  294.71  5559.7  295.36    5611   298.8  5788.7  303.96  5818.2  305.22
  5823.4  306.02  5838.9  306.23  5849.2   307.4  5863.3   306.9  5881.5  307.74
#Mann= 3 , 0 , 0
  4575.2     .11       0  5196.7     .06       0  5227.7     .11       0
Bank Sta=5196.7,5227.7
XS Rating Curve= 0 ,0
Exp/Cntr=0.3,0.1

Type RM Length L Ch R = 1 ,3580    ,496,496,496
BEGIN DESCRIPTION:
CCLC 042 5.0
END DESCRIPTION:
XS GIS Cut Line= 3
      3693417.89     10142061.09      3692833.05     10141750.07
      3691917.84     10141511.07
#Sta/Elev= 30
  4337.6   311.2  4382.9  309.54  4484.9  302.91  4642.1  296.59  4686.1  293.73
  4795.9  289.89  4994.4  287.29  5046.7  288.46 5092.34287.2966  5097.2  286.47
  5108.7   287.3  5150.1  288.28  5181.1  287.28  5201.7  288.22  5255.9  287.69
  5291.2  289.04  5331.7  288.88  5439.5  290.81  5480.8  292.44  5501.5  291.91
  5594.5  295.34    5645  296.14  5650.2  295.52  5685.5  297.46  5697.8  296.69
  5731.1   298.9  5749.5  299.28  5806.9  302.73  5847.3  303.94  5945.9  309.32
#Mann= 3 , 0 , 0
  4337.6     .11       0 5092.34     .06       0  5108.7     .11       0
Bank Sta=5092.34,5108.7
XS Rating Curve= 0 ,0
Exp/Cntr=0.3,0.1

Type RM Length L Ch R = 1 ,3084    ,499,499,499
BEGIN DESCRIPTION:
CCLC 042 4.0
END DESCRIPTION:
XS GIS Cut Line= 3
      3693417.87     10141661.08      3692636.29     10141331.82
      3692017.85     10141461.07
#Sta/Elev= 30
  4151.9   299.9  4184.5  299.26  4303.8  292.76  4379.8  290.16  4531.7  287.98
  4716.2  287.49    4732     287 4743.84284.8351  4755.7  282.39  4761.1  282.28
  4779.4  284.16  4782.7  280.87  4786.9  280.87    4803  284.81  4808.6  286.54
    4814  285.08  4824.7  286.81  4861.5  285.52  4878.9  286.38  4914.3  286.02
  4954.9  284.61  4967.2  284.93  4985.5   287.9  4996.4  286.39  5080.1  287.58
  5100.6  286.84  5182.3  287.46  5233.4  290.06  5456.9  296.65  5631.8  304.46
#Mann= 3 , 0 , 0
  4151.9     .11       0 4743.84     .06       0    4803     .11       0
Bank Sta=4743.84,4803
XS Rating Curve= 0 ,0
Exp/Cntr=0.3,0.1

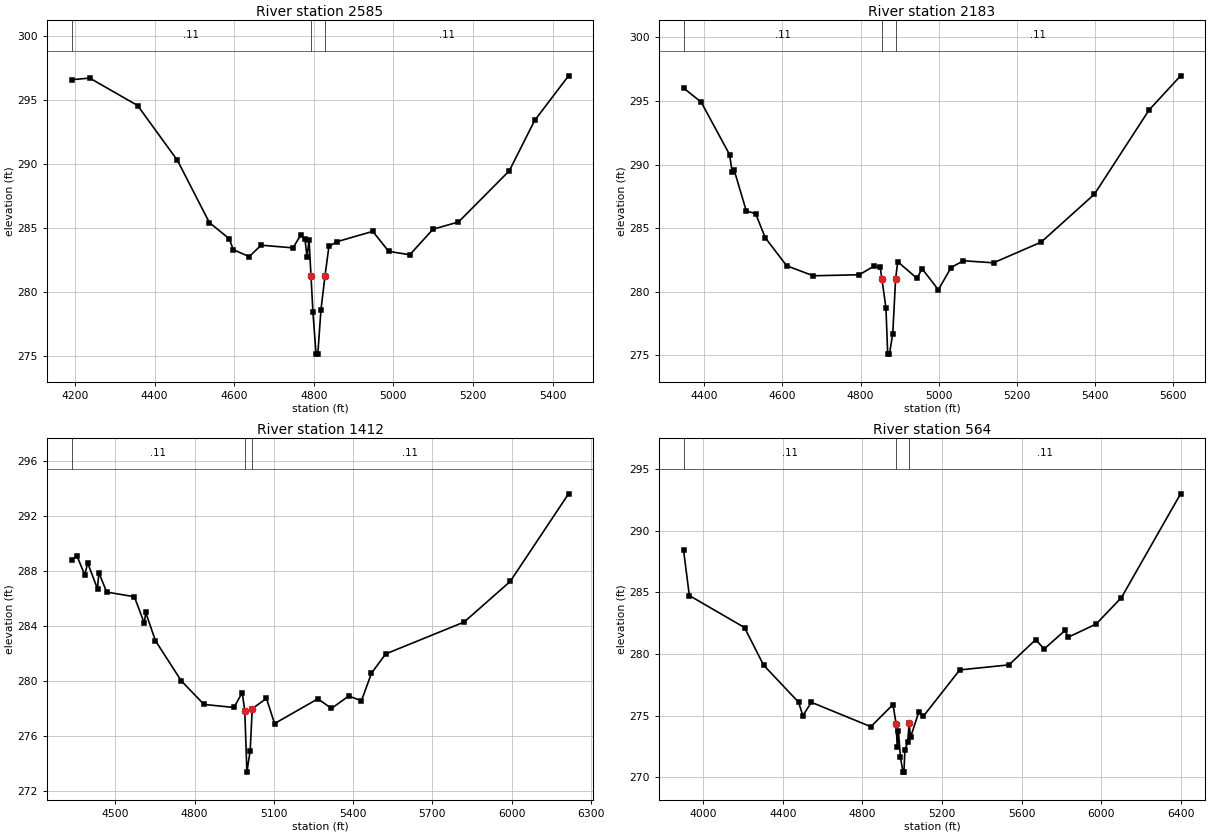
Type RM Length L Ch R = 1 ,2585    ,402,402,402
BEGIN DESCRIPTION:
CCLC 042 3.0
END DESCRIPTION:
XS GIS Cut Line= 3
      3693343.71     10140842.48      3692535.95     10140874.71
      3692117.83     10141011.08
#Sta/Elev= 30
  4191.6  296.56  4237.5  296.68  4357.6  294.54  4457.7  290.25  4537.7   285.4
  4587.8  284.13  4597.8  283.28  4637.8  282.74  4667.8  283.63  4747.9  283.42
  4767.9  284.46  4777.9  284.08  4783.1   282.7  4788.1  284.05 4792.99281.2206
  4797.9  278.38  4805.7  275.12  4810.1  275.12    4818  278.57    4828   281.2
    4838  283.53    4858   283.9  4948.1  284.71  4988.1  283.15    5041  282.88
  5099.5  284.88  5163.3  285.44    5291  289.44  5354.8  293.38  5439.8  296.86
#Mann= 3 , 0 , 0
  4191.6     .11       0 4792.99     .06       0    4828     .11       0
Bank Sta=4792.99,4828
XS Rating Curve= 0 ,0
Exp/Cntr=0.3,0.1

Type RM Length L Ch R = 1 ,2183    ,771,771,771
BEGIN DESCRIPTION:
CCLC 042 2.0
END DESCRIPTION:
XS GIS Cut Line= 3
      3693167.87     10140761.08      3692553.73     10140525.64
       3691967.9     10140711.06
#Sta/Elev= 30
    4347  296.02  4392.1  294.92  4464.8  290.79  4471.5  289.43  4476.8  289.55
  4507.7  286.35  4531.5  286.15  4556.2  284.25  4610.9  282.05    4679  281.26
  4796.8  281.34  4835.1  282.03  4850.4  281.92 4854.88280.9763  4865.1  278.73
  4869.6   275.1    4874   275.1  4882.5  276.71  4889.8  280.99  4895.2  282.37
  4944.5  281.06  4957.5  281.82  4999.2  280.16  5031.9  281.91  5063.3  282.44
  5140.4  282.28  5262.6  283.91  5398.8  287.68  5538.5  294.29  5619.2  296.98
#Mann= 3 , 0 , 0
    4347     .11       0 4854.88     .06       0  4889.8     .11       0
Bank Sta=4854.88,4889.8
XS Rating Curve= 0 ,0
Exp/Cntr=0.3,0.1

Type RM Length L Ch R = 1 ,1412    ,848,848,848
BEGIN DESCRIPTION:
Mapping XS 240b5101
END DESCRIPTION:
XS GIS Cut Line= 2
      3693317.62     10139944.04      3691482.29     10140360.57
#Sta/Elev= 30
    4334  288.84  4354.3  289.13  4384.1  287.74  4395.3   288.6  4432.4  286.72
  4437.5   287.9  4467.1  286.49  4571.9  286.15  4609.9  284.21    4615  285.01
  4651.6  282.96  4749.4  280.04  4835.6  278.32    4949   278.1  4980.3  279.18
    4990  277.86  4998.1   273.4  5010.5  274.97  5018.3  278.01  5072.1  278.76
  5102.8  276.93  5266.9  278.73  5318.2  278.03  5383.6  278.93  5431.8  278.59
  5469.8  280.59  5523.3  281.99  5820.6  284.31    5995  287.26    6216  293.63
#Mann= 3 , 0 , 0
    4334     .11       0    4990     .06       0  5018.3     .11       0
Bank Sta=4990,5018.3
XS Rating Curve= 0 ,0
Exp/Cntr=0.3,0.1

Type RM Length L Ch R = 1 ,564     ,0,0,0
BEGIN DESCRIPTION:
CCLC 042 1.0
END DESCRIPTION:
XS GIS Cut Line= 3
      3693378.42     10139900.66      3692429.87     10139344.25
      3691442.82      10140336.1
#Sta/Elev= 30
  3900.3  288.46  3929.5  284.75    4207  282.15  4302.8   279.1  4478.7  276.09
  4500.2     275  4543.1  276.08  4842.1   274.1  4953.5   275.9  4968.9274.3507
    4975  272.43  4980.8  273.76  4990.7  271.62    5004  270.41  5008.6  270.41
  5013.3   272.2  5027.5  272.84  5034.5  274.37  5041.6  273.23    5084  275.33
  5105.3  274.93  5289.1  278.71  5536.6  279.12    5671  281.17  5713.4  280.41
  5819.4  281.93  5833.6  281.36    5975  282.44  6102.3  284.59  6399.3  293.01
#Mann= 3 ,-1 , 0
  3900.3     .11       0  4968.9     .06       0  5034.5     .11       0
Bank Sta=4968.9,5034.5
XS Rating Curve= 0 ,0
Exp/Cntr=0.3,0.1

Chan Stop Cuts=-1
Use User Specified Reach Order=0
Composite Channel Slope=5