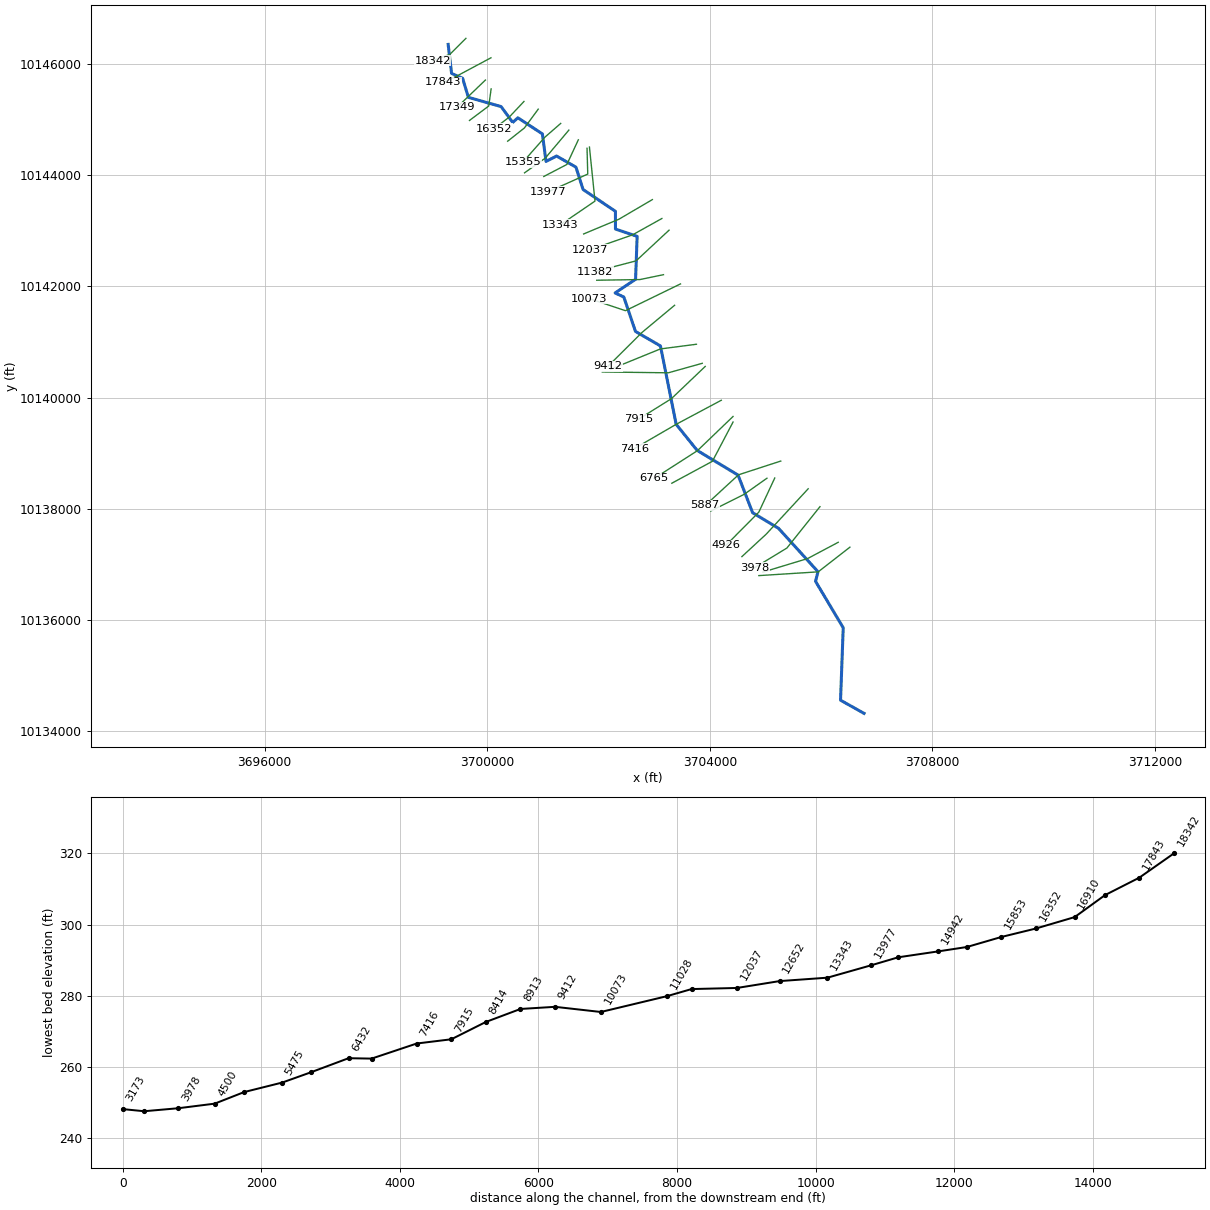
--- CCLC 044.prj (project) ---

Proj Title=CCLC 044 Base Level Engineering
Current Plan=p01
Default Exp/Contr=0.3,0.1
English Units
Geom File=g01
Flow File=f01
Flow File=f02
Plan File=p01
Y Axis Title=Elevation
X Axis Title(PF)=Main Channel Distance
X Axis Title(XS)=Station
BEGIN DESCRIPTION:
CCLC 044
END DESCRIPTION:
DSS Export Rating Curves= 0
DSS Export Rating Curve Sorted= 0
DSS Export Volume Flow Curves= 0
DXF OffsetX= 0
DXF OffsetY= 0
DXF ScaleX= 1
DXF ScaleY= 10

--- CCLC 044.p01 (plan) ---

Plan Title=Multiple Run
Short Identifier=Multiple
Geom File=g01
Flow File=f01
Subcritical Flow
K Sum by GR= 0
Std Step Tol= 0.01
Critical Tol= 0.01
Num of Std Step Trials= 20
Max Error Tol= 0.3
Flow Tol Ratio= 0.001
Split Flow NTrial= 30
Split Flow Tol= 0.02
Split Flow Ratio= 0.02
Log Output Level= 0
Friction Slope Method= 1
Unsteady Friction Slope Method= 2
Unsteady Bridges Friction Slope Method= 1
Parabolic Critical Depth
Global Vel Dist=  1 , 1 , 1
Global Log Level= 0
CheckData=True
Encroach Param= -1, 0, 0, 0
BEGIN DESCRIPTION:
Multiple Run
END DESCRIPTION:

--- CCLC 044.f01 (steady flow) ---

Flow Title=Multiple
Program Version=4.10
Number of Profiles= 7
Profile Names=10-year,25-year,50-year,1pct_min,100-year,1pct_plu,500-year
River Rch & RM=CCLC 044,Reach-1         ,18342
     380     499     660     288     871    2630    1562
River Rch & RM=CCLC 044,Reach-1         ,12652
    1083    1510    2078     939    2837    8568    5470
River Rch & RM=CCLC 044,Reach-1         ,4500
    1106    1527    2088     936    2828    8540    5368
Boundary for River Rch & Prof#=CCLC 044,Reach-1         , 1
Up Type= 0
Dn Type= 3
Dn Slope=0.004
Boundary for River Rch & Prof#=CCLC 044,Reach-1         , 2
Up Type= 0
Dn Type= 3
Dn Slope=0.004
Boundary for River Rch & Prof#=CCLC 044,Reach-1         , 3
Up Type= 0
Dn Type= 3
Dn Slope=0.004
Boundary for River Rch & Prof#=CCLC 044,Reach-1         , 4
Up Type= 0
Dn Type= 3
Dn Slope=0.004
Boundary for River Rch & Prof#=CCLC 044,Reach-1         , 5
Up Type= 0
Dn Type= 3
Dn Slope=0.004
Boundary for River Rch & Prof#=CCLC 044,Reach-1         , 6
Up Type= 0
Dn Type= 3
Dn Slope=0.004
Boundary for River Rch & Prof#=CCLC 044,Reach-1         , 7
Up Type= 0
Dn Type= 3
Dn Slope=0.004
DSS Import GetInterval= 0
DSS Import GetPeak= 0
DSS Import FillOption= 0

--- CCLC 044.f02 (steady flow) ---

Flow Title=Orig_BLE_Flows
Program Version=4.10
Number of Profiles= 7
Profile Names=10-year,25-year,50-year,1pct_min,100-year,1pct_plu,500-year
River Rch & RM=CCLC 044,Reach-1         ,18342
     380     489     574     222     670    2023     908
River Rch & RM=CCLC 044,Reach-1         ,12652
    1083    1480    1807     722    2182    6588    3180
River Rch & RM=CCLC 044,Reach-1         ,4500
    1106    1497    1816     720    2175    6568    3121
Boundary for River Rch & Prof#=CCLC 044,Reach-1         , 1
Up Type= 0
Dn Type= 3
Dn Slope=0.004
Boundary for River Rch & Prof#=CCLC 044,Reach-1         , 2
Up Type= 0
Dn Type= 3
Dn Slope=0.004
Boundary for River Rch & Prof#=CCLC 044,Reach-1         , 3
Up Type= 0
Dn Type= 3
Dn Slope=0.004
Boundary for River Rch & Prof#=CCLC 044,Reach-1         , 4
Up Type= 0
Dn Type= 3
Dn Slope=0.004
Boundary for River Rch & Prof#=CCLC 044,Reach-1         , 5
Up Type= 0
Dn Type= 3
Dn Slope=0.004
Boundary for River Rch & Prof#=CCLC 044,Reach-1         , 6
Up Type= 0
Dn Type= 3
Dn Slope=0.004
Boundary for River Rch & Prof#=CCLC 044,Reach-1         , 7
Up Type= 0
Dn Type= 3
Dn Slope=0.004
DSS Import GetInterval= 0
DSS Import GetPeak= 0
DSS Import FillOption= 0

--- CCLC 044.g01 (geometry) ---

Geom Title=Existing Conditions
Program Version=4.10

River Reach=CCLC 044        ,Reach-1
Reach XY= 30
      3699298.23     10146351.84      3699360.22     10145830.11
      3699558.05     10145742.97      3699661.48     10145400.02
      3700249.82     10145233.85      3700458.34     10144948.81
      3700551.52     10145032.16      3700991.62     10144742.35
      3701057.21      10144247.5      3701246.86      10144344.6
      3701594.94     10144144.16      3701722.68     10143743.23
      3702304.36     10143350.09      3702304.83     10143031.51
      3702694.47     10142899.96      3702666.35     10142127.66
      3702298.55     10141883.07      3702455.26     10141808.63
       3702664.6     10141190.34      3703113.11      10140929.9
      3703395.76     10139520.23      3703773.57     10139050.47
      3704508.05     10138607.13      3704769.63     10137930.47
      3705235.32     10137649.61      3705944.68     10136869.22
      3705900.28     10136696.98      3706397.69     10135861.76
      3706349.46      10134559.2      3706771.84     10134322.24

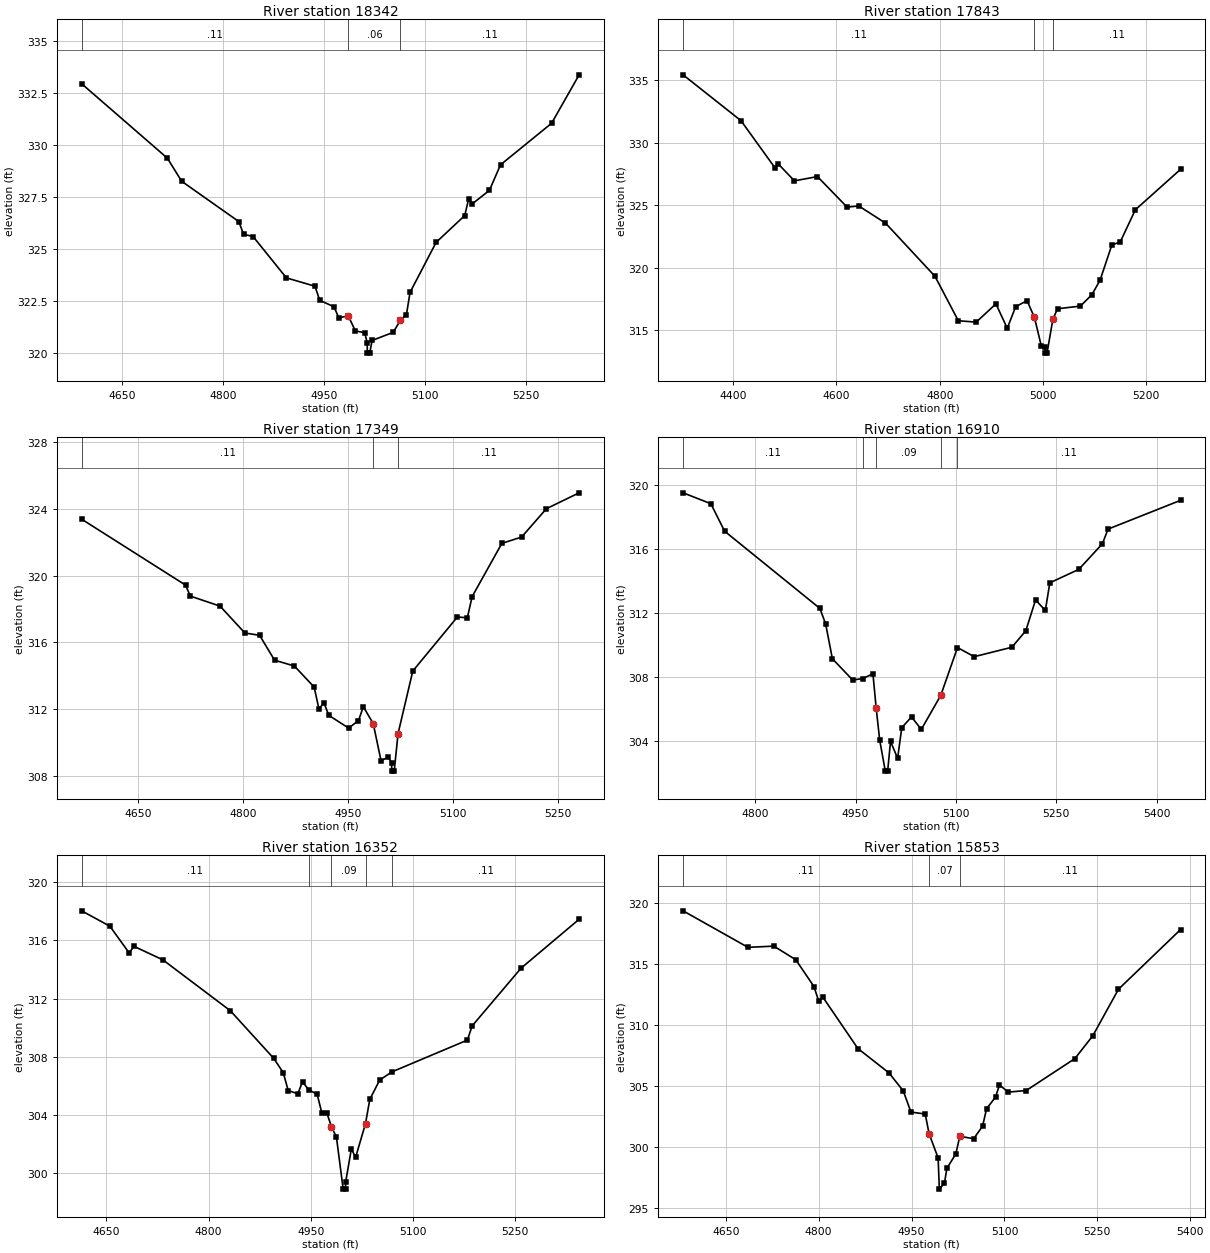
Type RM Length L Ch R = 1 ,18342   ,499,499,499
BEGIN DESCRIPTION:
CCLC 044 32.0
END DESCRIPTION:
XS GIS Cut Line= 3
      3699617.89     10146461.11        3699328.     10146171.73
      3699017.85     10146061.07
#Sta/Elev= 30
  4590.4  332.95  4717.7  329.37  4738.9  328.26  4823.8  326.32  4830.9  325.71
    4845   325.6  4894.5  323.61  4936.9  323.21    4944  322.53  4965.2  322.22
  4972.3  321.69  4986.4  321.78  4996.9  321.06  5010.8  320.97  5014.5  320.49
  5014.7  319.99  5018.2  319.99  5021.8   320.6  5053.2  320.99  5063.9  321.58
  5072.8  321.84  5078.1  322.91  5116.9  325.32  5159.4  326.61  5165.2  327.41
  5170.5  327.17    5196  327.82  5212.5  329.05  5288.4  331.05  5329.3  333.38
#Mann= 3 , 0 , 0
  4590.4     .11       0  4986.4     .06       0  5063.9     .11       0
Bank Sta=4986.4,5063.9
XS Rating Curve= 0 ,0
Exp/Cntr=0.3,0.1

Type RM Length L Ch R = 1 ,17843   ,494,494,494
BEGIN DESCRIPTION:
CCLC 044 31.0
END DESCRIPTION:
XS GIS Cut Line= 3
      3700067.88     10146111.09      3699453.22     10145782.66
      3699212.21     10145669.63
#Sta/Elev= 30
  4303.1  335.43  4415.3  331.76  4481.2  327.98  4486.8  328.33  4518.6  326.95
  4563.3  327.29  4620.6  324.85  4643.3  324.94    4695  323.57  4790.7  319.32
    4836  315.76  4870.6  315.65  4908.8  317.11  4930.7  315.16    4947  316.88
    4969  317.37  4983.4  316.02  4996.4  313.78  5003.9  313.67  5004.2  313.17
  5007.7  313.17    5019  315.87    5028  316.72  5072.2  316.93  5094.3  317.83
  5110.3  318.99  5133.1  321.81  5149.5  322.07  5178.8  324.64  5266.2  327.87
#Mann= 3 , 0 , 0
  4303.1     .11       0  4983.4     .06       0    5019     .11       0
Bank Sta=4983.4,5019
XS Rating Curve= 0 ,0
Exp/Cntr=0.3,0.1

Type RM Length L Ch R = 1 ,17349   ,439,439,439
BEGIN DESCRIPTION:
CCLC 044 30.0
END DESCRIPTION:
XS GIS Cut Line= 3
      3699967.88      10145711.1      3699657.08     10145412.34
      3699454.59     10145217.94
#Sta/Elev= 30
  4568.9  323.38  4717.5  319.43  4724.4  318.77  4766.9  318.17  4802.4  316.56
  4823.5  316.42  4844.9  314.93  4873.2  314.58  4901.5  313.32  4908.4  312.01
  4915.6  312.37  4922.6  311.62  4950.9  310.86    4965  311.31  4971.9  312.14
  4986.1  311.13  4997.3  308.89  5007.5  309.13  5012.4  308.78  5012.6  308.28
  5016.1  308.28  5021.6  310.53  5042.7  314.28  5106.5  317.52  5120.7  317.47
  5127.6  318.74  5170.1  321.93  5198.4  322.31  5233.9  324.01  5280.7  324.96
#Mann= 3 , 0 , 0
  4568.9     .11       0  4986.1     .06       0  5021.6     .11       0
Bank Sta=4986.1,5021.6
XS Rating Curve= 0 ,0
Exp/Cntr=0.3,0.1

Type RM Length L Ch R = 1 ,16910   ,558,558,558
BEGIN DESCRIPTION:
CCLC 044 29.0
END DESCRIPTION:
XS GIS Cut Line= 3
      3700070.88     10145552.12      3700027.47     10145243.95
      3699681.56     10144984.52
#Sta/Elev= 30
  4692.2   319.5  4733.7  318.82  4754.3   317.1  4896.7  312.27  4905.3   311.3
  4915.4  309.12  4945.7  307.79  4960.8  307.88    4976  308.18 4980.82  306.05
  4986.1  304.03  4994.5  302.09    4998  302.09  5002.3  303.95  5012.9  302.89
  5019.1  304.81  5033.7  305.48  5048.3   304.7  5077.4  306.83  5102.4  309.82
  5127.4  309.25  5183.7  309.84  5204.5  310.87  5219.1   312.8  5233.7  312.14
  5240.4  313.87  5283.7  314.71  5319.1  316.32  5327.4  317.23  5435.8  319.03
#Mann= 5 ,-1 , 0
  4692.2     .11       0  4960.8     .17       0 4980.82     .09       0
  5077.4     .17       0  5102.4     .11       0
Bank Sta=4980.82,5077.4
XS Rating Curve= 0 ,0
Exp/Cntr=0.3,0.1

Type RM Length L Ch R = 1 ,16352   ,499,499,499
BEGIN DESCRIPTION:
CCLC 044 28.0
END DESCRIPTION:
XS GIS Cut Line= 3
      3700661.17     10145326.43      3700396.29     10145045.11
      3700123.01       10144836.
#Sta/Elev= 30
  4613.6  318.03  4655.1  316.97  4683.4  315.13  4690.3  315.59  4732.8  314.66
  4831.9  311.16  4895.7  307.88  4909.6   306.9  4916.9  305.67    4931  305.45
  4937.9  306.28  4946.9  305.72  4959.4  305.42  4966.2  304.14  4973.5  304.15
  4980.4  303.18  4987.7  302.47  4997.6  298.89  5001.1  298.89  5001.3  299.39
  5009.6  301.65  5015.9  301.08  5030.4   303.4  5036.7  305.06  5051.2  306.39
    5069  306.95    5180  309.14  5186.9  310.11  5258.9  314.09  5344.1  317.45
#Mann= 5 ,-1 , 0
  4613.6     .11       0  4946.9     .17       0  4980.4     .09       0
  5030.4     .17       0    5069     .11       0
Bank Sta=4980.4,5030.4
XS Rating Curve= 0 ,0
Exp/Cntr=0.3,0.1

Type RM Length L Ch R = 1 ,15853   ,498,498,498
BEGIN DESCRIPTION:
CCLC 044 27.0
END DESCRIPTION:
XS GIS Cut Line= 3
      3700917.22     10145187.52      3700668.92     10144850.02
      3700367.82     10144611.05
#Sta/Elev= 30
    4581  319.37  4685.9  316.37  4727.6  316.47  4763.1  315.35  4792.4  313.15
  4800.1  311.94    4807  312.26  4863.3  308.06  4913.5  306.06  4936.6  304.58
    4949  302.84  4972.1  302.68  4978.3  301.06  4992.9  299.07  4994.9  296.51
  5003.2  297.01    5007  298.21  5021.5  299.41  5027.9  300.85  5050.3  300.65
  5064.7  301.68  5071.1  303.11  5085.6  304.07  5091.9  305.06  5106.4  304.48
  5135.2  304.61  5213.7  307.23  5242.6   309.1  5284.2  312.93  5384.4  317.83
#Mann= 3 ,-1 , 0
    4581     .11       0  4978.3     .07       0  5027.9     .11       0
Bank Sta=4978.3,5027.9
XS Rating Curve= 0 ,0
Exp/Cntr=0.3,0.1

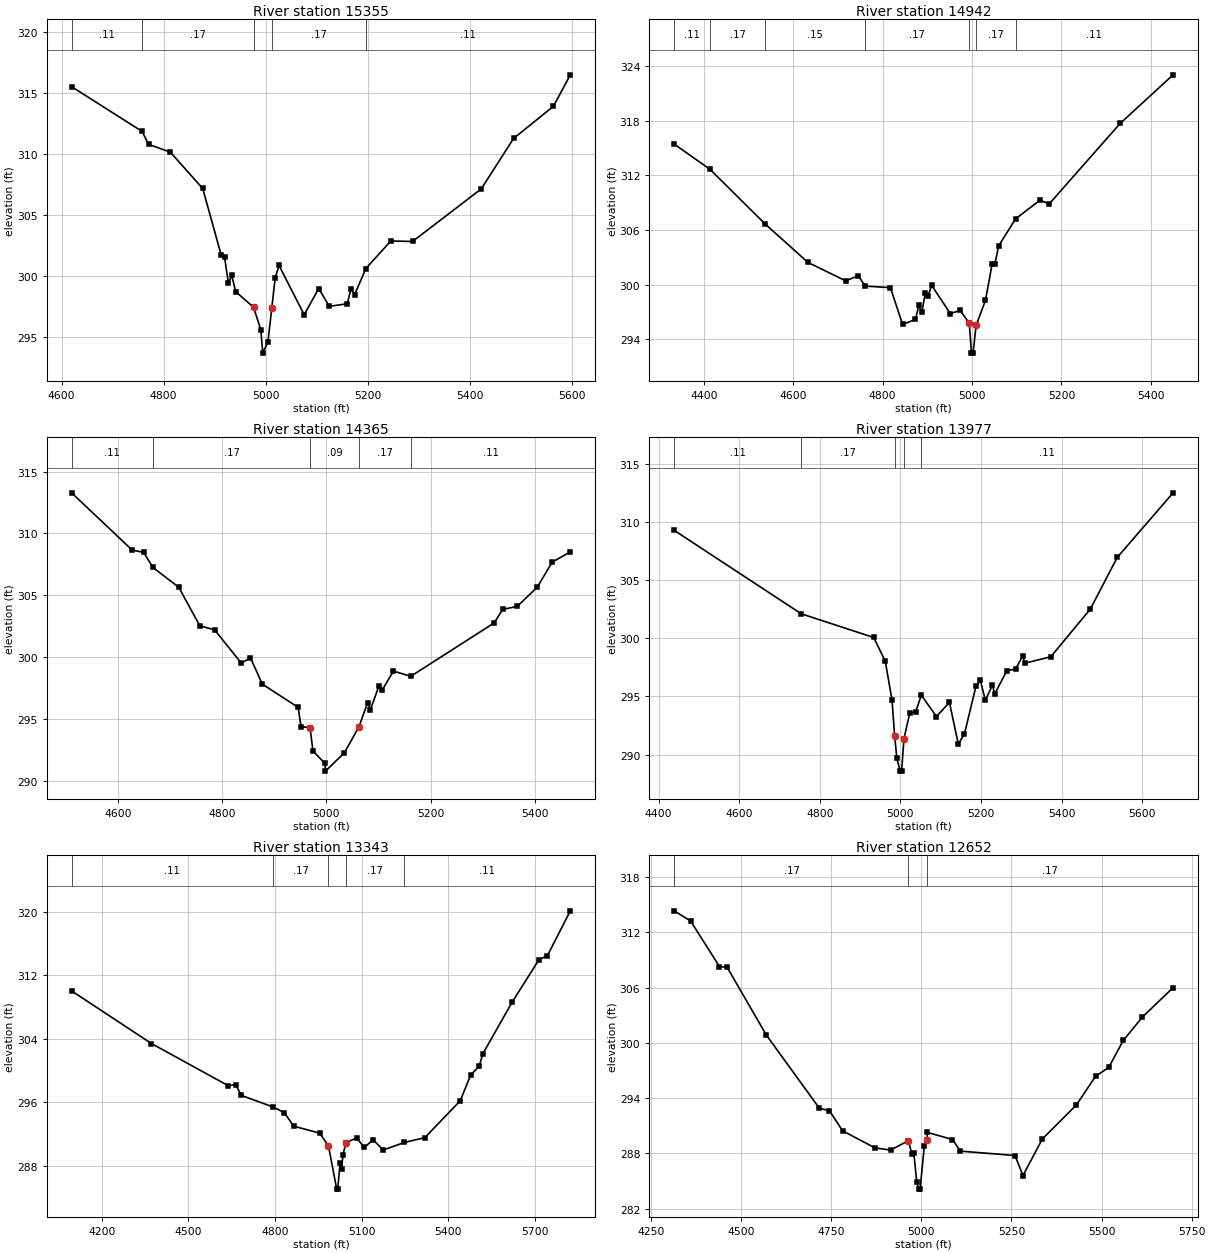
Type RM Length L Ch R = 1 ,15355   ,413,413,413
BEGIN DESCRIPTION:
CCLC 044 26.0
END DESCRIPTION:
XS GIS Cut Line= 3
      3701320.87     10144931.45      3701034.38     10144681.03
      3700639.45     10144232.66
#Sta/Elev= 30
  4619.5  315.55  4757.6  311.88  4770.3  310.82    4813  310.18  4876.6   307.2
  4912.7  301.76  4919.4  301.56    4927  299.44  4933.6  300.06  4941.2  298.74
  4976.3  297.45  4990.5  295.62  4994.4  293.69  5004.5  294.61    5012  297.36
  5018.7  299.86  5026.3  300.88  5075.6  296.84  5104.1  298.99  5124.9  297.53
  5160.1  297.74  5167.6  298.98  5174.3  298.47  5196.6  300.63  5245.4  302.89
  5288.1  302.85  5422.8  307.16  5486.4  311.31  5564.2  313.93  5597.5  316.52
#Mann= 5 ,-1 , 0
  4619.5     .11       0  4757.6     .17       0  4976.3     .09       0
    5012     .17       0  5196.6     .11       0
Bank Sta=4976.3,5012
XS Rating Curve= 0 ,0
Exp/Cntr=0.3,0.1

Type RM Length L Ch R = 1 ,14942   ,577,577,577
BEGIN DESCRIPTION:
CCLC 044 25.0
END DESCRIPTION:
XS GIS Cut Line= 3
      3701467.88     10144811.11       3701043.1     10144306.45
      3700671.35     10144042.77
#Sta/Elev= 30
  4334.3  315.43  4414.2  312.66  4536.9  306.68  4632.8  302.44  4717.4  300.41
    4746  300.97  4760.6  299.83  4817.5  299.66  4844.8  295.61  4873.4  296.17
  4881.2   297.7  4887.7  296.95  4895.5  299.07    4902  298.78  4909.5  299.93
  4951.5   296.8  4973.5  297.16  4993.9  295.73  4998.8  292.46  5002.3  292.46
  5009.2  295.52  5030.1  298.27  5044.9  302.24    5051  302.23  5059.6  304.26
  5097.5  307.23  5151.9  309.27  5172.8  308.88  5331.4  317.72  5449.7  323.06
#Mann= 7 ,-1 , 0
  4334.3     .11       0  4414.2     .17       0  4536.9     .15       0
  4760.6     .17       0  4993.9     .09       0  5009.2     .17       0
  5097.5     .11       0
Bank Sta=4993.9,5009.2
XS Rating Curve= 0 ,0
Exp/Cntr=0.3,0.1

Type RM Length L Ch R = 1 ,14365   ,388,388,388
BEGIN DESCRIPTION:
CCLC 044 24.0
END DESCRIPTION:
XS GIS Cut Line= 3
      3701637.71     10144636.31      3701431.81      10144193.1
      3701017.03     10143976.58
#Sta/Elev= 30
  4511.3  313.28  4627.3  308.66  4649.4  308.47  4667.3  307.25  4716.9  305.65
  4757.2  302.54  4785.6  302.21  4836.9  299.52  4854.3  299.96  4877.1  297.83
  4945.8  295.95  4951.3   294.4  4968.7   294.3  4974.2  292.43  4997.1  291.43
  4998.3   290.8  5034.7  292.29  5062.5  294.39  5078.9   296.3  5084.5  295.77
    5101   297.7  5106.6  297.32  5128.7  298.88  5161.9  298.46  5321.8  302.77
  5338.3  303.87    5366   304.1  5404.5  305.66  5433.1  307.68  5467.9  308.51
#Mann= 5 ,-1 , 0
  4511.3     .11       0  4667.3     .17       0  4968.7     .09       0
  5062.5     .17       0  5161.9     .11       0
Bank Sta=4968.7,5062.5
XS Rating Curve= 0 ,0
Exp/Cntr=0.3,0.1

Type RM Length L Ch R = 1 ,13977   ,634,634,634
BEGIN DESCRIPTION:
CCLC 044 23.0
END DESCRIPTION:
XS GIS Cut Line= 3
      3701793.97     10144484.41      3701806.99       10144020.
      3701101.23     10143703.92
#Sta/Elev= 30
    4439  309.28  4753.9  302.11  4933.8  300.07  4962.5  298.03  4979.3  294.66
  4985.7  291.62  4991.2  289.66  4999.5  288.57    5003  288.57  5008.9  291.37
  5023.2  293.56  5037.6  293.65  5052.1  295.11  5089.4  293.27  5121.8  294.48
  5143.7  290.91    5159  291.77  5187.7  295.89  5198.5  296.37  5210.9  294.66
  5228.6  295.98    5234  295.21  5264.2  297.21  5286.1  297.36  5303.6  298.49
  5309.1  297.86  5373.2  298.41  5471.4  302.51  5538.2  306.96  5676.9  312.52
#Mann= 5 ,-1 , 0
    4439     .11       0  4753.9     .17       0  4985.7     .09       0
  5008.9     .17       0  5052.1     .11       0
Bank Sta=4985.7,5008.9
XS Rating Curve= 0 ,0
Exp/Cntr=0.3,0.1

Type RM Length L Ch R = 1 ,13343   ,691,691,691
BEGIN DESCRIPTION:
CCLC 044 22.0
END DESCRIPTION:
XS GIS Cut Line= 3
      3701837.37     10144506.11       3701937.2     10143533.88
      3701317.89      10143111.1
#Sta/Elev= 30
    4096  310.02  4372.5   303.4    4639  298.08    4664  298.23  4684.1  296.86
    4793  295.42  4832.4  294.71  4865.1     293  4955.5  292.11  4985.7  290.49
  5014.1  285.07  5017.6  285.07  5025.8  288.34  5030.9  287.64    5036  289.42
    5046  290.91  5082.9  291.51  5109.9  290.32  5139.8  291.27  5175.7     290
  5248.1  290.94  5319.3  291.55  5441.9  296.19  5477.8   299.4  5507.6  300.55
  5520.5  302.13  5621.4  308.59  5714.3  313.93    5744  314.47  5823.2   320.1
#Mann= 5 ,-1 , 0
    4096     .11       0    4793     .17       0  4985.7     .09       0
    5046     .17       0  5248.1     .11       0
Bank Sta=4985.7,5046
XS Rating Curve= 0 ,0
Exp/Cntr=0.3,0.1

Type RM Length L Ch R = 1 ,12652   ,615,615,615
BEGIN DESCRIPTION:
CCLC 044 21.0
END DESCRIPTION:
XS GIS Cut Line= 3
      3702967.84     10143561.07      3702366.88     10143208.36
      3701733.19      10142943.6
#Sta/Elev= 30
  4314.9  314.34  4359.9  313.23    4440  308.29  4461.4   308.2    4570  300.85
  4717.4  292.88  4744.7  292.65  4781.8  290.44  4871.5  288.59  4914.7  288.35
  4964.2  289.37  4973.4  287.95  4979.2  288.04  4987.4  284.84    4993  284.11
  4996.6  284.11  5008.3  288.76 5015.28289.4545  5016.9  290.27  5086.5   289.5
  5108.2  288.24  5259.9  287.76    5282  285.59  5335.8  289.56  5430.3  293.26
  5483.3  296.36    5520  297.33  5560.2  300.26  5613.2  302.79  5698.5     306
#Mann= 3 ,-1 , 0
  4314.9     .17       0  4964.2     .09       0 5015.28     .17       0
Bank Sta=4964.2,5015.28
XS Rating Curve= 0 ,0
Exp/Cntr=0.3,0.1

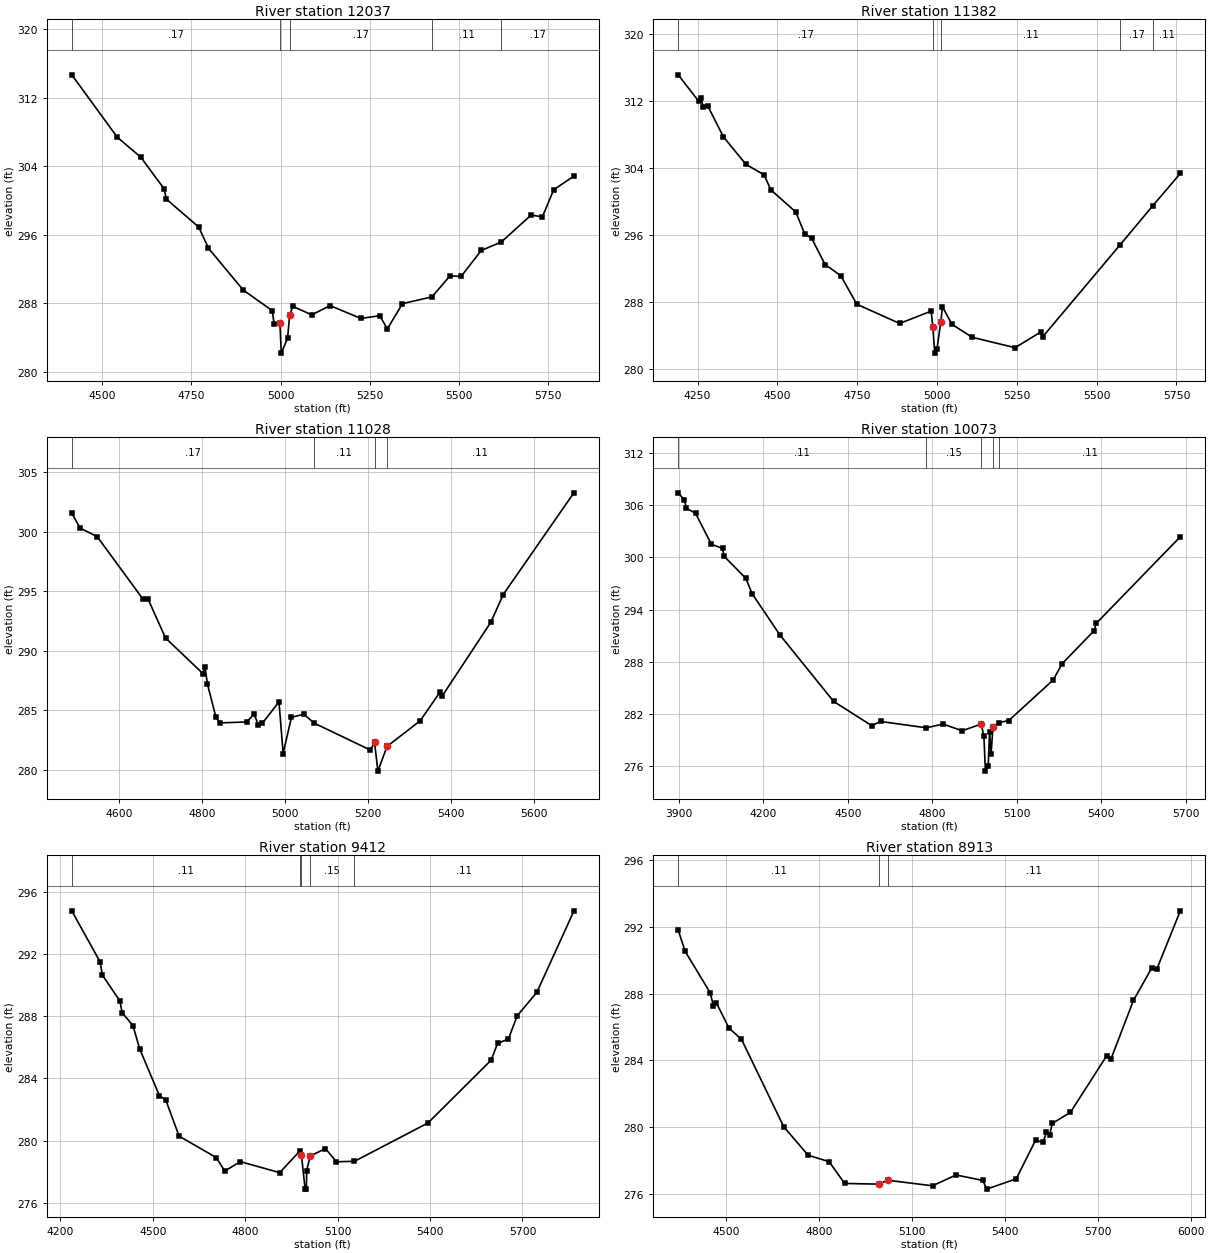
Type RM Length L Ch R = 1 ,12037   ,655,655,655
BEGIN DESCRIPTION:
CCLC 044 20.0
END DESCRIPTION:
XS GIS Cut Line= 3
      3703139.49     10143221.41      3702609.94     10142926.25
      3701854.76      10142661.5
#Sta/Elev= 30
  4414.7  314.68  4542.5  307.38    4608  305.06  4673.2  301.38  4679.9  300.16
  4770.3   296.9  4797.7  294.43  4894.9  289.55    4976  287.15  4981.8   285.6
  4997.7  285.71  5001.7  282.18  5019.3  283.92    5025  286.59  5033.8  287.64
    5087  286.65  5138.4  287.73  5224.5  286.23  5277.5  286.55  5298.8  285.01
  5341.1  287.96  5423.9  288.75  5474.2  291.21  5505.2  291.13  5561.9  294.17
  5618.1  295.16  5701.4   298.3  5733.1   298.1  5764.9  301.27  5821.2  302.84
#Mann= 5 ,-1 , 0
  4414.7     .17       0  4997.7     .09       0    5025     .17       0
  5423.9     .11       0  5618.1     .17       0
Bank Sta=4997.7,5025
XS Rating Curve= 0 ,0
Exp/Cntr=0.3,0.1

Type RM Length L Ch R = 1 ,11382   ,354,354,354
BEGIN DESCRIPTION:
CCLC 044 19.0
END DESCRIPTION:
XS GIS Cut Line= 3
      3703267.84     10143011.06      3702674.49     10142459.06
      3701937.22     10142266.53
#Sta/Elev= 30
  4189.6   315.1  4253.3  311.96  4260.2  312.39  4267.5  311.31  4281.7  311.42
    4331   307.7  4401.9   304.4  4458.5  303.16  4479.5  301.37  4557.7  298.72
  4585.7  296.12  4607.1   295.6  4649.6  292.45  4698.9  291.11  4748.8  287.71
  4883.1  285.41  4981.8  286.89    4987  284.94  4993.1  281.87    5000  282.37
  5011.9  285.64  5017.2  287.38  5047.2   285.3  5110.2  283.76  5244.4  282.52
  5325.3   284.4  5330.4  283.79  5574.1  294.83  5675.1  299.44    5762  303.32
#Mann= 5 ,-1 , 0
  4189.6     .17       0    4987     .06       0  5011.9     .11       0
  5574.1     .17       0  5675.1     .11       0
Bank Sta=4987,5011.9
XS Rating Curve= 0 ,0
Exp/Cntr=0.3,0.1

Type RM Length L Ch R = 1 ,11028   ,955,955,955
BEGIN DESCRIPTION:
CCLC 044 18.0
END DESCRIPTION:
XS GIS Cut Line= 3
      3703167.88     10142211.08      3702744.49     10142123.29
      3701967.88     10142111.07
#Sta/Elev= 30
  4486.1  301.55  4506.1  300.29  4547.4  299.57  4656.6  294.37    4670  294.31
  4711.9  291.06    4802  288.07  4807.1   288.6  4812.9  287.18  4833.4  284.39
  4843.6  283.93  4907.4  284.01  4925.1  284.68  4935.1  283.79  4945.1   283.9
  4985.1   285.7  4995.1  281.36  5015.1   284.4  5045.1  284.66  5069.3  283.92
  5205.2  281.65  5215.2   282.3  5223.3  279.88  5245.2  281.95  5325.2  284.11
  5373.8  286.56  5378.8  286.22  5495.2  292.38  5525.2  294.71  5695.2  303.25
#Mann= 4 ,-1 , 0
  4486.1     .17       0  5069.3     .11       0  5215.2     .09       0
  5245.2     .11       0
Bank Sta=5215.2,5245.2
XS Rating Curve= 0 ,0
Exp/Cntr=0.3,0.1

Type RM Length L Ch R = 1 ,10073   ,661,661,661
BEGIN DESCRIPTION:
CCLC 044 17.0
END DESCRIPTION:
XS GIS Cut Line= 3
      3703473.66     10142045.17      3702484.07      10141563.4
      3701837.35     10141780.42
#Sta/Elev= 30
  3897.6  307.43  3919.6  306.59  3926.3  305.66  3959.1  305.08  4015.3  301.51
  4054.8  301.04  4060.4  300.14  4137.6   297.6  4159.9  295.84  4257.7  291.13
  4449.2  283.45  4584.5  280.66  4615.9  281.14  4778.5  280.41  4838.3  280.84
  4905.7  280.07  4973.3  280.84  4982.9  279.49  4988.3  275.43  4998.2     276
  5003.1  279.98  5008.4  277.36  5015.3  280.55    5038  281.02  5071.4  281.25
  5229.1  285.91  5260.7  287.78    5374  291.57  5381.5  292.41  5680.4  302.38
#Mann= 5 ,-1 , 0
  3897.6     .11       0  4778.5     .15       0  4973.3     .09       0
  5015.3     .15       0    5038     .11       0
Bank Sta=4973.3,5015.3
XS Rating Curve= 0 ,0
Exp/Cntr=0.3,0.1

Type RM Length L Ch R = 1 ,9412    ,499,499,499
BEGIN DESCRIPTION:
CCLC 044 16.0
END DESCRIPTION:
XS GIS Cut Line= 3
      3703367.86     10141661.08      3702782.25     10141172.45
      3702167.82     10140561.04
#Sta/Elev= 30
  4237.3  294.78  4329.1   291.5  4336.9  290.64  4393.6  288.98  4400.7  288.23
  4435.8   287.4  4457.9  285.89  4521.7  282.89  4542.5  282.61  4585.5  280.29
  4706.2  278.91  4733.9  278.04  4784.3  278.65  4912.2  277.94  4976.9  279.32
  4982.5  279.09  4994.7  276.88  4998.9  276.88  4999.6  278.07  5011.1  279.01
  5060.7  279.49    5096  278.64  5154.9  278.67    5393  281.13  5598.1  285.17
  5619.3  286.25  5654.6  286.54  5682.9  288.03  5746.5  289.53  5866.8  294.76
#Mann= 5 ,-1 , 0
  4237.3     .11       0  4976.9     .15       0  4982.5     .09       0
  5011.1     .15       0  5154.9     .11       0
Bank Sta=4982.5,5011.1
XS Rating Curve= 0 ,0
Exp/Cntr=0.3,0.1

Type RM Length L Ch R = 1 ,8913    ,499,499,499
BEGIN DESCRIPTION:
CCLC 044 15.0
END DESCRIPTION:
XS GIS Cut Line= 3
      3703760.14      10140960.1      3703111.53     10140875.52
      3702217.88     10140511.08
#Sta/Elev= 30
  4345.9  291.81  4368.4  290.54  4449.1  288.06  4459.3  287.27  4469.2  287.45
  4509.6  285.94  4549.9  285.27  4686.2  280.02  4765.2  278.31  4832.3  277.93
  4882.7  276.62  4992.2  276.58  5022.6  276.81    5166  276.48  5241.9  277.13
    5328   276.8    5341  276.28    5436   276.9  5498.5  279.22  5522.4  279.08
  5533.4  279.69  5543.9  279.53    5552  280.22  5610.9  280.89  5727.5  284.28
  5741.9  284.11  5813.9   287.6  5872.9  289.55  5889.5  289.49  5965.1  292.98
#Mann= 3 , 0 , 0
  4345.9     .11       0  4992.2     .06       0  5022.6     .11       0
Bank Sta=4992.2,5022.6
XS Rating Curve= 0 ,0
Exp/Cntr=0.3,0.1

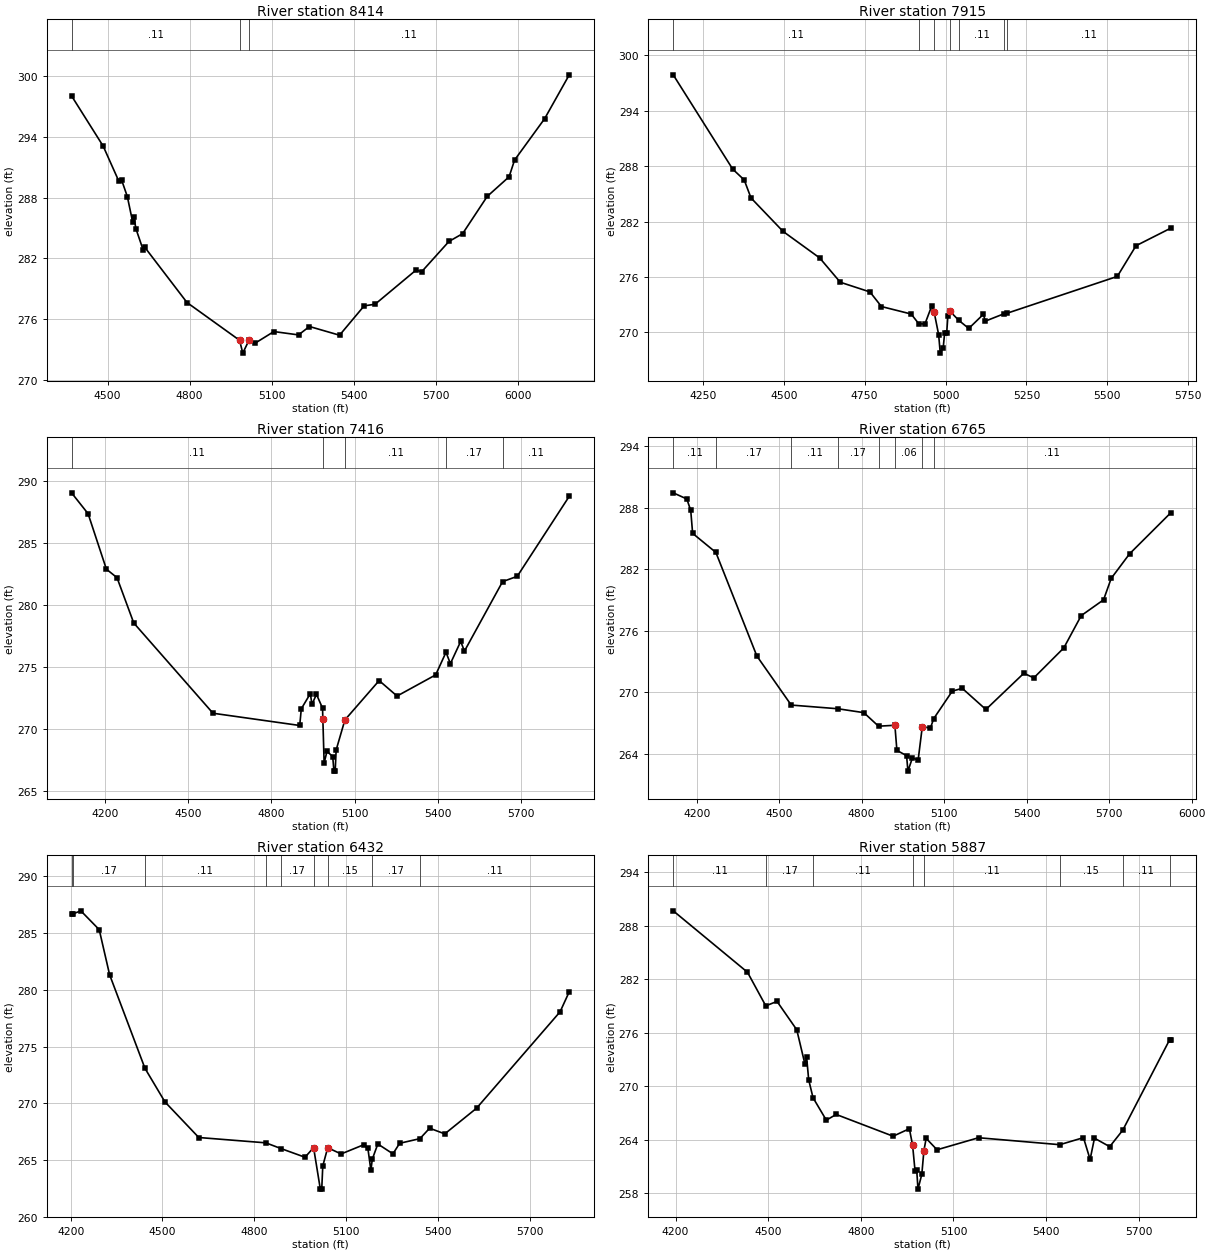
Type RM Length L Ch R = 1 ,8414    ,499,499,499
BEGIN DESCRIPTION:
CCLC 044 14.0
END DESCRIPTION:
XS GIS Cut Line= 3
      3703864.26     10140617.21      3703255.79     10140446.75
      3702067.88     10140461.07
#Sta/Elev= 30
  4368.1  298.04  4483.7  293.08  4540.9  289.62  4551.3  289.72  4572.1  288.09
  4591.2  285.63  4596.4  286.08  4603.2  284.94  4630.5  282.78  4635.7  283.09
  4790.2  277.63 4982.45 273.899  4994.2  272.63  5017.9  273.96  5037.9  273.59
  5107.9  274.76    5198  274.43    5238  275.26    5348   274.4    5438   277.3
    5478  277.46    5628  280.84    5648  280.66    5748  283.66    5798  284.43
    5888  288.11    5968  290.05    5988   291.7    6098  295.79    6188  300.12
#Mann= 3 , 0 , 0
  4368.1     .11       0 4982.45     .06       0  5017.9     .11       0
Bank Sta=4982.45,5017.9
XS Rating Curve= 0 ,0
Exp/Cntr=0.3,0.1

Type RM Length L Ch R = 1 ,7915    ,499,499,499
BEGIN DESCRIPTION:
CCLC 044 13.0
END DESCRIPTION:
XS GIS Cut Line= 3
      3703917.83     10140561.05       3703308.7     10139980.03
      3702717.84     10139611.07
#Sta/Elev= 30
  4158.2  297.87    4342  287.67  4377.6   286.5  4398.6  284.55  4497.7  280.93
  4610.9  278.06  4674.5  275.43  4766.3  274.38  4801.8   272.8  4893.7  271.99
  4916.7  270.96  4936.1   270.9  4957.5  272.89  4964.4  272.25  4978.6  269.76
  4983.6  267.76  4992.8  268.36  4997.1  269.93  5003.5  269.93  5007.2   271.8
  5013.1  272.31  5041.1   271.3  5071.7  270.43  5116.9  271.96  5122.8  271.22
  5182.1  272.04  5188.7  272.06  5530.9  276.06  5588.7  279.38  5696.6  281.29
#Mann= 7 ,-1 , 0
  4158.2     .11       0  4916.7     .15       0  4964.4     .09       0
  5013.1     .15       0  5041.1     .11       0  5182.1     .15       0
  5188.7     .11       0
Bank Sta=4964.4,5013.1
XS Rating Curve= 0 ,0
Exp/Cntr=0.3,0.1

Type RM Length L Ch R = 1 ,7416    ,651,651,651
BEGIN DESCRIPTION:
CCLC 044 12.0
END DESCRIPTION:
XS GIS Cut Line= 3
      3704207.18     10139953.17      3703395.76     10139520.23
      3702641.59      10139081.5
#Sta/Elev= 30
  4080.3  289.07  4139.9  287.38  4205.7   282.9    4244  282.21  4304.2  278.55
  4589.6  271.25  4901.9  270.26  4907.6  271.61  4940.2  272.84  4945.9  271.96
  4962.2  272.78  4984.1  271.66 4985.26270.7566  4989.8  267.22    5000  268.17
  5020.7  267.75  5025.1  266.57  5029.6  266.57  5033.1  268.28  5064.6  270.71
  5187.9  273.89  5252.4  272.64  5391.4  274.35  5428.7  276.18  5444.4  275.26
  5481.6  277.06    5495  276.27  5632.4  281.89  5685.2  282.32  5872.5  288.79
#Mann= 5 ,-1 , 0
  4080.3     .11       0 4985.26     .06       0  5064.6     .11       0
  5428.7     .17       0  5632.4     .11       0
Bank Sta=4985.26,5064.6
XS Rating Curve= 0 ,0
Exp/Cntr=0.3,0.1

Type RM Length L Ch R = 1 ,6765    ,333,333,333
BEGIN DESCRIPTION:
CCLC 044 11.0
END DESCRIPTION:
XS GIS Cut Line= 3
      3704417.83     10139661.05      3703777.47     10139046.04
      3703001.74     10138547.66
#Sta/Elev= 30
  4114.7  289.46  4164.2  288.86  4178.4  287.74  4185.3  285.51  4269.8  283.65
  4418.9  273.55  4543.8  268.77  4713.5  268.41  4807.9  268.03  4861.3  266.71
  4920.8   266.8  4928.1  264.35  4963.3  263.84  4968.2  262.33  4984.7  263.63
  5005.3   263.4  5020.5  266.67  5049.7  266.52  5062.3  267.46  5129.5  270.13
  5165.8   270.4  5251.7  268.34  5389.7  271.87    5426  271.42    5535  274.34
  5598.4  277.49  5679.6  279.03  5707.4  281.12  5774.1  283.51  5924.6  287.53
#Mann= 8 ,-1 , 0
  4114.7     .11       0  4269.8     .17       0  4543.8     .11       0
  4713.5     .17       0  4861.3     .15       0  4920.8     .06       0
  5020.5     .17       0  5062.3     .11       0
Bank Sta=4920.8,5020.5
XS Rating Curve= 0 ,0
Exp/Cntr=0.3,0.1

Type RM Length L Ch R = 1 ,6432    ,545,545,545
BEGIN DESCRIPTION:
CCLC 044 10.0
END DESCRIPTION:
XS GIS Cut Line= 3
      3704417.86     10139561.09      3704046.98     10138855.53
      3703317.84     10138461.07
#Sta/Elev= 30
  4202.9  286.65  4206.5  286.69  4233.2  286.97  4293.3  285.31  4327.2  281.34
  4442.7  273.09    4508  270.13  4618.6  266.99  4837.7  266.52  4886.7  266.02
  4965.7  265.25  4993.7   266.1  5015.7  262.44  5020.3  262.44  5023.7  264.48
  5039.8  266.09  5083.6  265.54  5158.2  266.36  5171.1  266.03  5180.9  264.09
  5185.5  265.08  5203.5  266.42  5252.9  265.55  5274.8  266.48  5341.1  266.89
  5372.8  267.81  5422.3  267.31    5526  269.57    5799  278.07    5829  279.84
#Mann= 9 ,-1 , 0
  4202.9     .11       0  4206.5     .17       0  4442.7     .11       0
  4837.7     .15       0  4886.7     .17       0  4993.7     .09       0
  5039.8     .15       0  5185.5     .17       0  5341.1     .11       0
Bank Sta=4993.7,5039.8
XS Rating Curve= 0 ,0
Exp/Cntr=0.3,0.1

Type RM Length L Ch R = 1 ,5887    ,412,412,412
BEGIN DESCRIPTION:
CCLC 044 9.0
END DESCRIPTION:
XS GIS Cut Line= 3
      3705274.86      10138859.4      3704515.32     10138612.01
      3703917.87     10138061.09
#Sta/Elev= 30
  4192.5  289.66  4432.9  282.78  4492.2  279.01  4528.6  279.51  4592.5  276.33
  4619.1  272.46  4624.4  273.27  4631.1  270.73  4645.1  268.72  4688.2   266.2
  4720.2  266.84  4904.5   264.4  4957.1  265.24  4967.6  263.38  4975.5   260.5
  4980.8  260.66    4985  258.47  4997.4  260.13  5004.2  262.79  5011.5  264.16
  5046.7  262.88  5181.1  264.23  5444.1  263.45  5520.8  264.24  5542.3   261.8
  5556.5  264.18  5605.8  263.23  5648.1  265.08  5799.5  275.19    5804  275.21
#Mann= 8 ,-1 , 0
  4192.5     .11       0  4492.2     .17       0  4645.1     .11       0
  4967.6     .06       0  5004.2     .11       0  5444.1     .15       0
  5648.1     .11       0  5799.5     .17       0
Bank Sta=4967.6,5004.2
XS Rating Curve= 0 ,0
Exp/Cntr=0.3,0.1

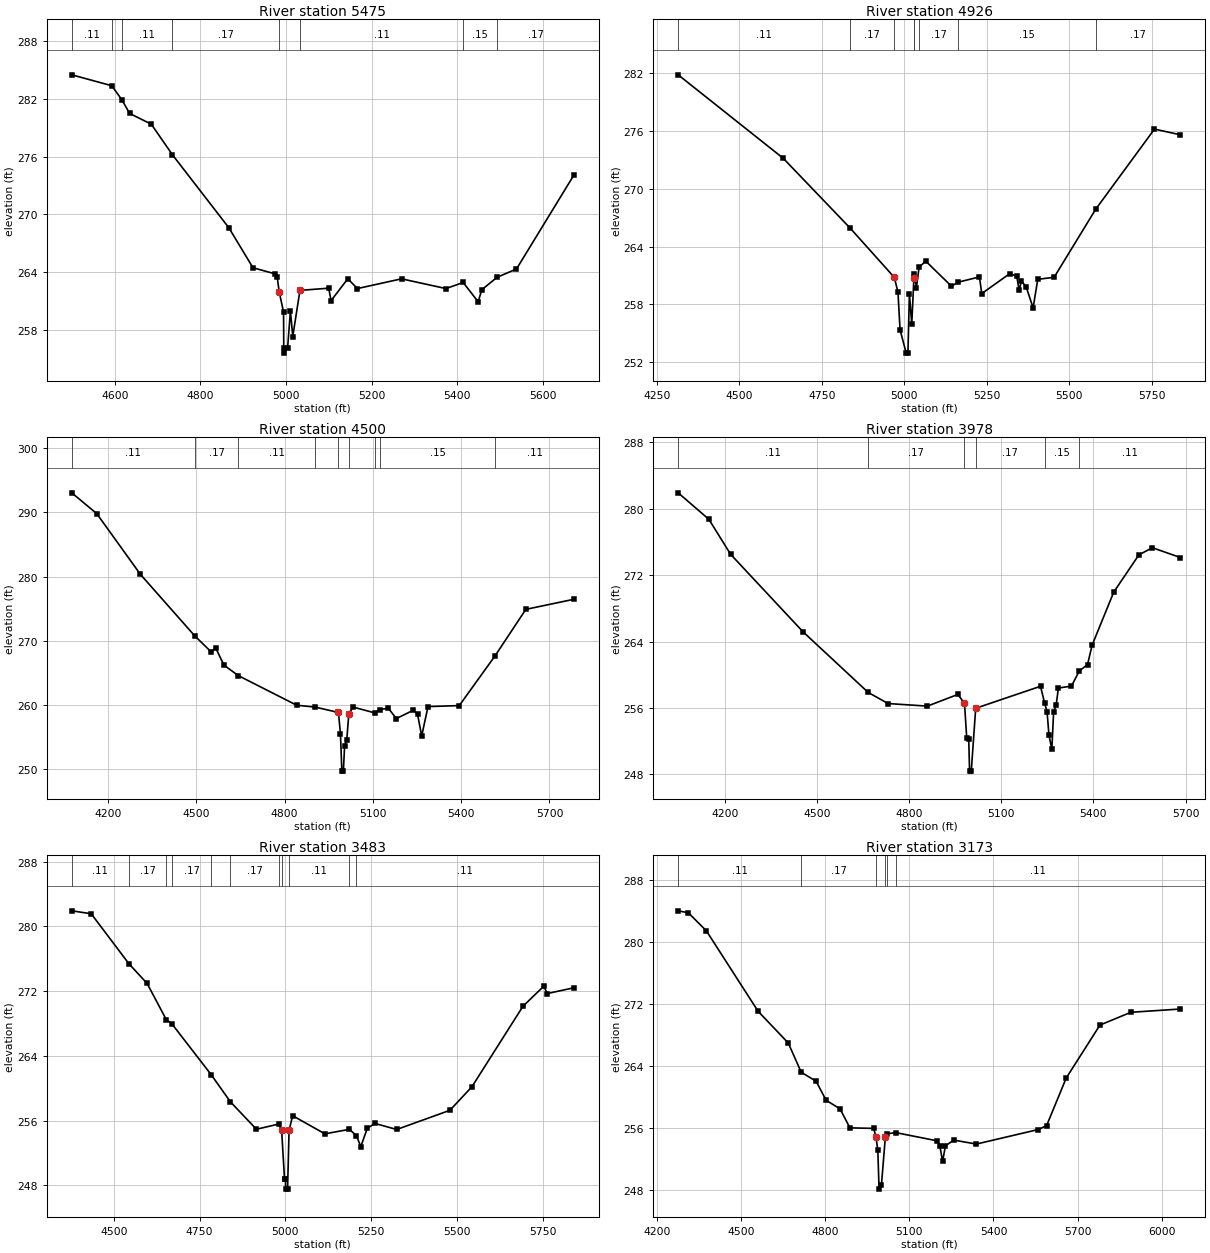
Type RM Length L Ch R = 1 ,5475    ,549,549,549
BEGIN DESCRIPTION:
CCLC 044 8.0
END DESCRIPTION:
XS GIS Cut Line= 3
      3705027.45     10138551.23      3704618.89     10138261.96
      3704017.89     10137961.09
#Sta/Elev= 30
  4499.4  284.48  4592.8  283.35  4616.5  281.88  4634.6  280.47  4685.1  279.36
  4734.2   276.2  4866.1  268.62  4922.6  264.46  4973.1  263.84  4979.2  263.47
 4983.73261.9808    4994  259.86  4994.5   256.1    4995   255.6  5003.4   256.1
    5010  259.98  5015.5  257.32  5032.3  262.11  5099.4  262.34    5105  261.05
  5144.1  263.32  5166.4   262.3  5269.6  263.31  5373.2   262.3  5413.5  262.93
  5448.5  260.93    5457  262.18  5492.7  263.47    5538  264.33  5672.1  274.08
#Mann= 8 ,-1 , 0
  4499.4     .11       0  4592.8     .17       0  4616.5     .11       0
  4734.2     .17       0 4983.73     .09       0  5032.3     .11       0
  5413.5     .15       0  5492.7     .17       0
Bank Sta=4983.73,5032.3
XS Rating Curve= 0 ,0
Exp/Cntr=0.3,0.1

Type RM Length L Ch R = 1 ,4926    ,426,426,426
BEGIN DESCRIPTION:
CCLC 044 7.0
END DESCRIPTION:
XS GIS Cut Line= 3
      3705167.21     10138554.67      3704880.77     10137940.13
      3704287.02     10137341.17
#Sta/Elev= 30
  4315.1  281.85  4633.3  273.18  4835.4  265.95    4970   260.8    4981  259.27
  4987.4  255.34  5006.1  252.93  5011.2  252.93  5015.7  259.12  5022.8  255.92
  5029.3  260.73  5029.9  261.17  5036.9  259.74    5045  261.86  5065.2  262.49
    5143  259.89  5164.2  260.31  5227.9  260.85  5234.9  259.12  5319.8  261.19
    5341  260.92  5348.1  259.47  5355.2  260.41  5369.3  259.83  5390.5  257.63
  5404.6   260.6  5454.2  260.81  5580.3  267.89  5758.2  276.21  5836.5  275.62
#Mann= 8 ,-1 , 0
  4315.1     .11       0  4835.4     .17       0    4970     .09       0
  5029.3     .12       0  5029.9     .11       0    5045     .17       0
  5164.2     .15       0  5580.3     .17       0
Bank Sta=4970,5029.3
XS Rating Curve= 0 ,0
Exp/Cntr=0.3,0.1

Type RM Length L Ch R = 1 ,4500    ,522,522,522
BEGIN DESCRIPTION:
CCLC 044 6.0
END DESCRIPTION:
XS GIS Cut Line= 3
      3705767.88      10138361.1      3705016.56     10137547.76
      3704577.21     10137141.27
#Sta/Elev= 30
  4077.3  293.04  4162.1   289.8  4310.7  280.32  4494.4  270.78  4551.7  268.21
  4565.8  268.91  4594.2  266.19  4643.2  264.55  4841.4  259.94  4904.3  259.65
  4983.2  258.81    4990  255.51  4994.8  249.67  4999.9  249.67  5004.2  253.63
  5011.5   254.5  5018.3  258.53  5032.5  259.66    5106  258.75    5124  259.27
  5152.8  259.47  5179.9  257.86  5237.7  259.16  5251.8  258.57    5266  255.15
  5287.5  259.73  5393.6  259.88  5515.8  267.67  5619.8  274.88  5783.1  276.45
#Mann= 9 ,-1 , 0
  4077.3     .11       0  4494.4     .17       0  4643.2     .11       0
  4904.3     .15       0  4983.2     .09       0  5018.3     .15       0
    5106     .17       0    5124     .15       0  5515.8     .11       0
Bank Sta=4983.2,5018.3
XS Rating Curve= 0 ,0
Exp/Cntr=0.3,0.1

Type RM Length L Ch R = 1 ,3978    ,495,495,495
BEGIN DESCRIPTION:
CCLC 044 5.0
END DESCRIPTION:
XS GIS Cut Line= 3
      3705979.75     10138039.12      3705385.83     10137295.75
      3704802.78     10136940.21
#Sta/Elev= 30
  4048.5  281.91  4148.4  278.72  4219.3   274.5  4454.6  265.18  4666.9  257.87
  4731.6  256.53  4859.7  256.22  4958.9  257.63  4980.4  256.56  4987.8  252.34
  4994.2  252.22    4997  248.39  5002.5  248.39  5016.9  255.96  5227.9  258.61
  5240.9  256.64  5249.3  255.49  5255.3  252.75  5264.7  251.01  5270.6  255.56
  5278.7   256.3    5286   258.4  5328.7  258.63  5353.8  260.44  5380.9  261.23
  5395.9  263.57  5466.2  269.95  5548.1  274.44    5592   275.3  5682.9  274.12
#Mann= 6 ,-1 , 0
  4048.5     .11       0  4666.9     .17       0  4980.4     .09       0
  5016.9     .17       0  5240.9     .15       0  5353.8     .11       0
Bank Sta=4980.4,5016.9
XS Rating Curve= 0 ,0
Exp/Cntr=0.3,0.1

Type RM Length L Ch R = 1 ,3483    ,310,310,310
BEGIN DESCRIPTION:
CCLC 044 4.0
END DESCRIPTION:
XS GIS Cut Line= 3
      3706307.87     10137398.48        3705758.     10137106.47
      3704953.73     10136862.02
#Sta/Elev= 30
  4377.4  281.93    4434  281.57  4543.6  275.41    4597  272.95    4653  268.47
  4668.5     268  4784.4  261.64  4839.6  258.33  4915.4  254.94  4981.5  255.59
  4988.8   254.9  4997.3   248.8    5000   248.8  5000.6  247.54  5006.2  247.54
  5010.6  254.83  5021.1  256.61  5115.1  254.37  5186.6  254.93    5207  254.13
  5219.6  252.79  5238.7  255.08  5261.4  255.65  5324.2  254.91  5479.3  257.28
  5543.6   260.2  5692.2  270.14  5752.7  272.61  5763.1  271.71  5840.6  272.42
#Mann= 11 ,-1 , 0
  4377.4     .11       0  4543.6     .17       0    4653     .11       0
  4668.5     .17       0  4784.4     .11       0  4839.6     .17       0
  4981.5     .11       0  4988.8     .06       0  5010.6     .11       0
  5186.6     .17       0    5207     .11       0
Bank Sta=4988.8,5010.6
XS Rating Curve= 0 ,0
Exp/Cntr=0.3,0.1

Type RM Length L Ch R = 1 ,3173    ,683,683,683
BEGIN DESCRIPTION:
CCLC 044 3.0
END DESCRIPTION:
XS GIS Cut Line= 3
      3706517.85     10137311.07      3705948.48     10136867.22
      3704881.86     10136799.58
#Sta/Elev= 30
  4275.6  284.02  4311.8  283.77    4376  281.45  4560.6  271.07  4668.2  266.98
  4714.2  263.22  4767.7  262.04    4803   259.6  4852.8  258.49  4888.1  256.04
  4973.1  255.97  4981.2  254.81  4987.6  253.13    4992  248.14  5000.4  248.64
  5014.4  254.84  5019.4  255.26    5051  255.43  5198.6  254.37  5208.6  253.74
  5218.6  251.71  5228.6  253.73  5258.7  254.46  5338.9  253.95  5559.3  255.82
  5589.4  256.32  5659.5  262.47  5779.7  269.29    5890  270.94  6066.3  271.36
#Mann= 6 ,-1 , 0
  4275.6     .11       0  4714.2     .17       0  4981.2     .09       0
  5014.4     .12       0  5019.4     .17       0    5051     .11       0
Bank Sta=4981.2,5014.4
XS Rating Curve= 0 ,0
Exp/Cntr=0.3,0.1