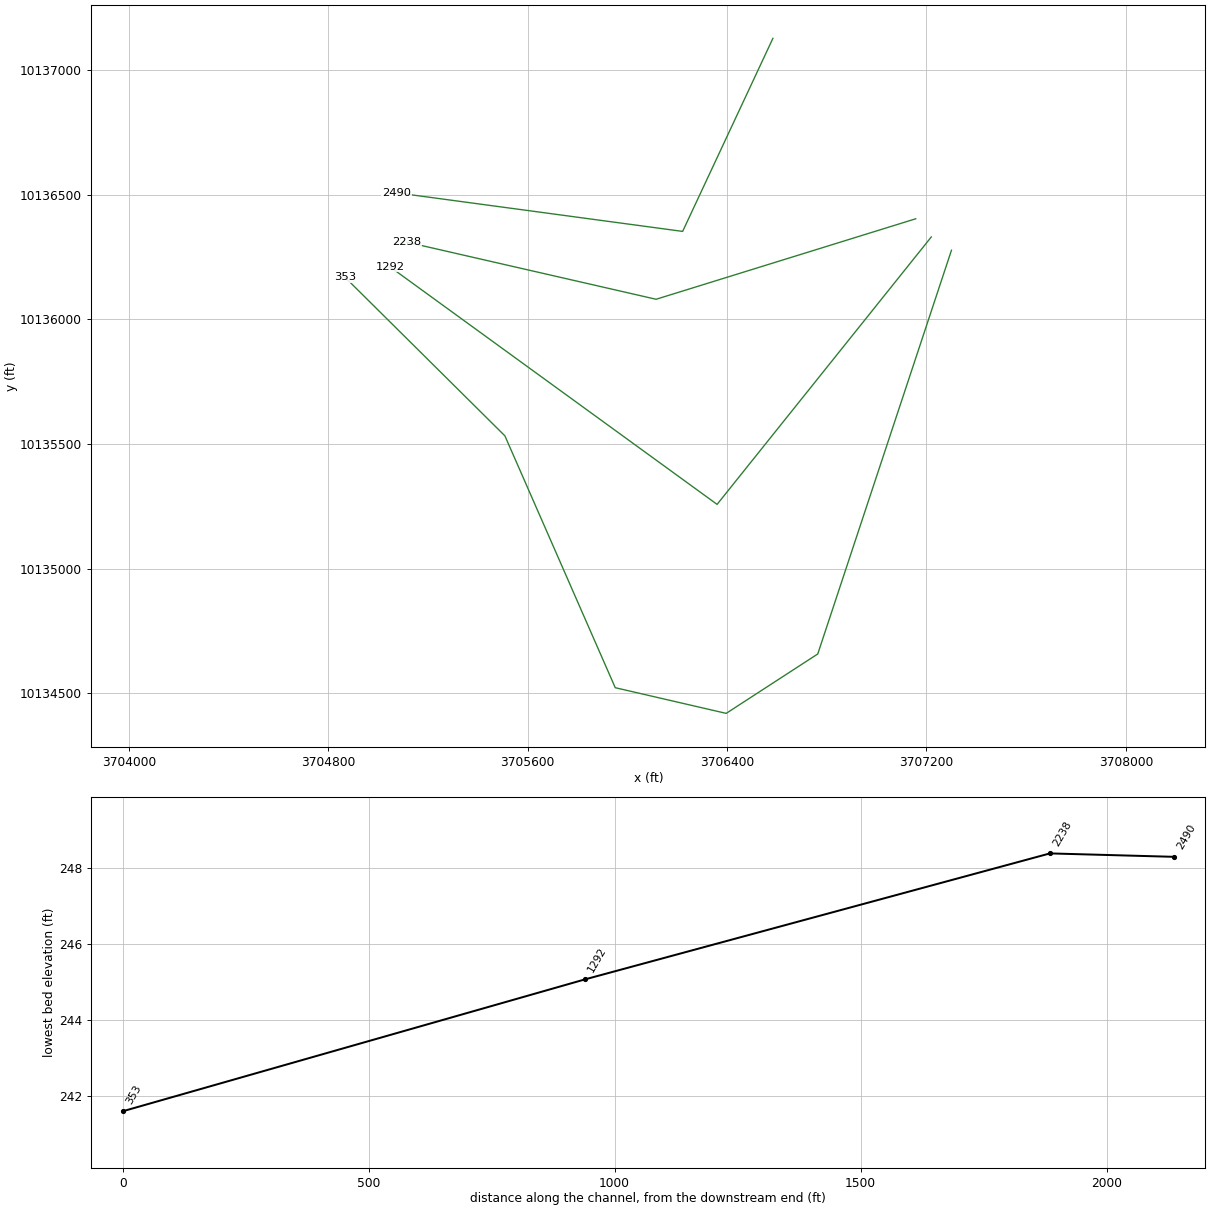
HEC-RAS study CCLC 044.prj: CCLC 044 Base Level Engineering

--- CCLC 044.g01 (geometry) --- (continued)

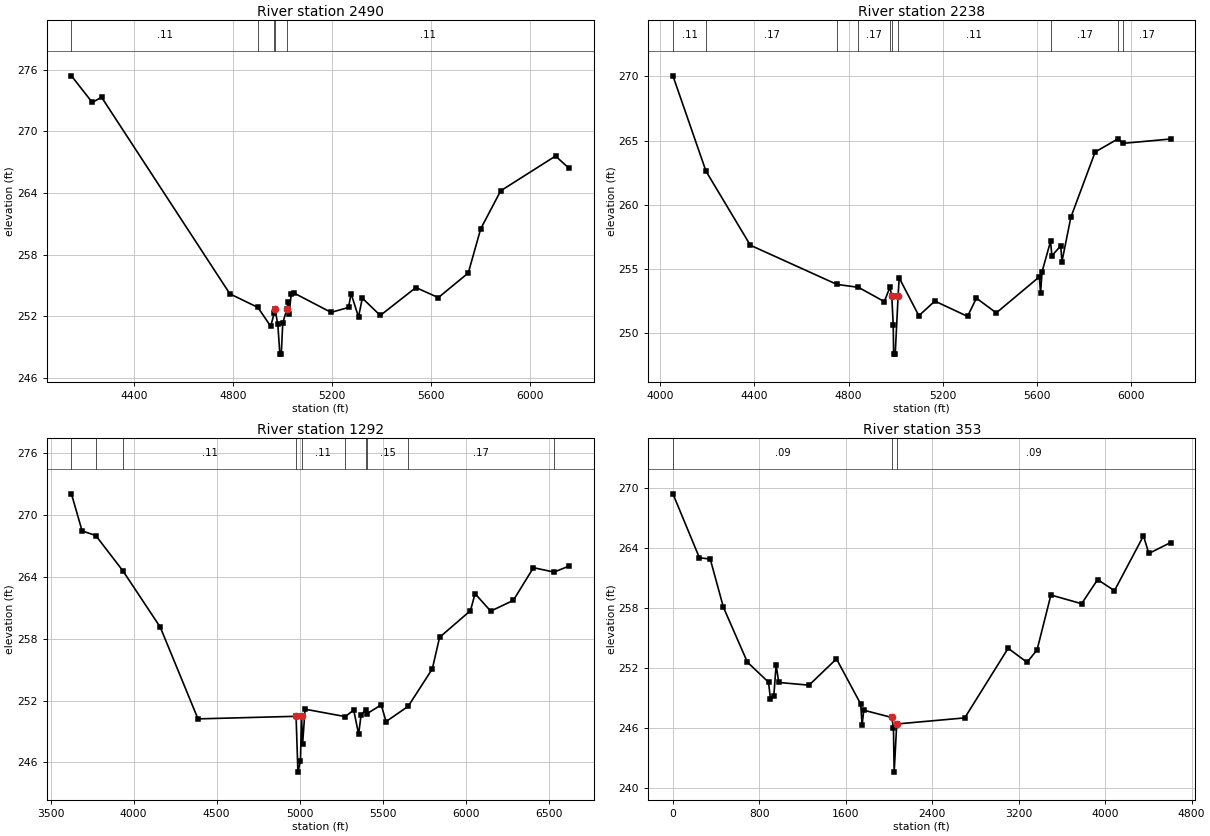
Type RM Length L Ch R = 1 ,2490    ,252,252,252
BEGIN DESCRIPTION:
CCLC 044 2.0
END DESCRIPTION:
XS GIS Cut Line= 3
       3706583.9     10137127.64       3706221.7     10136353.04
      3705073.49     10136507.84
#Sta/Elev= 30
  4144.9  275.42  4229.4  272.82  4266.7  273.34  4785.9  254.17  4899.4  252.84
  4951.3     251  4965.4   252.3  4968.6  252.67  4980.1  251.18  4988.3  248.29
    4994  248.29    5000  251.33 5016.37 252.646  5020.8  253.33  5025.9  252.24
  5034.2  254.16  5044.2  254.26  5195.6  252.36  5266.2  252.84  5276.3   254.2
  5306.6  251.91  5321.9  253.75  5394.6  252.06  5538.7  254.78  5629.5   253.8
  5750.6   256.2    5801  260.51  5881.8  264.21  6103.7   267.6  6158.6   266.4
#Mann= 5 ,-1 , 0
  4144.9     .11       0  4899.4     .17       0  4965.4     .11       0
  4968.6     .06       0 5016.37     .11       0
Bank Sta=4968.6,5016.37
XS Rating Curve= 0 ,0
Exp/Cntr=0.3,0.1

Type RM Length L Ch R = 1 ,2238    ,946,946,946
BEGIN DESCRIPTION:
Mapping XS 071b53d2
END DESCRIPTION:
XS GIS Cut Line= 3
      3707156.84     10136403.69      3706115.15     10136080.76
      3705115.17     10136309.92
#Sta/Elev= 30
  4053.2  270.05  4193.7  262.63  4382.4  256.86  4750.4  253.81  4842.4  253.58
  4952.1  252.47  4975.8  253.58  4983.9  252.93    4990  250.67  4991.9  248.38
  4998.5  248.38 5010.78252.8771  5015.3  254.32  5099.1  251.37  5167.1  252.51
  5306.1  251.32  5343.9  252.74  5428.3  251.59  5611.5   254.4  5616.7  253.13
  5623.2  254.81  5659.3  257.17  5664.7  256.04  5702.5  256.81  5707.6  255.58
  5745.4  259.03  5848.9  264.12  5946.8  265.15  5965.8  264.79  6169.7  265.13
#Mann= 10 ,-1 , 0
  4053.2     .11       0  4193.7     .17       0  4750.4     .11       0
  4842.4     .17       0  4975.8     .11       0  4983.9     .06       0
 5010.78     .11       0  5659.3     .17       0  5946.8     .11       0
  5965.8     .17       0
Bank Sta=4983.9,5010.78
XS Rating Curve= 0 ,0
Exp/Cntr=0.3,0.1

Type RM Length L Ch R = 1 ,1292    ,939,939,939
BEGIN DESCRIPTION:
CCLC 044 1.0
END DESCRIPTION:
XS GIS Cut Line= 3
      3707219.33     10136330.78      3706359.94     10135257.84
       3705047.4       10136211.
#Sta/Elev= 30
  3625.7  272.08  3689.9  268.48  3772.3  268.03  3936.2  264.59  4160.5  259.14
  4387.8  250.23  4978.4  250.48  4989.5  245.06  5004.8  246.14 5011.14250.4786
  5017.9  247.82  5032.6  251.17  5274.7  250.45  5325.6  251.09    5355  248.74
  5369.7  250.57  5397.3  251.12  5403.2  250.71    5491  251.59  5520.4  249.97
  5653.5  251.45  5798.7  255.08  5842.7  258.15  6028.7  260.74  6056.1  262.39
  6150.4  260.69  6286.4  261.73  6407.8  264.91  6531.9  264.48  6622.5  265.07
#Mann= 10 ,-1 , 0
  3625.7     .11       0  3772.3     .17       0  3936.2     .11       0
  4978.4     .06       0 5011.14     .11       0  5274.7     .17       0
  5397.3     .11       0  5403.2     .15       0  5653.5     .17       0
  6531.9     .11       0
Bank Sta=4978.4,5011.14
XS Rating Curve= 0 ,0
Exp/Cntr=0.3,0.1

Type RM Length L Ch R = 1 ,353     ,0,0,0
XS GIS Cut Line= 6
      3707300.29      10136277.5      3706763.83     10134657.71
       3706396.4      10134419.3      3705951.33     10134522.29
      3705508.62     10135532.71        3704868.     10136168.13
#Sta/Elev= 30
       0   269.4   245.1  263.01   345.4  262.88     467  258.07   688.9  252.58
   884.4  250.58   902.2  248.94   933.8  249.23   954.8   252.3   979.5  250.55
  1259.6  250.28  1513.2  252.91  1737.3   248.4  1750.6  246.29  1765.8  247.78
  2025.5  247.05  2040.6  245.99  2047.2  241.59  2070.9   246.4  2700.3  247.01
    3102  253.97  3276.7  252.56  3369.7  253.81  3497.5  259.29  3781.5  258.42
    3930  260.83  4085.5  259.72  4354.2   265.2  4403.7  263.44  4605.1  264.53
#Mann= 3 , 0 , 0
       0     .09       0  2025.5     .06       0  2070.9     .09       0
Bank Sta=2025.5,2070.9
XS Rating Curve= 0 ,0
Exp/Cntr=0.3,0.1

Chan Stop Cuts=-1
Use User Specified Reach Order=0
Composite Channel Slope=5