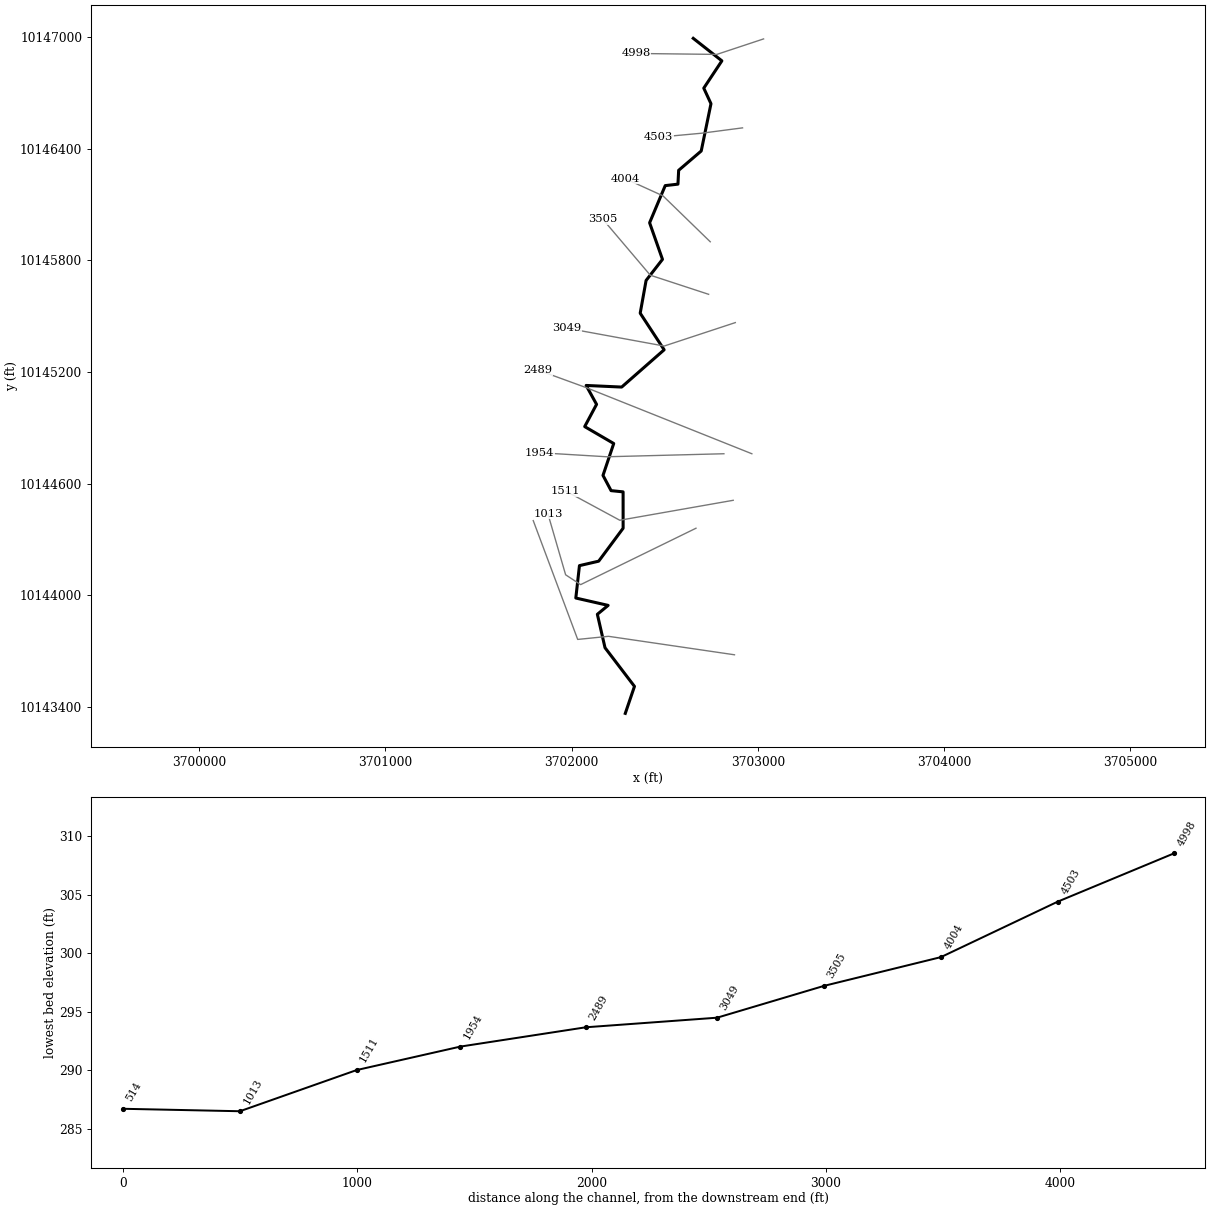
--- CCLC 045.prj (project) ---

Proj Title=CCLC 045 Base Level Engineering
Current Plan=p01
Default Exp/Contr=0.3,0.1
English Units
Geom File=g01
Flow File=f01
Flow File=f02
Plan File=p01
Y Axis Title=Elevation
X Axis Title(PF)=Main Channel Distance
X Axis Title(XS)=Station
BEGIN DESCRIPTION:
CCLC 045
END DESCRIPTION:
DSS Export Rating Curves= 0
DSS Export Rating Curve Sorted= 0
DSS Export Volume Flow Curves= 0
DXF OffsetX= 0
DXF OffsetY= 0
DXF ScaleX= 1
DXF ScaleY= 10

--- CCLC 045.p01 (plan) ---

Plan Title=Multiple Run
Short Identifier=Multiple
Geom File=g01
Flow File=f01
Subcritical Flow
K Sum by GR= 0
Std Step Tol= 0.01
Critical Tol= 0.01
Num of Std Step Trials= 20
Max Error Tol= 0.3
Flow Tol Ratio= 0.001
Split Flow NTrial= 30
Split Flow Tol= 0.02
Split Flow Ratio= 0.02
Log Output Level= 0
Friction Slope Method= 1
Unsteady Friction Slope Method= 2
Unsteady Bridges Friction Slope Method= 1
Parabolic Critical Depth
Global Vel Dist=  1 , 1 , 1
Global Log Level= 0
CheckData=True
Encroach Param= -1, 0, 0, 0
BEGIN DESCRIPTION:
Multiple Run
END DESCRIPTION:

--- CCLC 045.f01 (steady flow) ---

Flow Title=Multiple
Program Version=4.10
Number of Profiles= 7
Profile Names=10-year,25-year,50-year,1pct_min,100-year,1pct_plu,500-year
River Rch & RM=CCLC 045,Reach-1         ,4998
     449     598     797     350    1058    3195    1926
Boundary for River Rch & Prof#=CCLC 045,Reach-1         , 1
Up Type= 0
Dn Type= 3
Dn Slope=0.005
Boundary for River Rch & Prof#=CCLC 045,Reach-1         , 2
Up Type= 0
Dn Type= 3
Dn Slope=0.005
Boundary for River Rch & Prof#=CCLC 045,Reach-1         , 3
Up Type= 0
Dn Type= 3
Dn Slope=0.005
Boundary for River Rch & Prof#=CCLC 045,Reach-1         , 4
Up Type= 0
Dn Type= 3
Dn Slope=0.005
Boundary for River Rch & Prof#=CCLC 045,Reach-1         , 5
Up Type= 0
Dn Type= 3
Dn Slope=0.005
Boundary for River Rch & Prof#=CCLC 045,Reach-1         , 6
Up Type= 0
Dn Type= 3
Dn Slope=0.005
Boundary for River Rch & Prof#=CCLC 045,Reach-1         , 7
Up Type= 0
Dn Type= 3
Dn Slope=0.005
DSS Import GetInterval= 0
DSS Import GetPeak= 0
DSS Import FillOption= 0

--- CCLC 045.f02 (steady flow) ---

Flow Title=Orig_BLE_Flows
Program Version=4.10
Number of Profiles= 7
Profile Names=10-year,25-year,50-year,1pct_min,100-year,1pct_plu,500-year
River Rch & RM=CCLC 045,Reach-1         ,4998
     449     586     693     269     814    2458    1120
Boundary for River Rch & Prof#=CCLC 045,Reach-1         , 1
Up Type= 0
Dn Type= 3
Dn Slope=0.005
Boundary for River Rch & Prof#=CCLC 045,Reach-1         , 2
Up Type= 0
Dn Type= 3
Dn Slope=0.005
Boundary for River Rch & Prof#=CCLC 045,Reach-1         , 3
Up Type= 0
Dn Type= 3
Dn Slope=0.005
Boundary for River Rch & Prof#=CCLC 045,Reach-1         , 4
Up Type= 0
Dn Type= 3
Dn Slope=0.005
Boundary for River Rch & Prof#=CCLC 045,Reach-1         , 5
Up Type= 0
Dn Type= 3
Dn Slope=0.005
Boundary for River Rch & Prof#=CCLC 045,Reach-1         , 6
Up Type= 0
Dn Type= 3
Dn Slope=0.005
Boundary for River Rch & Prof#=CCLC 045,Reach-1         , 7
Up Type= 0
Dn Type= 3
Dn Slope=0.005
DSS Import GetInterval= 0
DSS Import GetPeak= 0
DSS Import FillOption= 0

--- CCLC 045.g01 (geometry) ---

Geom Title=Existing Conditions
Program Version=4.10

River Reach=CCLC 045        ,Reach-1
Reach XY= 30
      3702653.23     10146991.84      3702806.95     10146870.99
      3702709.74     10146724.38       3702748.4     10146640.86
      3702696.05     10146386.89      3702574.84     10146283.12
      3702571.07     10146208.82      3702502.75     10146200.93
      3702418.84     10146001.46      3702487.96     10145804.88
      3702399.96     10145691.62      3702368.34     10145515.82
      3702496.93     10145319.32      3702268.94     10145119.14
      3702078.01     10145127.83      3702134.01      10145026.3
      3702070.28     10144906.83      3702226.21     10144815.96
      3702168.54     10144644.79        3702212.     10144562.95
      3702276.54     10144556.36      3702276.65     10144360.99
      3702145.41     10144184.14      3702042.14     10144160.23
      3702022.59     10143986.27      3702196.18     10143946.71
      3702138.29     10143898.94      3702179.38     10143719.38
      3702337.57     10143511.83      3702288.23     10143366.84

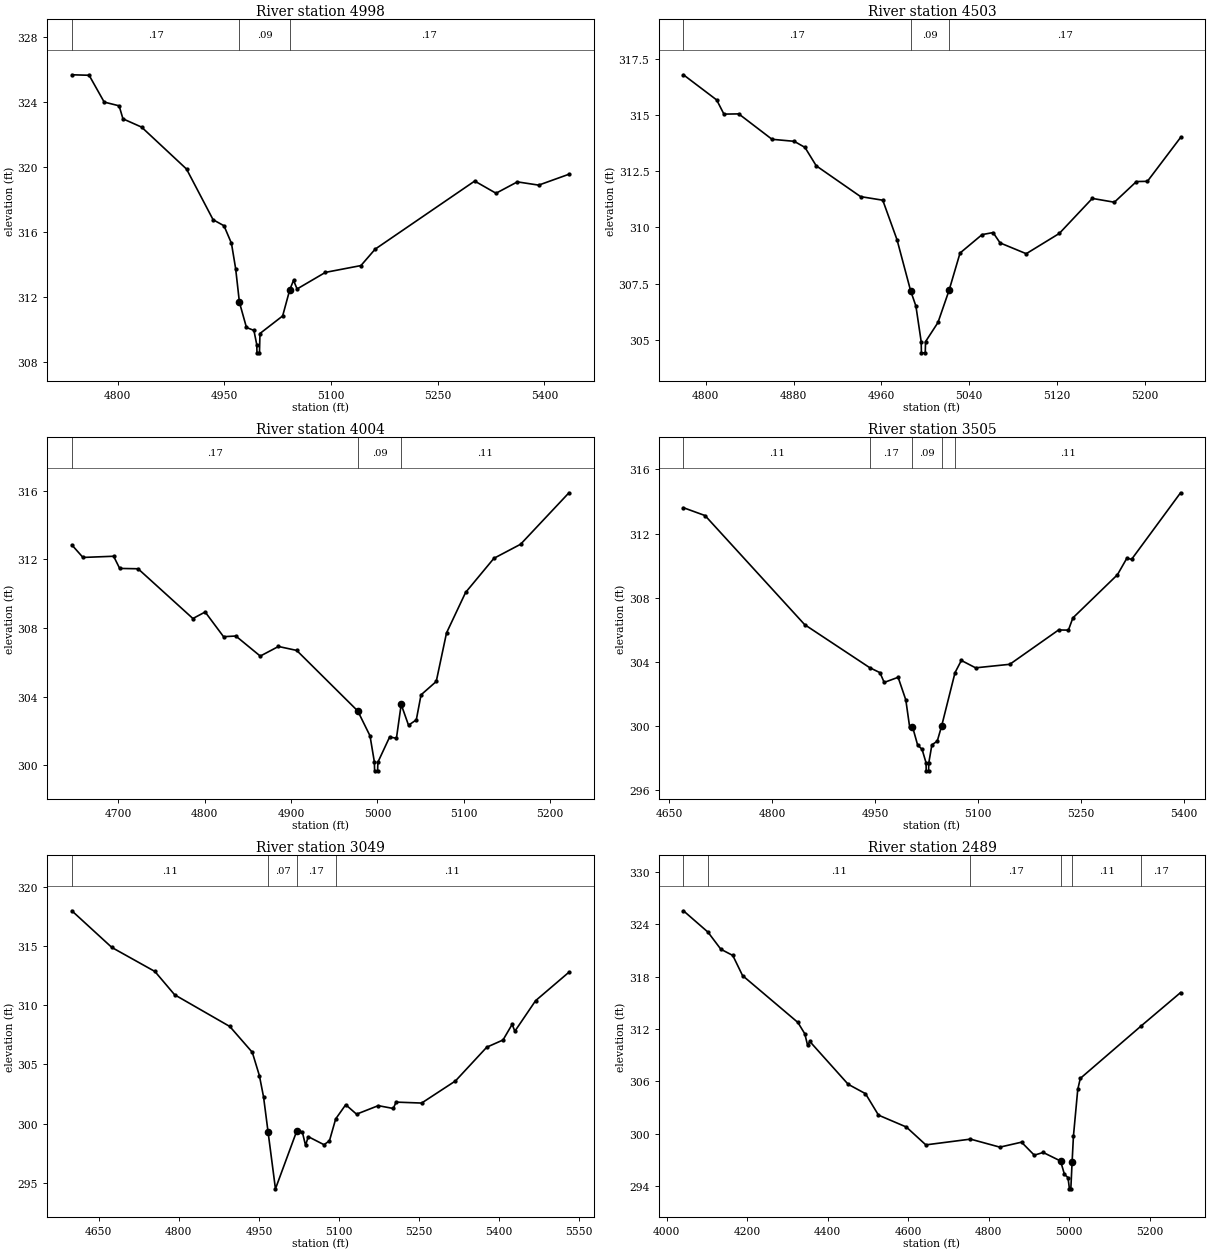
Type RM Length L Ch R = 1 ,4998    ,495,495,495
BEGIN DESCRIPTION:
CCLC 045 10.0
END DESCRIPTION:
XS GIS Cut Line= 3
      3703030.96     10146988.75       3702779.8     10146905.51
      3702345.23     10146910.62
#Sta/Elev= 30
  4735.4  325.65  4759.7  325.62  4780.9  323.97  4801.9  323.74  4807.3  322.94
  4833.5  322.43  4896.7  319.85  4934.1  316.73  4949.4  316.36  4959.9  315.28
  4965.8  313.72  4971.1  311.65    4981   310.1  4991.5  309.92  4995.5  309.04
  4995.8  308.54  4999.3  308.54    5000  309.73  5031.9  310.81  5041.9  312.42
  5047.2     313  5052.2  312.47    5092  313.49    5142  313.91    5162  314.92
    5302  319.11    5332  318.36    5362  319.06    5392  318.86  5434.6  319.53
#Mann= 3 , 0 , 0
  4735.4     .17       0  4971.1     .09       0  5041.9     .17       0
Bank Sta=4971.1,5041.9
XS Rating Curve= 0 ,0
Exp/Cntr=0.3,0.1

Type RM Length L Ch R = 1 ,4503    ,499,499,499
BEGIN DESCRIPTION:
CCLC 045 9.0
END DESCRIPTION:
XS GIS Cut Line= 3
      3702917.87     10146511.07      3702699.44     10146482.47
      3702467.82     10146461.07
#Sta/Elev= 30
  4779.7  316.79    4810  315.67  4816.6  315.04  4830.1  315.05  4860.4  313.92
  4880.6  313.83  4890.4  313.56  4900.7  312.74  4941.1  311.37  4961.3  311.21
  4974.3  309.45 4986.66307.1852  4991.5   306.5  4996.3  304.92  4996.5  304.42
    5000  304.42  5000.3  304.92  5011.6  305.77  5021.7   307.2  5031.7  308.86
  5051.8  309.68  5061.8  309.77  5068.2  309.31    5092  308.83  5122.1  309.73
  5152.2  311.29  5172.3  311.12  5192.4  312.04  5202.4  312.05  5232.6     314
#Mann= 3 , 0 , 0
  4779.7     .17       0 4986.66     .09       0  5021.7     .17       0
Bank Sta=4986.66,5021.7
XS Rating Curve= 0 ,0
Exp/Cntr=0.3,0.1

Type RM Length L Ch R = 1 ,4004    ,499,499,499
BEGIN DESCRIPTION:
CCLC 045 8.0
END DESCRIPTION:
XS GIS Cut Line= 3
      3702744.48     10145899.35      3702490.64     10146145.95
      3702288.78     10146237.87
#Sta/Elev= 30
  4646.1  312.84    4659  312.11  4694.5  312.18  4701.5  311.47  4722.8  311.45
  4786.3  308.55  4800.5  308.93  4821.8  307.49    4836  307.53  4864.3  306.36
  4885.4  306.92  4906.5  306.69  4977.2  303.16  4991.4  301.71  4996.5  300.17
  4996.7  299.67  5000.2  299.67  5000.5  300.17  5014.1  301.64    5022  301.57
  5027.5  303.54    5036  302.33    5045  302.64  5050.5   304.1  5068.1  304.88
    5080  307.71  5102.1  310.07  5134.9  312.06  5165.8  312.88  5221.8  315.88
#Mann= 3 , 0 , 0
  4646.1     .17       0  4977.2     .09       0  5027.5     .11       0
Bank Sta=4977.2,5027.5
XS Rating Curve= 0 ,0
Exp/Cntr=0.3,0.1

Type RM Length L Ch R = 1 ,3505    ,456,456,456
BEGIN DESCRIPTION:
CCLC 045 7.0
END DESCRIPTION:
XS GIS Cut Line= 3
      3702735.77     10145617.23      3702422.47      10145719.9
      3702167.25     10146020.85
#Sta/Elev= 30
  4670.3  313.61  4701.8  313.12    4847  306.32  4941.7  303.64  4956.6  303.33
  4962.8  302.72  4983.1  303.04  4994.3  301.63  4999.8  299.97    5004  299.97
  5011.5  298.82    5018  298.55  5023.8  297.71    5024  297.21  5027.5  297.21
  5027.8  297.71  5032.3  298.83  5040.1  299.06  5046.6  300.02    5066  303.33
  5075.2  304.09    5096  303.63  5145.8  303.85  5216.9  305.99  5231.2  305.98
  5237.7  306.74  5302.6  309.43  5316.2  310.45  5323.4   310.4  5394.6  314.54
#Mann= 5 ,-1 , 0
  4670.3     .11       0  4941.7     .17       0    5004     .09       0
  5046.6     .17       0    5066     .11       0
Bank Sta=5004,5046.6
XS Rating Curve= 0 ,0
Exp/Cntr=0.3,0.1

Type RM Length L Ch R = 1 ,3049    ,560,560,560
BEGIN DESCRIPTION:
CCLC 045 6.0
END DESCRIPTION:
XS GIS Cut Line= 3
      3702879.08     10145465.32      3702497.09     10145339.44
      3701976.27     10145434.92
#Sta/Elev= 30
  4599.4  317.99  4674.4  314.89  4755.1  312.86  4792.1  310.89  4895.5  308.21
  4937.6  306.03  4950.9  304.06  4958.7  302.26 4967.21299.2838    4981  294.49
  5021.2  299.41  5031.3  299.31  5037.4  298.16  5042.5   298.9    5072  298.22
  5082.2  298.55  5093.9   300.4  5112.7   301.6    5133   300.8  5173.7  301.52
  5201.9  301.28    5207  301.82    5255  301.74  5318.4  303.61    5377  306.46
  5407.5  307.07  5424.6  308.39  5429.7  307.81  5468.5  310.39  5531.1   312.8
#Mann= 4 ,-1 , 0
  4599.4     .11       0 4967.21     .07       0  5021.2     .17       0
  5093.9     .11       0
Bank Sta=4967.21,5021.2
XS Rating Curve= 0 ,0
Exp/Cntr=0.3,0.1

Type RM Length L Ch R = 1 ,2489    ,535,535,535
BEGIN DESCRIPTION:
CCLC 045 5.0
END DESCRIPTION:
XS GIS Cut Line= 3
      3702967.89     10144761.06      3702084.76     10145113.75
       3701817.9     10145211.05
#Sta/Elev= 30
  4041.5  325.55  4102.3  323.11  4134.5  321.14  4164.1  320.43  4188.4  318.12
  4325.8  312.75    4343  311.45    4350  310.12  4355.4  310.57  4450.7  305.66
  4493.8  304.58  4526.1  302.12  4595.2  300.76  4643.7  298.71  4754.6  299.37
  4827.6  298.45  4881.4  299.02  4913.1  297.53  4935.3  297.84  4978.4  296.86
  4988.1  295.32  4996.9  294.96  5000.4  293.67  5003.9  293.67  5007.1  296.77
  5010.4  299.72  5021.1  305.06  5027.4  306.33  5179.2  312.37  5276.5  316.17
#Mann= 6 ,-1 , 0
  4041.5     .17       0  4102.3     .11       0  4754.6     .17       0
  4978.4     .09       0  5007.1     .11       0  5179.2     .17       0
Bank Sta=4978.4,5007.1
XS Rating Curve= 0 ,0
Exp/Cntr=0.3,0.1

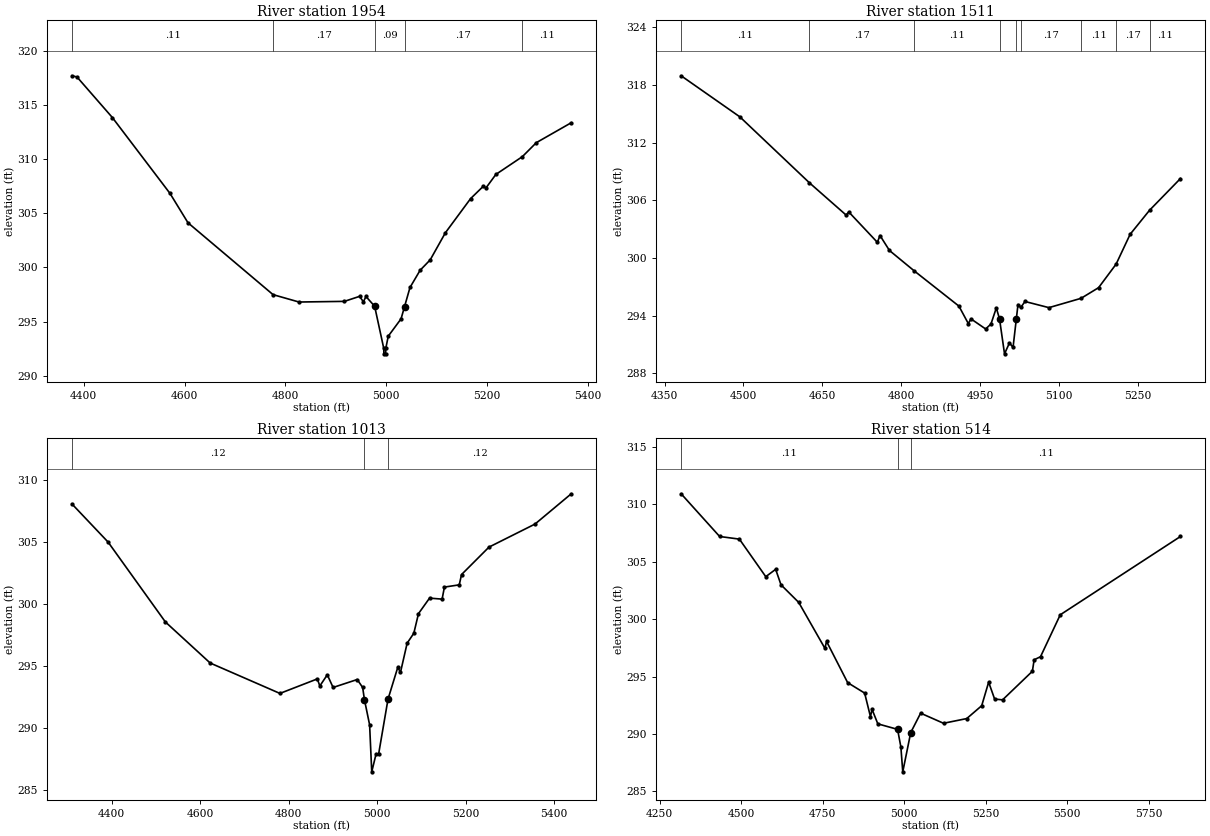
Type RM Length L Ch R = 1 ,1954    ,443,443,443
BEGIN DESCRIPTION:
CCLC 045 4.0
END DESCRIPTION:
XS GIS Cut Line= 3
       3702817.9     10144761.07      3702188.93     10144744.82
      3701828.66     10144766.52
#Sta/Elev= 30
  4376.8  317.67  4386.8  317.56  4456.9  313.82  4571.2  306.82  4606.9  304.11
  4775.6  297.48    4827   296.8    4917  296.86    4947  297.32  4954.8  296.82
  4959.8  297.31    4977  296.41  4995.1  292.52  4995.3  292.02  4998.8  292.02
  4999.1  292.52    5004  293.65  5029.4  295.25 5036.35296.3848  5047.1  298.14
  5067.2  299.73  5087.2  300.69  5117.3  303.19  5167.3  306.34  5192.7  307.49
  5197.7  307.32  5217.4  308.57  5269.9  310.21  5297.6   311.5  5366.9  313.34
#Mann= 5 ,-1 , 0
  4376.8     .11       0  4775.6     .17       0    4977     .09       0
 5036.35     .17       0  5269.9     .11       0
Bank Sta=4977,5036.35
XS Rating Curve= 0 ,0
Exp/Cntr=0.3,0.1

Type RM Length L Ch R = 1 ,1511    ,498,498,498
BEGIN DESCRIPTION:
CCLC 045 3.0
END DESCRIPTION:
XS GIS Cut Line= 3
      3702867.89     10144511.08      3702258.74     10144403.94
      3701967.86     10144561.07
#Sta/Elev= 30
  4381.5  318.96  4493.2  314.68  4625.5  307.81  4695.1  304.46  4700.2  304.78
  4754.5  301.62  4759.5  302.33  4777.5  300.77  4824.5  298.65  4909.5  294.98
  4927.4  293.16  4932.4  293.65  4960.3   292.6  4970.4  293.11  4980.6  294.79
  4986.7  293.65  4996.2  290.01  5005.6  291.15  5012.4  290.68  5018.6293.6218
  5021.8  295.14  5027.1  294.84  5035.1  295.46  5080.6  294.82  5141.7  295.79
    5175   296.9  5208.3  299.35    5235  302.46  5271.9  304.96  5330.6  308.26
#Mann= 9 ,-1 , 0
  4381.5     .11       0  4625.5     .17       0  4824.5     .11       0
  4986.7     .07       0  5018.6     .11       0  5027.1     .17       0
  5141.7     .11       0  5208.3     .17       0  5271.9     .11       0
Bank Sta=4986.7,5018.6
XS Rating Curve= 0 ,0
Exp/Cntr=0.3,0.1

Type RM Length L Ch R = 1 ,1013    ,499,499,499
BEGIN DESCRIPTION:
CCLC 045 2.0
END DESCRIPTION:
XS GIS Cut Line= 4
      3702667.87     10144361.08      3702048.36     10144058.17
      3701967.85     10144111.07      3701872.47     10144439.68
#Sta/Elev= 30
  4310.4  308.08    4392  305.01  4521.5  298.57  4622.7  295.26  4780.3  292.81
  4864.8  293.98  4870.4  293.41  4887.3  294.31  4900.4  293.29  4954.9  293.93
  4967.2  293.29 4971.19292.3121  4982.9  290.28  4987.7  286.49  4997.5  287.93
  5003.3  287.93  5024.5  292.35  5046.6  294.92  5052.6   294.5  5067.7  296.86
  5082.8  297.66  5093.3  299.24  5118.3  300.49  5146.7  300.41  5151.9  301.38
  5185.4  301.56  5190.6  302.39  5252.5   304.6  5356.6  306.46  5438.5   308.9
#Mann= 3 , 0 , 0
  4310.4     .12       0 4971.19     .07       0  5024.5     .12       0
Bank Sta=4971.19,5024.5
XS Rating Curve= 0 ,0
Exp/Cntr=0.3,0.1

Type RM Length L Ch R = 1 ,514     ,0,0,0
BEGIN DESCRIPTION:
CCLC 045 1.0
END DESCRIPTION:
XS GIS Cut Line= 4
      3702874.66     10143681.46      3702197.89     10143780.69
      3702032.68     10143763.92      3701793.96     10144401.96
#Sta/Elev= 30
    4316  310.92  4434.1   307.2  4494.7  306.97  4575.6   303.7  4605.9  304.34
  4622.3  302.99  4676.6  301.46  4756.9  297.46    4762  298.06  4826.7  294.47
  4878.8  293.56  4896.6  291.51  4901.6  292.14  4919.2  290.88  4979.8   290.4
  4989.9  288.87  4995.7   286.7  5020.1  290.12  5050.5  291.81  5120.7  290.93
  5191.9  291.34  5237.8  292.46  5259.1  294.51  5277.4  293.04  5301.8  292.97
  5393.2  295.46  5398.6  296.46  5418.2  296.73  5478.7  300.38  5847.3   307.2
#Mann= 3 , 0 , 0
    4316     .11       0  4979.8     .07       0  5020.1     .11       0
Bank Sta=4979.8,5020.1
XS Rating Curve= 0 ,0
Exp/Cntr=0.3,0.1

Chan Stop Cuts=-1
Use User Specified Reach Order=0
Composite Channel Slope=5