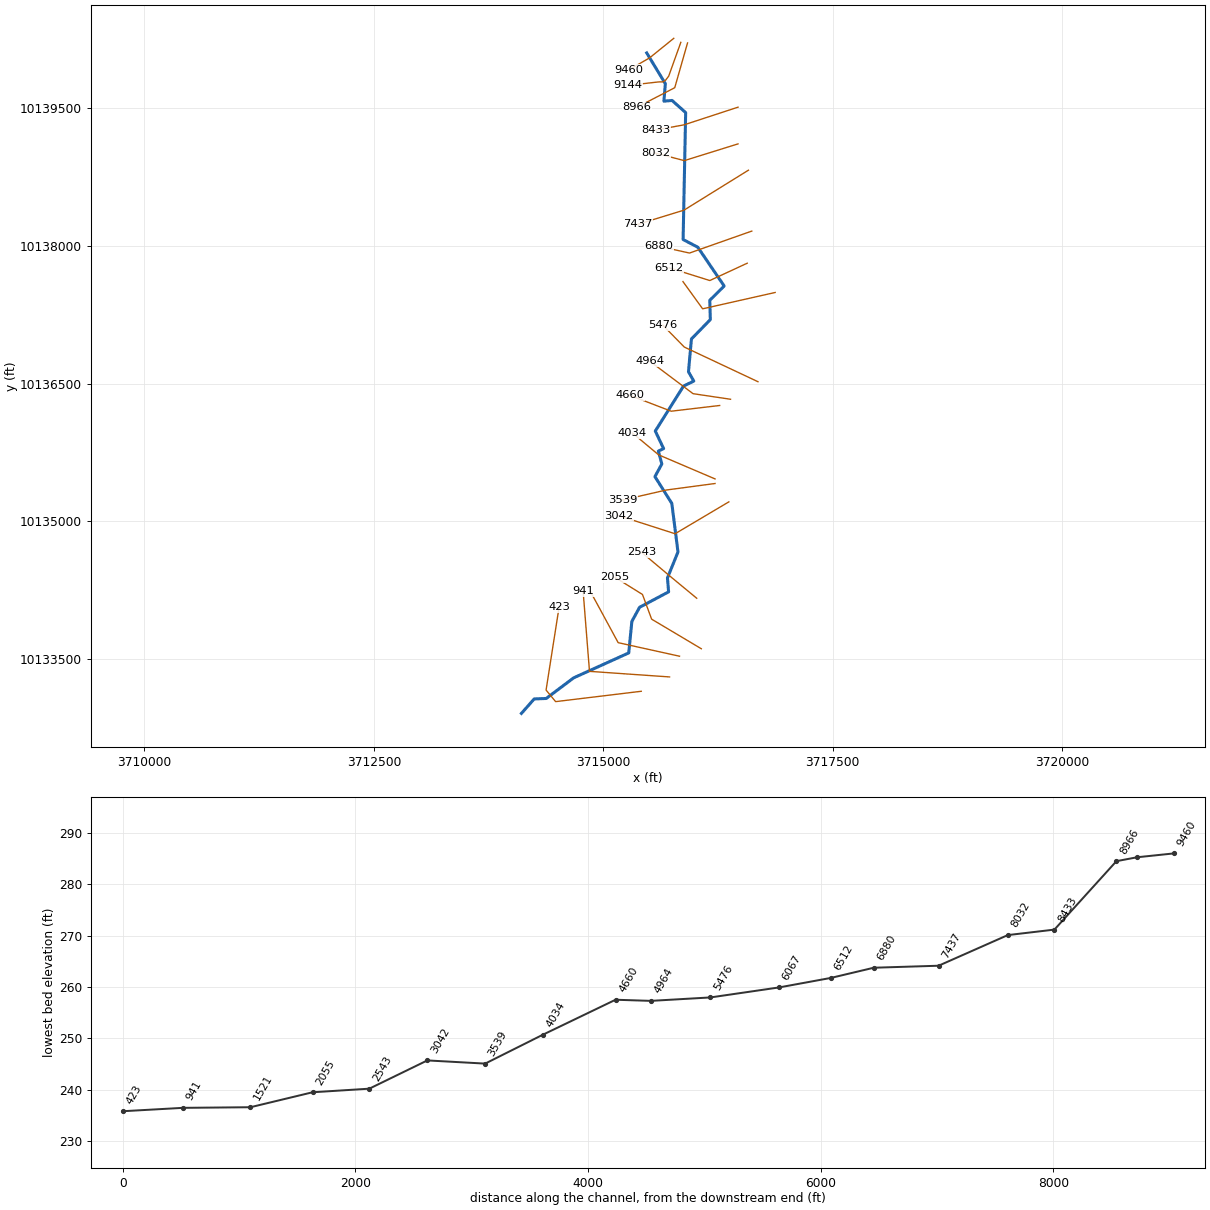
--- CCLC 047.prj (project) ---

Proj Title=CCLC 047 Base Level Engineering
Current Plan=p01
Default Exp/Contr=0.3,0.1
English Units
Geom File=g01
Flow File=f01
Flow File=f02
Plan File=p01
Y Axis Title=Elevation
X Axis Title(PF)=Main Channel Distance
X Axis Title(XS)=Station
BEGIN DESCRIPTION:
CCLC 047
END DESCRIPTION:
DSS Export Rating Curves= 0
DSS Export Rating Curve Sorted= 0
DSS Export Volume Flow Curves= 0
DXF OffsetX= 0
DXF OffsetY= 0
DXF ScaleX= 1
DXF ScaleY= 10

--- CCLC 047.p01 (plan) ---

Plan Title=Multiple Run
Short Identifier=Multiple
Geom File=g01
Flow File=f01
Subcritical Flow
K Sum by GR= 0
Std Step Tol= 0.01
Critical Tol= 0.01
Num of Std Step Trials= 20
Max Error Tol= 0.3
Flow Tol Ratio= 0.001
Split Flow NTrial= 30
Split Flow Tol= 0.02
Split Flow Ratio= 0.02
Log Output Level= 0
Friction Slope Method= 1
Unsteady Friction Slope Method= 2
Unsteady Bridges Friction Slope Method= 1
Parabolic Critical Depth
Global Vel Dist=  1 , 1 , 1
Global Log Level= 0
CheckData=True
Encroach Param= -1, 0, 0, 0
BEGIN DESCRIPTION:
Multiple Run
END DESCRIPTION:

--- CCLC 047.f01 (steady flow) ---

Flow Title=Multiple
Program Version=4.10
Number of Profiles= 7
Profile Names=10-year,25-year,50-year,1pct_min,100-year,1pct_plu,500-year
River Rch & RM=CCLC 047,Reach-1         ,9460
     684     934    1270     568    1715    5179    3232
Boundary for River Rch & Prof#=CCLC 047,Reach-1         , 1
Up Type= 0
Dn Type= 3
Dn Slope=0.005
Boundary for River Rch & Prof#=CCLC 047,Reach-1         , 2
Up Type= 0
Dn Type= 3
Dn Slope=0.005
Boundary for River Rch & Prof#=CCLC 047,Reach-1         , 3
Up Type= 0
Dn Type= 3
Dn Slope=0.005
Boundary for River Rch & Prof#=CCLC 047,Reach-1         , 4
Up Type= 0
Dn Type= 3
Dn Slope=0.005
Boundary for River Rch & Prof#=CCLC 047,Reach-1         , 5
Up Type= 0
Dn Type= 3
Dn Slope=0.005
Boundary for River Rch & Prof#=CCLC 047,Reach-1         , 6
Up Type= 0
Dn Type= 3
Dn Slope=0.005
Boundary for River Rch & Prof#=CCLC 047,Reach-1         , 7
Up Type= 0
Dn Type= 3
Dn Slope=0.005
DSS Import GetInterval= 0
DSS Import GetPeak= 0
DSS Import FillOption= 0

--- CCLC 047.f02 (steady flow) ---

Flow Title=Orig_BLE_Flows
Program Version=4.10
Number of Profiles= 7
Profile Names=10-year,25-year,50-year,1pct_min,100-year,1pct_plu,500-year
River Rch & RM=CCLC 047,Reach-1         ,9460
     684     916    1104     437    1319    3983    1879
Boundary for River Rch & Prof#=CCLC 047,Reach-1         , 1
Up Type= 0
Dn Type= 3
Dn Slope=0.005
Boundary for River Rch & Prof#=CCLC 047,Reach-1         , 2
Up Type= 0
Dn Type= 3
Dn Slope=0.005
Boundary for River Rch & Prof#=CCLC 047,Reach-1         , 3
Up Type= 0
Dn Type= 3
Dn Slope=0.005
Boundary for River Rch & Prof#=CCLC 047,Reach-1         , 4
Up Type= 0
Dn Type= 3
Dn Slope=0.005
Boundary for River Rch & Prof#=CCLC 047,Reach-1         , 5
Up Type= 0
Dn Type= 3
Dn Slope=0.005
Boundary for River Rch & Prof#=CCLC 047,Reach-1         , 6
Up Type= 0
Dn Type= 3
Dn Slope=0.005
Boundary for River Rch & Prof#=CCLC 047,Reach-1         , 7
Up Type= 0
Dn Type= 3
Dn Slope=0.005
DSS Import GetInterval= 0
DSS Import GetPeak= 0
DSS Import FillOption= 0

--- CCLC 047.g01 (geometry) ---

Geom Title=Existing Conditions
Program Version=4.10

River Reach=CCLC 047        ,Reach-1
Reach XY= 30
      3715473.23     10140101.84      3715676.08     10139766.67
       3715660.3     10139576.48      3715748.89     10139584.32
      3715897.38     10139451.86       3715869.6     10138069.22
      3716029.49     10137985.53      3716316.98     10137562.66
      3716160.27     10137406.98      3716166.05     10137196.83
      3715960.12     10136985.32      3715928.06     10136628.85
      3715985.92     10136526.92      3715873.98     10136472.37
       3715566.5     10135982.67      3715657.27     10135791.32
      3715599.62     10135764.33      3715637.85     10135623.69
      3715562.53     10135486.17      3715746.68      10135194.3
      3715813.66     10134664.97      3715699.02     10134382.72
      3715711.64     10134230.65       3715395.5     10134062.74
      3715311.21     10133908.38      3715277.19     10133565.45
      3714677.49     10133294.07      3714378.23     10133069.13
      3714247.27      10133064.2      3714108.23     10132906.84

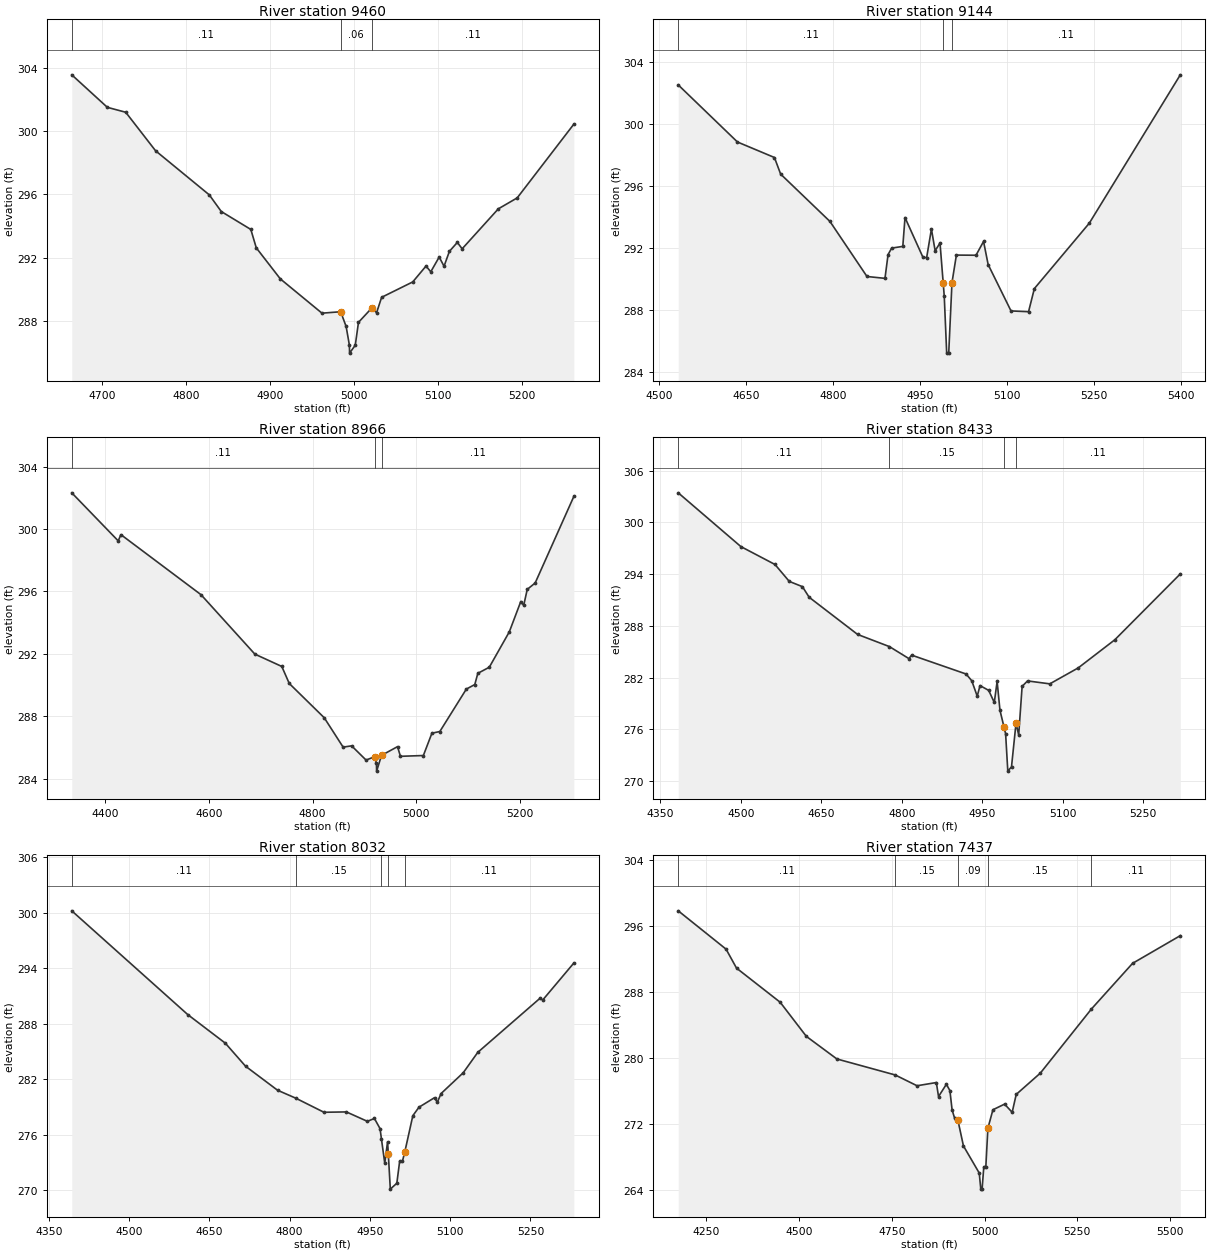
Type RM Length L Ch R = 1 ,9460    ,316,316,316
BEGIN DESCRIPTION:
CCLC 047 19.0
END DESCRIPTION:
XS GIS Cut Line= 3
      3715767.83     10140261.06      3715505.08     10140048.64
      3715279.42     10139918.45
#Sta/Elev= 30
  4663.5  303.54  4705.9  301.49  4727.8  301.18  4763.4  298.75  4827.4  295.97
  4841.7  294.92  4876.9  293.79  4883.4  292.63  4912.1  290.67  4961.7  288.51
    4984   288.6  4990.5  287.67  4994.4  286.49  4994.6  285.99  5001.4  286.49
  5005.2  287.93    5021  288.83  5026.8  288.54  5032.8  289.51  5069.9  290.48
  5085.7  291.48  5091.4  291.12  5101.4  292.05  5107.2  291.47  5113.6  292.41
    5123  292.97  5128.8  292.57  5171.9  295.09  5194.4  295.78  5261.9  300.43
#Mann= 3 , 0 , 0
  4663.5     .11       0    4984     .06       0    5021     .11       0
Bank Sta=4984,5021
XS Rating Curve= 0 ,0
Exp/Cntr=0.3,0.1

Type RM Length L Ch R = 1 ,9144    ,178,178,178
BEGIN DESCRIPTION:
Mapping XS 9a9934da
END DESCRIPTION:
XS GIS Cut Line= 6
       3715844.5     10140217.08      3715712.54     10139848.99
      3715677.82     10139803.85      3715650.04     10139786.49
       3715604.9     10139786.49      3715268.14      10139748.3
#Sta/Elev= 30
  4533.6  302.53  4635.6  298.85  4699.3  297.85    4710  296.78  4794.9  293.73
  4858.7  290.18  4889.7  290.06    4895  291.59  4901.2  292.01  4920.4  292.12
  4924.2  293.98  4955.2  291.41  4961.5   291.4  4969.7  293.24  4976.1  291.84
  4984.5  292.34 4989.95289.7791  4991.8  288.91    4996  285.24  4999.5  285.24
  5005.1  289.78  5012.7  291.56  5046.5  291.55  5059.5  292.44  5067.4  290.95
  5106.8  287.96    5137  287.91    5147   289.4  5241.7  293.62  5398.4  303.18
#Mann= 3 , 0 , 0
  4533.6     .11       0 4989.95     .06       0  5005.1     .11       0
Bank Sta=4989.95,5005.1
XS Rating Curve= 0 ,0
Exp/Cntr=0.3,0.1

Type RM Length L Ch R = 1 ,8966    ,533,533,533
BEGIN DESCRIPTION:
CCLC 047 18.0
END DESCRIPTION:
XS GIS Cut Line= 3
      3715917.85     10140211.07      3715778.51     10139723.12
      3715367.88     10139511.09
#Sta/Elev= 30
  4335.1  302.32  4424.8  299.24    4430  299.64  4584.7  295.79  4688.7  291.98
  4740.7  291.19  4755.1   290.1  4822.7   287.9  4859.1  286.02  4875.6   286.1
  4903.4  285.19  4919.9   285.4  4923.5  284.98  4923.8  284.48  4933.3  285.49
  4964.2  286.05  4969.8  285.43  5014.1  285.48  5030.6  286.91  5045.9  287.02
  5097.1  289.74  5113.4  290.03  5119.3  290.75  5141.4  291.14  5180.1  293.41
  5202.2  295.35  5207.9  295.11  5214.7  296.13    5230  296.54  5304.7  302.09
#Mann= 3 , 0 , 0
  4335.1     .11       0  4919.9     .06       0  4933.3     .11       0
Bank Sta=4919.9,4933.3
XS Rating Curve= 0 ,0
Exp/Cntr=0.3,0.1

Type RM Length L Ch R = 1 ,8433    ,401,401,401
BEGIN DESCRIPTION:
CCLC 047 17.0
END DESCRIPTION:
XS GIS Cut Line= 3
      3716467.87     10139511.08       3715881.7     10139319.11
      3715567.82     10139261.07
#Sta/Elev= 30
  4383.2  303.43  4499.9   297.2  4563.6  295.12  4590.2  293.16  4614.7  292.55
  4627.3  291.32  4717.6  287.01  4776.9   285.6  4813.2  284.21  4818.4  284.61
  4919.9  282.42  4930.4  281.64  4940.6  279.85  4945.8  281.08    4962  280.52
  4972.4  279.12  4977.7  281.56    4983  278.21  4990.5  276.28  4993.5  275.51
  4997.6  271.16  5004.5  271.66  5012.9  276.71  5017.9  275.37  5024.3  280.99
  5034.4  281.62  5075.9  281.28  5128.9  283.13  5197.1  286.39  5319.2  294.03
#Mann= 4 ,-1 , 0
  4383.2     .11       0  4776.9     .15       0  4990.5     .06       0
  5012.9     .11       0
Bank Sta=4990.5,5012.9
XS Rating Curve= 0 ,0
Exp/Cntr=0.3,0.1

Type RM Length L Ch R = 1 ,8032    ,595,595,595
BEGIN DESCRIPTION:
CCLC 047 16.0
END DESCRIPTION:
XS GIS Cut Line= 3
      3716467.86     10139111.07      3715882.68     10138928.85
      3715567.83     10139011.08
#Sta/Elev= 30
  4392.9  300.22  4609.6  288.99  4679.9  285.89  4717.6   283.4  4777.4   280.8
  4811.4  279.94  4864.2  278.41  4906.1  278.45  4945.3  277.43  4958.5  277.74
    4969  276.64  4971.6  275.54  4977.8   272.9  4983.1  275.22 4984.47  273.91
  4988.2  270.09  5000.4  270.73  5005.7  273.12  5010.9  273.12 5015.22   274.1
  5030.3  278.04  5041.8  278.96  5070.8  279.99    5076  279.49  5083.1  280.44
  5124.5  282.69  5151.7   284.9  5267.9  290.75  5273.1  290.57  5331.2  294.57
#Mann= 5 ,-1 , 0
  4392.9     .11       0  4811.4     .15       0  4971.6     .11       0
 4984.47     .06       0 5015.22     .11       0
Bank Sta=4984.47,5015.22
XS Rating Curve= 0 ,0
Exp/Cntr=0.3,0.1

Type RM Length L Ch R = 1 ,7437    ,557,557,557
BEGIN DESCRIPTION:
CCLC 047 15.0
END DESCRIPTION:
XS GIS Cut Line= 3
      3716581.45     10138824.67      3715879.48     10138389.34
      3715374.83     10138234.39
#Sta/Elev= 30
    4174  297.89    4303  293.24  4331.2  290.94  4448.9   286.8  4519.5  282.66
  4601.8  279.92    4759  277.98    4818  276.67    4870  277.06  4875.9  275.36
  4897.1  276.85  4906.6  276.08  4912.5  273.74  4919.5   272.7  4927.9  272.54
  4943.1  269.37  4985.7  266.08  4989.9  264.13  4993.4  264.13    4998  266.85
  5003.5  266.85    5009  271.51  5022.6  273.76    5054  274.44  5074.5  273.45
  5085.4  275.62  5150.4   278.2  5288.2  285.98  5399.2  291.52  5527.9  294.88
#Mann= 5 ,-1 , 0
    4174     .11       0    4759     .15       0  4927.9     .09       0
    5009     .15       0  5288.2     .11       0
Bank Sta=4927.9,5009
XS Rating Curve= 0 ,0
Exp/Cntr=0.3,0.1

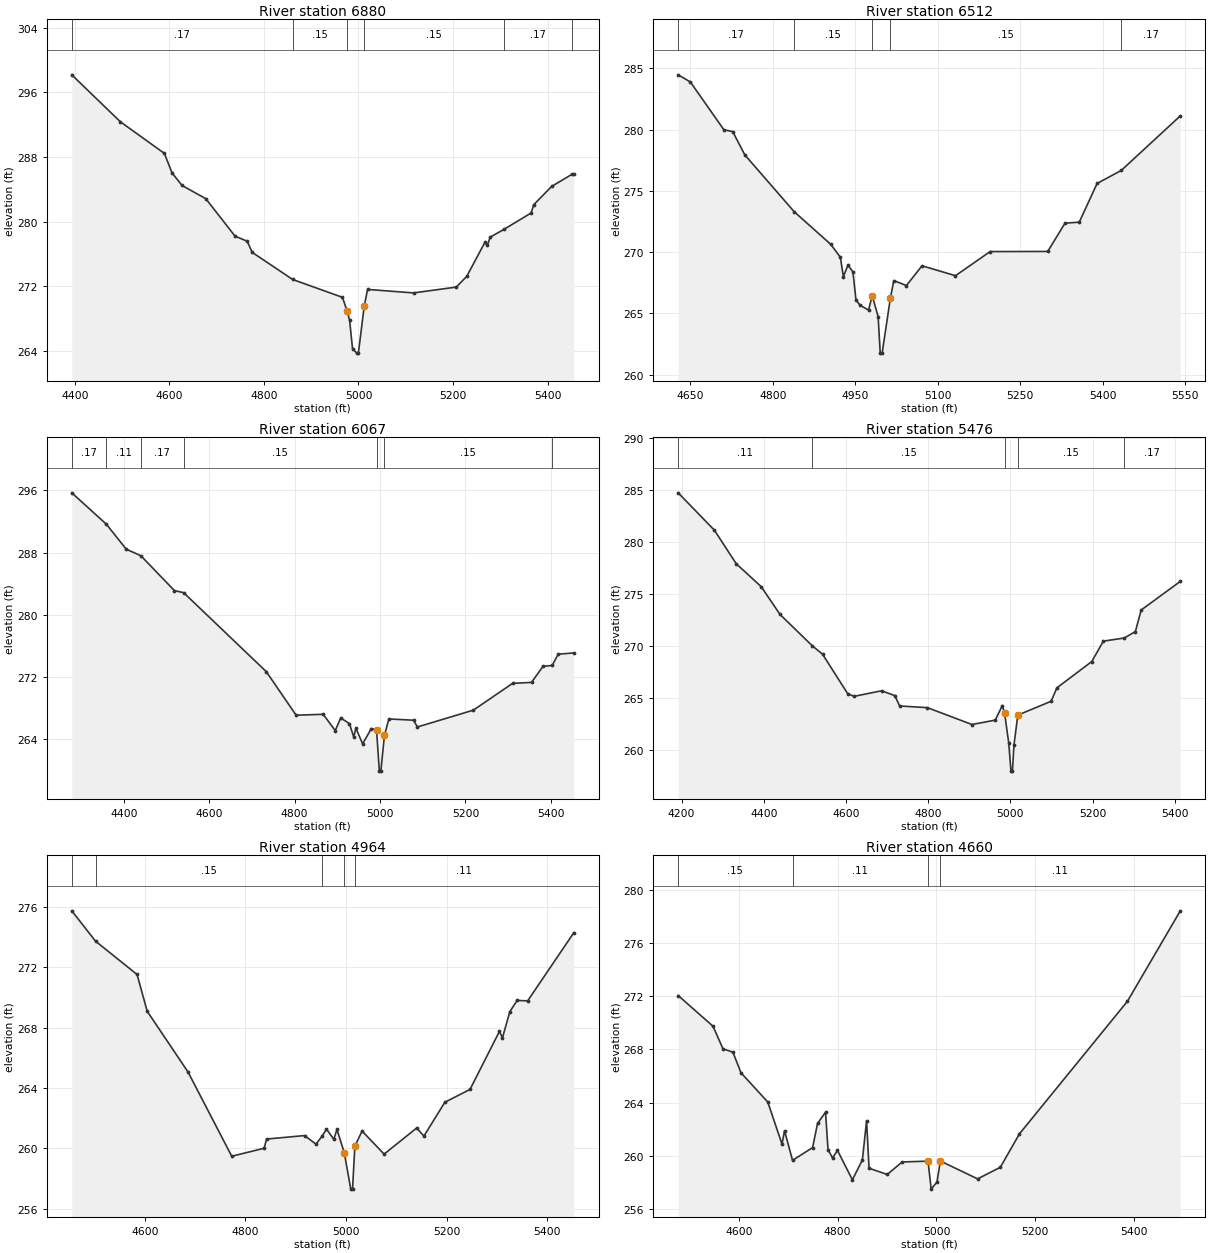
Type RM Length L Ch R = 1 ,6880    ,368,368,368
BEGIN DESCRIPTION:
CCLC 047 14.0
END DESCRIPTION:
XS GIS Cut Line= 3
      3716617.84     10138161.07      3715939.11      10137921.9
      3715604.89     10137995.69
#Sta/Elev= 30
  4393.7  298.17  4496.7  292.35  4589.6  288.45  4605.7  286.04  4626.9  284.48
  4677.1  282.85    4739  278.21  4764.6  277.59  4775.4   276.2  4860.9  272.85
  4966.2  270.64    4976  268.94  4981.3   267.8  4987.4   264.3  4996.3  263.74
  4999.8  263.74  5012.2  269.56  5019.2  271.62  5116.5  271.19  5206.8  271.91
  5228.9  273.23  5267.5  277.46  5272.6  277.07  5278.5  278.09  5307.4  279.04
  5365.1  281.08  5370.6   282.1  5408.7  284.37  5452.2  285.89  5455.6  285.89
#Mann= 6 ,-1 , 0
  4393.7     .17       0  4860.9     .15       0    4976     .09       0
  5012.2     .15       0  5307.4     .17       0  5452.2     .11       0
Bank Sta=4976,5012.2
XS Rating Curve= 0 ,0
Exp/Cntr=0.3,0.1

Type RM Length L Ch R = 1 ,6512    ,445,445,445
BEGIN DESCRIPTION:
CCLC 047 13.0
END DESCRIPTION:
XS GIS Cut Line= 3
      3716567.87     10137811.08      3716160.46     10137622.43
      3715717.83     10137761.08
#Sta/Elev= 30
    4628  284.48  4650.1   283.9    4711     280  4727.2  279.84  4749.2  277.94
    4839   273.3  4905.4  270.64  4922.8  269.59  4928.3  268.01  4936.6  268.94
  4945.7  268.39  4951.2  266.11  4958.6  265.67  4974.1  265.27  4980.7  266.45
  4991.5  264.74  4995.3  261.76  4998.8  261.76  5013.7  266.24    5020  267.68
  5042.9  267.28  5071.3  268.89  5132.1  268.08    5195  270.05  5299.8  270.06
  5331.2  272.37  5357.1  272.45  5389.5  275.61  5433.6  276.68  5540.8  281.13
#Mann= 5 ,-1 , 0
    4628     .17       0    4839     .15       0  4980.7     .09       0
  5013.7     .15       0  5433.6     .17       0
Bank Sta=4980.7,5013.7
XS Rating Curve= 0 ,0
Exp/Cntr=0.3,0.1

Type RM Length L Ch R = 1 ,6067    ,591,591,591
BEGIN DESCRIPTION:
CCLC 047 12.0
END DESCRIPTION:
XS GIS Cut Line= 3
      3716872.29     10137492.22      3716082.33     10137314.27
      3715867.88     10137611.04
#Sta/Elev= 30
  4278.2   295.7  4359.1  291.67  4405.8  288.45    4440  287.61  4518.5  283.13
  4540.2  282.86  4733.8   272.7  4803.6   267.1    4867  267.22  4895.2  265.12
    4908  266.75  4928.5  266.02  4938.4  264.31  4943.6  265.43  4959.3  263.42
  4979.8  265.39  4991.9  265.21  4998.5  259.91    5002  259.91  5010.5  264.54
  5020.8  266.62  5078.5  266.46  5087.7  265.59  5218.6  267.75  5310.6   271.2
  5354.8  271.32  5381.8  273.39  5403.2   273.5  5417.4  274.95  5454.1  275.11
#Mann= 7 ,-1 , 0
  4278.2     .17       0  4359.1     .11       0    4440     .17       0
  4540.2     .15       0  4991.9     .09       0  5010.5     .15       0
  5403.2     .17       0
Bank Sta=4991.9,5010.5
XS Rating Curve= 0 ,0
Exp/Cntr=0.3,0.1

Type RM Length L Ch R = 1 ,5476    ,512,512,512
BEGIN DESCRIPTION:
CCLC 047 11.0
END DESCRIPTION:
XS GIS Cut Line= 3
      3716685.62       10136520.      3715882.68      10136897.6
       3715648.4     10137136.22
#Sta/Elev= 30
  4191.9   284.7    4280  281.11  4333.1  277.89    4394  275.68  4439.6  273.02
  4518.5  269.99  4543.1   269.2  4604.7  265.38  4620.4  265.15  4686.7  265.68
  4718.7  265.22  4730.9  264.22  4798.2  264.06  4906.7  262.44  4963.3  262.86
  4980.6  264.26  4986.1  263.52  4996.1  260.69  5001.6  257.96  5005.1  257.96
  5008.9  260.47  5018.2  263.34  5099.2  264.67  5113.3  265.96  5198.2  268.49
  5226.4  270.45  5277.3  270.75  5304.3  271.37  5318.4  273.44  5413.6  276.19
#Mann= 5 ,-1 , 0
  4191.9     .11       0  4518.5     .15       0  4986.1     .09       0
  5018.2     .15       0  5277.3     .17       0
Bank Sta=4986.1,5018.2
XS Rating Curve= 0 ,0
Exp/Cntr=0.3,0.1

Type RM Length L Ch R = 1 ,4964    ,304,304,304
BEGIN DESCRIPTION:
CCLC 047 10.0
END DESCRIPTION:
XS GIS Cut Line= 3
       3716386.2     10136329.02      3715978.17     10136389.79
      3715509.39     10136741.37
#Sta/Elev= 30
  4454.6  275.74  4501.8  273.73  4584.4  271.52  4604.6  269.08  4685.5  265.07
  4772.7  259.47    4837     260    4842  260.61  4917.5  260.84  4940.3  260.27
  4952.9  260.83  4961.1  261.27  4975.7  260.59  4981.9  261.25  4996.5   259.7
  5009.4  257.29  5012.9  257.29  5017.5  260.14  5031.9  261.14  5075.7  259.61
  5140.3  261.34  5154.9  260.81  5196.5  263.05  5246.5   263.9  5304.9  267.74
  5311.1  267.33  5325.7  269.06  5340.3   269.8  5361.1  269.77  5453.1   274.3
#Mann= 5 ,-1 , 0
  4454.6     .11       0  4501.8     .15       0  4952.9     .11       0
  4996.5     .06       0  5017.5     .11       0
Bank Sta=4996.5,5017.5
XS Rating Curve= 0 ,0
Exp/Cntr=0.3,0.1

Type RM Length L Ch R = 1 ,4660    ,626,626,626
BEGIN DESCRIPTION:
CCLC 047 9.0
END DESCRIPTION:
XS GIS Cut Line= 3
      3716267.86     10136261.07      3715739.45     10136198.81
      3715288.05     10136372.43
#Sta/Elev= 30
  4477.5  272.05    4548  269.74  4568.1  268.05  4588.3  267.79  4604.5  266.25
  4658.8  264.05  4687.5  260.89  4692.6   261.9  4708.8  259.67  4749.4  260.63
  4759.4  262.44  4775.6  263.29  4780.6  260.48  4789.7  259.85  4799.7  260.42
  4829.9  258.21  4850.1   259.7  4858.6  262.65  4863.6  259.08  4900.4  258.61
  4930.6  259.55 4982.87259.6115  4989.3  257.51  5001.1  258.05 5007.82259.6213
  5083.2  258.28  5129.1  259.15  5167.8  261.66  5386.3  271.62  5493.2  278.41
#Mann= 4 ,-1 , 0
  4477.5     .15       0  4708.8     .11       0 4982.87     .06       0
 5007.82     .11       0
Bank Sta=4982.87,5007.82
XS Rating Curve= 0 ,0
Exp/Cntr=0.3,0.1

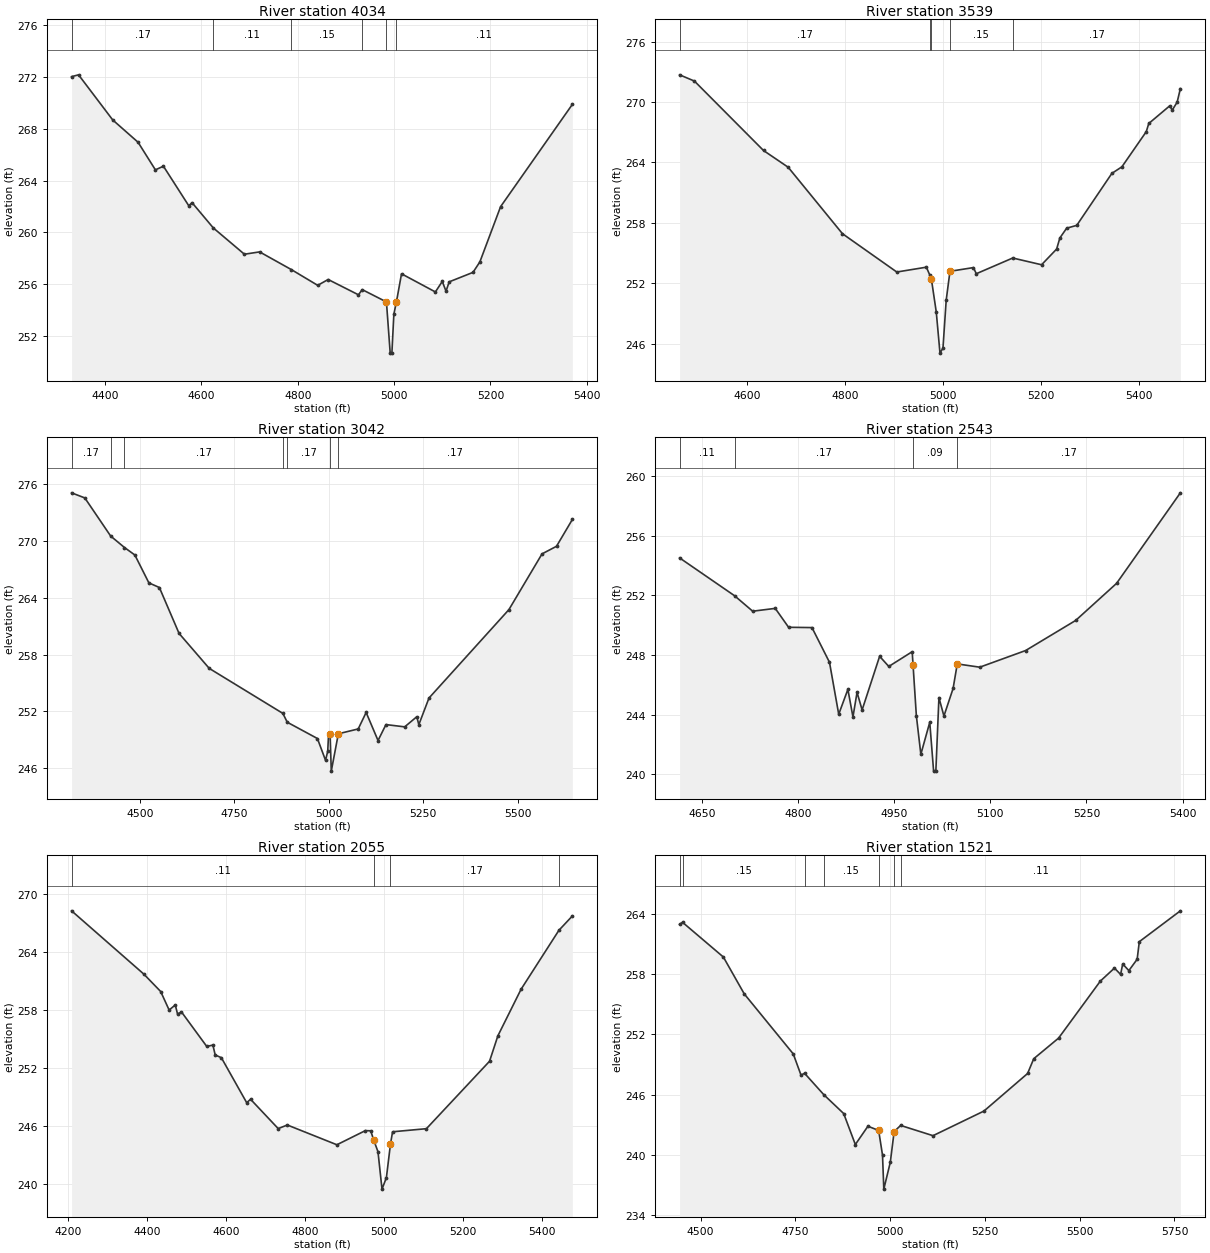
Type RM Length L Ch R = 1 ,4034    ,495,495,495
BEGIN DESCRIPTION:
CCLC 047 8.0
END DESCRIPTION:
XS GIS Cut Line= 3
      3716217.85     10135461.07      3715602.07     10135723.86
      3715317.86     10135961.07
#Sta/Elev= 30
  4330.5  272.02    4345  272.16  4415.9  268.68  4468.5  266.96  4504.5  264.83
  4521.2  265.11  4573.8  262.06  4580.6   262.3  4624.7  260.35  4689.3  258.32
  4720.9   258.5    4787  257.13  4841.5  255.92  4863.2  256.37  4926.1  255.19
  4933.9  255.59  4984.2  254.64    4992  250.69  4995.5  250.69  4999.6   253.7
 5004.95254.6445  5015.5  256.81  5085.8  255.41  5100.1  256.22  5107.9  255.47
  5114.5  256.19  5163.9  256.92  5178.2  257.73  5221.2  261.99  5370.2  269.88
#Mann= 6 ,-1 , 0
  4330.5     .17       0  4624.7     .11       0    4787     .15       0
  4933.9     .11       0  4984.2     .06       0 5004.95     .11       0
Bank Sta=4984.2,5004.95
XS Rating Curve= 0 ,0
Exp/Cntr=0.3,0.1

Type RM Length L Ch R = 1 ,3539    ,497,497,497
BEGIN DESCRIPTION:
CCLC 047 7.0
END DESCRIPTION:
XS GIS Cut Line= 3
      3716217.84     10135411.07      3715684.27     10135339.87
      3715211.38     10135231.26
#Sta/Elev= 30
  4461.7   272.7    4492  272.08  4633.2  265.19  4683.6  263.53  4794.6  256.93
  4905.6  253.13  4966.1  253.61  4973.2  252.81  4976.2  252.47  4986.3  249.16
  4993.9  245.08    5000  245.58  5006.6  250.34  5014.3   253.2  5062.3  253.57
  5068.1  252.96  5142.6  254.52  5201.5  253.85  5232.3  255.41  5238.9  256.51
  5252.8  257.48  5273.4  257.76  5345.2  262.92  5365.7  263.57  5415.5  267.06
  5420.6  267.87  5463.4  269.62  5468.6   269.2  5478.6  269.99  5485.2  271.33
#Mann= 5 ,-1 , 0
  4461.7     .17       0  4973.2     .15       0  4976.2     .09       0
  5014.3     .15       0  5142.6     .17       0
Bank Sta=4976.2,5014.3
XS Rating Curve= 0 ,0
Exp/Cntr=0.3,0.1

Type RM Length L Ch R = 1 ,3042    ,499,499,499
BEGIN DESCRIPTION:
CCLC 047 6.0
END DESCRIPTION:
XS GIS Cut Line= 3
      3716367.86     10135211.08      3715782.17     10134863.82
      3715167.86     10135061.07
#Sta/Elev= 30
  4319.1  275.06  4354.2  274.52  4422.6   270.5  4459.2  269.29  4486.7   268.5
  4523.8  265.56  4551.6  265.07  4603.7  260.23  4683.6  256.54  4878.6  251.79
  4890.2  250.86  4970.1  249.14  4991.6  246.84  4997.4   247.8  4999.6   249.6
  5003.7   249.6  5006.8   245.7  5025.5  249.64  5078.1  250.15  5099.1  251.89
  5130.6  248.93  5151.6  250.61  5201.2  250.37  5233.3  251.44  5238.6   250.6
  5265.5  253.41  5477.2  262.74  5564.9  268.62  5603.2  269.42  5645.2  272.25
#Mann= 7 ,-1 , 0
  4319.1     .17       0  4422.6     .11       0  4459.2     .17       0
  4878.6     .11       0  4890.2     .17       0  5003.7     .09       0
  5025.5     .17       0
Bank Sta=5003.7,5025.5
XS Rating Curve= 0 ,0
Exp/Cntr=0.3,0.1

Type RM Length L Ch R = 1 ,2543    ,488,488,488
BEGIN DESCRIPTION:
CCLC 047 5.0
END DESCRIPTION:
XS GIS Cut Line= 3
      3716017.88     10134161.05      3715721.48     10134406.12
      3715417.83     10134661.09
#Sta/Elev= 30
  4615.4  254.52  4701.1  251.98  4729.4  250.94  4764.6  251.13  4785.4  249.86
  4821.9  249.84  4849.2  247.51  4863.6  244.02  4877.9  245.69  4885.8  243.84
  4892.2  245.49  4900.1  244.31  4927.4  247.91  4941.7  247.23  4978.2  248.22
 4979.51247.3537  4984.7  243.92  4991.7  241.33  5005.6  243.48  5011.6   240.2
  5015.1   240.2  5019.9  245.14  5027.7   243.9    5042  245.75  5048.5   247.4
  5083.6  247.18  5155.2   248.3  5233.2  250.32    5297  252.81  5396.5  258.89
#Mann= 4 ,-1 , 0
  4615.4     .11       0  4701.1     .17       0 4979.51     .09       0
  5048.5     .17       0
Bank Sta=4979.51,5048.5
XS Rating Curve= 0 ,0
Exp/Cntr=0.3,0.1

Type RM Length L Ch R = 1 ,2055    ,534,534,534
BEGIN DESCRIPTION:
CCLC 047 4.0
END DESCRIPTION:
XS GIS Cut Line= 4
      3716067.85     10133611.07      3715526.78     10133933.19
      3715426.95     10134202.29      3715127.47     10134388.92
#Sta/Elev= 30
  4208.2  268.23  4391.3   261.7  4434.1   259.9  4455.5  257.99  4471.1  258.51
  4476.9  257.57  4486.7   257.8  4550.9  254.23  4566.5  254.37  4572.3  253.35
  4587.9  253.07  4652.2  248.42  4661.9  248.78    4732  245.75  4755.2  246.12
  4880.8  244.08    4953  245.54  4966.6  245.52  4974.3  244.55    4985  243.36
  4995.2   239.5  5006.3  240.68  5016.7  244.16    5022  245.42  5107.8  245.74
  5267.8   252.7    5289  255.33  5347.7  260.13  5443.7  266.22  5477.8   267.7
#Mann= 4 ,-1 , 0
  4208.2     .11       0  4974.3     .09       0  5016.7     .17       0
  5443.7     .11       0
Bank Sta=4974.3,5016.7
XS Rating Curve= 0 ,0
Exp/Cntr=0.3,0.1

Type RM Length L Ch R = 1 ,1521    ,580,580,580
BEGIN DESCRIPTION:
CCLC 047 3.0
END DESCRIPTION:
XS GIS Cut Line= 3
      3715830.59     10133529.55       3715162.2     10133677.11
      3714858.62     10134236.56
#Sta/Elev= 30
  4444.6  262.94  4452.3  263.15  4560.1  259.69  4615.2  256.02  4744.4  250.05
  4764.9  247.94  4774.3  248.12    4825  245.99  4877.5  244.11  4908.2  241.03
  4941.4  242.85  4969.7  242.43  4979.9  239.97  4983.3  236.59  5000.4  239.26
  5010.6  242.32  5027.7  242.93  5113.1  241.91  5247.4  244.36  5362.6   248.1
  5378.8  249.57  5444.3  251.62  5554.6   257.3  5591.7  258.59  5607.9  257.96
  5613.5     259  5629.7  258.34  5651.6  259.47  5657.3  261.22  5765.6  264.29
#Mann= 7 ,-1 , 0
  4444.6     .11       0  4452.3     .15       0  4774.3     .11       0
    4825     .15       0  4969.7     .09       0  5010.6     .15       0
  5027.7     .11       0
Bank Sta=4969.7,5010.6
XS Rating Curve= 0 ,0
Exp/Cntr=0.3,0.1

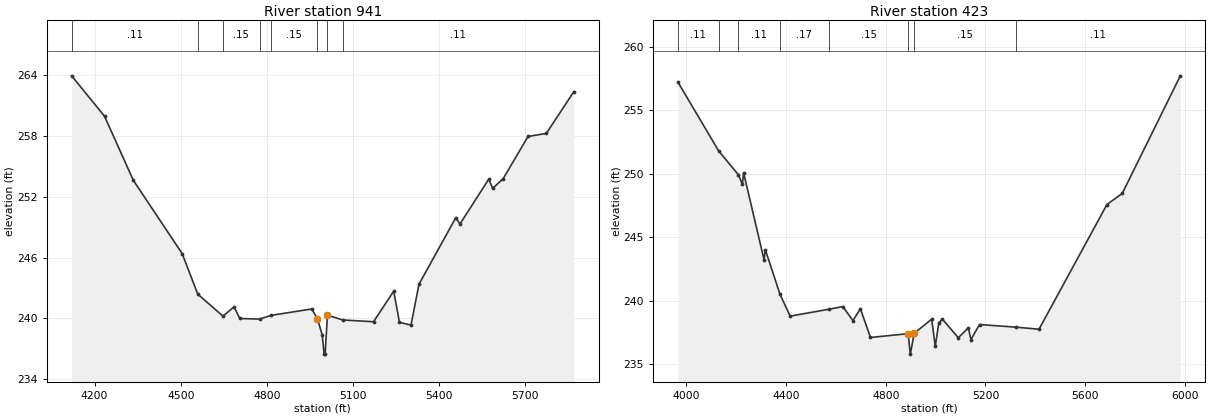
Type RM Length L Ch R = 1 ,941     ,518,518,518
BEGIN DESCRIPTION:
CCLC 047 2.0
END DESCRIPTION:
XS GIS Cut Line= 3
      3715722.11     10133303.85       3714849.7     10133364.61
      3714780.29     10134236.53
#Sta/Elev= 30
  4120.1  263.96  4234.6  259.97  4334.9  253.64  4505.3  246.39  4559.2   242.4
  4647.2  240.22  4685.7  241.14  4705.8  239.99    4775  239.93    4815   240.3
  4956.4  240.93  4976.4  239.95    4993  238.35  4999.4  236.47  5002.9  236.47
  5011.1  240.32  5065.1  239.84  5171.6  239.67  5241.9  242.69  5261.9  239.61
  5302.1  239.34    5330  243.38  5458.2  249.95  5472.6  249.32  5572.9  253.75
  5586.5  252.84  5623.1   253.8  5709.7  257.97  5773.5  258.27  5869.3   262.4
#Mann= 8 ,-1 , 0
  4120.1     .11       0  4559.2     .17       0  4647.2     .15       0
    4775     .17       0    4815     .15       0  4976.4     .09       0
  5011.1     .15       0  5065.1     .11       0
Bank Sta=4976.4,5011.1
XS Rating Curve= 0 ,0
Exp/Cntr=0.3,0.1

Type RM Length L Ch R = 1 ,423     ,0,0,0
BEGIN DESCRIPTION:
CCLC 047 1.0
END DESCRIPTION:
XS GIS Cut Line= 4
      3715413.98      10133147.6      3714480.77     10133034.75
      3714376.61     10133160.62      3714517.84     10134061.03
#Sta/Elev= 30
  3967.1  257.19  4129.5  251.81  4208.8  249.93  4224.9  249.18  4229.9  250.08
  4311.9  243.23  4316.9  244.03  4375.7  240.53  4416.5   238.8  4571.4  239.34
    4628  239.55  4668.3  238.45  4698.5  239.38  4738.8  237.12  4889.9  237.42
  4898.8  235.81  4914.2  237.45  4984.5  238.56  4998.8  236.42  5013.1  238.28
  5027.5  238.56  5091.2   237.1  5131.7  237.88  5141.8  236.95  5176.3  238.14
  5323.5  237.93  5415.1  237.77  5687.4  247.58  5749.1  248.46  5981.9  257.71
#Mann= 8 ,-1 , 0
  3967.1     .11       0  4129.5     .17       0  4208.8     .11       0
  4375.7     .17       0  4571.4     .15       0  4889.9     .09       0
  4914.2     .15       0  5323.5     .11       0
Bank Sta=4889.9,4914.2
XS Rating Curve= 0 ,0
Exp/Cntr=0.3,0.1

Chan Stop Cuts=-1
Use User Specified Reach Order=0
Composite Channel Slope=5