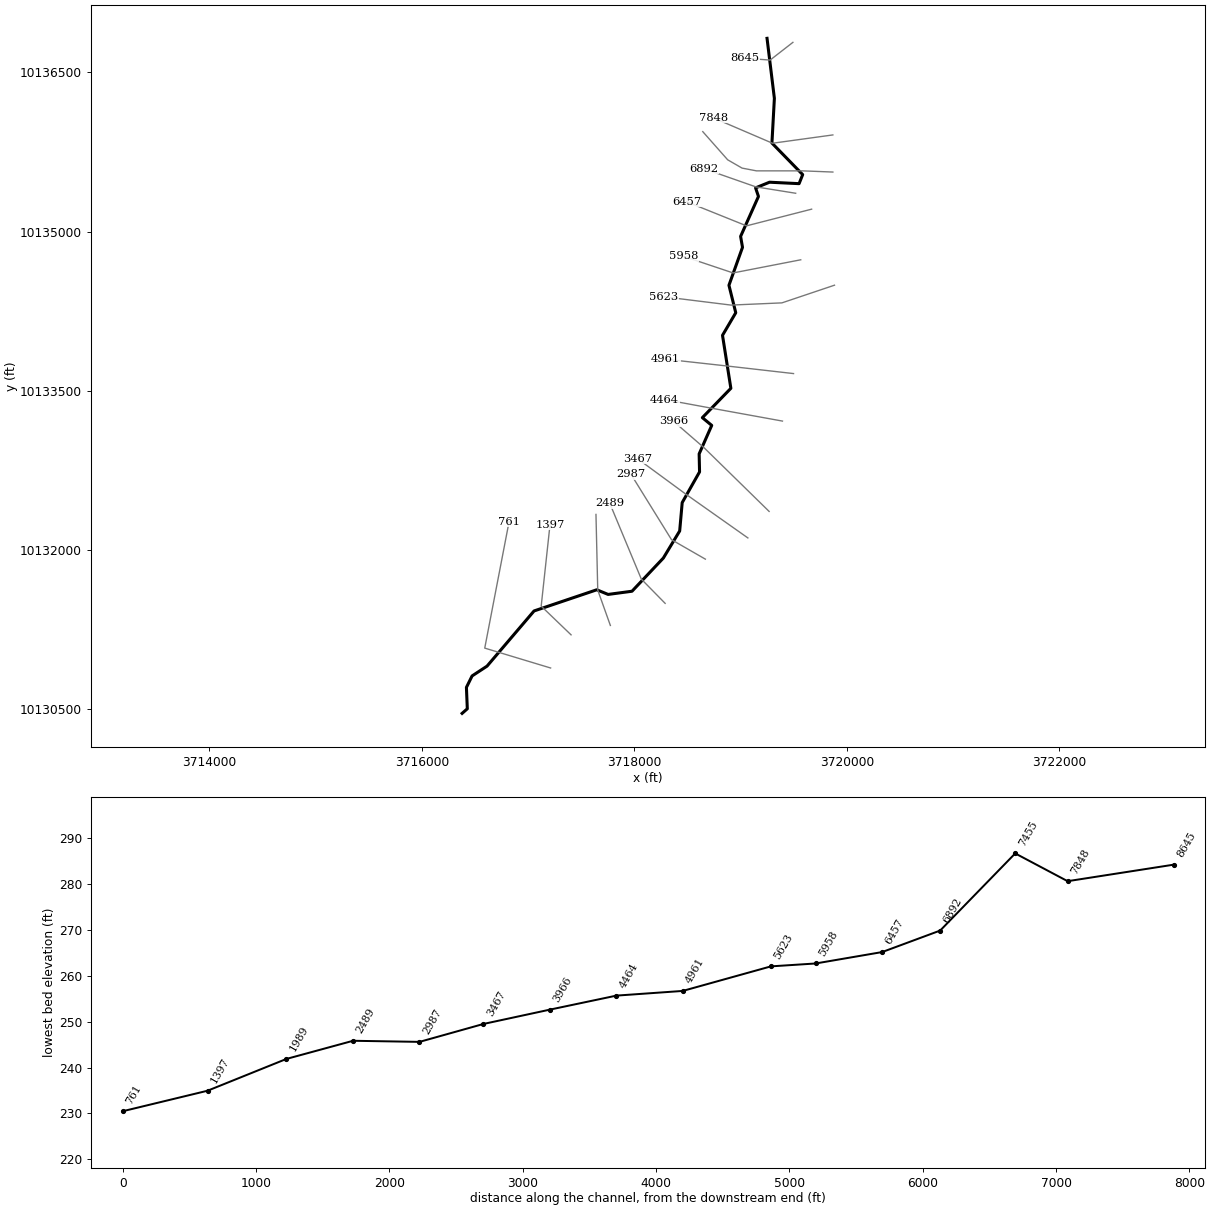
--- CCLC 049.prj (project) ---

Proj Title=CCLC 049 Base Level Engineering
Current Plan=p01
Default Exp/Contr=0.3,0.1
English Units
Geom File=g01
Flow File=f01
Flow File=f02
Plan File=p01
Y Axis Title=Elevation
X Axis Title(PF)=Main Channel Distance
X Axis Title(XS)=Station
BEGIN DESCRIPTION:
CCLC 049
END DESCRIPTION:
DSS Export Rating Curves= 0
DSS Export Rating Curve Sorted= 0
DSS Export Volume Flow Curves= 0
DXF OffsetX= 0
DXF OffsetY= 0
DXF ScaleX= 1
DXF ScaleY= 10

--- CCLC 049.p01 (plan) ---

Plan Title=Multiple Run
Short Identifier=Multiple
Geom File=g01
Flow File=f01
Subcritical Flow
K Sum by GR= 0
Std Step Tol= 0.01
Critical Tol= 0.01
Num of Std Step Trials= 20
Max Error Tol= 0.3
Flow Tol Ratio= 0.001
Split Flow NTrial= 30
Split Flow Tol= 0.02
Split Flow Ratio= 0.02
Log Output Level= 0
Friction Slope Method= 1
Unsteady Friction Slope Method= 2
Unsteady Bridges Friction Slope Method= 1
Parabolic Critical Depth
Global Vel Dist=  1 , 1 , 1
Global Log Level= 0
CheckData=True
Encroach Param= -1, 0, 0, 0
BEGIN DESCRIPTION:
Multiple Run
END DESCRIPTION:

--- CCLC 049.f01 (steady flow) ---

Flow Title=Multiple
Program Version=4.10
Number of Profiles= 7
Profile Names=10-year,25-year,50-year,1pct_min,100-year,1pct_plu,500-year
River Rch & RM=CCLC 049,Reach-1         ,8645
     255     328     429     185     559    1688     980
River Rch & RM=CCLC 049,Reach-1         ,6892
     580     782    1055     468    1414    4270    2628
Boundary for River Rch & Prof#=CCLC 049,Reach-1         , 1
Up Type= 0
Dn Type= 3
Dn Slope=0.005
Boundary for River Rch & Prof#=CCLC 049,Reach-1         , 2
Up Type= 0
Dn Type= 3
Dn Slope=0.005
Boundary for River Rch & Prof#=CCLC 049,Reach-1         , 3
Up Type= 0
Dn Type= 3
Dn Slope=0.005
Boundary for River Rch & Prof#=CCLC 049,Reach-1         , 4
Up Type= 0
Dn Type= 3
Dn Slope=0.005
Boundary for River Rch & Prof#=CCLC 049,Reach-1         , 5
Up Type= 0
Dn Type= 3
Dn Slope=0.005
Boundary for River Rch & Prof#=CCLC 049,Reach-1         , 6
Up Type= 0
Dn Type= 3
Dn Slope=0.005
Boundary for River Rch & Prof#=CCLC 049,Reach-1         , 7
Up Type= 0
Dn Type= 3
Dn Slope=0.005
DSS Import GetInterval= 0
DSS Import GetPeak= 0
DSS Import FillOption= 0

--- CCLC 049.f02 (steady flow) ---

Flow Title=Orig_BLE_Flows
Program Version=4.10
Number of Profiles= 7
Profile Names=10-year,25-year,50-year,1pct_min,100-year,1pct_plu,500-year
River Rch & RM=CCLC 049,Reach-1         ,8645
     255     322     373     142     430    1299     570
River Rch & RM=CCLC 049,Reach-1         ,6892
     580     767     917     360    1088    3285    1528
Boundary for River Rch & Prof#=CCLC 049,Reach-1         , 1
Up Type= 0
Dn Type= 3
Dn Slope=0.005
Boundary for River Rch & Prof#=CCLC 049,Reach-1         , 2
Up Type= 0
Dn Type= 3
Dn Slope=0.005
Boundary for River Rch & Prof#=CCLC 049,Reach-1         , 3
Up Type= 0
Dn Type= 3
Dn Slope=0.005
Boundary for River Rch & Prof#=CCLC 049,Reach-1         , 4
Up Type= 0
Dn Type= 3
Dn Slope=0.005
Boundary for River Rch & Prof#=CCLC 049,Reach-1         , 5
Up Type= 0
Dn Type= 3
Dn Slope=0.005
Boundary for River Rch & Prof#=CCLC 049,Reach-1         , 6
Up Type= 0
Dn Type= 3
Dn Slope=0.005
Boundary for River Rch & Prof#=CCLC 049,Reach-1         , 7
Up Type= 0
Dn Type= 3
Dn Slope=0.005
DSS Import GetInterval= 0
DSS Import GetPeak= 0
DSS Import FillOption= 0

--- CCLC 049.g01 (geometry) ---

Geom Title=Existing Conditions
Program Version=4.10

River Reach=CCLC 049        ,Reach-1
Reach XY= 30
      3719248.23     10136821.84      3719317.34     10136255.96
      3719294.31     10135834.51      3719583.78     10135537.03
      3719549.96     10135451.63      3719271.54     10135465.22
      3719140.38     10135411.77       3719167.6     10135331.07
       3718999.5     10134954.28      3719017.34     10134851.14
      3718889.73      10134493.5      3718953.89     10134234.41
      3718829.12     10134021.55      3718907.74     10133521.82
      3718639.53     10133245.19       3718727.7     10133172.26
      3718609.29     10132903.54      3718613.08     10132733.72
      3718449.77      10132444.3      3718426.03     10132176.74
      3718272.34      10131921.4      3717977.42      10131608.5
      3717752.23     10131578.42       3717645.7     10131622.26
      3717055.52      10131422.6      3716613.04     10130902.45
      3716472.34     10130809.99      3716418.89     10130701.87
      3716427.22      10130500.1      3716378.23     10130456.84

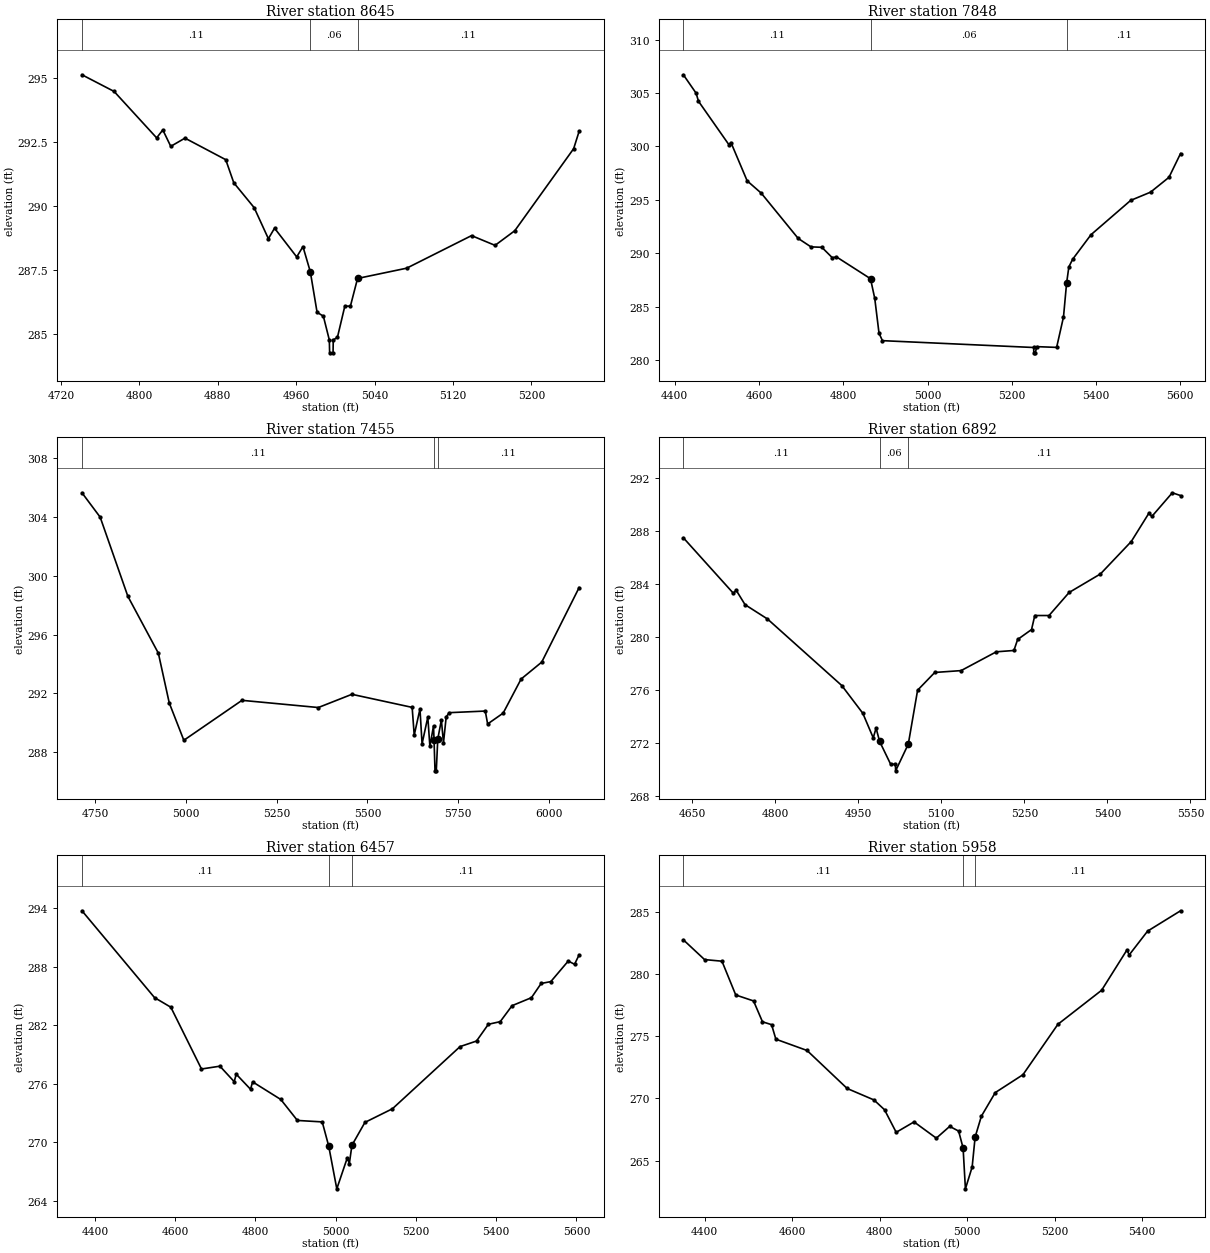
Type RM Length L Ch R = 1 ,8645    ,797,797,797
BEGIN DESCRIPTION:
CCLC 049 16.0
END DESCRIPTION:
XS GIS Cut Line= 3
      3719491.66     10136783.89      3719277.35     10136616.97
       3719042.3     10136633.86
#Sta/Elev= 30
  4741.4  295.12  4774.2  294.47  4817.6  292.66  4823.9  292.97    4832  292.33
  4846.5  292.65  4888.1  291.81  4896.3  290.91  4917.1  289.94  4931.6  288.73
  4937.9  289.14  4960.5  288.02  4966.9  288.42  4974.4  287.44  4981.3  285.86
  4987.7  285.71  4993.8  284.78  4994.1  284.28  4997.6  284.28  4997.8  284.78
  5002.1  284.89  5009.6   286.1  5015.3   286.1  5022.6  287.18  5072.7  287.58
  5138.9  288.85  5162.9  288.47    5183  289.04  5243.1  292.24  5248.7  292.92
#Mann= 3 , 0 , 0
  4741.4     .11       0  4974.4     .06       0  5022.6     .11       0
Bank Sta=4974.4,5022.6
XS Rating Curve= 0 ,0
Exp/Cntr=0.3,0.1

Type RM Length L Ch R = 1 ,7848    ,393,393,393
BEGIN DESCRIPTION:
CCLC 049 15.0
END DESCRIPTION:
XS GIS Cut Line= 3
      3719867.81     10135911.07      3719299.68     10135832.68
      3718742.59     10136072.17
#Sta/Elev= 30
  4420.6   306.7  4450.8  304.98  4456.5  304.22  4528.4  300.17  4533.5  300.36
    4572  296.77  4605.4  295.62  4693.1  291.38  4723.4  290.59  4749.2  290.55
  4773.9  289.58    4784  289.65  4864.7  287.61  4874.8  285.76  4884.9  282.51
    4893  281.81  5251.9  281.17  5252.2  280.67  5255.7  280.67  5259.3  281.25
  5306.4  281.18  5322.7  284.03    5330  287.18  5335.4  288.71  5344.4  289.43
    5388  291.73  5482.1  294.94  5529.2  295.71    5573   297.1  5600.5  299.33
#Mann= 3 , 0 , 0
  4420.6     .11       0  4864.7     .06       0    5330     .11       0
Bank Sta=4864.7,5330
XS Rating Curve= 0 ,0
Exp/Cntr=0.3,0.1

Type RM Length L Ch R = 1 ,7455    ,563,563,563
BEGIN DESCRIPTION:
CCLC 049 14.0
END DESCRIPTION:
XS GIS Cut Line= 6
      3719867.89     10135561.07      3719582.51     10135572.28
      3719148.64     10135572.26      3719013.22      10135598.3
       3718877.8     10135676.43      3718643.43     10135942.04
#Sta/Elev= 30
  4714.4  305.66  4764.5     304  4840.7  298.61  4924.6  294.74  4954.6  291.35
  4994.7  288.81  5154.7  291.53  5364.7  291.04  5457.1  291.94  5622.9  291.05
  5628.6  289.16  5644.4  290.94  5650.2  288.57    5666  290.39  5671.7  288.39
  5681.7  289.79 5683.11288.8403  5685.8  286.73  5689.3  286.73  5693.4  288.89
  5703.3  290.19  5709.1  288.64  5716.5  290.39  5724.8  290.69  5824.1   290.8
  5830.6  289.92  5873.3  290.66  5922.7  292.98  5979.4  294.13  6082.4  299.21
#Mann= 3 , 0 , 0
  4714.4     .11       0 5683.11     .06       0  5693.4     .11       0
Bank Sta=5683.11,5693.4
XS Rating Curve= 0 ,0
Exp/Cntr=0.3,0.1

Type RM Length L Ch R = 1 ,6892    ,435,435,435
BEGIN DESCRIPTION:
CCLC 049 13.0
END DESCRIPTION:
XS GIS Cut Line= 3
      3719517.83     10135361.07      3719143.43     10135421.22
      3718653.83      10135593.1
#Sta/Elev= 30
    4634   287.5  4724.3  283.31  4729.4  283.54  4745.4  282.45  4785.9  281.37
  4920.2  276.34  4958.1  274.25    4977  272.39  4982.1  273.13  4988.5  272.12
  5008.4   270.4  5017.1   270.4  5017.4   269.9  5040.3  271.92  5057.1  275.99
  5088.1  277.33  5135.7  277.47  5199.3  278.89  5231.1  278.99  5237.8  279.82
  5262.9  280.57  5268.8  281.63  5294.5  281.63  5330.8  283.37  5387.4  284.77
  5443.1  287.22  5474.8  289.35  5480.4  289.12  5517.2   290.9  5532.1  290.69
#Mann= 3 , 0 , 0
    4634     .11       0  4988.5     .06       0  5040.3     .11       0
Bank Sta=4988.5,5040.3
XS Rating Curve= 0 ,0
Exp/Cntr=0.3,0.1

Type RM Length L Ch R = 1 ,6457    ,499,499,499
BEGIN DESCRIPTION:
CCLC 049 12.0
END DESCRIPTION:
XS GIS Cut Line= 3
      3719667.85     10135211.07      3719055.33     10135053.74
       3718492.6     10135280.51
#Sta/Elev= 30
  4367.6  293.75  4548.4  284.84  4589.1  283.85  4665.5  277.51  4711.4   277.8
    4747  276.21  4752.1  276.98  4787.7  275.43  4792.9  276.19  4863.2  274.38
  4904.5  272.23  4966.4  272.08 4982.55269.5985  5002.7  265.21  5028.6  268.36
    5034  267.81  5040.4  269.68  5072.8  272.03  5141.4  273.43  5309.9  279.81
  5350.9  280.38  5380.4   282.1    5410  282.37  5439.5  284.01  5487.8  284.83
    5512  286.29  5536.1  286.48  5579.5  288.59  5595.2  288.26  5606.7  289.23
#Mann= 3 , 0 , 0
  4367.6     .11       0 4982.55     .06       0  5040.4     .11       0
Bank Sta=4982.55,5040.4
XS Rating Curve= 0 ,0
Exp/Cntr=0.3,0.1

Type RM Length L Ch R = 1 ,5958    ,335,335,335
BEGIN DESCRIPTION:
CCLC 049 11.0
END DESCRIPTION:
XS GIS Cut Line= 3
      3719565.31     10134733.72      3718928.88     10134609.74
      3718466.33     10134764.97
#Sta/Elev= 30
  4351.6  282.77    4400  281.18  4439.8  281.05  4471.3  278.33    4512  277.85
  4532.4  276.17  4553.2  275.94    4563  274.77  4634.3  273.86    4726   270.8
  4787.1  269.88  4811.3  269.09    4838  267.27  4878.8  268.11  4929.7   266.8
  4960.3  267.75  4980.7  267.37  4990.9  266.01  4996.2  262.72  5011.6  264.48
  5018.4  266.89  5032.7  268.57  5064.4  270.47  5127.7  271.91  5207.6  275.97
  5307.5  278.71  5365.3  281.95  5370.6  281.56  5412.5  283.47  5487.9  285.11
#Mann= 3 , 0 , 0
  4351.6     .11       0  4990.9     .06       0  5018.4     .11       0
Bank Sta=4990.9,5018.4
XS Rating Curve= 0 ,0
Exp/Cntr=0.3,0.1

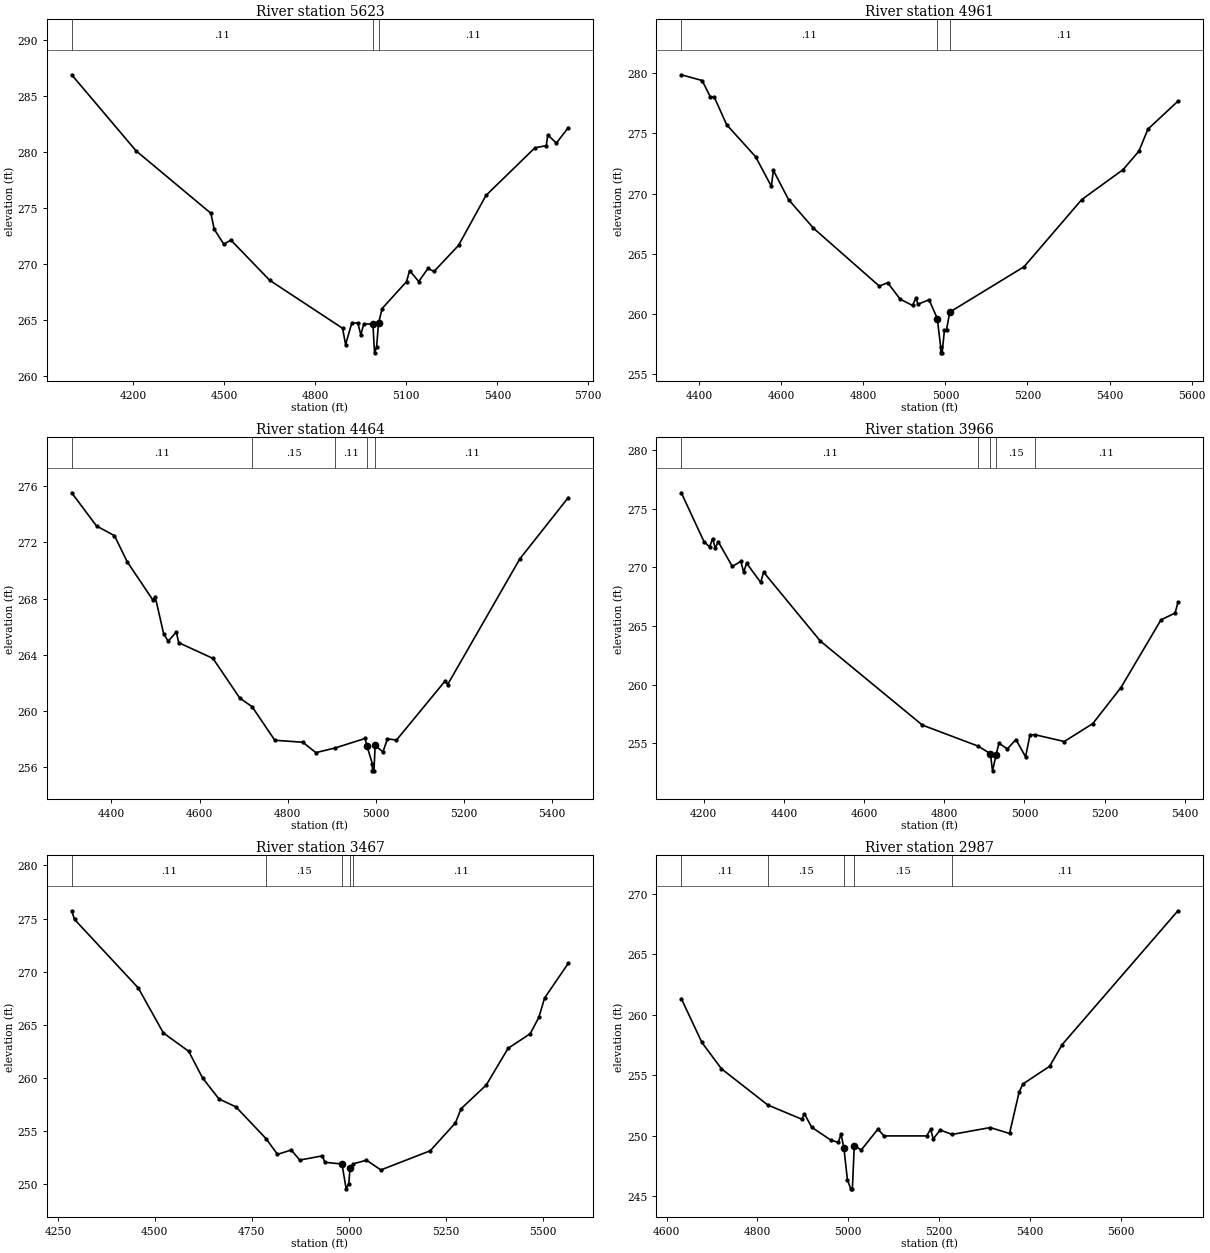
Type RM Length L Ch R = 1 ,5623    ,662,662,662
BEGIN DESCRIPTION:
CCLC 049 10.0
END DESCRIPTION:
XS GIS Cut Line= 4
      3719883.01     10134494.14      3719388.22     10134327.47
      3718909.05     10134306.63      3718278.81     10134384.76
#Sta/Elev= 30
  3997.1  286.88  4209.3   280.1    4456  274.53  4466.8  273.11  4498.5  271.78
  4521.9  272.14  4649.7  268.56  4889.9  264.28  4899.9  262.83    4920  264.72
    4940  264.77    4950   263.7    4960  264.67    4990  264.65  4995.2  262.09
    5002  262.59 5008.36264.7099  5020.2  266.04  5100.8  268.44  5110.9  269.42
  5141.1  268.45  5171.3  269.61  5191.5  269.35  5272.1  271.67  5362.8  276.13
    5524  280.37  5561.3  280.56  5566.3  281.52  5594.6  280.79  5633.9  282.17
#Mann= 3 , 0 , 0
  3997.1     .11       0    4990     .06       0 5008.36     .11       0
Bank Sta=4990,5008.36
XS Rating Curve= 0 ,0
Exp/Cntr=0.3,0.1

Type RM Length L Ch R = 1 ,4961    ,497,497,497
BEGIN DESCRIPTION:
CCLC 049 9.0
END DESCRIPTION:
XS GIS Cut Line= 3
      3719497.61      10133660.8      3718858.27     10133733.85
       3718295.1     10133796.15
#Sta/Elev= 30
  4356.5  279.89  4407.3  279.41  4426.7  278.08  4436.8  278.03    4467  275.73
  4537.4  273.07  4575.9   270.6  4580.9  271.92  4617.9  269.49  4678.3  267.12
  4838.9  262.29  4859.5  262.57  4889.7   261.2  4919.9  260.68  4928.2  261.29
  4933.2  260.78  4960.2  261.15  4980.3  259.59  4988.4  257.23  4988.6  256.73
  4992.1  256.73  4997.7  258.63  5002.7  258.63  5010.5  260.12  5191.6   263.9
  5332.4   269.5    5433  271.99  5471.6  273.53  5493.4  275.36  5566.6  277.69
#Mann= 3 , 0 , 0
  4356.5     .11       0  4980.3     .06       0  5010.5     .11       0
Bank Sta=4980.3,5010.5
XS Rating Curve= 0 ,0
Exp/Cntr=0.3,0.1

Type RM Length L Ch R = 1 ,4464    ,498,498,498
BEGIN DESCRIPTION:
CCLC 049 8.0
END DESCRIPTION:
XS GIS Cut Line= 3
      3719393.46     10133212.88      3718714.32     10133336.46
      3718284.01     10133416.02
#Sta/Elev= 30
  4309.7  275.54  4366.2  273.17  4406.9  272.48  4435.8  270.62  4494.2  267.89
  4499.3  268.13  4518.7  265.47  4528.9  264.96  4547.5  265.61  4552.6  264.85
  4630.5  263.73  4691.5   260.9  4719.6  260.28    4771  257.89  4834.5  257.75
  4864.3  257.01    4908  257.34  4976.1  258.02  4980.4257.4751  4992.6  256.21
  4992.8  255.71  4996.3  255.71  4998.9  257.52  5016.7  257.06  5026.9     258
  5047.3   257.9  5158.4  262.14  5163.5  261.86  5327.4  270.82  5437.6   275.2
#Mann= 5 ,-1 , 0
  4309.7     .11       0  4719.6     .15       0    4908     .11       0
  4980.4     .06       0  4998.9     .11       0
Bank Sta=4980.4,4998.9
XS Rating Curve= 0 ,0
Exp/Cntr=0.3,0.1

Type RM Length L Ch R = 1 ,3966    ,499,499,499
BEGIN DESCRIPTION:
CCLC 049 7.0
END DESCRIPTION:
XS GIS Cut Line= 3
      3719267.85     10132361.07      3718657.05     10132960.22
      3718367.88     10133211.05
#Sta/Elev= 30
  4144.4  276.36  4200.9   272.2  4215.1  271.74  4222.2  272.45  4229.2  271.64
  4236.3   272.2  4271.6  270.08  4292.9  270.52  4299.9  269.58  4307.1  270.36
  4342.4  268.72  4349.5   269.6  4490.9  263.73  4745.5  256.56  4885.1  254.76
  4915.1  254.12  4920.5  252.66  4929.3  254.01  4936.4  255.01  4957.6  254.53
  4978.8  255.33  5002.8  253.86  5013.9  255.72    5026  255.74  5099.4  255.16
  5170.6  256.69  5240.8  259.76  5340.6  265.53  5375.7  266.11  5382.8  267.01
#Mann= 5 ,-1 , 0
  4144.4     .11       0  4885.1     .15       0  4915.1     .09       0
  4929.3     .15       0    5026     .11       0
Bank Sta=4915.1,4929.3
XS Rating Curve= 0 ,0
Exp/Cntr=0.3,0.1

Type RM Length L Ch R = 1 ,3467    ,480,480,480
BEGIN DESCRIPTION:
CCLC 049 6.0
END DESCRIPTION:
XS GIS Cut Line= 3
      3719067.82     10132111.09      3718484.57     10132523.46
      3718028.81     10132858.74
#Sta/Elev= 30
  4285.7  275.73  4293.1  274.91  4457.1  268.47    4522  264.22  4587.3  262.49
  4622.9  259.99  4665.3     258  4709.1  257.25  4786.5  254.27  4816.2  252.78
  4851.9  253.19  4873.5  252.24  4931.9  252.64  4938.1  252.03  4982.4  251.87
  4993.2  249.53    5000  250.03  5003.3   251.5    5011  251.88  5045.6  252.23
  5082.7  251.31    5210  253.12  5274.8  255.74  5289.5  257.08  5354.3  259.31
  5410.6  262.77  5467.7  264.15    5490   265.7  5504.7  267.51  5565.8  270.78
#Mann= 5 ,-1 , 0
  4285.7     .11       0  4786.5     .15       0  4982.4     .09       0
  5003.3     .15       0    5011     .11       0
Bank Sta=4982.4,5003.3
XS Rating Curve= 0 ,0
Exp/Cntr=0.3,0.1

Type RM Length L Ch R = 1 ,2987    ,498,498,498
BEGIN DESCRIPTION:
CCLC 049 5.0
END DESCRIPTION:
XS GIS Cut Line= 3
      3718667.84     10131911.08      3718349.34     10132094.41
      3717967.86     10132711.05
#Sta/Elev= 30
  4632.5  261.33  4677.7  257.71  4720.9  255.53  4822.9  252.54  4897.6  251.37
  4903.4  251.82  4919.2  250.71  4962.3  249.62  4978.1  249.46  4983.8  250.16
  4990.2     249    4998  246.35  5005.4  245.62  5008.9  245.62    5013  249.19
  5028.4  248.83  5065.1  250.55  5078.4  249.99  5172.5  249.99  5180.9  250.55
  5186.7  249.74  5202.1  250.48  5228.1  250.11  5312.1  250.68  5354.6  250.19
  5375.9  253.63  5384.1  254.28  5442.9  255.74  5470.4  257.53  5725.1  268.58
#Mann= 5 ,-1 , 0
  4632.5     .11       0  4822.9     .15       0  4990.2     .09       0
    5013     .15       0  5228.1     .11       0
Bank Sta=4990.2,5013
XS Rating Curve= 0 ,0
Exp/Cntr=0.3,0.1

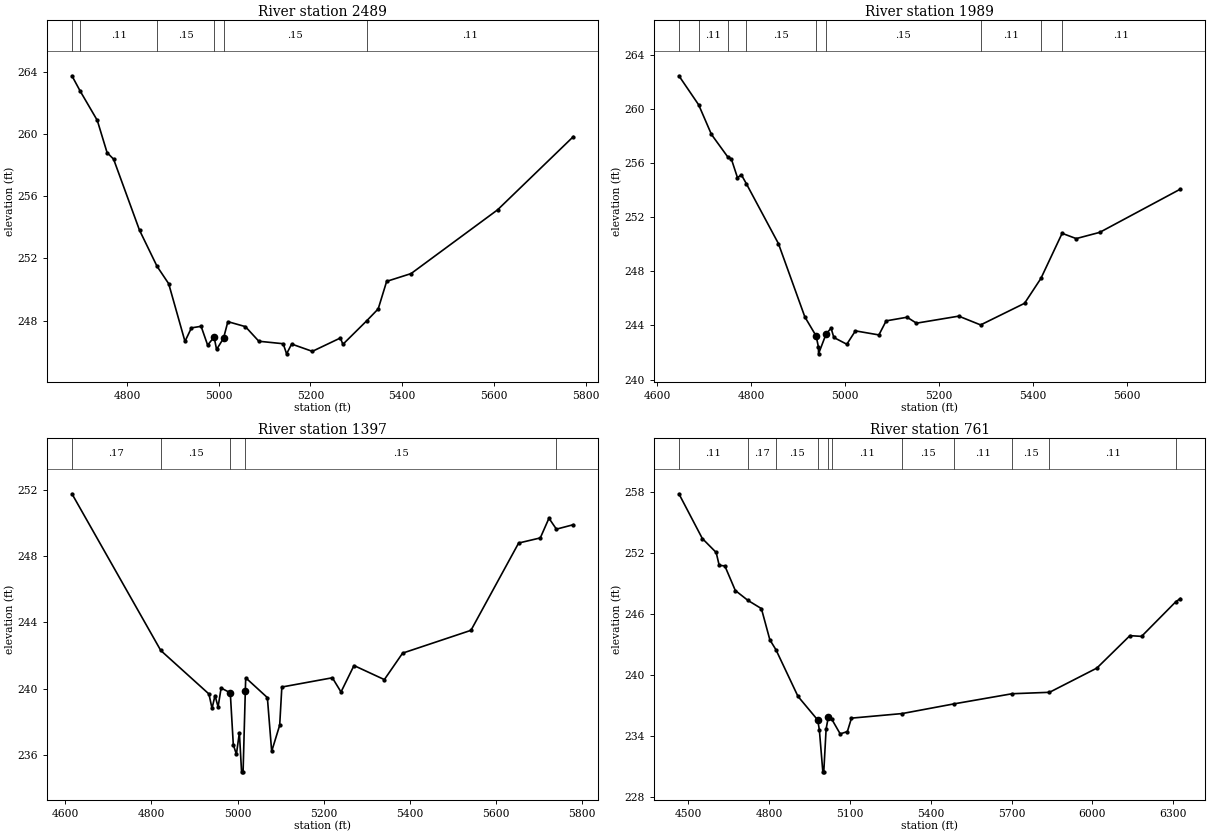
Type RM Length L Ch R = 1 ,2489    ,500,500,500
BEGIN DESCRIPTION:
CCLC 049 4.0
END DESCRIPTION:
XS GIS Cut Line= 3
      3718289.24     10131494.16      3718065.33     10131722.49
      3717768.58     10132436.48
#Sta/Elev= 30
  4680.2  263.74  4698.3  262.75  4735.5  260.87  4756.8   258.8    4771  258.38
  4827.5  253.81  4865.7  251.49  4891.1  250.37  4926.6  246.66  4940.7  247.53
  4961.8  247.63    4976  246.42  4990.1  246.94  4995.5  246.14  5010.6  246.86
  5020.1  247.93  5058.3  247.61  5087.6  246.67  5140.7  246.51  5148.1  245.86
  5159.1  246.49  5204.2  246.02  5265.4  246.88  5270.8  246.47  5322.9  247.99
  5347.8  248.75  5366.2  250.52  5419.4  251.02    5608  255.12  5773.2  259.83
#Mann= 6 ,-1 , 0
  4680.2     .17       0  4698.3     .11       0  4865.7     .15       0
  4990.1     .09       0  5010.6     .15       0  5322.9     .11       0
Bank Sta=4990.1,5010.6
XS Rating Curve= 0 ,0
Exp/Cntr=0.3,0.1

Type RM Length L Ch R = 1 ,1989    ,592,592,592
BEGIN DESCRIPTION:
CCLC 049 3.0
END DESCRIPTION:
XS GIS Cut Line= 3
      3717773.64     10131285.79       3717654.9     10131619.49
      3717638.22      10132332.7
#Sta/Elev= 30
  4645.8  262.48  4687.9  260.33  4715.1  258.14  4749.3   256.5  4757.5  256.32
  4770.5  254.94  4778.8  255.15  4789.3   254.5  4857.7  250.06    4914  244.63
    4938  243.22  4942.9   242.4  4943.1   241.9  4959.2  243.37  4969.8   243.8
  4975.7  243.11  5003.3  242.61  5021.6   243.6  5071.6   243.3  5087.1  244.34
  5131.6  244.61  5151.6  244.17  5241.6  244.69  5288.2  244.04  5381.7  245.64
  5416.5  247.48  5461.7  250.82  5491.7  250.43  5541.7  250.89  5713.4  254.09
#Mann= 9 ,-1 , 0
  4645.8     .17       0  4687.9     .11       0  4749.3     .17       0
  4789.3     .15       0    4938     .09       0  4959.2     .15       0
  5288.2     .11       0  5416.5     .15       0  5461.7     .11       0
Bank Sta=4938,4959.2
XS Rating Curve= 0 ,0
Exp/Cntr=0.3,0.1

Type RM Length L Ch R = 1 ,1397    ,636,636,636
BEGIN DESCRIPTION:
CCLC 049 2.0
END DESCRIPTION:
XS GIS Cut Line= 3
      3717403.83     10131197.27       3717122.6     10131468.09
      3717205.77     10132237.47
#Sta/Elev= 30
  4615.4  251.78  4821.7   242.3  4933.5  239.67  4940.7   238.8  4947.6  239.57
  4954.8  238.89  4961.8  240.03  4983.1  239.74  4990.1   236.6  4997.3  236.02
  5004.2  237.33  5009.3  234.96  5012.8  234.96    5018239.8584  5018.9  240.65
  5069.2  239.45  5079.2   236.2  5097.8  237.78  5102.8  240.09  5220.1  240.65
  5240.2  239.79  5270.3  241.39  5340.8  240.54  5383.2  242.14  5541.9  243.52
  5652.6   248.8  5702.9  249.11    5723   250.3  5740.3  249.64  5779.7  249.91
#Mann= 5 ,-1 , 0
  4615.4     .17       0  4821.7     .15       0  4983.1     .09       0
    5018     .15       0  5740.3     .17       0
Bank Sta=4983.1,5018
XS Rating Curve= 0 ,0
Exp/Cntr=0.3,0.1

Type RM Length L Ch R = 1 ,761     ,0,0,0
BEGIN DESCRIPTION:
CCLC 049 1.0
END DESCRIPTION:
XS GIS Cut Line= 3
      3717211.15     10130884.75      3716591.35     10131072.26
      3716820.52     10132264.99
#Sta/Elev= 30
  4464.7  257.83  4551.7  253.43  4603.1  252.06  4614.4  250.79  4635.3  250.74
  4674.2  248.32  4720.9  247.35  4771.1  246.54  4802.5  243.47  4825.2  242.49
  4906.9  237.91  4980.1  235.59  4986.3  234.62  4999.2  230.49  5002.7  230.49
  5011.4   234.7  5019.2  235.84  5032.7  235.65  5063.7  234.22  5090.3  234.45
  5105.5  235.77  5293.8  236.22  5487.9  237.18  5702.3  238.17  5840.9  238.31
  6016.7  240.69  6139.5  243.88  6182.8  243.81  6310.1  247.22  6326.8  247.53
#Mann= 11 ,-1 , 0
  4464.7     .11       0  4720.9     .17       0  4825.2     .15       0
  4980.1     .06       0  5019.2     .15       0  5032.7     .11       0
  5293.8     .15       0  5487.9     .11       0  5702.3     .15       0
  5840.9     .11       0  6310.1     .15       0
Bank Sta=4980.1,5019.2
XS Rating Curve= 0 ,0
Exp/Cntr=0.3,0.1

Chan Stop Cuts=-1
Use User Specified Reach Order=0
Composite Channel Slope=5