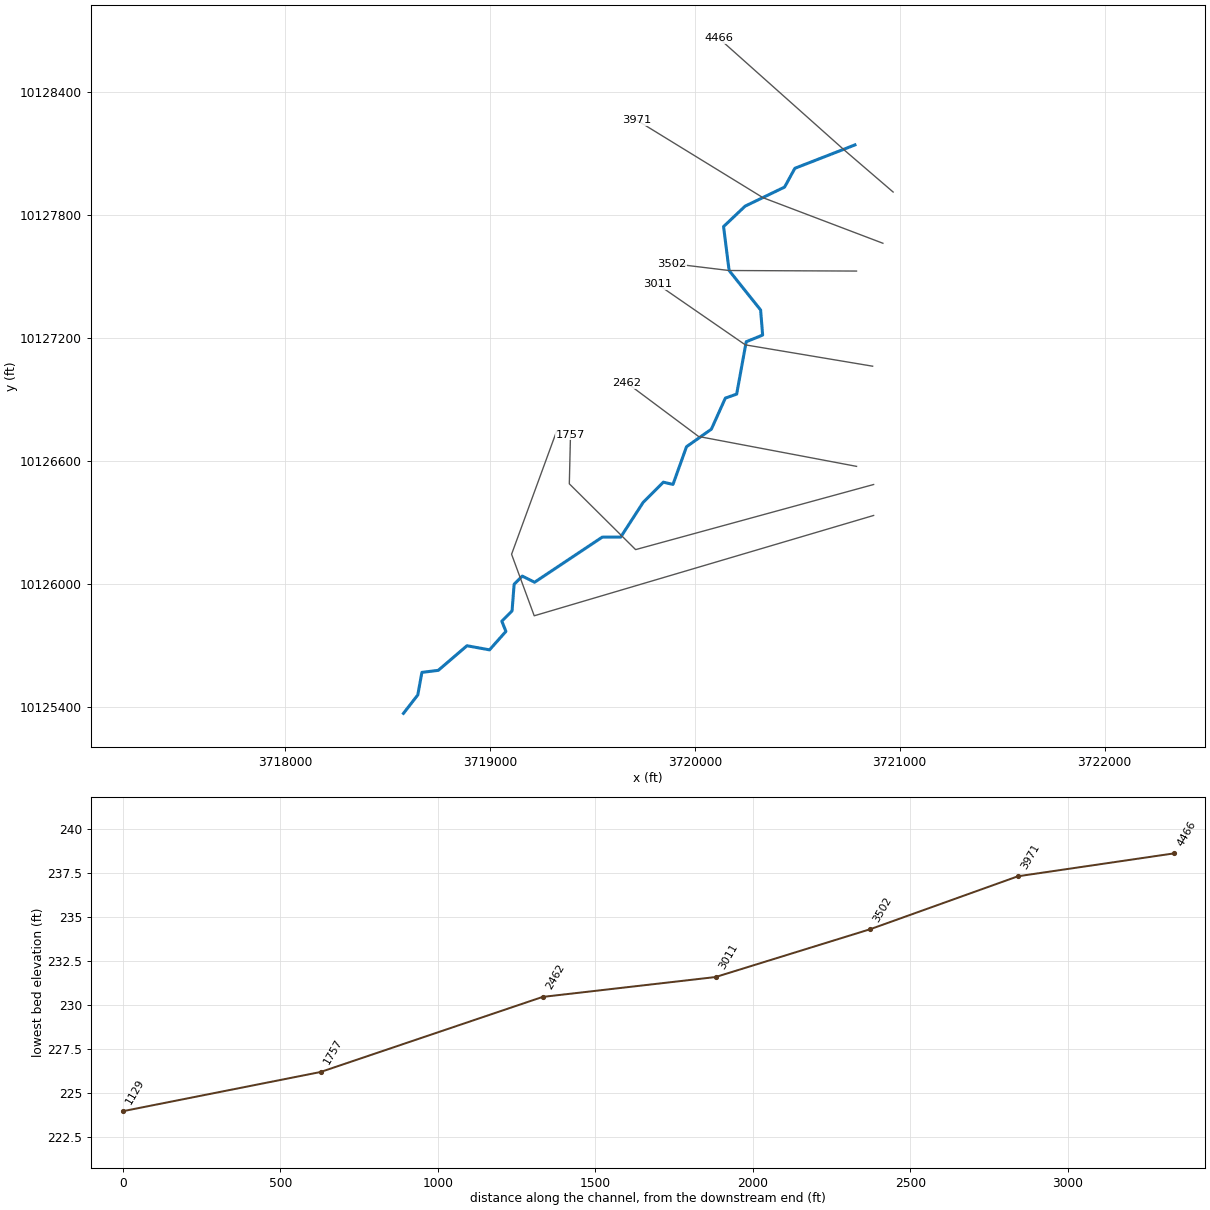
--- CCLC 050.prj (project) ---

Proj Title=CCLC 050 Base Level Engineering
Current Plan=p01
Default Exp/Contr=0.3,0.1
English Units
Geom File=g01
Flow File=f01
Flow File=f02
Plan File=p01
Y Axis Title=Elevation
X Axis Title(PF)=Main Channel Distance
X Axis Title(XS)=Station
BEGIN DESCRIPTION:
CCLC 050
END DESCRIPTION:
DSS Export Rating Curves= 0
DSS Export Rating Curve Sorted= 0
DSS Export Volume Flow Curves= 0
DXF OffsetX= 0
DXF OffsetY= 0
DXF ScaleX= 1
DXF ScaleY= 10

--- CCLC 050.p01 (plan) ---

Plan Title=Multiple Run
Short Identifier=Multiple
Geom File=g01
Flow File=f01
Subcritical Flow
K Sum by GR= 0
Std Step Tol= 0.01
Critical Tol= 0.01
Num of Std Step Trials= 20
Max Error Tol= 0.3
Flow Tol Ratio= 0.001
Split Flow NTrial= 30
Split Flow Tol= 0.02
Split Flow Ratio= 0.02
Log Output Level= 0
Friction Slope Method= 1
Unsteady Friction Slope Method= 2
Unsteady Bridges Friction Slope Method= 1
Parabolic Critical Depth
Global Vel Dist=  1 , 1 , 1
Global Log Level= 0
CheckData=True
Encroach Param= -1, 0, 0, 0
BEGIN DESCRIPTION:
Multiple Run
END DESCRIPTION:

--- CCLC 050.f01 (steady flow) ---

Flow Title=Multiple
Program Version=4.10
Number of Profiles= 7
Profile Names=10-year,25-year,50-year,1pct_min,100-year,1pct_plu,500-year
River Rch & RM=CCLC 050,Reach-1         ,4466
     627     847    1143     508    1533    4630    2850
Boundary for River Rch & Prof#=CCLC 050,Reach-1         , 1
Up Type= 0
Dn Type= 3
Dn Slope=0.005
Boundary for River Rch & Prof#=CCLC 050,Reach-1         , 2
Up Type= 0
Dn Type= 3
Dn Slope=0.005
Boundary for River Rch & Prof#=CCLC 050,Reach-1         , 3
Up Type= 0
Dn Type= 3
Dn Slope=0.005
Boundary for River Rch & Prof#=CCLC 050,Reach-1         , 4
Up Type= 0
Dn Type= 3
Dn Slope=0.005
Boundary for River Rch & Prof#=CCLC 050,Reach-1         , 5
Up Type= 0
Dn Type= 3
Dn Slope=0.005
Boundary for River Rch & Prof#=CCLC 050,Reach-1         , 6
Up Type= 0
Dn Type= 3
Dn Slope=0.005
Boundary for River Rch & Prof#=CCLC 050,Reach-1         , 7
Up Type= 0
Dn Type= 3
Dn Slope=0.005
DSS Import GetInterval= 0
DSS Import GetPeak= 0
DSS Import FillOption= 0

--- CCLC 050.f02 (steady flow) ---

Flow Title=Orig_BLE_Flows
Program Version=4.10
Number of Profiles= 7
Profile Names=10-year,25-year,50-year,1pct_min,100-year,1pct_plu,500-year
River Rch & RM=CCLC 050,Reach-1         ,4466
     627     830     994     391    1179    3562    1657
Boundary for River Rch & Prof#=CCLC 050,Reach-1         , 1
Up Type= 0
Dn Type= 3
Dn Slope=0.005
Boundary for River Rch & Prof#=CCLC 050,Reach-1         , 2
Up Type= 0
Dn Type= 3
Dn Slope=0.005
Boundary for River Rch & Prof#=CCLC 050,Reach-1         , 3
Up Type= 0
Dn Type= 3
Dn Slope=0.005
Boundary for River Rch & Prof#=CCLC 050,Reach-1         , 4
Up Type= 0
Dn Type= 3
Dn Slope=0.005
Boundary for River Rch & Prof#=CCLC 050,Reach-1         , 5
Up Type= 0
Dn Type= 3
Dn Slope=0.005
Boundary for River Rch & Prof#=CCLC 050,Reach-1         , 6
Up Type= 0
Dn Type= 3
Dn Slope=0.005
Boundary for River Rch & Prof#=CCLC 050,Reach-1         , 7
Up Type= 0
Dn Type= 3
Dn Slope=0.005
DSS Import GetInterval= 0
DSS Import GetPeak= 0
DSS Import FillOption= 0

--- CCLC 050.g01 (geometry) ---

Geom Title=Existing Conditions
Program Version=4.10

River Reach=CCLC 050        ,Reach-1
Reach XY= 30
       3720781.5     10128140.95      3720488.23     10128026.84
      3720438.23     10127935.21      3720245.44     10127842.06
       3720140.4     10127742.43      3720167.47     10127528.01
      3720321.25     10127335.24        3720331.     10127212.87
      3720250.86     10127180.38      3720204.29     10126924.81
      3720149.06     10126905.32      3720080.84      10126753.7
      3719959.55     10126668.15      3719893.49     10126484.05
      3719846.57     10126495.18      3719748.23     10126396.84
      3719638.23     10126226.84      3719548.23     10126226.84
      3719218.23     10126006.84      3719158.23     10126036.84
      3719118.23     10125996.84      3719108.23     10125866.84
      3719058.23     10125816.84      3719078.23     10125766.84
      3718998.23     10125676.84      3718888.23     10125696.84
      3718748.23     10125576.84      3718668.23     10125566.84
      3718648.23     10125456.84      3718578.23     10125366.84

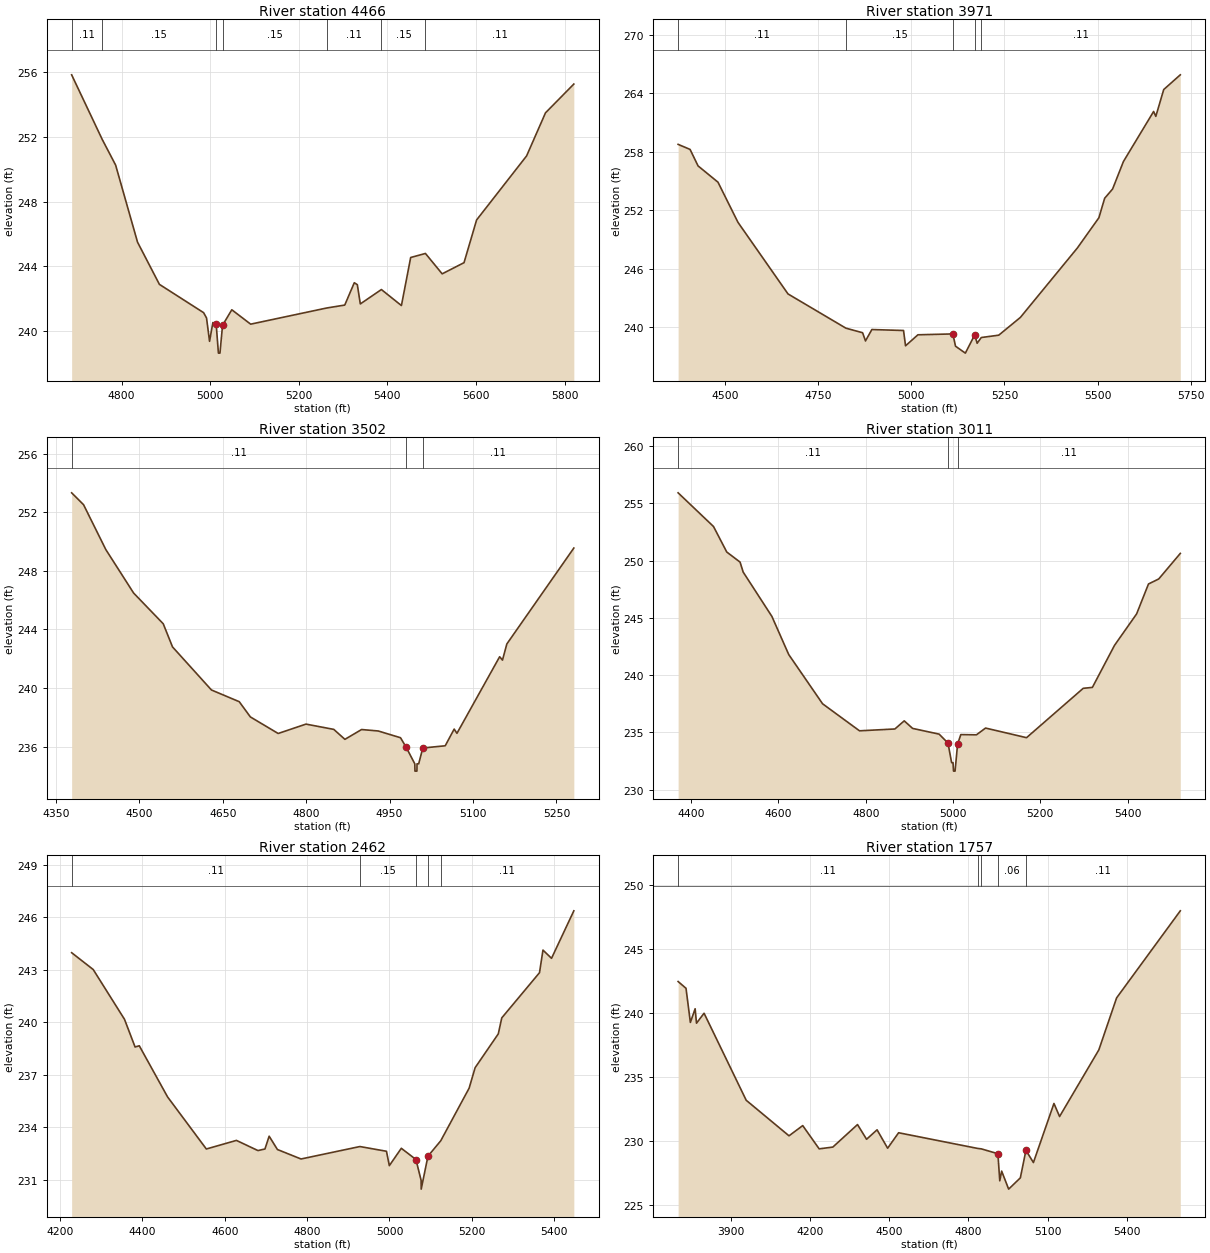
Type RM Length L Ch R = 1 ,4466    ,495,495,495
BEGIN DESCRIPTION:
CCLC 050 7.0
END DESCRIPTION:
XS GIS Cut Line= 3
      3720967.83     10127911.09       3720730.6     10128114.96
      3720117.85     10128661.08
#Sta/Elev= 30
  4687.2  255.84    4756  251.86  4786.5  250.26  4835.9   245.5  4885.3  242.89
  4985.1  241.14  4991.7  240.81  4998.5  239.37    5006  240.53  5013.5  240.41
  5018.5  238.64    5022  238.64  5027.8  240.36  5048.7  241.32  5091.3  240.43
  5263.1  241.43  5303.7  241.61  5325.2  242.99  5332.1  242.87  5338.8  241.68
  5386.4  242.57  5431.6  241.58  5452.5  244.55  5485.8   244.8  5523.6  243.54
  5572.9  244.23  5601.3  246.87  5714.2  250.83  5756.8  253.49  5820.8  255.27
#Mann= 7 ,-1 , 0
  4687.2     .11       0    4756     .15       0  5013.5     .09       0
  5027.8     .15       0  5263.1     .11       0  5386.4     .15       0
  5485.8     .11       0
Bank Sta=5013.5,5027.8
XS Rating Curve= 0 ,0
Exp/Cntr=0.3,0.1

Type RM Length L Ch R = 1 ,3971    ,469,469,469
BEGIN DESCRIPTION:
CCLC 050 6.0
END DESCRIPTION:
XS GIS Cut Line= 3
      3720917.88     10127661.06      3720333.16     10127883.21
      3719717.83     10128261.09
#Sta/Elev= 30
  4374.5  258.75  4406.6  258.23    4428  256.54  4481.5  254.87    4535  250.76
  4669.4  243.41  4824.7   239.9  4869.6  239.43  4877.3  238.59  4894.4  239.76
  4979.4  239.66  4984.8  238.09    5018  239.22  5111.8  239.31  5118.9  238.05
  5145.3  237.34  5170.5  239.22  5176.9  238.35    5188  238.94  5234.9  239.18
  5292.9     241  5445.6  248.11  5503.6  251.22  5519.1  253.22  5540.4  254.17
  5569.5  256.99  5650.5  262.12  5656.4  261.62  5677.6  264.37  5722.1  265.88
#Mann= 5 ,-1 , 0
  4374.5     .11       0  4824.7     .15       0  5111.8     .09       0
  5170.5     .15       0    5188     .11       0
Bank Sta=5111.8,5170.5
XS Rating Curve= 0 ,0
Exp/Cntr=0.3,0.1

Type RM Length L Ch R = 1 ,3502    ,491,491,491
BEGIN DESCRIPTION:
CCLC 050 5.0
END DESCRIPTION:
XS GIS Cut Line= 3
      3720789.27     10127525.38      3720167.47     10127528.01
      3719888.21     10127561.84
#Sta/Elev= 30
  4378.2  253.33  4399.6  252.52  4439.6  249.46  4489.6  246.49  4542.9  244.39
  4559.6  242.81  4629.6  239.87  4679.6  239.07  4699.6  238.03  4749.6   236.9
  4799.6  237.54  4849.6  237.18  4869.6   236.5  4899.6  237.17  4929.6  237.07
  4969.6  236.61  4979.6  235.97  4995.3  234.83  4995.6  234.33  4999.1  234.33
  4999.3  234.83  5002.3  234.83  5009.7  235.91    5050  236.06  5066.1   237.2
  5071.1  236.91  5147.9  242.14    5153  241.91  5160.8  243.01  5281.3  249.56
#Mann= 3 , 0 , 0
  4378.2     .11       0  4979.6     .06       0  5009.7     .11       0
Bank Sta=4979.6,5009.7
XS Rating Curve= 0 ,0
Exp/Cntr=0.3,0.1

Type RM Length L Ch R = 1 ,3011    ,549,549,549
BEGIN DESCRIPTION:
CCLC 050 4.0
END DESCRIPTION:
XS GIS Cut Line= 3
      3720867.86     10127061.07      3720246.53     10127165.22
      3719817.81      10127461.1
#Sta/Elev= 30
    4370  255.91  4451.1  252.97  4481.5  250.74    4512  249.86  4519.1  248.99
  4584.9  245.12  4623.5  241.79  4701.1  237.49  4785.7  235.13  4866.8  235.29
  4888.2     236  4907.4  235.34  4968.2  234.84  4988.5  234.06  4996.8  232.35
    5000  232.35  5001.2  231.61  5004.7  231.61  5010.5  233.97  5017.9   234.8
  5053.7  234.78  5074.6  235.37  5168.5  234.53  5298.4  238.84  5319.4  238.92
  5370.1  242.59  5420.8  245.34    5448  247.95  5471.5  248.39  5520.9  250.62
#Mann= 3 , 0 , 0
    4370     .11       0  4988.5     .06       0  5010.5     .11       0
Bank Sta=4988.5,5010.5
XS Rating Curve= 0 ,0
Exp/Cntr=0.3,0.1

Type RM Length L Ch R = 1 ,2462    ,705,705,705
BEGIN DESCRIPTION:
CCLC 050 3.0
END DESCRIPTION:
XS GIS Cut Line= 3
      3720789.31     10126572.25      3720018.43     10126718.09
      3719669.45     10126978.53
#Sta/Elev= 30
  4227.9  243.97  4280.3  243.01  4356.3  240.17    4382  238.59  4392.2  238.66
    4461  235.74  4555.1  232.77  4628.2  233.26  4680.5  232.68  4697.5  232.77
  4707.7   233.5  4727.8  232.74  4785.2   232.2  4928.1  232.91  4992.7  232.64
  4999.7  231.82  5028.8  232.81  5064.3  232.17  5076.9  230.98  5077.1  230.48
  5093.5  232.36  5124.6  233.24  5193.5  236.24  5208.1  237.41  5264.4  239.34
  5272.8  240.25  5364.5  242.83  5372.9  244.12  5393.7  243.65  5447.9  246.36
#Mann= 5 ,-1 , 0
  4227.9     .11       0  4928.1     .15       0  5064.3     .09       0
  5093.5     .15       0  5124.6     .11       0
Bank Sta=5064.3,5093.5
XS Rating Curve= 0 ,0
Exp/Cntr=0.3,0.1

Type RM Length L Ch R = 1 ,1757    ,628,628,628
BEGIN DESCRIPTION:
CCLC 050 2.0
END DESCRIPTION:
XS GIS Cut Line= 4
       3720872.6     10126483.72      3719711.14     10126166.01
      3719387.64     10126487.11       3719393.4     10126727.31
#Sta/Elev= 30
  3701.3  242.45  3731.2  241.92  3747.7  239.25  3765.7  240.32  3770.9  239.19
  3799.5  239.97    3959  233.16  4120.9  230.38  4172.8  231.18    4235  229.36
  4286.8   229.5  4380.1  231.26  4414.4  230.11  4454.1  230.85  4494.1  229.41
  4535.6  230.62  4835.5  229.39  4848.4  229.36  4911.3  228.98  4918.4  226.86
  4925.5  227.62    4952  226.21  4996.2  227.09  5017.4  229.24  5045.7  228.29
  5123.4  232.91  5144.7  231.89  5293.2   237.1  5360.5  241.17  5601.5  247.98
#Mann= 5 ,-1 , 0
  3701.3     .11       0  4835.5     .15       0  4848.4     .11       0
  4911.3     .06       0  5017.4     .11       0
Bank Sta=4911.3,5017.4
XS Rating Curve= 0 ,0
Exp/Cntr=0.3,0.1

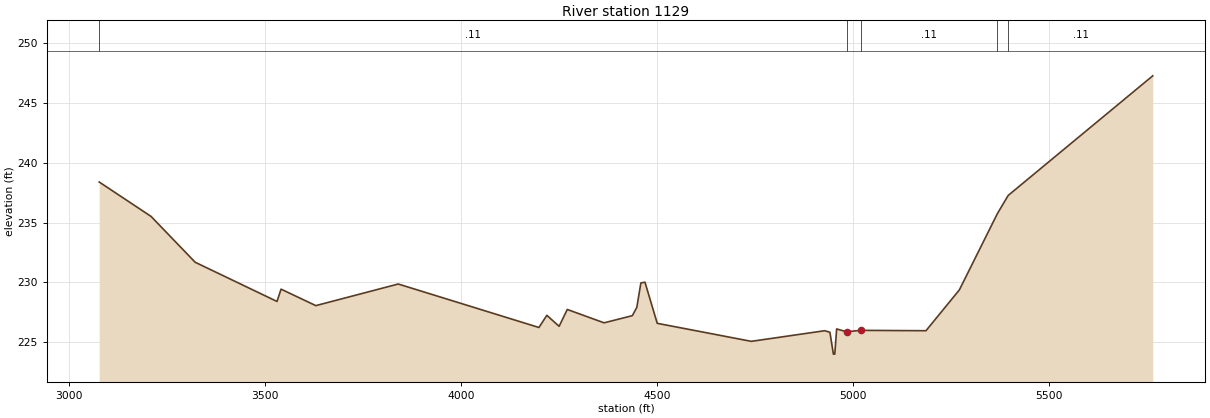
Type RM Length L Ch R = 1 ,1129    ,0,0,0
BEGIN DESCRIPTION:
CCLC 050 1.0
END DESCRIPTION:
XS GIS Cut Line= 4
      3720872.61     10126332.68      3719216.35     10125843.09
      3719105.86     10126143.39      3719325.72     10126744.13
#Sta/Elev= 30
  3076.7  238.39  3208.9  235.51  3321.5  231.67  3530.1  228.39  3540.5  229.42
  3629.1  228.04  3839.3  229.85  4198.1  226.21  4218.3  227.23  4249.6  226.31
  4270.4  227.72  4364.3   226.6  4436.3   227.2  4447.7  227.89  4458.1  229.94
  4468.6     230  4499.8  226.56  4739.7  225.05    4927  225.94  4940.2  225.81
  4949.1  223.98  4952.6  223.98  4957.4  226.09  4982.6  225.85  5018.4  225.97
  5185.2  225.94  5270.4  229.36  5367.4  235.75    5395  237.27  5763.5  247.28
#Mann= 5 ,-1 , 0
  3076.7     .11       0  4982.6     .06       0  5018.4     .11       0
  5367.4     .17       0    5395     .11       0
Bank Sta=4982.6,5018.4
XS Rating Curve= 0 ,0
Exp/Cntr=0.3,0.1

Chan Stop Cuts=-1
Use User Specified Reach Order=0
Composite Channel Slope=5