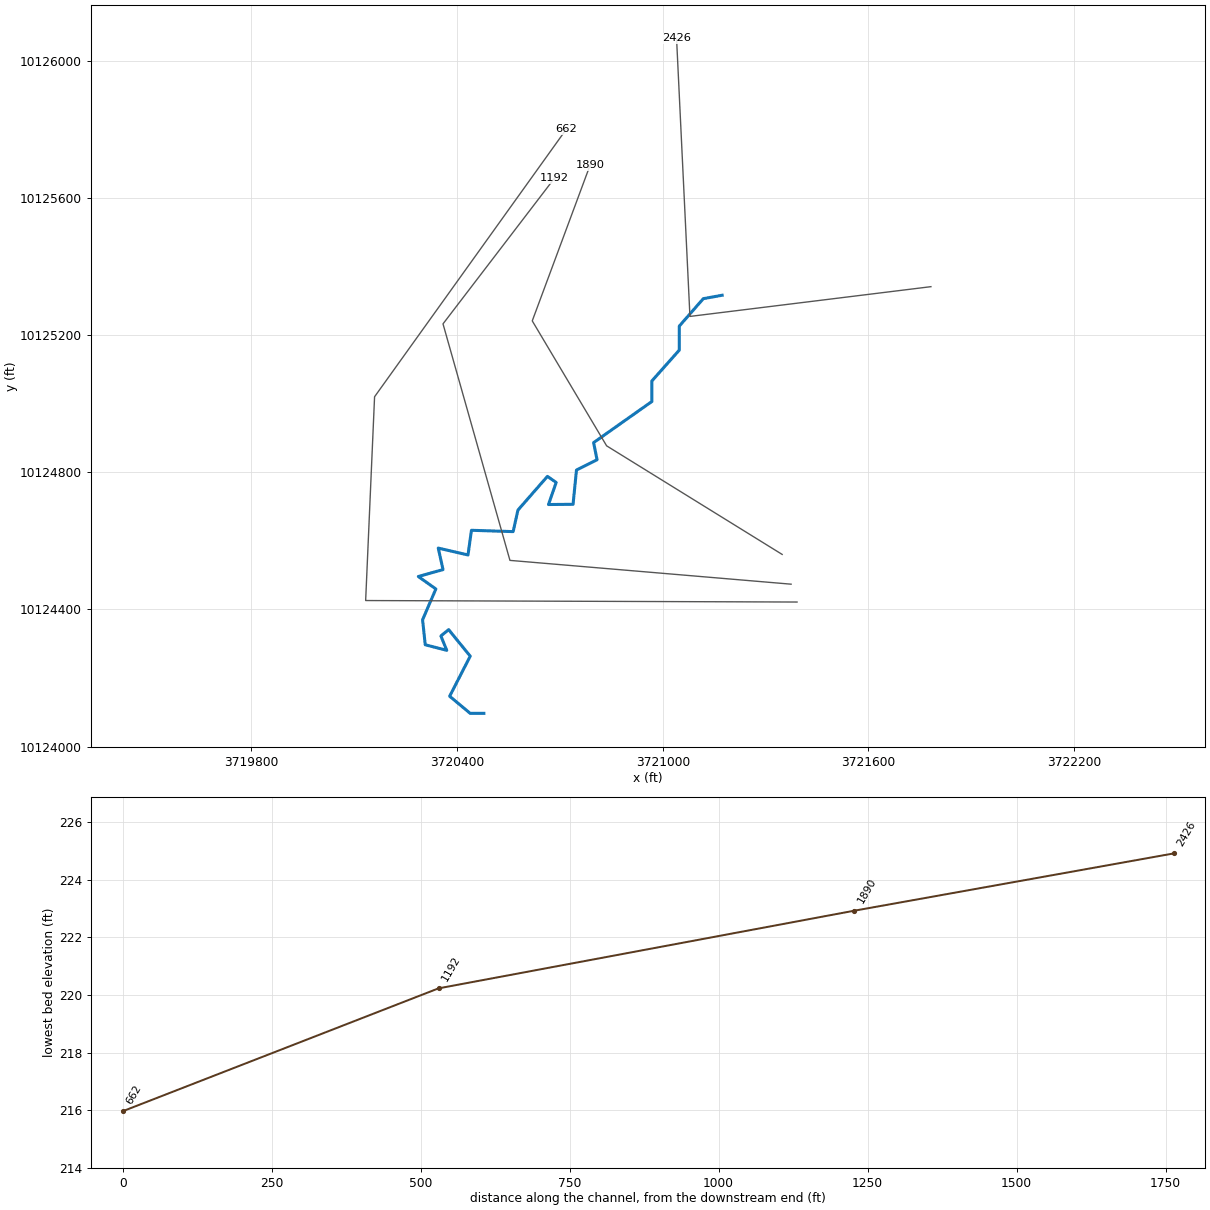
--- CCLC 051.prj (project) ---

Proj Title=CCLC 051 Base Level Engineering
Current Plan=p01
Default Exp/Contr=0.3,0.1
English Units
Geom File=g01
Flow File=f01
Flow File=f02
Plan File=p01
Y Axis Title=Elevation
X Axis Title(PF)=Main Channel Distance
X Axis Title(XS)=Station
BEGIN DESCRIPTION:
CCLC 051
END DESCRIPTION:
DSS Export Rating Curves= 0
DSS Export Rating Curve Sorted= 0
DSS Export Volume Flow Curves= 0
DXF OffsetX= 0
DXF OffsetY= 0
DXF ScaleX= 1
DXF ScaleY= 10

--- CCLC 051.p01 (plan) ---

Plan Title=Multiple Run
Short Identifier=Multiple
Geom File=g01
Flow File=f01
Subcritical Flow
K Sum by GR= 0
Std Step Tol= 0.01
Critical Tol= 0.01
Num of Std Step Trials= 20
Max Error Tol= 0.3
Flow Tol Ratio= 0.001
Split Flow NTrial= 30
Split Flow Tol= 0.02
Split Flow Ratio= 0.02
Log Output Level= 0
Friction Slope Method= 1
Unsteady Friction Slope Method= 2
Unsteady Bridges Friction Slope Method= 1
Parabolic Critical Depth
Global Vel Dist=  1 , 1 , 1
Global Log Level= 0
CheckData=True
Encroach Param= -1, 0, 0, 0
BEGIN DESCRIPTION:
Multiple Run
END DESCRIPTION:

--- CCLC 051.f01 (steady flow) ---

Flow Title=Multiple
Program Version=4.10
Number of Profiles= 7
Profile Names=10-year,25-year,50-year,1pct_min,100-year,1pct_plu,500-year
River Rch & RM=CCLC 051,Reach-1         ,2426
     594     803    1083     481    1453    4388    2702
Boundary for River Rch & Prof#=CCLC 051,Reach-1         , 1
Up Type= 0
Dn Type= 3
Dn Slope=0.005
Boundary for River Rch & Prof#=CCLC 051,Reach-1         , 2
Up Type= 0
Dn Type= 3
Dn Slope=0.005
Boundary for River Rch & Prof#=CCLC 051,Reach-1         , 3
Up Type= 0
Dn Type= 3
Dn Slope=0.005
Boundary for River Rch & Prof#=CCLC 051,Reach-1         , 4
Up Type= 0
Dn Type= 3
Dn Slope=0.005
Boundary for River Rch & Prof#=CCLC 051,Reach-1         , 5
Up Type= 0
Dn Type= 3
Dn Slope=0.005
Boundary for River Rch & Prof#=CCLC 051,Reach-1         , 6
Up Type= 0
Dn Type= 3
Dn Slope=0.005
Boundary for River Rch & Prof#=CCLC 051,Reach-1         , 7
Up Type= 0
Dn Type= 3
Dn Slope=0.005
DSS Import GetInterval= 0
DSS Import GetPeak= 0
DSS Import FillOption= 0

--- CCLC 051.f02 (steady flow) ---

Flow Title=Orig_BLE_Flows
Program Version=4.10
Number of Profiles= 7
Profile Names=10-year,25-year,50-year,1pct_min,100-year,1pct_plu,500-year
River Rch & RM=CCLC 051,Reach-1         ,2426
     594     787     942     370    1118    3376    1571
Boundary for River Rch & Prof#=CCLC 051,Reach-1         , 1
Up Type= 0
Dn Type= 3
Dn Slope=0.005
Boundary for River Rch & Prof#=CCLC 051,Reach-1         , 2
Up Type= 0
Dn Type= 3
Dn Slope=0.005
Boundary for River Rch & Prof#=CCLC 051,Reach-1         , 3
Up Type= 0
Dn Type= 3
Dn Slope=0.005
Boundary for River Rch & Prof#=CCLC 051,Reach-1         , 4
Up Type= 0
Dn Type= 3
Dn Slope=0.005
Boundary for River Rch & Prof#=CCLC 051,Reach-1         , 5
Up Type= 0
Dn Type= 3
Dn Slope=0.005
Boundary for River Rch & Prof#=CCLC 051,Reach-1         , 6
Up Type= 0
Dn Type= 3
Dn Slope=0.005
Boundary for River Rch & Prof#=CCLC 051,Reach-1         , 7
Up Type= 0
Dn Type= 3
Dn Slope=0.005
DSS Import GetInterval= 0
DSS Import GetPeak= 0
DSS Import FillOption= 0

--- CCLC 051.g01 (geometry) ---

Geom Title=Existing Conditions
Program Version=4.10

River Reach=CCLC 051        ,Reach-1
Reach XY= 30
      3721173.23     10125316.84      3721118.23     10125306.84
      3721048.23     10125226.84      3721048.23     10125156.84
      3720968.23     10125066.84      3720968.23     10125006.84
      3720798.23     10124886.84      3720808.23     10124836.84
      3720748.23     10124806.84      3720738.23     10124706.84
      3720666.52     10124706.21        3720689.     10124770.53
      3720663.42     10124788.35      3720577.41     10124689.93
      3720563.46     10124627.16      3720441.79     10124631.04
      3720431.72     10124558.97      3720344.92     10124579.11
      3720358.87     10124516.34       3720286.8      10124496.2
      3720337.95     10124459.77       3720299.2     10124369.88
      3720306.95     10124297.03      3720369.72     10124280.76
      3720352.67     10124322.61      3720375.15     10124341.21
      3720438.23      10124263.8      3720378.23     10124146.84
      3720438.23     10124096.84      3720478.23     10124096.84

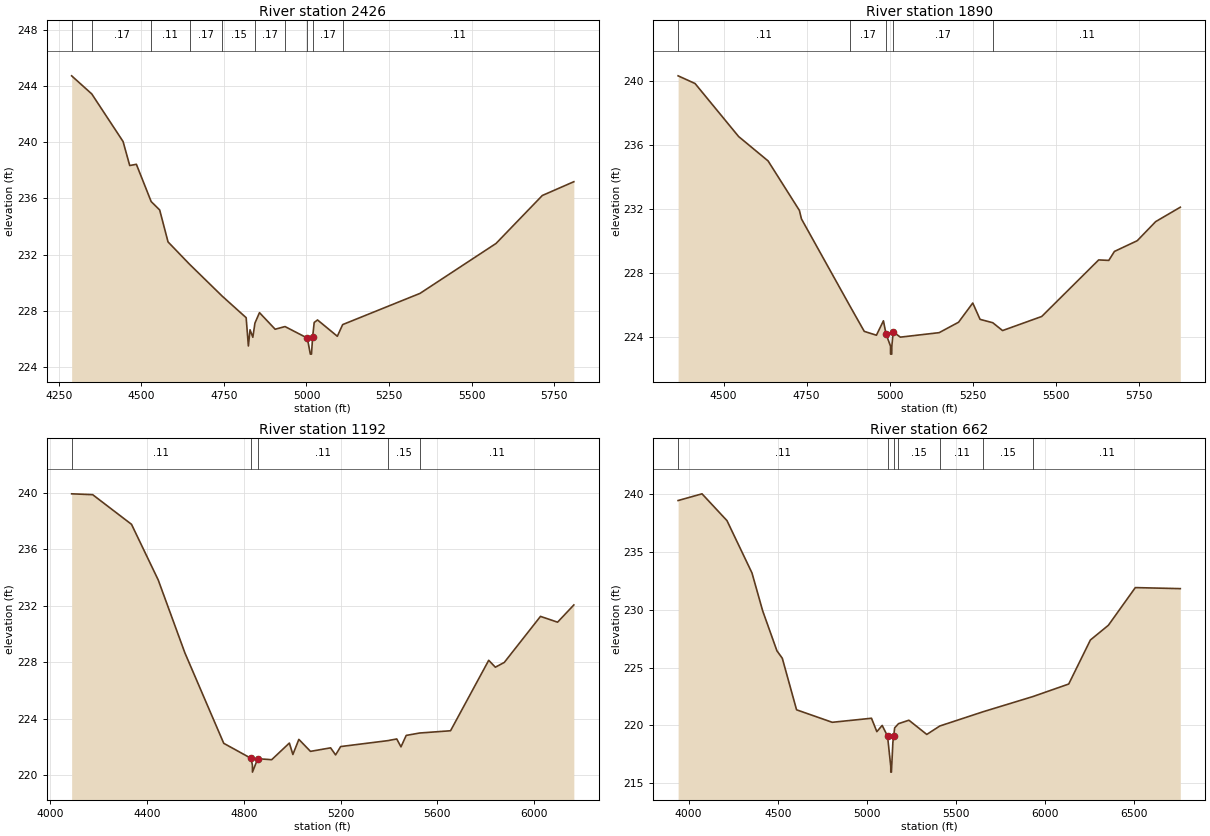
Type RM Length L Ch R = 1 ,2426    ,536,536,536
BEGIN DESCRIPTION:
CCLC 051 4.0
END DESCRIPTION:
XS GIS Cut Line= 3
      3721782.42     10125341.85      3721079.27     10125255.04
      3721040.22     10126066.42
#Sta/Elev= 30
  4288.8  244.71  4349.8  243.42  4444.5  240.04  4464.7  238.33  4484.8  238.42
  4529.6  235.77  4555.4  235.17  4580.7   232.9  4645.9  231.31  4744.9  229.04
  4817.3  227.51    4824   225.5    4829  226.65  4837.5  226.12  4843.8  227.12
  4857.6  227.87  4905.1  226.69    4935  226.88  5002.5  226.06  5011.6  224.92
  5015.1  224.92 5018.59226.1397  5023.3  227.17  5033.4  227.35  5093.4  226.19
  5109.5  227.02  5343.8  229.24    5574  232.79  5714.1   236.2  5809.6  237.18
#Mann= 10 ,-1 , 0
  4288.8     .11       0  4349.8     .17       0  4529.6     .11       0
  4645.9     .17       0  4744.9     .15       0  4843.8     .17       0
    4935     .15       0  5002.5     .09       0 5018.59     .17       0
  5109.5     .11       0
Bank Sta=5002.5,5018.59
XS Rating Curve= 0 ,0
Exp/Cntr=0.3,0.1

Type RM Length L Ch R = 1 ,1890    ,698,698,698
BEGIN DESCRIPTION:
CCLC 051 3.0
END DESCRIPTION:
XS GIS Cut Line= 4
      3721348.36      10124560.6      3720836.22     10124877.44
       3720619.2     10125242.02      3720788.18     10125696.95
#Sta/Elev= 30
  4363.2   240.3  4414.2  239.82  4545.4  236.51    4634  234.99  4728.3   231.9
  4734.5  231.37  4881.9  225.88  4923.6  224.35  4960.2  224.11  4981.3  225.01
  4989.3  224.17  5002.6  223.43  5002.8  222.93  5006.3  222.93  5006.6  223.43
  5010.7  224.32  5032.2  223.99    5149  224.27  5207.4  224.92  5250.2  226.12
  5272.2   225.1  5310.4  224.89  5339.9   224.4  5457.8  225.28  5629.3  228.81
  5659.7  228.78  5676.7  229.34  5745.4  230.01  5800.8   231.2    5875   232.1
#Mann= 5 ,-1 , 0
  4363.2     .11       0  4881.9     .17       0  4989.3     .09       0
  5010.7     .17       0  5310.4     .11       0
Bank Sta=4989.3,5010.7
XS Rating Curve= 0 ,0
Exp/Cntr=0.3,0.1

Type RM Length L Ch R = 1 ,1192    ,530,530,530
BEGIN DESCRIPTION:
Mapping XS 7b7553f5
END DESCRIPTION:
XS GIS Cut Line= 4
      3721374.44     10124473.79       3720554.1     10124543.23
      3720358.79     10125233.34      3720684.31     10125658.68
#Sta/Elev= 30
  4087.9  239.94  4174.8  239.88  4335.4  237.78  4445.8  233.84  4556.2  228.67
  4716.7  222.27  4829.2  221.21  4835.2  220.73  4835.4  220.23  4857.2  221.18
  4914.9  221.11    4988  222.29  5002.5  221.48  5027.2  222.55  5075.2   221.7
  5158.4  221.95  5179.1  221.45  5199.9  222.04  5395.1  222.46  5431.8  222.58
  5449.4  222.02    5471  222.83  5526.4     223  5654.3  223.16  5812.1  228.15
  5839.6  227.66  5876.5     228  6026.1  231.26  6096.8  230.85    6164  232.07
#Mann= 5 ,-1 , 0
  4087.9     .11       0  4829.2     .06       0  4857.2     .11       0
  5395.1     .15       0  5526.4     .11       0
Bank Sta=4829.2,4857.2
XS Rating Curve= 0 ,0
Exp/Cntr=0.3,0.1

Type RM Length L Ch R = 1 ,662     ,0,0,0
BEGIN DESCRIPTION:
CCLC 051 2.0
END DESCRIPTION:
XS GIS Cut Line= 4
      3721391.81     10124421.71      3720133.09     10124426.05
      3720159.13     10125020.67      3720719.04     10125801.94
#Sta/Elev= 30
  3941.7  239.45  4075.7  240.03  4215.7  237.71  4355.7  233.19  4415.7  229.91
  4495.7  226.45  4525.7  225.81  4605.7  221.35  4805.7  220.27  5025.7  220.62
  5055.7  219.46  5085.7     220  5115.7  219.07  5133.7  216.46  5133.9  215.96
  5137.4  215.96  5145.7  218.55 5149.96219.0782  5155.7  219.79    5177  220.15
  5235.5  220.45  5335.6  219.22  5408.7  219.95    5653  221.19  5929.4  222.49
  6131.3  223.58  6252.9  227.39  6353.6  228.66  6504.7  231.92  6756.8  231.83
#Mann= 7 ,-1 , 0
  3941.7     .11       0  5115.7     .06       0 5149.96     .11       0
    5177     .15       0  5408.7     .11       0    5653     .15       0
  5929.4     .11       0
Bank Sta=5115.7,5149.96
XS Rating Curve= 0 ,0
Exp/Cntr=0.3,0.1

Chan Stop Cuts=-1
Use User Specified Reach Order=0
Composite Channel Slope=5