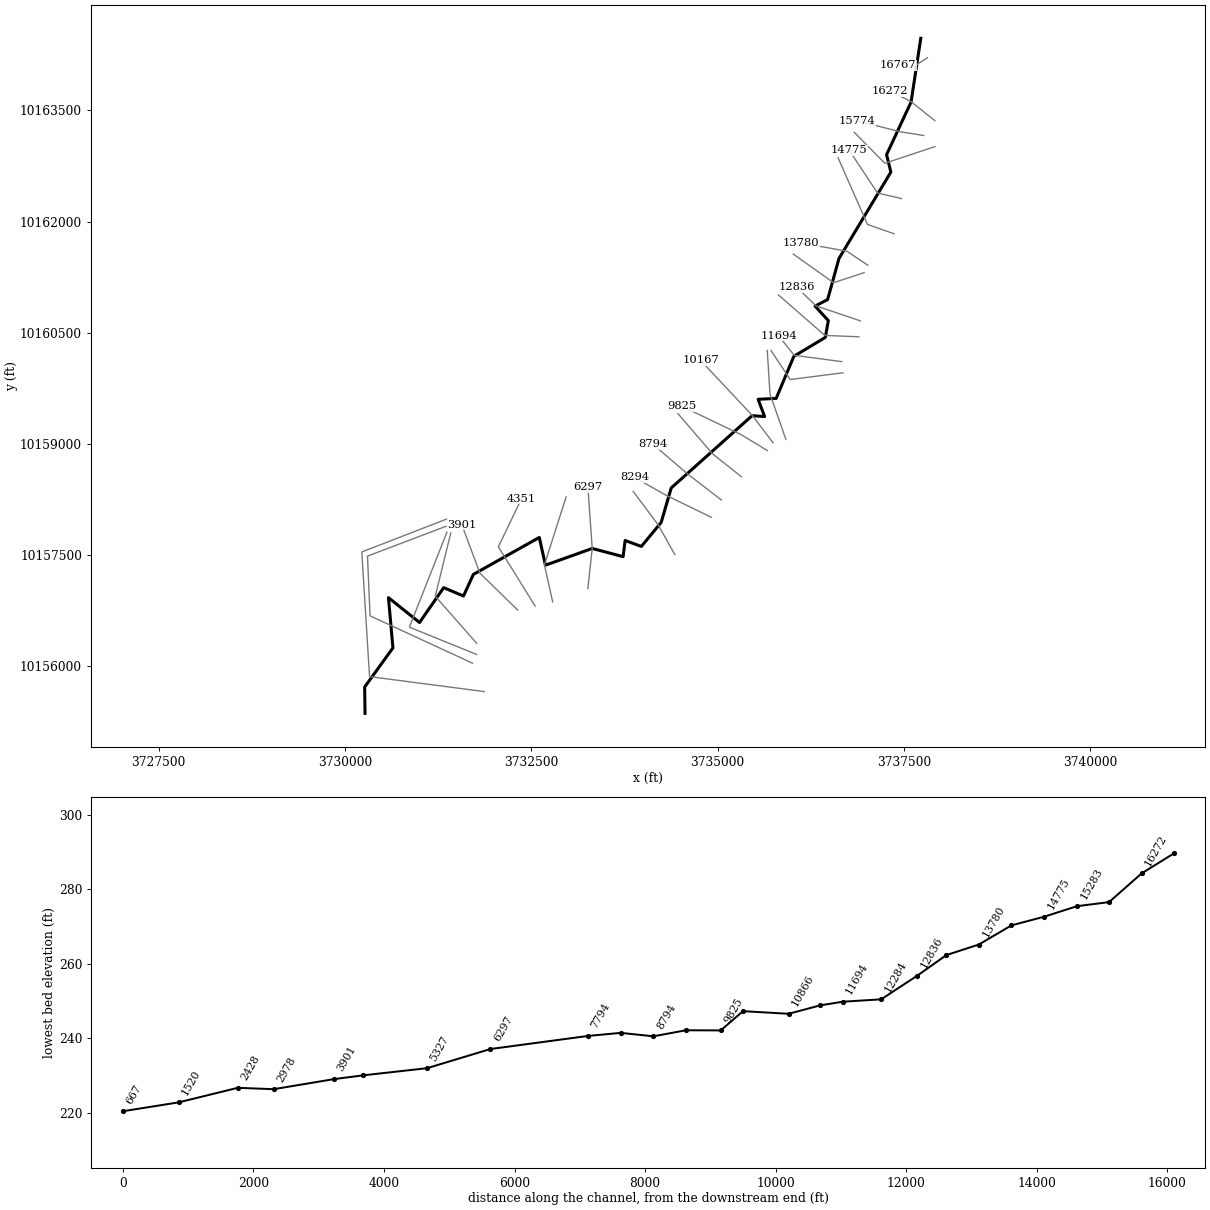
--- CCLC 058.prj (project) ---

Proj Title=CCLC 058 Base Level Engineering
Current Plan=p01
Default Exp/Contr=0.3,0.1
English Units
Geom File=g01
Flow File=f01
Flow File=f02
Plan File=p01
Y Axis Title=Elevation
X Axis Title(PF)=Main Channel Distance
X Axis Title(XS)=Station
BEGIN DESCRIPTION:
CCLC 058
END DESCRIPTION:
DSS Export Rating Curves= 0
DSS Export Rating Curve Sorted= 0
DSS Export Volume Flow Curves= 0
DXF OffsetX= 0
DXF OffsetY= 0
DXF ScaleX= 1
DXF ScaleY= 10

--- CCLC 058.p01 (plan) ---

Plan Title=Multiple Run
Short Identifier=Multiple
Geom File=g01
Flow File=f01
Subcritical Flow
K Sum by GR= 0
Std Step Tol= 0.01
Critical Tol= 0.01
Num of Std Step Trials= 20
Max Error Tol= 0.3
Flow Tol Ratio= 0.001
Split Flow NTrial= 30
Split Flow Tol= 0.02
Split Flow Ratio= 0.02
Log Output Level= 0
Friction Slope Method= 1
Unsteady Friction Slope Method= 2
Unsteady Bridges Friction Slope Method= 1
Parabolic Critical Depth
Global Vel Dist=  1 , 1 , 1
Global Log Level= 0
CheckData=True
Encroach Param= -1, 0, 0, 0
BEGIN DESCRIPTION:
Multiple Run
END DESCRIPTION:

--- CCLC 058.f01 (steady flow) ---

Flow Title=Multiple
Program Version=4.10
Number of Profiles= 7
Profile Names=10-year,25-year,50-year,1pct_min,100-year,1pct_plu,500-year
River Rch & RM=CCLC 058,Reach-1         ,16767
    1125    1590    2211    1012    3055    9226    6029
River Rch & RM=CCLC 058,Reach-1         ,10167
    1143    1597    2203     997    3012    9096    5831
River Rch & RM=CCLC 058,Reach-1         ,1520
    1335    1874    2593    1176    3552   10727    6902
Boundary for River Rch & Prof#=CCLC 058,Reach-1         , 1
Up Type= 0
Dn Type= 3
Dn Slope=0.005
Boundary for River Rch & Prof#=CCLC 058,Reach-1         , 2
Up Type= 0
Dn Type= 3
Dn Slope=0.005
Boundary for River Rch & Prof#=CCLC 058,Reach-1         , 3
Up Type= 0
Dn Type= 3
Dn Slope=0.005
Boundary for River Rch & Prof#=CCLC 058,Reach-1         , 4
Up Type= 0
Dn Type= 3
Dn Slope=0.005
Boundary for River Rch & Prof#=CCLC 058,Reach-1         , 5
Up Type= 0
Dn Type= 3
Dn Slope=0.005
Boundary for River Rch & Prof#=CCLC 058,Reach-1         , 6
Up Type= 0
Dn Type= 3
Dn Slope=0.005
Boundary for River Rch & Prof#=CCLC 058,Reach-1         , 7
Up Type= 0
Dn Type= 3
Dn Slope=0.005
DSS Import GetInterval= 0
DSS Import GetPeak= 0
DSS Import FillOption= 0

--- CCLC 058.f02 (steady flow) ---

Flow Title=Orig_BLE_Flows
Program Version=4.10
Number of Profiles= 7
Profile Names=10-year,25-year,50-year,1pct_min,100-year,1pct_plu,500-year
River Rch & RM=CCLC 058,Reach-1         ,16767
    1125    1559    1923     778    2350    7097    3505
River Rch & RM=CCLC 058,Reach-1         ,10167
    1143    1566    1916     767    2317    6998    3390
River Rch & RM=CCLC 058,Reach-1         ,1520
    1335    1837    2255     905    2732    8251    4013
Boundary for River Rch & Prof#=CCLC 058,Reach-1         , 1
Up Type= 0
Dn Type= 3
Dn Slope=0.005
Boundary for River Rch & Prof#=CCLC 058,Reach-1         , 2
Up Type= 0
Dn Type= 3
Dn Slope=0.005
Boundary for River Rch & Prof#=CCLC 058,Reach-1         , 3
Up Type= 0
Dn Type= 3
Dn Slope=0.005
Boundary for River Rch & Prof#=CCLC 058,Reach-1         , 4
Up Type= 0
Dn Type= 3
Dn Slope=0.005
Boundary for River Rch & Prof#=CCLC 058,Reach-1         , 5
Up Type= 0
Dn Type= 3
Dn Slope=0.005
Boundary for River Rch & Prof#=CCLC 058,Reach-1         , 6
Up Type= 0
Dn Type= 3
Dn Slope=0.005
Boundary for River Rch & Prof#=CCLC 058,Reach-1         , 7
Up Type= 0
Dn Type= 3
Dn Slope=0.005
DSS Import GetInterval= 0
DSS Import GetPeak= 0
DSS Import FillOption= 0

--- CCLC 058.g01 (geometry) ---

Geom Title=Existing Conditions
Program Version=4.10

River Reach=CCLC 058        ,Reach-1
Reach XY= 30
      3737728.23     10164471.84      3737597.56     10163611.91
      3737269.07     10162902.56      3737326.51     10162667.67
      3736629.83     10161501.59      3736477.61     10160948.28
      3736309.09     10160860.24      3736487.21     10160664.34
      3736446.63     10160437.62      3736024.59     10160183.11
      3735787.08     10159615.31      3735545.15      10159603.5
      3735631.88     10159370.56      3735463.43     10159381.84
      3734378.51     10158407.68      3734243.64     10157942.91
      3733977.52     10157618.54      3733759.78     10157698.81
      3733732.28     10157480.73      3733317.87     10157591.25
      3732690.09     10157365.56      3732607.45     10157739.86
      3731722.66     10157241.19      3731589.73     10156949.67
       3731324.3     10157062.45      3730999.98     10156592.57
       3730582.8     10156927.78      3730642.92     10156250.08
      3730263.48      10155722.3      3730268.23     10155366.84

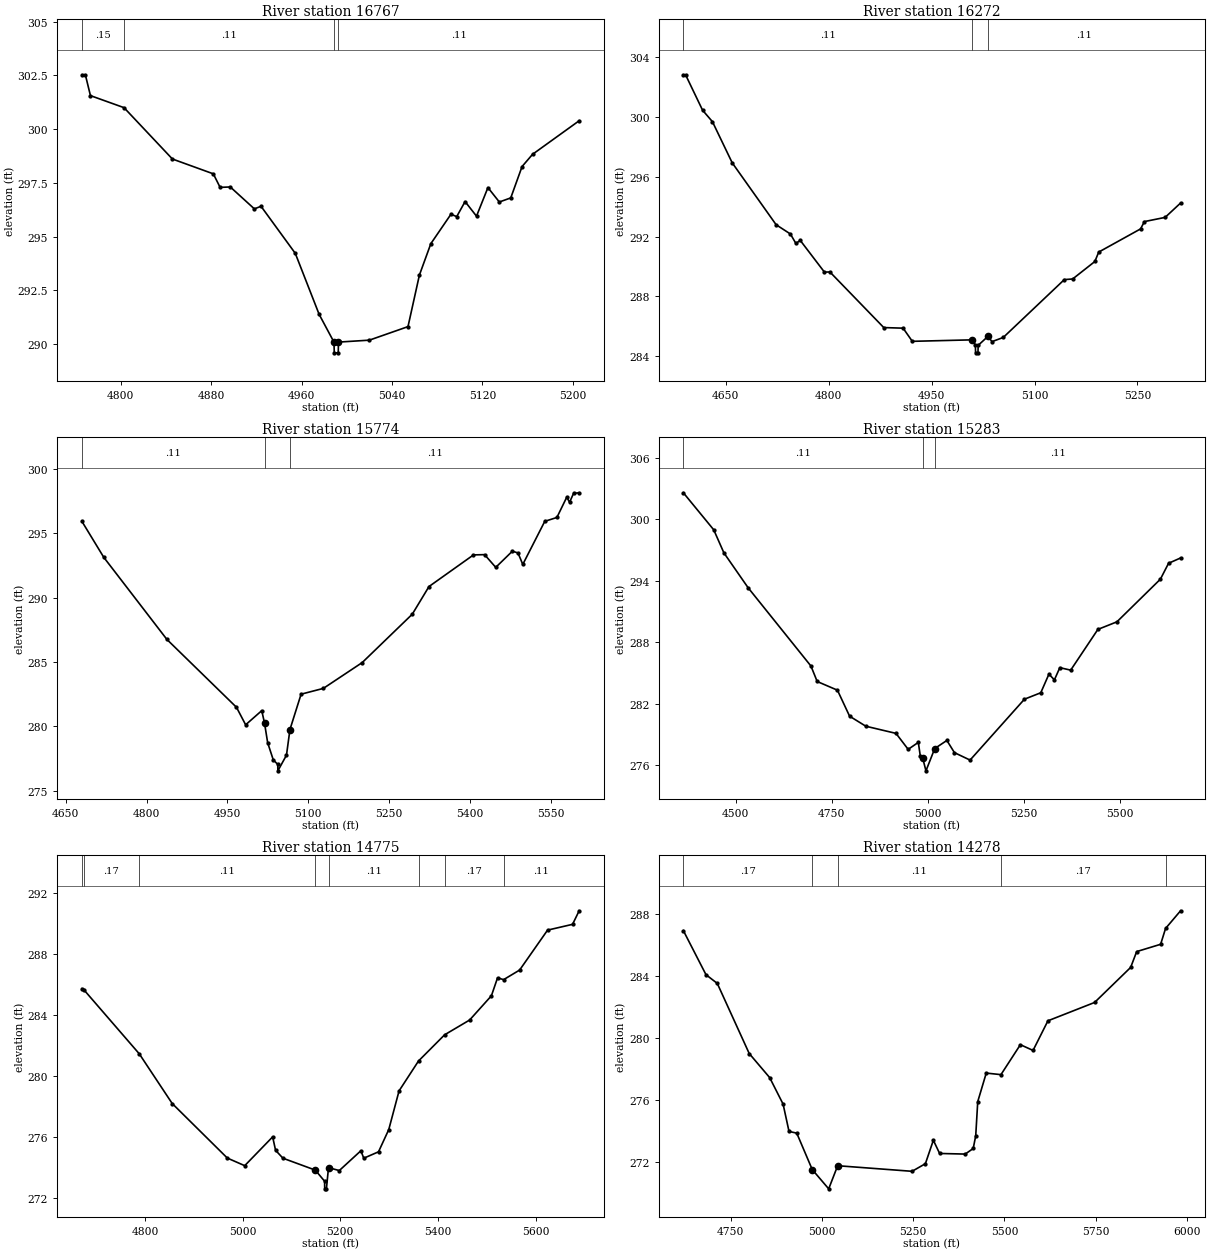
Type RM Length L Ch R = 1 ,16767   ,495,495,495
BEGIN DESCRIPTION:
CCLC 058 26.0
END DESCRIPTION:
XS GIS Cut Line= 3
      3737817.83     10164211.06      3737621.47     10164083.23
      3737417.87     10164111.07
#Sta/Elev= 30
  4765.7  302.53  4768.7  302.53  4773.2  301.56  4802.9     301  4845.7  298.61
  4881.9  297.92  4887.9  297.29  4896.9  297.31  4918.2  296.29  4924.1  296.41
  4954.4  294.22  4975.5  291.38  4988.6  290.09  4988.9  289.59  4992.4  289.59
  4992.6  290.09  5019.9  290.18  5054.1  290.81  5064.2  293.21  5074.3  294.67
  5092.1  296.04  5097.2  295.93  5104.6  296.63  5114.7  295.95  5124.8  297.28
  5134.9  296.61    5145   296.8    5155  298.26  5164.3  298.83  5205.5  300.39
#Mann= 4 ,-1 , 0
  4765.7     .15       0  4802.9     .11       0  4988.6     .06       0
  4992.6     .11       0
Bank Sta=4988.6,4992.6
XS Rating Curve= 0 ,0
Exp/Cntr=0.3,0.1

Type RM Length L Ch R = 1 ,16272   ,498,498,498
BEGIN DESCRIPTION:
CCLC 058 25.0
END DESCRIPTION:
XS GIS Cut Line= 3
      3737917.82     10163361.09      3737596.32     10163618.57
      3737317.86     10163761.07
#Sta/Elev= 30
  4588.1  302.82  4591.3  302.82  4616.1  300.45  4630.5  299.68  4659.3  296.93
  4723.3  292.79  4744.1  292.17  4752.1  291.54  4758.5  291.74  4793.7  289.62
  4801.7  289.63  4880.2  285.91  4908.4  285.87  4921.8  284.99  5009.5  285.09
  5013.8  284.72    5014  284.22  5017.5  284.22  5017.8  284.72    5032  285.32
    5038  284.97  5054.4  285.25  5143.4  289.12  5155.5  289.16  5187.9  290.33
  5193.5  290.96  5254.5  292.51  5260.1     293  5290.3  293.28  5312.8  294.24
#Mann= 3 , 0 , 0
  4588.1     .11       0  5009.5     .06       0    5032     .11       0
Bank Sta=5009.5,5032
XS Rating Curve= 0 ,0
Exp/Cntr=0.3,0.1

Type RM Length L Ch R = 1 ,15774   ,491,491,491
BEGIN DESCRIPTION:
CCLC 058 24.0
END DESCRIPTION:
XS GIS Cut Line= 3
      3737767.81     10163161.08      3737452.02     10163211.55
      3736867.85     10163361.07
#Sta/Elev= 30
  4680.2  295.92  4720.7  293.13  4837.8  286.75    4967  281.47    4984  280.11
  5013.9  281.21    5019  280.25  5024.9  278.71  5035.3  277.38  5043.6  277.03
  5043.8  276.53  5059.8  277.75  5066.2  279.74  5086.9  282.49  5128.2  282.94
  5200.4  284.95  5293.3  288.71  5324.3  290.86  5406.9  293.32  5427.5  293.34
  5448.2  292.35  5479.1  293.61  5489.5  293.47  5498.4  292.58  5539.2  295.93
  5561.7  296.23    5580  297.81  5585.2  297.41  5592.7  298.11    5603  298.15
#Mann= 3 , 0 , 0
  4680.2     .11       0    5019     .06       0  5066.2     .11       0
Bank Sta=5019,5066.2
XS Rating Curve= 0 ,0
Exp/Cntr=0.3,0.1

Type RM Length L Ch R = 1 ,15283   ,508,508,508
BEGIN DESCRIPTION:
CCLC 058 23.0
END DESCRIPTION:
XS GIS Cut Line= 3
       3737917.9     10163011.09      3737245.78     10162786.63
      3736836.04     10163203.32
#Sta/Elev= 30
  4363.8  302.61  4442.8  298.99  4469.2  296.74  4532.4  293.32  4695.6  285.68
  4711.8  284.17  4764.5  283.32  4796.1  280.78  4838.3   279.8  4916.8   279.1
  4948.4  277.54  4974.8  278.22    4980  276.88  4985.9  276.73  4994.7  275.44
  5017.5  277.62  5049.1  278.41  5068.7  277.22  5109.4  276.49  5250.8  282.44
  5293.3  283.07  5314.5  284.89  5328.7  284.33  5342.8  285.52  5371.1  285.28
  5441.8  289.26  5491.3     290  5604.4  294.17  5625.6  295.72  5656.8  296.24
#Mann= 3 , 0 , 0
  4363.8     .11       0  4985.9     .06       0  5017.5     .11       0
Bank Sta=4985.9,5017.5
XS Rating Curve= 0 ,0
Exp/Cntr=0.3,0.1

Type RM Length L Ch R = 1 ,14775   ,497,497,497
BEGIN DESCRIPTION:
CCLC 058 22.0
END DESCRIPTION:
XS GIS Cut Line= 3
      3737467.81     10162311.08      3737147.49     10162385.72
      3736767.86     10162961.06
#Sta/Elev= 30
  4671.1  285.72  4674.6  285.67  4788.5  281.45  4855.9  278.19  4968.8  274.61
  5004.4  274.11  5061.6     276  5067.6  275.12  5082.7   274.6  5148.9  273.82
    5168  273.09  5168.2  272.59  5171.7  272.59    5176  273.98  5198.1  273.79
  5242.3  275.09  5248.2   274.6  5278.4  275.02  5299.4  276.48  5320.5  279.02
  5360.3  280.98  5413.8   282.7    5465  283.67  5509.6  285.26  5522.2  286.44
  5534.6  286.32  5567.4  286.95  5624.6  289.57  5675.8  289.95  5689.3  290.84
#Mann= 8 ,-1 , 0
  4671.1     .15       0  4674.6     .17       0  4788.5     .11       0
  5148.9     .06       0    5176     .11       0  5360.3     .11       0
  5413.8     .17       0  5534.6     .11       0
Bank Sta=5148.9,5176
XS Rating Curve= 0 ,0
Exp/Cntr=0.3,0.1

Type RM Length L Ch R = 1 ,14278   ,498,498,498
BEGIN DESCRIPTION:
CCLC 058 21.0
END DESCRIPTION:
XS GIS Cut Line= 3
      3737370.77     10161835.24      3737012.82      10161961.6
      3736617.84      10162861.1
#Sta/Elev= 30
  4620.4  286.93  4682.4  284.09  4713.3  283.53  4800.8  279.01  4856.8  277.46
  4893.6  275.75  4909.8  273.99    4931  273.88  4973.5  271.53  5018.5  270.29
  5043.1  271.78  5246.9  271.42  5283.4  271.91  5305.2  273.42  5322.4  272.57
  5392.5  272.53  5414.4  272.89  5421.3  273.71  5426.8  275.91  5450.1  277.75
  5490.4  277.65  5543.6  279.58  5578.3  279.21  5619.1  281.12  5746.8   282.3
  5845.7  284.56  5862.2  285.58  5927.8  286.05  5941.3  287.07  5982.4  288.21
#Mann= 5 ,-1 , 0
  4620.4     .17       0  4973.5     .06       0  5043.1     .11       0
  5490.4     .17       0  5941.3     .11       0
Bank Sta=4973.5,5043.1
XS Rating Curve= 0 ,0
Exp/Cntr=0.3,0.1

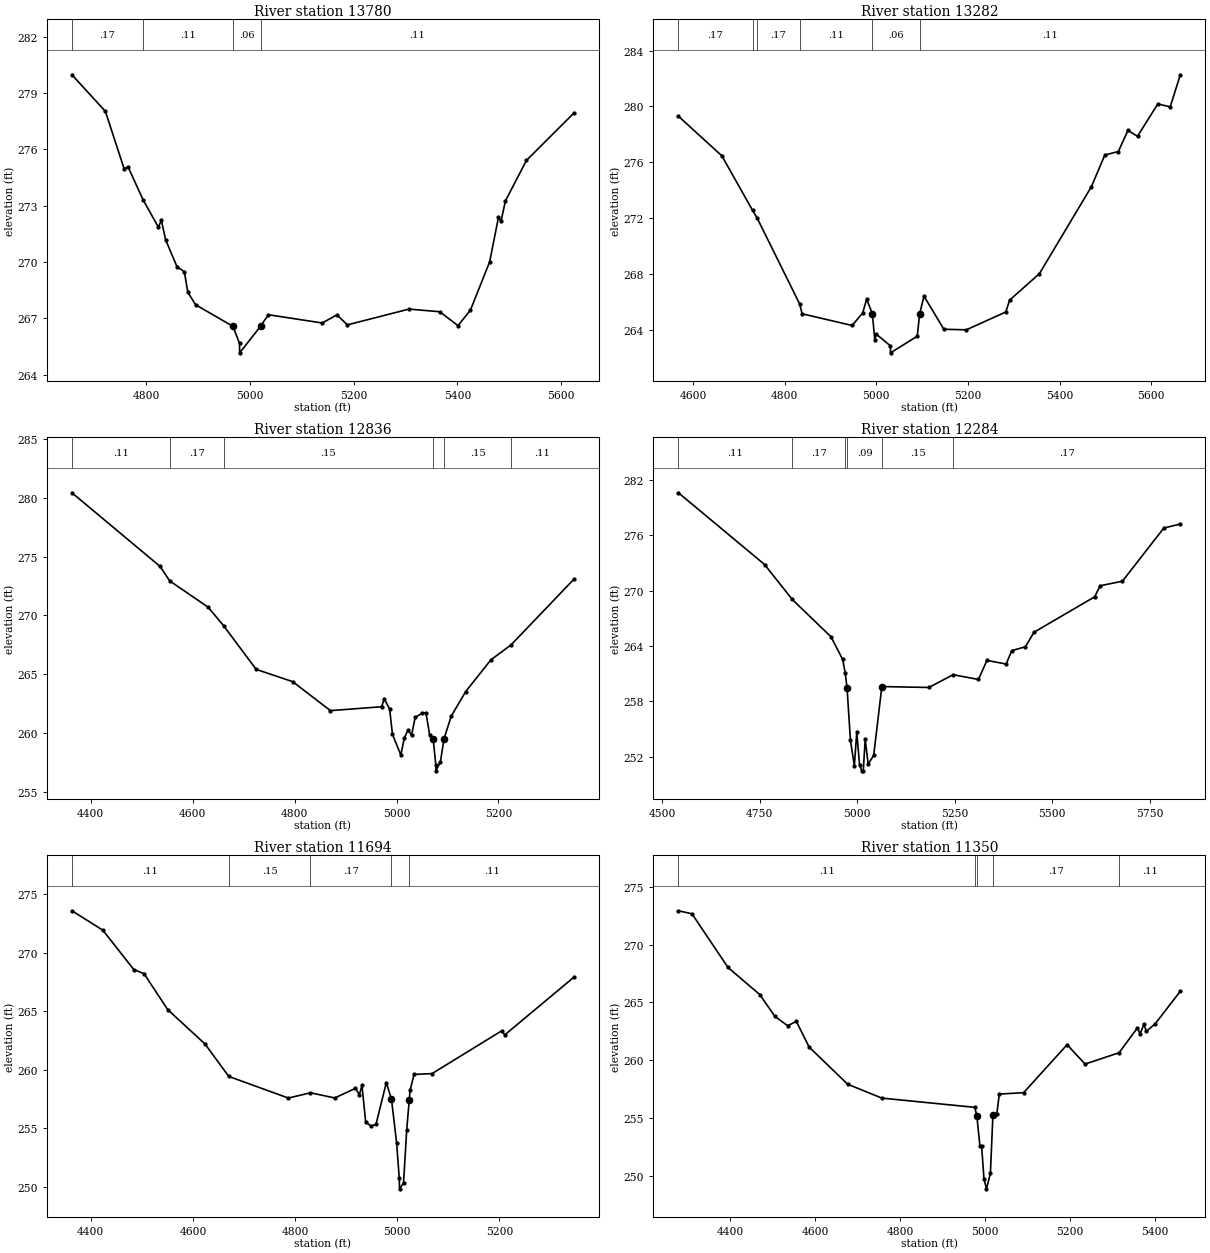
Type RM Length L Ch R = 1 ,13780   ,498,498,498
BEGIN DESCRIPTION:
CCLC 058 20.0
END DESCRIPTION:
XS GIS Cut Line= 3
      3737017.82     10161411.09      3736732.86     10161602.36
      3736117.89     10161711.06
#Sta/Elev= 30
  4656.8  279.97  4721.3  278.02  4757.3  274.97  4765.2  275.05  4793.8  273.32
  4823.3  271.86  4829.3  272.21  4837.4  271.18  4859.3  269.75  4873.5  269.48
  4880.3  268.38  4895.3  267.72  4967.3  266.57  4979.9  265.66  4980.2  265.16
  5020.8  266.59  5035.5  267.19  5139.2  266.75  5167.6  267.18  5187.9  266.65
  5306.6  267.49  5365.8  267.35  5401.1  266.61    5425  267.43  5462.1     270
  5479.1  272.37  5484.2  272.18  5492.5  273.25  5533.1  275.41  5624.5  277.93
#Mann= 4 ,-1 , 0
  4656.8     .17       0  4793.8     .11       0  4967.3     .06       0
  5020.8     .11       0
Bank Sta=4967.3,5020.8
XS Rating Curve= 0 ,0
Exp/Cntr=0.3,0.1

Type RM Length L Ch R = 1 ,13282   ,446,446,446
BEGIN DESCRIPTION:
CCLC 058 19.0
END DESCRIPTION:
XS GIS Cut Line= 3
      3736967.84     10161311.07      3736557.78     10161175.77
      3736017.86     10161561.07
#Sta/Elev= 30
  4568.2  279.29    4663  276.45    4730  272.54  4739.4  272.03  4832.6  265.84
  4838.1  265.13  4947.3  264.29  4970.4   265.2  4978.9  266.18  4991.3  265.14
  4996.8  263.22  4999.5  263.68  5030.8  262.83    5031  262.33  5089.3  263.52
 5094.57  265.14  5104.1  266.39  5147.3  264.02  5196.5  263.98  5282.5  265.26
  5290.9  266.11    5356  268.01  5469.1  274.23  5498.6  276.51  5528.1  276.76
    5549  278.27  5569.9  277.85  5614.2  280.17  5641.2  279.96  5663.3  282.26
#Mann= 6 ,-1 , 0
  4568.2     .17       0    4730     .11       0  4739.4     .17       0
  4832.6     .11       0  4991.3     .06       0 5094.57     .11       0
Bank Sta=4991.3,5094.57
XS Rating Curve= 0 ,0
Exp/Cntr=0.3,0.1

Type RM Length L Ch R = 1 ,12836   ,552,552,552
BEGIN DESCRIPTION:
CCLC 058 18.0
END DESCRIPTION:
XS GIS Cut Line= 3
      3736917.87     10160661.07      3736322.17     10160863.02
      3736067.82      10161111.1
#Sta/Elev= 30
  4363.5  280.41  4536.3  274.16  4555.3  272.93  4630.5   270.7  4660.9  269.13
  4724.8  265.42  4796.4  264.38  4870.4  261.92  4970.8  262.25    4976  262.92
  4986.5  262.06  4992.1  259.91  5008.4  258.16  5015.3  259.59  5022.5  260.28
  5029.5  259.84  5036.6  261.34  5050.8  261.73  5057.8  261.73  5064.9  259.88
  5071.9  259.51  5077.1  257.31  5077.3  256.81  5086.1  257.58  5093.2  259.54
  5107.4  261.46  5135.7  263.54  5185.1  266.23  5224.4  267.49  5347.8  273.07
#Mann= 6 ,-1 , 0
  4363.5     .11       0  4555.3     .17       0  4660.9     .15       0
  5071.9     .09       0  5093.2     .15       0  5224.4     .11       0
Bank Sta=5071.9,5093.2
XS Rating Curve= 0 ,0
Exp/Cntr=0.3,0.1

Type RM Length L Ch R = 1 ,12284   ,590,590,590
BEGIN DESCRIPTION:
CCLC 058 17.0
END DESCRIPTION:
XS GIS Cut Line= 3
      3736898.56     10160446.35      3736440.42     10160464.62
      3735817.83     10161011.09
#Sta/Elev= 30
  4541.5  280.59  4762.4  272.82  4833.5  269.03  4932.5     265  4962.5  262.55
  4969.2  261.08 4973.88259.4597  4982.6  253.77  4992.6  251.02  4998.8  254.65
  5006.1  251.06    5012  250.47  5015.5  250.47  5020.4  253.91    5028   251.2
  5042.2  252.14  5063.1   259.6  5183.6   259.5  5245.7  260.88  5310.7  260.37
  5332.6  262.43  5381.9  262.04  5396.1  263.49  5431.3  263.91  5453.1  265.48
  5608.7  269.32  5622.9  270.52  5679.9  271.01  5786.1  276.77  5828.4  277.21
#Mann= 6 ,-1 , 0
  4541.5     .11       0  4833.5     .17       0  4969.2     .15       0
 4973.88     .09       0  5063.1     .15       0  5245.7     .17       0
Bank Sta=4973.88,5063.1
XS Rating Curve= 0 ,0
Exp/Cntr=0.3,0.1

Type RM Length L Ch R = 1 ,11694   ,344,344,344
BEGIN DESCRIPTION:
CCLC 058 16.0
END DESCRIPTION:
XS GIS Cut Line= 3
      3736667.81     10160111.08      3736030.51     10160196.35
      3735817.87     10160461.04
#Sta/Elev= 30
  4363.1  273.59  4423.6  271.93  4484.1  268.57  4504.3  268.21  4550.6  265.14
  4623.6   262.2  4670.1  259.43  4786.8  257.58    4830  258.03  4877.6  257.59
    4918  258.41  4925.8  257.87  4930.8  258.66  4938.1  255.54  4948.2  255.19
  4958.3  255.33  4978.5   258.9  4988.6  257.48  4998.7  253.73  5003.8  250.73
  5004.3  249.82  5012.2  250.32  5018.4  254.85 5023.43257.4337    5025  258.24
  5032.8   259.6    5068  259.67    5204  263.32  5210.4  262.98  5345.6  267.91
#Mann= 5 ,-1 , 0
  4363.1     .11       0  4670.1     .15       0    4830     .17       0
  4988.6     .06       0 5023.43     .11       0
Bank Sta=4988.6,5023.43
XS Rating Curve= 0 ,0
Exp/Cntr=0.3,0.1

Type RM Length L Ch R = 1 ,11350   ,484,484,484
BEGIN DESCRIPTION:
CCLC 058 15.0
END DESCRIPTION:
XS GIS Cut Line= 3
      3736683.32     10159960.24      3735974.95     10159869.96
      3735717.88     10160261.03
#Sta/Elev= 30
    4278  272.94  4309.9  272.68  4394.8  268.03  4469.6  265.68  4505.3  263.79
  4535.5  262.98  4555.7  263.36  4585.9  261.13  4676.7  257.91  4757.3  256.71
  4976.1  255.91 4981.04255.1173  4988.1  252.56  4992.1  252.56  4997.7  249.71
  5003.6  248.85  5012.8  250.19  5018.7  255.24  5027.8  255.31  5033.8  257.06
    5091  257.18  5193.5  261.34  5235.7  259.66  5315.8  260.64  5359.2   262.8
  5365.2  262.27  5374.3  263.09  5380.3   262.5  5401.4  263.17  5460.1  265.97
#Mann= 5 ,-1 , 0
    4278     .11       0  4976.1     .17       0 4981.04     .09       0
  5018.7     .17       0  5315.8     .11       0
Bank Sta=4981.04,5018.7
XS Rating Curve= 0 ,0
Exp/Cntr=0.3,0.1

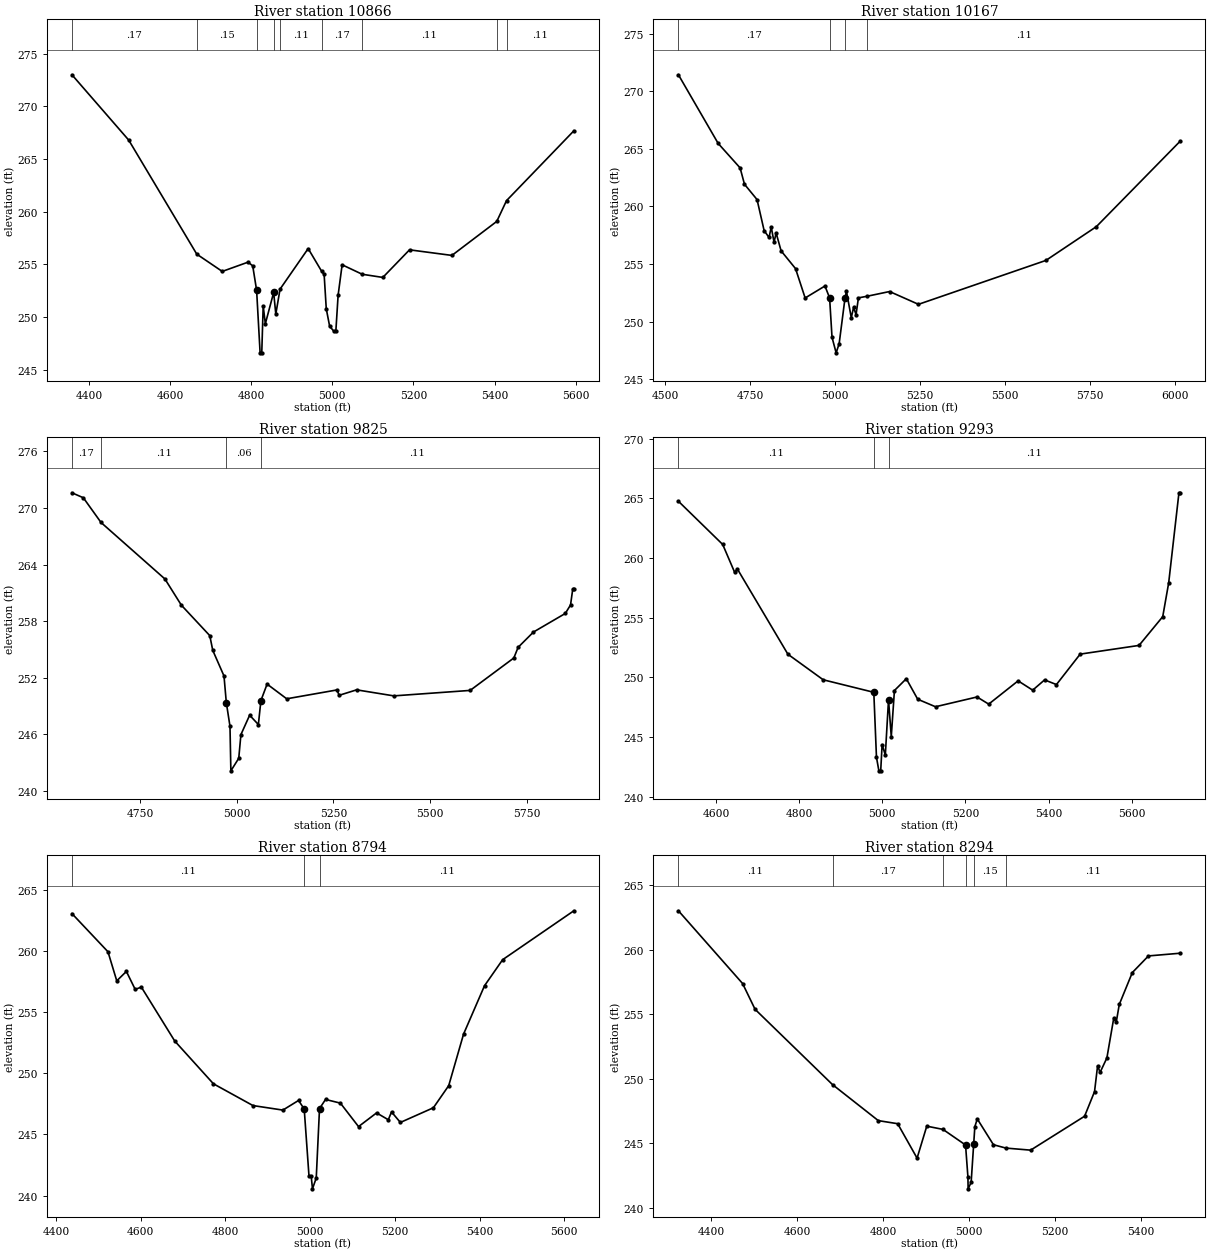
Type RM Length L Ch R = 1 ,10866   ,699,699,699
BEGIN DESCRIPTION:
CCLC 058 14.0
END DESCRIPTION:
XS GIS Cut Line= 3
      3735917.84     10159061.11      3735704.12     10159675.52
      3735667.85     10160261.08
#Sta/Elev= 30
  4358.1  272.99    4498  266.79  4665.8  255.96  4728.6  254.32  4792.2   255.2
  4803.7  254.85  4813.3  252.53  4821.9  246.59    4826  246.59  4829.5  251.05
  4834.8  249.35  4855.3  252.32  4860.6  250.27  4871.1  252.64  4940.4  256.49
  4973.8  254.32  4979.7  254.06    4985  250.77  4993.3  249.12  5003.6  248.64
  5008.6  248.64  5014.2  252.06  5024.1  254.95  5073.6  254.05  5124.4  253.75
  5190.2  256.37  5294.7  255.84  5405.3  259.07  5429.3  261.04  5595.3  267.67
#Mann= 9 ,-1 , 0
  4358.1     .17       0  4665.8     .15       0  4813.3     .09       0
  4855.3     .15       0  4871.1     .11       0  4973.8     .17       0
  5073.6     .11       0  5405.3     .17       0  5429.3     .11       0
Bank Sta=4813.3,4855.3
XS Rating Curve= 0 ,0
Exp/Cntr=0.3,0.1

Type RM Length L Ch R = 1 ,10167   ,342,342,342
BEGIN DESCRIPTION:
CCLC 058 13.0
END DESCRIPTION:
XS GIS Cut Line= 3
      3735745.76     10159015.82      3735468.01     10159383.85
      3734773.92     10160126.52
#Sta/Elev= 30
  4538.2  271.42  4655.3  265.46  4719.8  263.34  4732.7  261.92  4769.7  260.59
  4790.6  257.89  4805.1   257.3  4811.4  258.22  4819.7  256.89  4825.9  257.69
  4840.5  256.14    4883   254.6  4911.3  252.05  4969.6  253.09  4983.3  252.06
  4990.4  248.64  5002.5  247.29  5011.4  248.08 5028.71 252.056  5032.9  252.63
  5047.1  250.34  5053.9  251.23  5061.2  250.61  5068.1  252.06  5093.6   252.2
  5159.9  252.61  5244.9   251.5  5620.1  255.31  5768.6  258.24  6015.8  265.67
#Mann= 4 ,-1 , 0
  4538.2     .17       0  4983.3     .09       0 5028.71     .17       0
  5093.6     .11       0
Bank Sta=4983.3,5028.71
XS Rating Curve= 0 ,0
Exp/Cntr=0.3,0.1

Type RM Length L Ch R = 1 ,9825    ,532,532,532
BEGIN DESCRIPTION:
CCLC 058 12.0
END DESCRIPTION:
XS GIS Cut Line= 3
      3735669.42     10158911.62      3735315.23     10159126.91
      3734517.83     10159511.08
#Sta/Elev= 30
  4572.9  271.62  4602.4  271.09  4648.2  268.47  4813.6  262.48  4856.2   259.7
  4929.8  256.47  4937.5  254.91  4966.6  252.19  4972.6  249.37  4982.1  246.86
  4984.4  242.13  5004.8  243.46  5010.4  245.97    5033  248.03  5055.6  247.04
  5062.2  249.58  5078.2  251.33    5129  249.77  5259.2  250.71  5264.7  250.14
    5310  250.72  5406.3  250.08    5604  250.66  5717.1   254.1  5728.2  255.23
  5767.9  256.85  5850.3  258.82  5863.9  259.72  5869.7  261.43  5872.5  261.43
#Mann= 4 ,-1 , 0
  4572.9     .17       0  4648.2     .11       0  4972.6     .06       0
  5062.2     .11       0
Bank Sta=4972.6,5062.2
XS Rating Curve= 0 ,0
Exp/Cntr=0.3,0.1

Type RM Length L Ch R = 1 ,9293    ,499,499,499
BEGIN DESCRIPTION:
CCLC 058 11.0
END DESCRIPTION:
XS GIS Cut Line= 3
      3735317.83     10158561.08      3734934.19     10158866.71
      3734467.85     10159411.07
#Sta/Elev= 30
  4509.5  264.76    4616  261.14  4644.8   258.8  4651.2  259.09  4772.9  251.94
  4857.8   249.8  4979.5  248.75  4985.9  243.31  4991.7  242.17  4996.1  242.17
  4999.5  244.37  5007.2  243.49  5014.9  248.13  5021.5  245.03  5029.1   248.9
  5057.7  249.89  5085.1  248.17  5127.9  247.54  5227.8  248.36  5255.9  247.76
  5326.6  249.71  5361.7  248.93  5390.3  249.79  5418.8   249.4  5475.9  251.95
  5617.5  252.68  5674.5  255.09  5688.8  257.92  5713.5  265.47  5716.8  265.47
#Mann= 3 , 0 , 0
  4509.5     .11       0  4979.5     .06       0  5014.9     .11       0
Bank Sta=4979.5,5014.9
XS Rating Curve= 0 ,0
Exp/Cntr=0.3,0.1

Type RM Length L Ch R = 1 ,8794    ,500,500,500
BEGIN DESCRIPTION:
CCLC 058 10.0
END DESCRIPTION:
XS GIS Cut Line= 3
      3735051.33     10158244.97      3734606.85     10158589.22
      3734134.64     10158994.99
#Sta/Elev= 30
  4437.8  263.06  4522.8  259.94  4543.6  257.56  4566.3  258.33  4587.1  256.86
  4601.6  257.05  4680.4  252.64  4771.8  249.14  4865.1  247.36  4935.7  246.99
  4972.8  247.78  4986.1  247.07  4997.4  241.58  5002.6  241.58  5005.6  240.55
  5014.5  241.44  5022.2  247.11  5036.4  247.86  5071.5  247.56  5114.3  245.64
  5156.9  246.76  5184.6   246.2  5192.2  246.84  5213.1  245.98    5291  247.18
  5327.2  248.99  5362.3  253.21  5411.7  257.16  5454.5  259.29  5622.6  263.29
#Mann= 3 , 0 , 0
  4437.8     .11       0  4986.1     .06       0  5022.2     .11       0
Bank Sta=4986.1,5022.2
XS Rating Curve= 0 ,0
Exp/Cntr=0.3,0.1

Type RM Length L Ch R = 1 ,8294    ,500,500,500
BEGIN DESCRIPTION:
CCLC 058 9.0
END DESCRIPTION:
XS GIS Cut Line= 3
      3734917.83     10158011.08      3734310.99     10158307.59
      3733884.65     10158550.53
#Sta/Elev= 30
  4324.6  263.03  4473.7  257.39  4502.7  255.39  4682.7  249.55    4789  246.76
    4834  246.52  4879.1  243.85  4901.6  246.33  4939.2  246.08  4991.7  244.87
  4997.2   242.4  4997.7  241.47  5004.7  241.97 5010.62244.9439  5013.3  246.29
    5019  246.89  5056.5  244.89  5085.4  244.63  5142.9  244.47  5268.3   247.1
  5291.4  249.01  5298.5  251.01  5304.3   250.5  5320.1  251.62    5336   254.7
  5341.7  254.37  5348.9  255.77  5379.2  258.24  5416.7  259.53  5490.7  259.74
#Mann= 6 ,-1 , 0
  4324.6     .11       0  4682.7     .17       0  4939.2     .15       0
  4991.7     .09       0 5010.62     .15       0  5085.4     .11       0
Bank Sta=4991.7,5010.62
XS Rating Curve= 0 ,0
Exp/Cntr=0.3,0.1

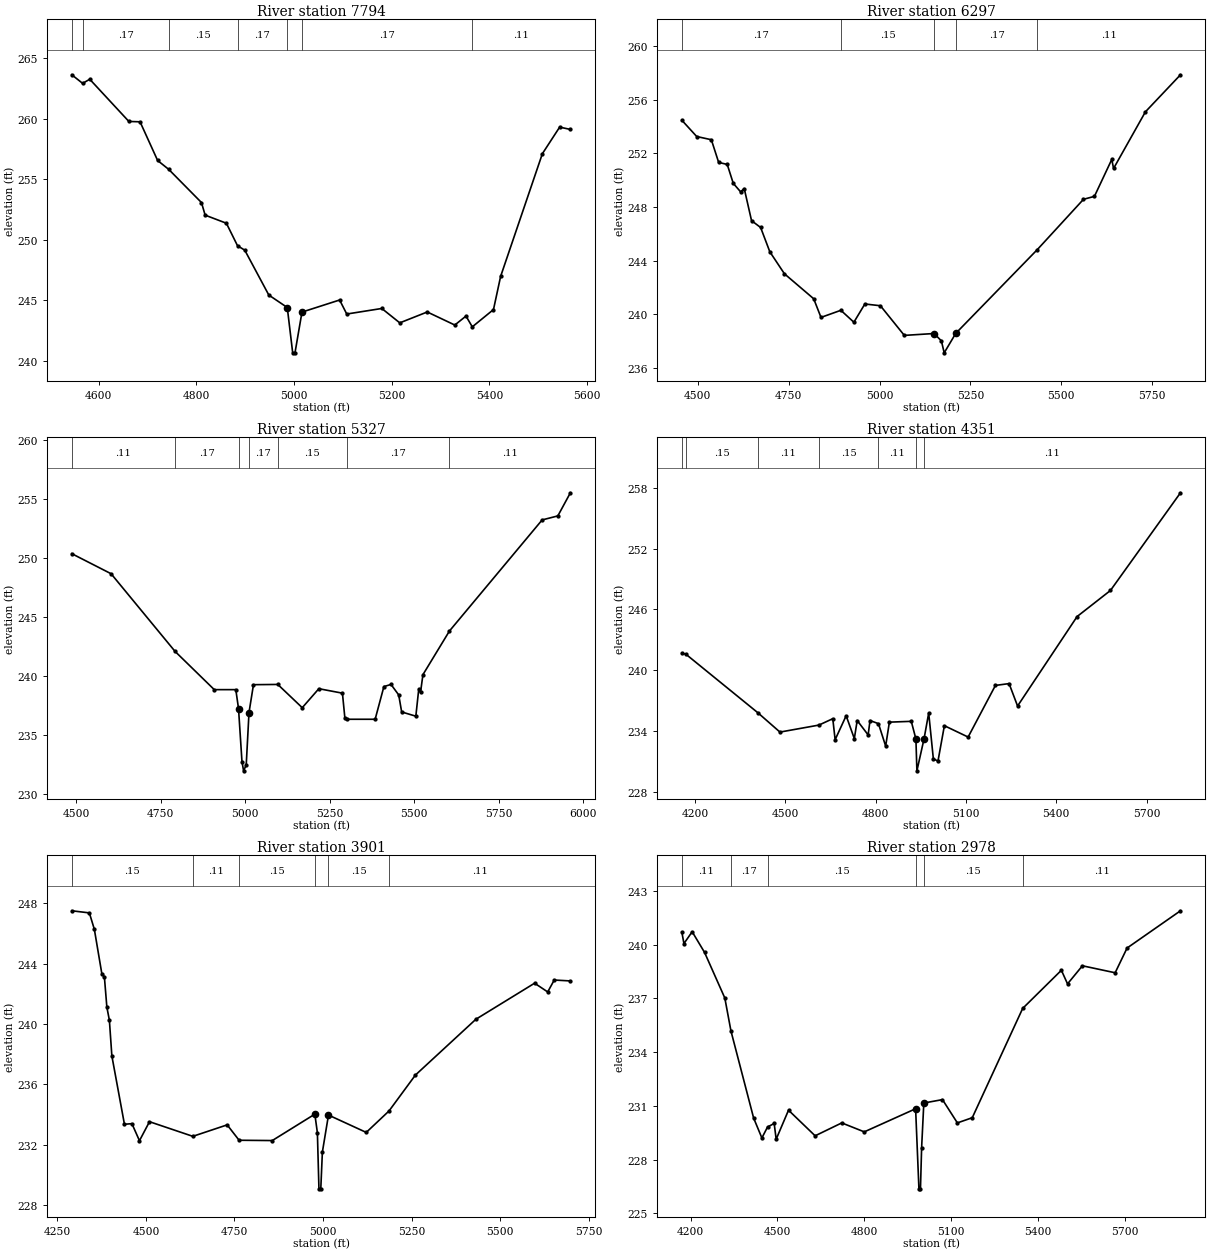
Type RM Length L Ch R = 1 ,7794    ,1497,1497,1497
BEGIN DESCRIPTION:
CCLC 058 8.0
END DESCRIPTION:
XS GIS Cut Line= 3
      3734426.32     10157508.89      3734205.27     10157906.81
      3733867.83      10158361.1
#Sta/Elev= 30
  4544.8  263.65    4567  262.94  4581.6  263.28  4661.7  259.79  4684.6  259.76
  4720.6  256.56  4743.2  255.83  4810.4  253.08  4817.9  252.04  4861.4  251.37
  4884.2  249.51  4899.1  249.14  4948.3  245.43  4986.1   244.4  4997.2  240.65
  5001.9  240.65  5016.2  244.02  5093.3  245.02  5107.9  243.86  5179.7  244.32
  5216.5  243.13  5272.8  244.03  5329.2  242.95  5352.1  243.69    5365   242.8
  5408.4  244.23    5423  246.97  5508.5  257.12  5543.9  259.32  5565.9  259.13
#Mann= 7 ,-1 , 0
  4544.8     .11       0    4567     .17       0  4743.2     .15       0
  4884.2     .17       0  4986.1     .09       0  5016.2     .17       0
    5365     .11       0
Bank Sta=4986.1,5016.2
XS Rating Curve= 0 ,0
Exp/Cntr=0.3,0.1

Type RM Length L Ch R = 1 ,6297    ,970,970,970
BEGIN DESCRIPTION:
CCLC 058 7.0
END DESCRIPTION:
XS GIS Cut Line= 3
      3733259.67     10157050.48      3733317.87     10157591.25
      3733259.76     10158417.31
#Sta/Elev= 30
  4456.1  254.47  4496.9  253.26  4537.2  253.02  4557.3  251.33  4580.9  251.18
  4597.5  249.77  4617.6  249.14  4627.7  249.38  4647.8  246.99  4672.8  246.48
  4698.1  244.67  4738.3  243.03  4818.8  241.17  4838.9  239.78  4893.6  240.31
  4929.4  239.42  4959.6  240.78  5002.4  240.65  5068.2  238.44  5150.2  238.58
  5170.2  238.03  5177.9  237.14  5209.7  238.59  5434.4  244.84  5561.2  248.58
  5591.3   248.8    5639  251.55    5644  250.88  5731.6   255.1  5828.1  257.86
#Mann= 5 ,-1 , 0
  4456.1     .17       0  4893.6     .15       0  5150.2     .09       0
  5209.7     .17       0  5434.4     .11       0
Bank Sta=5150.2,5209.7
XS Rating Curve= 0 ,0
Exp/Cntr=0.3,0.1

Type RM Length L Ch R = 1 ,5327    ,976,976,976
BEGIN DESCRIPTION:
CCLC 058 6.0
END DESCRIPTION:
XS GIS Cut Line= 3
      3732787.46     10156869.94       3732676.2     10157370.42
      3732967.93     10158286.39
#Sta/Elev= 30
  4487.3   250.4  4603.5   248.7  4792.6  242.12  4908.5  238.88  4972.2  238.88
  4980.2  237.28  4990.4  232.79  4995.2     232    5003   232.5  5011.2  236.94
  5024.4   239.3  5096.3  239.32  5168.6  237.35  5217.7  238.96  5287.4  238.58
  5294.5  236.51  5299.8  236.37  5384.1  236.37    5410  239.14    5431  239.32
  5453.8  238.43  5462.5  236.99  5504.4  236.63  5512.9   238.9  5518.2  238.64
  5525.4  240.15  5603.8  243.85  5877.8  253.26  5924.2   253.6  5961.3  255.56
#Mann= 7 ,-1 , 0
  4487.3     .11       0  4792.6     .17       0  4980.2     .09       0
  5011.2     .17       0  5096.3     .15       0  5299.8     .17       0
  5603.8     .11       0
Bank Sta=4980.2,5011.2
XS Rating Curve= 0 ,0
Exp/Cntr=0.3,0.1

Type RM Length L Ch R = 1 ,4351    ,450,450,450
BEGIN DESCRIPTION:
CCLC 058 5.0
END DESCRIPTION:
XS GIS Cut Line= 3
      3732551.34     10156814.41      3732058.28     10157613.02
      3732367.83     10158261.03
#Sta/Elev= 30
    4156  241.69  4169.2  241.59  4408.3  235.82  4481.9  233.91  4611.3   234.6
  4657.4  235.23  4665.2  233.16  4701.8  235.52    4729  233.27  4738.5  235.05
  4774.9  233.63  4781.1  235.05  4809.2  234.74  4833.1  232.53  4845.5  234.89
  4918.2  234.97  4933.6  233.23  4936.9  230.09 4960.82233.2729  4976.1  235.79
  4991.5  231.29  5006.9  231.04  5028.2  234.54  5107.1  233.42  5197.8  238.51
  5243.2  238.69  5271.4  236.48  5469.2   245.3    5580  247.87  5812.7   257.5
#Mann= 7 ,-1 , 0
    4156     .11       0  4169.2     .15       0  4408.3     .11       0
  4611.3     .15       0  4809.2     .11       0  4933.6     .06       0
 4960.82     .11       0
Bank Sta=4933.6,4960.82
XS Rating Curve= 0 ,0
Exp/Cntr=0.3,0.1

Type RM Length L Ch R = 1 ,3901    ,923,923,923
BEGIN DESCRIPTION:
CCLC 058 4.0
END DESCRIPTION:
XS GIS Cut Line= 3
      3732317.88     10156761.04      3731810.85     10157256.77
      3731567.84      10157911.1
#Sta/Elev= 30
  4290.9   247.5  4340.5  247.36  4354.6  246.27  4375.7  243.33  4382.9  243.12
  4389.9  241.11    4397  240.25    4404  237.88  4439.5  233.35  4460.6  233.39
  4481.9  232.26  4510.2  233.52  4632.5  232.55  4729.4  233.31  4763.1  232.29
  4856.7  232.27  4976.8  234.02    4984  232.79  4988.4  229.07  4993.6  229.07
  4998.1  231.51  5015.3  233.96  5121.9  232.81  5186.1  234.23  5260.6  236.61
  5431.3  240.31    5597   242.7    5634  242.12  5652.4  242.91    5698  242.85
#Mann= 6 ,-1 , 0
  4290.9     .15       0  4632.5     .11       0  4763.1     .15       0
  4976.8     .09       0  5015.3     .15       0  5186.1     .11       0
Bank Sta=4976.8,5015.3
XS Rating Curve= 0 ,0
Exp/Cntr=0.3,0.1

Type RM Length L Ch R = 1 ,2978    ,550,550,550
BEGIN DESCRIPTION:
CCLC 058 3.0
END DESCRIPTION:
XS GIS Cut Line= 3
      3731767.83     10156311.09      3731211.06     10156946.35
      3731419.39     10157800.49
#Sta/Elev= 30
  4169.6  240.69  4176.7  240.06  4205.2  240.72  4247.9  239.57  4318.1  237.02
  4339.3  235.18  4417.7  230.32  4446.2  229.21  4465.7  229.82  4488.7  230.02
  4495.6  229.14  4538.3  230.76  4630.3  229.33  4722.4  230.05  4800.2  229.55
  4977.7  230.84  4989.2  226.37  4994.5  226.37  4998.5  228.67  5006.1  231.16
  5070.6  231.35  5122.1  230.05  5173.6  230.34  5347.9  236.44  5481.7  238.57
    5503  237.81  5554.4  238.82  5667.6  238.43  5708.8  239.81  5893.5  241.89
#Mann= 6 ,-1 , 0
  4169.6     .11       0  4339.3     .17       0  4465.7     .15       0
  4977.7     .09       0  5006.1     .15       0  5347.9     .11       0
Bank Sta=4977.7,5006.1
XS Rating Curve= 0 ,0
Exp/Cntr=0.3,0.1

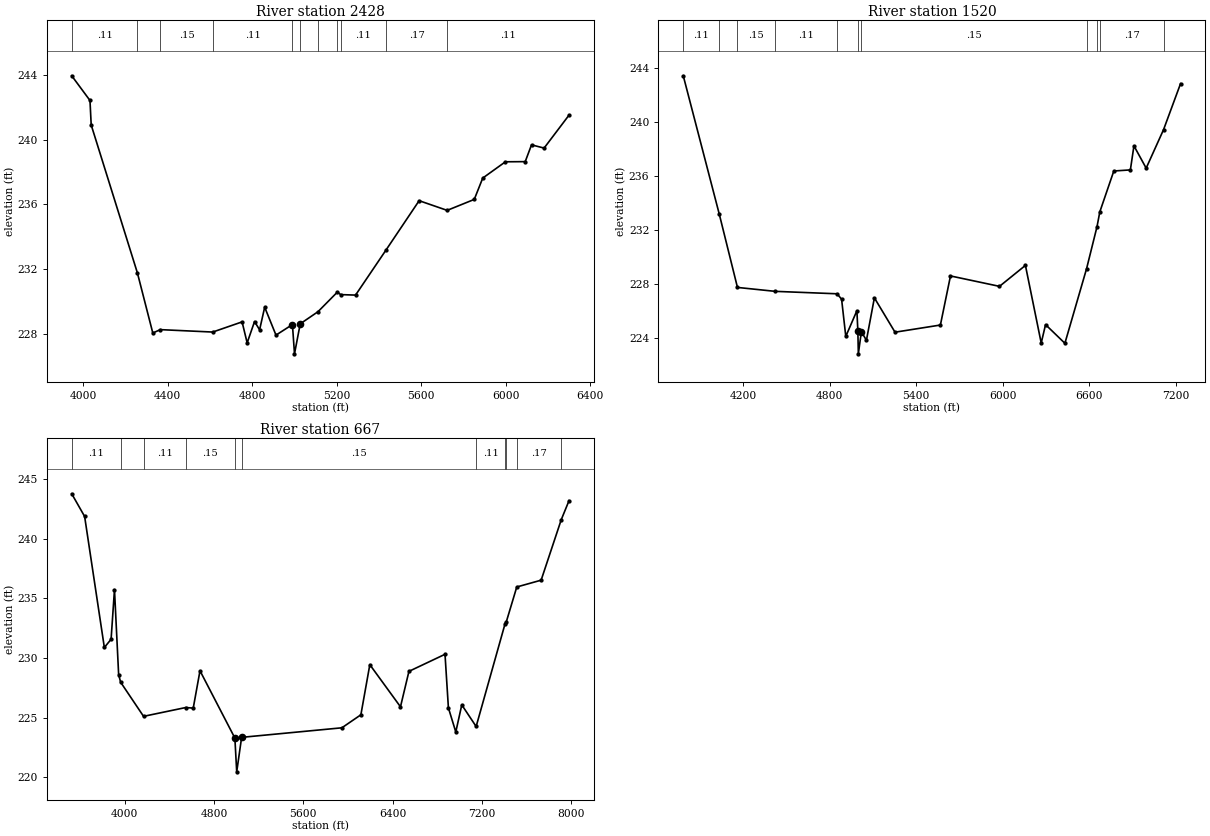
Type RM Length L Ch R = 1 ,2428    ,908,908,908
BEGIN DESCRIPTION:
CCLC 058 2.0
END DESCRIPTION:
XS GIS Cut Line= 3
      3731767.85     10156161.07      3730863.84     10156529.68
      3731367.85     10157811.06
#Sta/Elev= 30
  3945.9  243.97  4032.3  242.44  4038.1  240.92  4256.8  231.75  4329.6  228.03
  4365.1  228.24    4613  228.09  4752.1  228.72  4776.1  227.42    4811  228.74
    4835  228.23    4859  229.63  4912.5   227.9 4990.31228.5549  5000.1  226.74
  5027.2   228.6  5111.2  229.35  5203.3  230.57  5218.5  230.41    5289  230.38
    5433  233.17  5589.9  236.23  5722.5  235.63  5850.8  236.31  5890.8  237.63
  5998.2  238.64  6091.9  238.65  6121.7  239.69  6181.2  239.49  6299.1  241.53
#Mann= 11 ,-1 , 0
  3945.9     .11       0  4256.8     .17       0  4365.1     .15       0
    4613     .11       0 4990.31     .06       0  5027.2     .11       0
  5111.2     .11       0  5203.3     .15       0  5218.5     .11       0
    5433     .17       0  5722.5     .11       0
Bank Sta=4990.31,5027.2
XS Rating Curve= 0 ,0
Exp/Cntr=0.3,0.1

Type RM Length L Ch R = 1 ,1520    ,853,853,853
BEGIN DESCRIPTION:
Mapping XS f2b0ed2c
END DESCRIPTION:
XS GIS Cut Line= 4
      3731711.08     10156043.56      3730336.06     10156682.46
      3730301.34     10157488.02       3731356.9      10157890.8
#Sta/Elev= 30
  3782.5  243.39  4031.8  233.19  4158.8  227.74  4421.5  227.45  4850.5  227.27
  4881.7  226.87  4910.8  224.12    4988  226.02 4994.67224.4966    4998  222.83
    5019  224.47  5054.1  223.83  5109.3  226.97  5252.6  224.43  5567.6  224.96
  5637.6  228.59  5977.9  227.82  6157.9  229.37  6267.5  223.63  6297.6  224.99
  6431.9  223.61  6582.5  229.13  6654.8  232.23  6674.4  233.33  6771.5  236.35
  6886.5  236.43  6911.2  238.21  6996.1  236.56  7116.9  239.41  7234.8  242.81
#Mann= 11 ,-1 , 0
  3782.5     .11       0  4031.8     .17       0  4158.8     .15       0
  4421.5     .11       0  4850.5     .15       0 4994.67     .09       0
    5019     .15       0  6582.5     .17       0  6654.8     .11       0
  6674.4     .17       0  7116.9     .11       0
Bank Sta=4994.67,5019
XS Rating Curve= 0 ,0
Exp/Cntr=0.3,0.1

Type RM Length L Ch R = 1 ,667     ,0,0,0
BEGIN DESCRIPTION:
CCLC 058 1.0
END DESCRIPTION:
XS GIS Cut Line= 4
      3731867.87     10155661.07      3730329.12     10155863.02
      3730224.95     10157543.57      3731363.31     10157987.81
#Sta/Elev= 30
  3523.6  243.76  3639.3  241.86  3816.1  230.88  3876.6  231.57  3906.9  235.73
  3944.2  228.61  3962.1  227.97  4167.6  225.11  4546.2  225.85  4612.9   225.8
  4673.4  228.93  4986.1  223.29  5002.6  220.46  5046.6  223.35  5945.3  224.15
  6115.6  225.24  6195.8  229.44  6470.6  225.91  6546.4  228.88  6869.8  230.31
  6900.2  225.82  6966.4   223.8  7020.1  226.07  7148.9  224.26  7408.7  232.89
  7418.6  233.01    7513  235.95  7731.4  236.52  7911.8  241.59  7981.3  243.18
#Mann= 11 ,-1 , 0
  3523.6     .11       0  3962.1     .15       0  4167.6     .11       0
  4546.2     .15       0  4986.1     .09       0  5046.6     .15       0
  7148.9     .11       0  7408.7     .17       0  7418.6     .11       0
    7513     .17       0  7911.8     .11       0
Bank Sta=4986.1,5046.6
XS Rating Curve= 0 ,0
Exp/Cntr=0.3,0.1

Chan Stop Cuts=-1
Use User Specified Reach Order=0
Composite Channel Slope=5