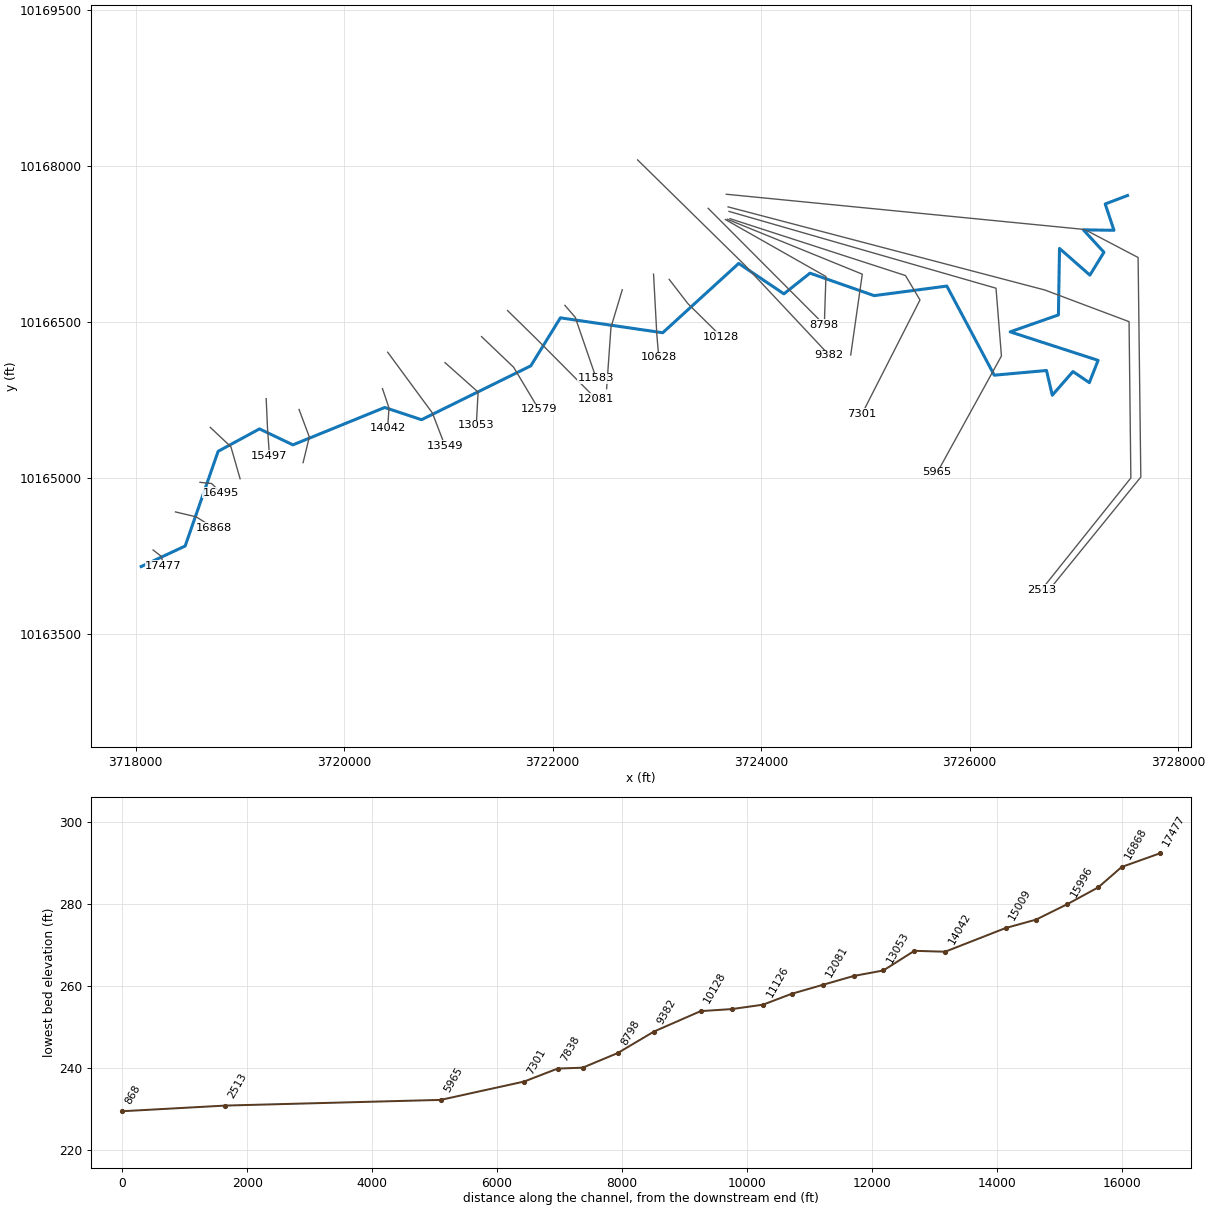
--- CCLC 063.prj (project) ---

Proj Title=CCLC 063 Base Level Engineering
Current Plan=p01
Default Exp/Contr=0.3,0.1
English Units
Geom File=g01
Flow File=f01
Flow File=f02
Plan File=p01
Y Axis Title=Elevation
X Axis Title(PF)=Main Channel Distance
X Axis Title(XS)=Station
BEGIN DESCRIPTION:
CCLC 063
END DESCRIPTION:
DSS Export Rating Curves= 0
DSS Export Rating Curve Sorted= 0
DSS Export Volume Flow Curves= 0
DXF OffsetX= 0
DXF OffsetY= 0
DXF ScaleX= 1
DXF ScaleY= 10

--- CCLC 063.p01 (plan) ---

Plan Title=Multiple Run
Short Identifier=Multiple
Geom File=g01
Flow File=f01
Subcritical Flow
K Sum by GR= 0
Std Step Tol= 0.01
Critical Tol= 0.01
Num of Std Step Trials= 20
Max Error Tol= 0.3
Flow Tol Ratio= 0.001
Split Flow NTrial= 30
Split Flow Tol= 0.02
Split Flow Ratio= 0.02
Log Output Level= 0
Friction Slope Method= 1
Unsteady Friction Slope Method= 2
Unsteady Bridges Friction Slope Method= 1
Parabolic Critical Depth
Global Vel Dist=  1 , 1 , 1
Global Log Level= 0
CheckData=True
Encroach Param= -1, 0, 0, 0
BEGIN DESCRIPTION:
Multiple Run
END DESCRIPTION:

--- CCLC 063.f01 (steady flow) ---

Flow Title=Multiple
Program Version=4.10
Number of Profiles= 7
Profile Names=10-year,25-year,50-year,1pct_min,100-year,1pct_plu,500-year
River Rch & RM=CCLC 063,Reach-1         ,17477
     624     842    1134     502    1517    4581    2810
River Rch & RM=CCLC 063,Reach-1         ,8798
     804    1094    1482     659    1990    6010    3715
Boundary for River Rch & Prof#=CCLC 063,Reach-1         , 1
Up Type= 0
Dn Type= 3
Dn Slope=0.005
Boundary for River Rch & Prof#=CCLC 063,Reach-1         , 2
Up Type= 0
Dn Type= 3
Dn Slope=0.005
Boundary for River Rch & Prof#=CCLC 063,Reach-1         , 3
Up Type= 0
Dn Type= 3
Dn Slope=0.005
Boundary for River Rch & Prof#=CCLC 063,Reach-1         , 4
Up Type= 0
Dn Type= 3
Dn Slope=0.005
Boundary for River Rch & Prof#=CCLC 063,Reach-1         , 5
Up Type= 0
Dn Type= 3
Dn Slope=0.005
Boundary for River Rch & Prof#=CCLC 063,Reach-1         , 6
Up Type= 0
Dn Type= 3
Dn Slope=0.005
Boundary for River Rch & Prof#=CCLC 063,Reach-1         , 7
Up Type= 0
Dn Type= 3
Dn Slope=0.005
DSS Import GetInterval= 0
DSS Import GetPeak= 0
DSS Import FillOption= 0

--- CCLC 063.f02 (steady flow) ---

Flow Title=Orig_BLE_Flows
Program Version=4.10
Number of Profiles= 7
Profile Names=10-year,25-year,50-year,1pct_min,100-year,1pct_plu,500-year
River Rch & RM=CCLC 063,Reach-1         ,17477
     624     825     986     387    1167    3525    1634
River Rch & RM=CCLC 063,Reach-1         ,8798
     804    1073    1289     507    1531    4624    2160
Boundary for River Rch & Prof#=CCLC 063,Reach-1         , 1
Up Type= 0
Dn Type= 3
Dn Slope=0.005
Boundary for River Rch & Prof#=CCLC 063,Reach-1         , 2
Up Type= 0
Dn Type= 3
Dn Slope=0.005
Boundary for River Rch & Prof#=CCLC 063,Reach-1         , 3
Up Type= 0
Dn Type= 3
Dn Slope=0.005
Boundary for River Rch & Prof#=CCLC 063,Reach-1         , 4
Up Type= 0
Dn Type= 3
Dn Slope=0.005
Boundary for River Rch & Prof#=CCLC 063,Reach-1         , 5
Up Type= 0
Dn Type= 3
Dn Slope=0.005
Boundary for River Rch & Prof#=CCLC 063,Reach-1         , 6
Up Type= 0
Dn Type= 3
Dn Slope=0.005
Boundary for River Rch & Prof#=CCLC 063,Reach-1         , 7
Up Type= 0
Dn Type= 3
Dn Slope=0.005
DSS Import GetInterval= 0
DSS Import GetPeak= 0
DSS Import FillOption= 0

--- CCLC 063.g01 (geometry) ---

Geom Title=Existing Conditions
Program Version=4.10

River Reach=CCLC 063        ,Reach-1
Reach XY= 30
      3718053.23     10164151.84       3718475.2     10164349.14
      3718791.53     10165258.94      3719188.35     10165474.42
      3719508.74     10165320.99      3720389.01     10165680.11
      3720742.68     10165562.78      3721790.52     10166080.27
      3722074.31     10166541.36      3723055.75     10166398.24
      3723784.57     10167064.18      3724218.16     10166771.72
      3724468.11     10166970.66      3725083.63     10166754.72
      3725780.77     10166846.53      3726235.84      10165990.4
      3726736.66     10166035.59      3726792.22     10165798.04
      3726990.78     10166025.54      3727147.49     10165918.86
       3727231.6     10166132.93      3726388.23     10166406.84
      3726851.09     10166569.37      3726861.48     10167208.41
       3727152.9     10166951.76      3727287.77     10167171.67
      3727090.32     10167386.88      3727383.73     10167382.49
      3727299.75     10167635.24      3727513.94     10167716.85

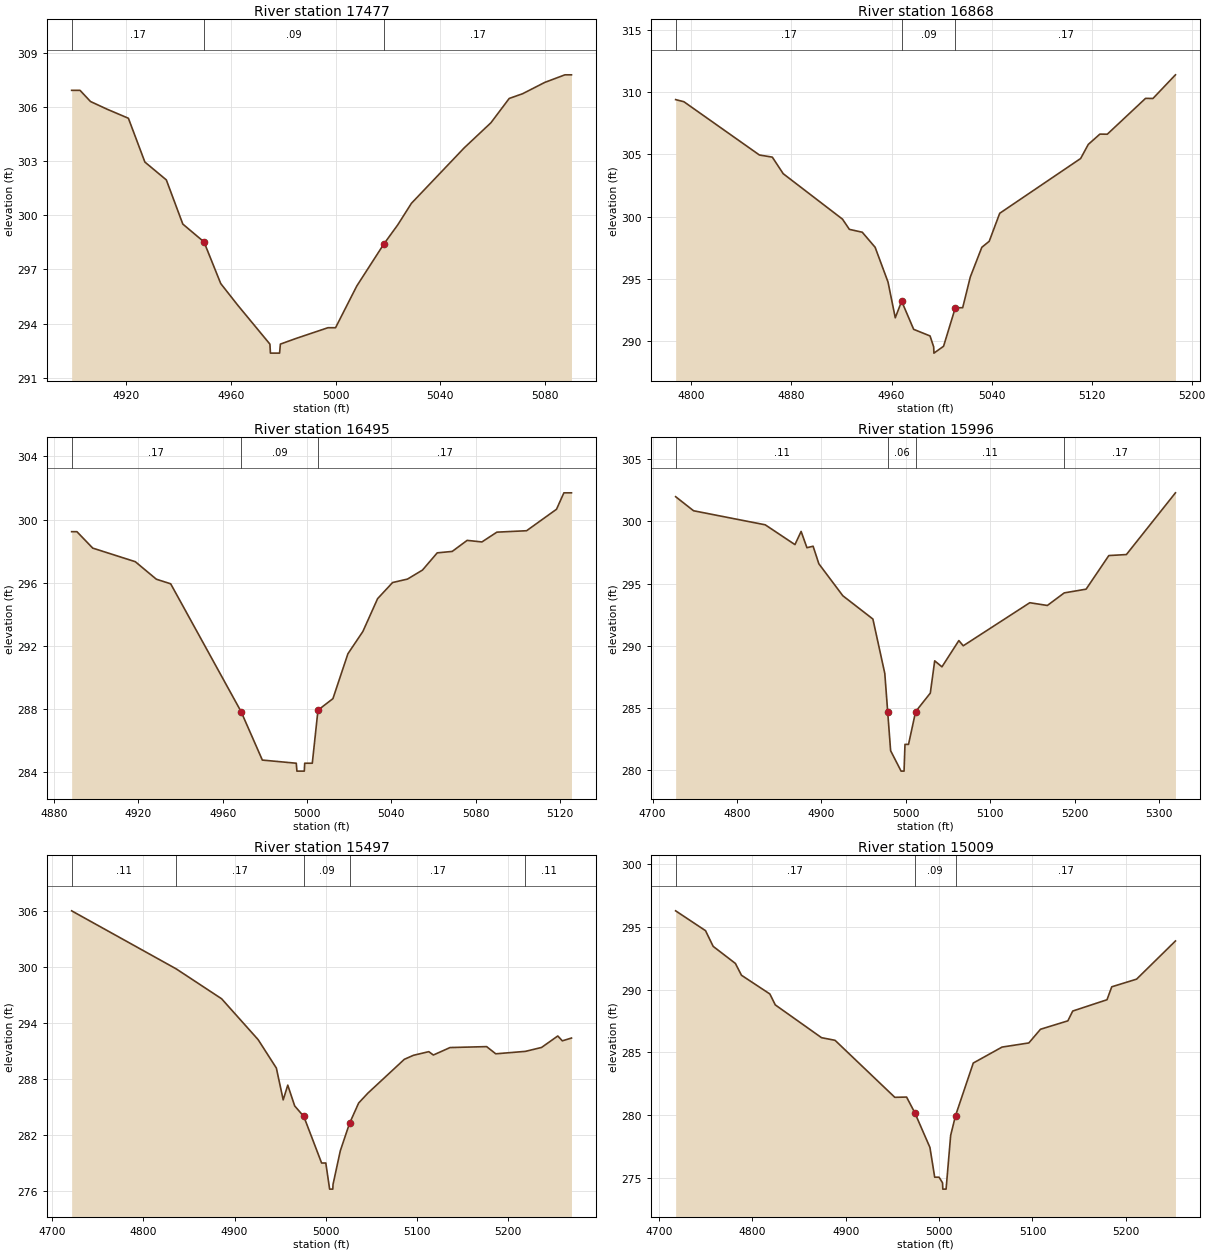
Type RM Length L Ch R = 1 ,17477   ,609,609,609
BEGIN DESCRIPTION:
CCLC 063 20.0
END DESCRIPTION:
XS GIS Cut Line= 3
      3718167.85     10164311.07      3718247.35     10164248.94
      3718267.84      10164161.1
#Sta/Elev= 29
  4899.1  306.94  4902.3  306.94  4906.3  306.32  4912.7  305.89  4920.8  305.39
  4927.1  302.96  4935.3  301.97  4941.6  299.52  4949.7  298.53  4956.1  296.22
  4962.6  295.02  4974.9  292.86  4975.1  292.36  4978.6  292.36  4978.9  292.86
    4985  293.18  4997.1  293.77    5000  293.77  5008.1  296.08  5018.4   298.4
  5023.8  299.48    5029  300.67  5049.2  303.75  5059.4  305.14  5066.4  306.49
  5071.5  306.75    5080  307.38  5087.7   307.8  5090.2   307.8
#Mann= 3 , 0 , 0
  4899.1     .17       0  4949.7     .09       0  5018.4     .17       0
Bank Sta=4949.7,5018.4
XS Rating Curve= 0 ,0
Exp/Cntr=0.3,0.1

Type RM Length L Ch R = 1 ,16868   ,373,373,373
BEGIN DESCRIPTION:
CCLC 063 19.0
END DESCRIPTION:
XS GIS Cut Line= 3
      3718382.66      10164676.7      3718580.58     10164629.83
      3718746.96     10164525.84
#Sta/Elev= 30
  4787.4   309.4    4794  309.23  4854.4  304.95  4864.7  304.78  4873.4  303.45
  4920.8   299.8  4926.3  298.98  4936.6  298.75  4946.9  297.54  4957.2  294.75
    4963  291.88  4968.1  293.21  4977.7  290.95  4990.8  290.42  4993.7  289.54
  4993.9  289.04  5001.6  289.59    5011  292.68  5016.9  292.69    5023  295.16
  5032.2  297.54  5038.1  298.02  5046.5  300.27  5111.2  304.67  5117.3   305.8
  5126.6  306.63  5132.5  306.62  5163.1   309.5    5169  309.49    5187  311.39
#Mann= 3 , 0 , 0
  4787.4     .17       0  4968.1     .09       0    5011     .17       0
Bank Sta=4968.1,5011
XS Rating Curve= 0 ,0
Exp/Cntr=0.3,0.1

Type RM Length L Ch R = 1 ,16495   ,499,499,499
BEGIN DESCRIPTION:
CCLC 063 18.0
END DESCRIPTION:
XS GIS Cut Line= 3
      3718617.86     10164961.07      3718728.97      10164949.6
      3718817.89     10164861.04
#Sta/Elev= 30
  4888.3  299.24  4890.8  299.24  4898.3   298.2  4918.5  297.34  4928.5  296.23
  4935.3  295.94  4968.7  287.85  4978.8  284.78  4994.9  284.58  4995.2  284.08
  4998.7  284.08  4998.9  284.58  5002.5  284.58  5005.2  287.94  5012.3  288.67
  5019.4  291.51  5026.5  292.92  5033.5     295  5040.6  296.02  5047.7  296.24
  5054.8  296.81  5061.8   297.9  5068.9  297.99    5076  298.69    5083  298.59
  5090.1  299.21  5104.2   299.3  5118.4  300.66  5121.9   301.7  5125.5   301.7
#Mann= 3 , 0 , 0
  4888.3     .17       0  4968.7     .09       0  5005.2     .17       0
Bank Sta=4968.7,5005.2
XS Rating Curve= 0 ,0
Exp/Cntr=0.3,0.1

Type RM Length L Ch R = 1 ,15996   ,499,499,499
BEGIN DESCRIPTION:
CCLC 063 17.0
END DESCRIPTION:
XS GIS Cut Line= 3
      3718715.99     10165489.21      3718914.38     10165302.12
      3719002.22     10164995.24
#Sta/Elev= 30
  4727.3  301.99  4748.5  300.86  4833.4  299.73  4868.6  298.14  4875.9   299.2
  4882.8  297.89  4890.1  298.01  4896.9   296.6  4925.3  294.03  4960.9  292.16
    4975  287.79 4978.43284.7028  4981.9  281.58  4994.3  279.94  4997.8  279.94
  4998.9  282.09  5003.1  282.09  5011.5  284.72  5028.9  286.21  5034.1   288.8
  5042.7  288.32  5062.7  290.43  5067.9  290.01  5146.7  293.47  5167.5  293.25
  5187.5  294.26  5213.4  294.56  5240.3  297.26  5261.1  297.34  5319.2   302.3
#Mann= 4 ,-1 , 0
  4727.3     .11       0 4978.43     .06       0  5011.5     .11       0
  5187.5     .17       0
Bank Sta=4978.43,5011.5
XS Rating Curve= 0 ,0
Exp/Cntr=0.3,0.1

Type RM Length L Ch R = 1 ,15497   ,488,488,488
BEGIN DESCRIPTION:
CCLC 063 16.0
END DESCRIPTION:
XS GIS Cut Line= 3
      3719252.45     10165765.29      3719264.81     10165486.96
      3719283.71     10165218.32
#Sta/Elev= 30
  4721.4  306.02  4836.1  299.79  4885.8  296.59  4925.8  292.21  4945.8  289.16
  4953.3  285.75  4958.3  287.33  4965.9   285.1  4975.9  283.97  4995.4  278.98
    5000  278.98  5004.2  276.18  5007.7  276.18  5007.9  276.68  5015.9  280.29
    5026  283.23    5036  285.41    5046  286.46  5086.1   290.1  5096.1  290.53
  5112.9  290.92  5117.9  290.56  5136.2  291.36  5176.3  291.46  5186.3  290.69
  5218.8  290.95  5236.5  291.37  5254.3   292.6  5259.3  292.08  5269.3  292.38
#Mann= 5 ,-1 , 0
  4721.4     .11       0  4836.1     .17       0  4975.9     .09       0
    5026     .17       0  5218.8     .11       0
Bank Sta=4975.9,5026
XS Rating Curve= 0 ,0
Exp/Cntr=0.3,0.1

Type RM Length L Ch R = 1 ,15009   ,967,967,967
BEGIN DESCRIPTION:
CCLC 063 15.0
END DESCRIPTION:
XS GIS Cut Line= 3
      3719567.86     10165661.04      3719666.15     10165396.62
      3719606.61     10165150.62
#Sta/Elev= 30
  4717.9  296.28  4749.9   294.7  4758.1  293.45  4781.9  292.09  4788.4  291.15
  4818.8  289.66  4824.6  288.79  4874.1  286.18  4888.6  285.97  4952.6  281.43
  4965.2  281.45  4973.9  280.22  4990.2  277.44  4995.3  275.07    5000  275.07
  5003.7  274.62    5004  274.12  5007.5  274.12  5012.4   278.4  5017.6  279.97
  5036.6  284.16  5067.4  285.43  5096.1  285.76  5108.6  286.85  5137.9  287.52
  5143.1   288.3  5179.8   289.2  5184.9  290.23  5211.5  290.84  5253.1  293.88
#Mann= 3 , 0 , 0
  4717.9     .17       0  4973.9     .09       0  5017.6     .17       0
Bank Sta=4973.9,5017.6
XS Rating Curve= 0 ,0
Exp/Cntr=0.3,0.1

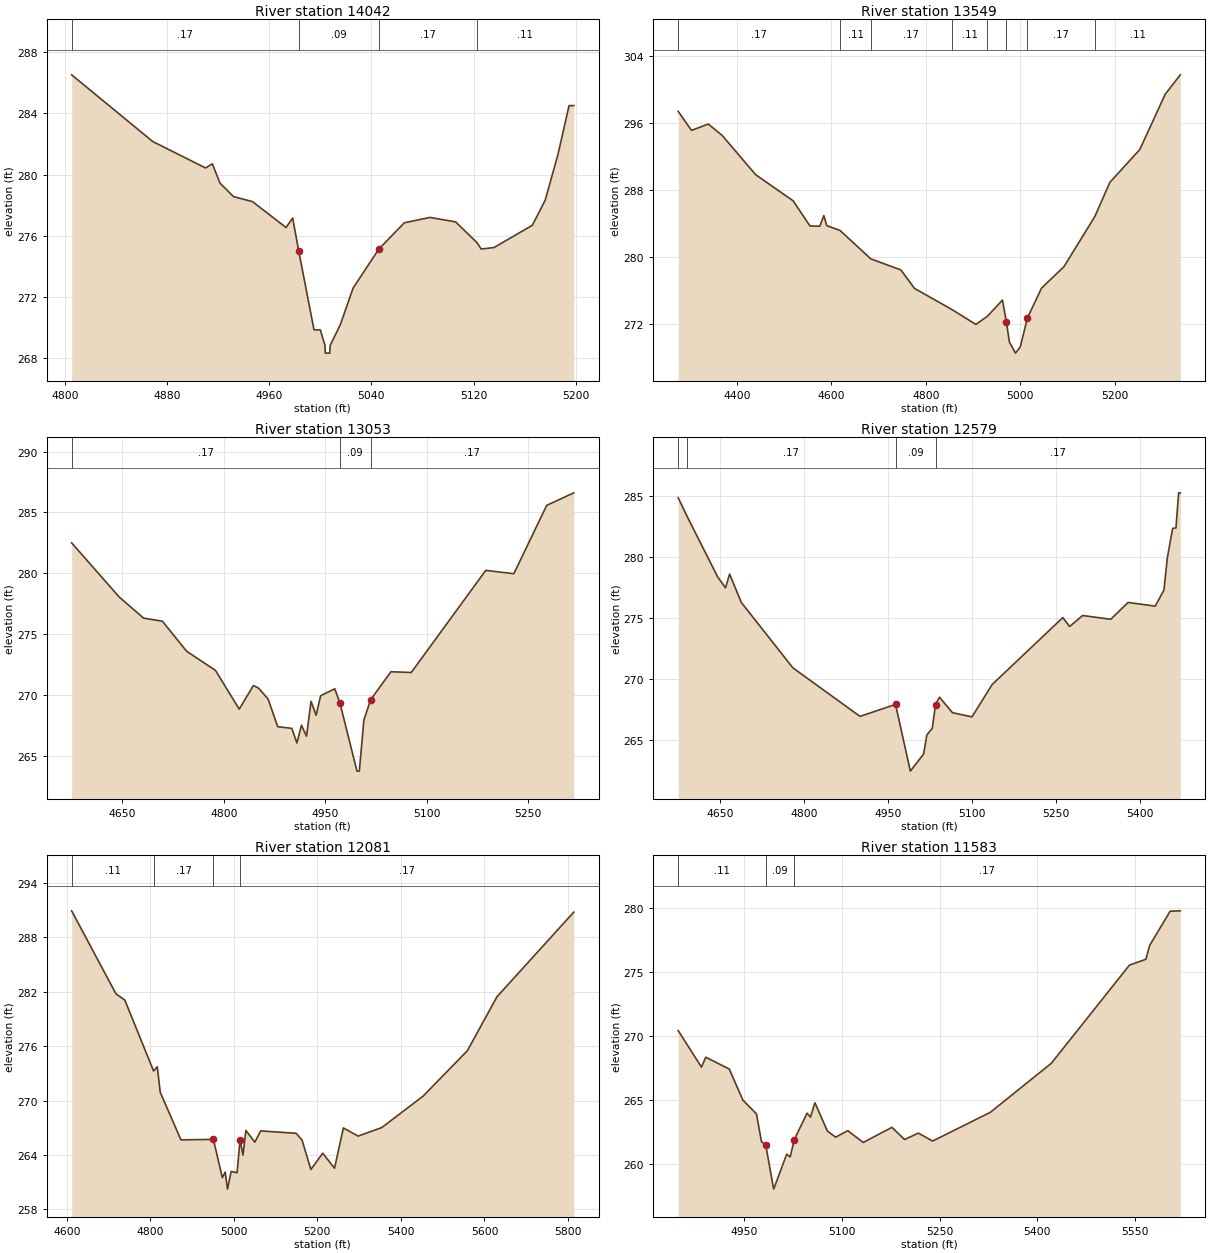
Type RM Length L Ch R = 1 ,14042   ,493,493,493
BEGIN DESCRIPTION:
CCLC 063 13.0
END DESCRIPTION:
XS GIS Cut Line= 3
      3720367.84     10165861.09      3720430.12     10165676.73
      3720417.38     10165478.74
#Sta/Elev= 30
  4805.4  286.51  4868.8  282.16  4910.2  280.43  4915.5   280.7  4921.5  279.44
  4932.1  278.56    4947  278.23  4973.2  276.54  4978.4  277.16 4983.07275.0334
  4995.1  269.86    5000  269.86  5003.7  268.84  5003.9  268.34  5007.4  268.34
  5007.7  268.84  5015.7   270.2  5025.7  272.59  5045.8  275.13  5065.8  276.85
  5085.8   277.2  5105.9  276.91  5122.6  275.56  5125.9  275.14  5135.9  275.23
    5166  276.69    5176  278.32    5186   281.3  5194.7   284.5  5198.4   284.5
#Mann= 4 ,-1 , 0
  4805.4     .17       0 4983.07     .09       0  5045.8     .17       0
  5122.6     .11       0
Bank Sta=4983.07,5045.8
XS Rating Curve= 0 ,0
Exp/Cntr=0.3,0.1

Type RM Length L Ch R = 1 ,13549   ,496,496,496
BEGIN DESCRIPTION:
CCLC 063 12.0
END DESCRIPTION:
XS GIS Cut Line= 3
      3720417.86     10166211.07       3720846.4      10165627.4
      3720967.84     10165311.11
#Sta/Elev= 30
  4275.9  297.45  4304.1  295.17  4339.6  295.93  4368.9  294.58  4439.9  289.88
  4519.4  286.75  4554.9  283.75  4575.7  283.72  4584.2  284.99  4590.4   283.8
  4618.7  283.21  4683.7  279.82  4747.3   278.5  4776.3  276.29  4855.3  273.77
    4906  271.99  4930.6  272.97  4962.3   274.9  4970.6  272.31    4977   269.9
  4989.9  268.56    5000   269.3  5015.1  272.75  5045.1  276.33  5092.5  278.89
  5157.9  284.88  5189.8  288.97  5253.1  292.89  5306.7  299.48  5338.8  301.81
#Mann= 8 ,-1 , 0
  4275.9     .17       0  4618.7     .11       0  4683.7     .17       0
  4855.3     .11       0  4930.6     .17       0  4970.6     .09       0
  5015.1     .17       0  5157.9     .11       0
Bank Sta=4970.6,5015.1
XS Rating Curve= 0 ,0
Exp/Cntr=0.3,0.1

Type RM Length L Ch R = 1 ,13053   ,474,474,474
BEGIN DESCRIPTION:
CCLC 063 11.0
END DESCRIPTION:
XS GIS Cut Line= 3
      3720967.88     10166111.04      3721285.09     10165828.04
      3721267.85      10165511.1
#Sta/Elev= 30
  4574.9   282.5  4645.5  278.04  4681.4  276.32  4709.1  276.07    4745   273.6
  4787.6  272.03  4822.7  268.85  4843.7  270.79  4851.2  270.58  4865.4  269.68
  4879.6  267.41  4900.5  267.27    4908  266.07  4914.7  267.53  4922.2  266.63
  4928.9  269.49  4936.4  268.35  4943.1  269.95    4964  270.52  4971.6  269.35
  4996.8  263.76  5000.3  263.76    5007  267.95    5017  269.62    5047  271.92
  5077.1  271.86  5187.2  280.24  5228.8  279.97  5277.4  285.58  5317.4  286.61
#Mann= 3 , 0 , 0
  4574.9     .17       0  4971.6     .09       0    5017     .17       0
Bank Sta=4971.6,5017
XS Rating Curve= 0 ,0
Exp/Cntr=0.3,0.1

Type RM Length L Ch R = 1 ,12579   ,498,498,498
BEGIN DESCRIPTION:
CCLC 063 10.0
END DESCRIPTION:
XS GIS Cut Line= 3
      3721317.87     10166361.05      3721625.67     10166066.97
      3721867.87     10165661.04
#Sta/Elev= 30
  4574.3  284.84  4589.7  283.36  4644.9  278.35    4659  277.45  4666.3  278.58
  4687.3  276.25  4779.5  270.89  4899.6  266.91  4963.2  267.89  4989.7  262.42
  5013.4  263.82  5019.2  265.38  5028.9  265.93  5034.8  267.88  5041.8  268.48
  5065.1  267.21    5100  266.87    5136  269.52  5262.5  275.01  5274.7  274.28
    5298  275.18  5348.1  274.87  5379.3  276.25  5427.9  275.95  5443.5  277.28
  5449.4  279.88    5459  282.33  5464.9  282.36  5469.7  285.24  5472.7  285.24
#Mann= 4 ,-1 , 0
  4574.3     .11       0  4589.7     .17       0  4963.2     .09       0
  5034.8     .17       0
Bank Sta=4963.2,5034.8
XS Rating Curve= 0 ,0
Exp/Cntr=0.3,0.1

Type RM Length L Ch R = 1 ,12081   ,498,498,498
BEGIN DESCRIPTION:
CCLC 063 9.0
END DESCRIPTION:
XS GIS Cut Line= 3
      3721567.82      10166611.1      3721844.87     10166339.04
      3722417.89     10165761.04
#Sta/Elev= 30
  4611.7  290.94  4717.8  281.78    4739   281.1  4807.9  273.27  4816.8  273.73
  4823.8  270.93  4873.4  265.67  4951.1  265.73  4972.4  261.51  4979.4  262.12
  4984.8  260.24  4993.6  262.19  5007.8  262.05  5014.8  265.67  5021.9  263.99
  5028.9  266.72  5050.2  265.42  5064.3  266.66  5149.2   266.4  5163.3  265.65
  5184.5  262.41  5212.8   264.2  5241.1  262.55  5262.3  266.99  5297.6  266.09
  5354.2  267.03  5453.2   270.5  5559.3  275.52    5630  281.46  5813.9   290.8
#Mann= 4 ,-1 , 0
  4611.7     .11       0  4807.9     .17       0  4951.1     .09       0
  5014.8     .17       0
Bank Sta=4951.1,5014.8
XS Rating Curve= 0 ,0
Exp/Cntr=0.3,0.1

Type RM Length L Ch R = 1 ,11583   ,457,457,457
BEGIN DESCRIPTION:
CCLC 063 8.0
END DESCRIPTION:
XS GIS Cut Line= 3
      3722117.85     10166661.07      3722216.44     10166546.71
      3722417.85     10165961.07
#Sta/Elev= 30
    4849  270.42  4884.7  267.57  4891.3  268.34  4927.4  267.42  4948.3  264.99
  4969.1  263.92  4976.8  261.75  4983.4  261.48  4995.5  258.05  5015.5  260.78
  5020.8  260.56  5027.1  261.91  5046.7  263.97    5052  263.67  5058.8  264.79
  5077.9  262.58  5090.6   262.1  5109.2  262.61  5132.9  261.69  5176.9  262.87
  5196.3  261.92  5217.5  262.42  5239.4   261.8  5327.8  264.04  5421.5  267.87
  5541.2  275.52  5566.4  275.98  5572.4  277.07  5603.7  279.73  5619.3  279.76
#Mann= 3 , 0 , 0
    4849     .11       0  4983.4     .09       0  5027.1     .17       0
Bank Sta=4983.4,5027.1
XS Rating Curve= 0 ,0
Exp/Cntr=0.3,0.1

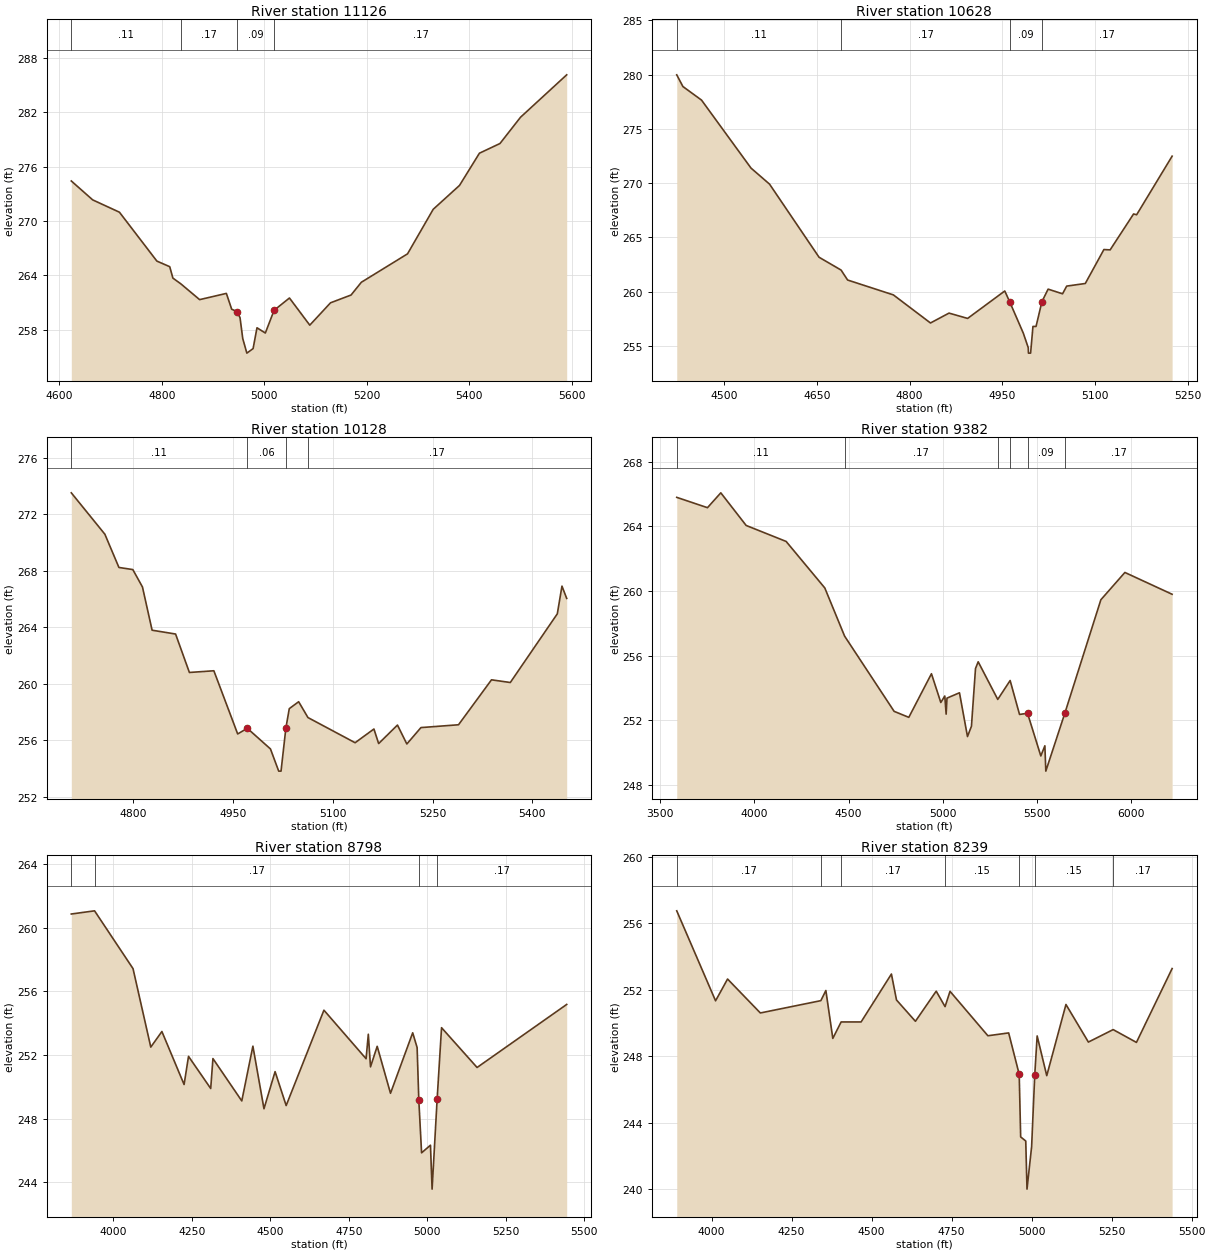
Type RM Length L Ch R = 1 ,11126   ,498,498,498
BEGIN DESCRIPTION:
CCLC 063 7.0
END DESCRIPTION:
XS GIS Cut Line= 3
      3722667.85     10166811.06      3722559.44      10166450.2
      3722517.85     10165861.06
#Sta/Elev= 30
  4623.2  274.42    4665  272.33  4717.2  270.97  4790.3  265.57  4815.4  264.95
  4821.6  263.69  4837.2  263.05  4873.8  261.31    4926     262  4936.4  260.25
  4946.9  259.99  4952.7  259.31    4958  257.01    4966   255.4  4978.2   255.9
  4985.8   258.2  5002.1  257.62  5019.2  260.13  5049.2  261.49  5088.9  258.49
  5129.4  260.96  5169.5  261.82  5189.6  263.23  5279.8  266.37  5329.9  271.29
  5381.3  273.93  5420.2  277.49  5460.3  278.56  5500.4  281.46  5590.6  286.15
#Mann= 4 ,-1 , 0
  4623.2     .11       0  4837.2     .17       0  4946.9     .09       0
  5019.2     .17       0
Bank Sta=4946.9,5019.2
XS Rating Curve= 0 ,0
Exp/Cntr=0.3,0.1

Type RM Length L Ch R = 1 ,10628   ,500,500,500
BEGIN DESCRIPTION:
CCLC 063 6.0
END DESCRIPTION:
XS GIS Cut Line= 3
      3722967.85     10166961.07      3722999.03     10166385.01
      3723017.85      10166161.1
#Sta/Elev= 30
  4423.1  279.99  4433.1  278.91  4463.2  277.66  4543.3  271.39  4573.3  269.91
  4653.4  263.17    4689  261.99  4699.6  261.07  4773.6   259.7  4833.7  257.11
  4863.7  258.02  4893.8  257.53  4953.9  260.06 4962.11  259.03  4983.9  256.17
  4991.9  254.83  4992.2  254.33  4995.7  254.33  4999.5  256.79  5004.5  256.79
    5014  259.07    5024  260.23  5047.4   259.8  5054.1  260.51  5084.2  260.75
  5114.3  263.88  5124.4  263.85  5162.3  267.16  5167.3  267.09  5224.7  272.49
#Mann= 4 ,-1 , 0
  4423.1     .11       0    4689     .17       0 4962.11     .09       0
    5014     .17       0
Bank Sta=4962.11,5014
XS Rating Curve= 0 ,0
Exp/Cntr=0.3,0.1

Type RM Length L Ch R = 1 ,10128   ,746,746,746
BEGIN DESCRIPTION:
CCLC 063 5.0
END DESCRIPTION:
XS GIS Cut Line= 3
      3723117.83     10166911.09      3723296.55     10166678.53
      3723617.86     10166361.06
#Sta/Elev= 30
  4706.7  273.52  4757.2  270.59  4778.3  268.24  4799.2  268.09  4813.7  266.86
  4828.2   263.8  4863.5  263.53  4884.3  260.81  4921.1  260.93  4956.9  256.46
  4971.4  256.86  5006.2   255.4  5018.6  253.83  5022.1  253.83 5029.41256.8808
  5034.5  258.25  5048.6  258.74  5062.6  257.62  5133.5  255.84  5161.8  256.81
  5168.9  255.78  5197.2  257.09  5211.3  255.75  5232.5  256.91    5289  257.11
  5338.6  260.29  5366.9   260.1  5437.6  264.96  5444.6  266.92  5451.7  266.05
#Mann= 4 ,-1 , 0
  4706.7     .11       0  4971.4     .06       0 5029.41     .11       0
  5062.6     .17       0
Bank Sta=4971.4,5029.41
XS Rating Curve= 0 ,0
Exp/Cntr=0.3,0.1

Type RM Length L Ch R = 1 ,9382    ,584,584,584
BEGIN DESCRIPTION:
CCLC 063 4.0
END DESCRIPTION:
XS GIS Cut Line= 3
      3722814.94     10168058.66      3723839.26      10167051.7
      3724653.14     10166182.29
#Sta/Elev= 30
  3588.7   265.8  3751.7  265.16  3822.4  266.08  3956.8  264.06  4168.9  263.07
    4374  260.19  4478.9  257.21  4741.7  252.55  4819.5  252.18  4939.6  254.88
  4989.2   253.1  5010.3   253.5  5017.5  252.38    5022  253.37  5088.2   253.7
  5130.7  250.99  5151.7  251.63  5173.2   255.2  5187.4  255.62  5291.2  253.29
  5356.9  254.46  5406.7  252.36  5449.2  252.43  5519.6  249.79  5541.1  250.42
  5546.1  248.85  5647.1  252.44  5838.1  259.46  5965.5  261.15    6216   259.8
#Mann= 6 ,-1 , 0
  3588.7     .11       0  4478.9     .17       0  5291.2     .11       0
  5356.9     .17       0  5449.2     .09       0  5647.1     .17       0
Bank Sta=5449.2,5647.1
XS Rating Curve= 0 ,0
Exp/Cntr=0.3,0.1

Type RM Length L Ch R = 1 ,8798    ,559,559,559
BEGIN DESCRIPTION:
Mapping XS 0708b473
END DESCRIPTION:
XS GIS Cut Line= 2
      3723492.05     10167593.36       3724605.4      10166474.8
#Sta/Elev= 30
  3866.2  260.85  3940.3  261.05  4062.8  257.42  4119.4  252.49  4154.8  253.47
  4225.5  250.14  4239.6  251.91  4310.3  249.89  4317.4  251.77  4409.3  249.11
  4444.7  252.55    4480  248.62  4515.4  250.95  4550.7  248.82    4671  254.81
  4805.3  251.76  4812.4   253.3  4819.4  251.25  4840.7  252.54  4883.1  249.59
  4953.8  253.39  4967.9  252.46 4973.29249.1576  4982.1  245.85  5010.4  246.33
  5015.6  243.57  5031.6   249.2  5045.7  253.71  5158.9  251.21  5444.4  255.17
#Mann= 4 ,-1 , 0
  3866.2     .11       0  3940.3     .17       0 4973.29     .09       0
  5031.6     .17       0
Bank Sta=4973.29,5031.6
XS Rating Curve= 0 ,0
Exp/Cntr=0.3,0.1

Type RM Length L Ch R = 1 ,8239    ,401,401,401
BEGIN DESCRIPTION:
CCLC 063 3.0
END DESCRIPTION:
XS GIS Cut Line= 3
      3723656.98     10167485.72      3724621.14     10166938.35
      3724606.62     10166499.59
#Sta/Elev= 30
  3891.3  256.74  4012.6  251.33  4050.1  252.64  4152.5   250.6  4341.5  251.34
  4357.2  251.95  4378.9  249.07  4404.9  250.06  4467.3  250.06    4562  252.94
  4577.9  251.38    4637   250.1  4701.9  251.91  4729.6  250.98  4745.1   251.9
  4863.4  249.23  4928.3   249.4 4961.21 246.917  4965.8  243.15  4981.7   242.9
  4985.6  240.01    5000  242.56 5009.82246.8788  5017.3  249.22  5047.3  246.83
  5107.3  251.11  5177.4  248.85  5254.8   249.6  5327.5  248.83    5439  253.27
#Mann= 7 ,-1 , 0
  3891.3     .17       0  4341.5     .15       0  4404.9     .17       0
  4729.6     .15       0 4961.21     .09       0 5009.82     .15       0
  5254.8     .17       0
Bank Sta=4961.21,5009.82
XS Rating Curve= 0 ,0
Exp/Cntr=0.3,0.1

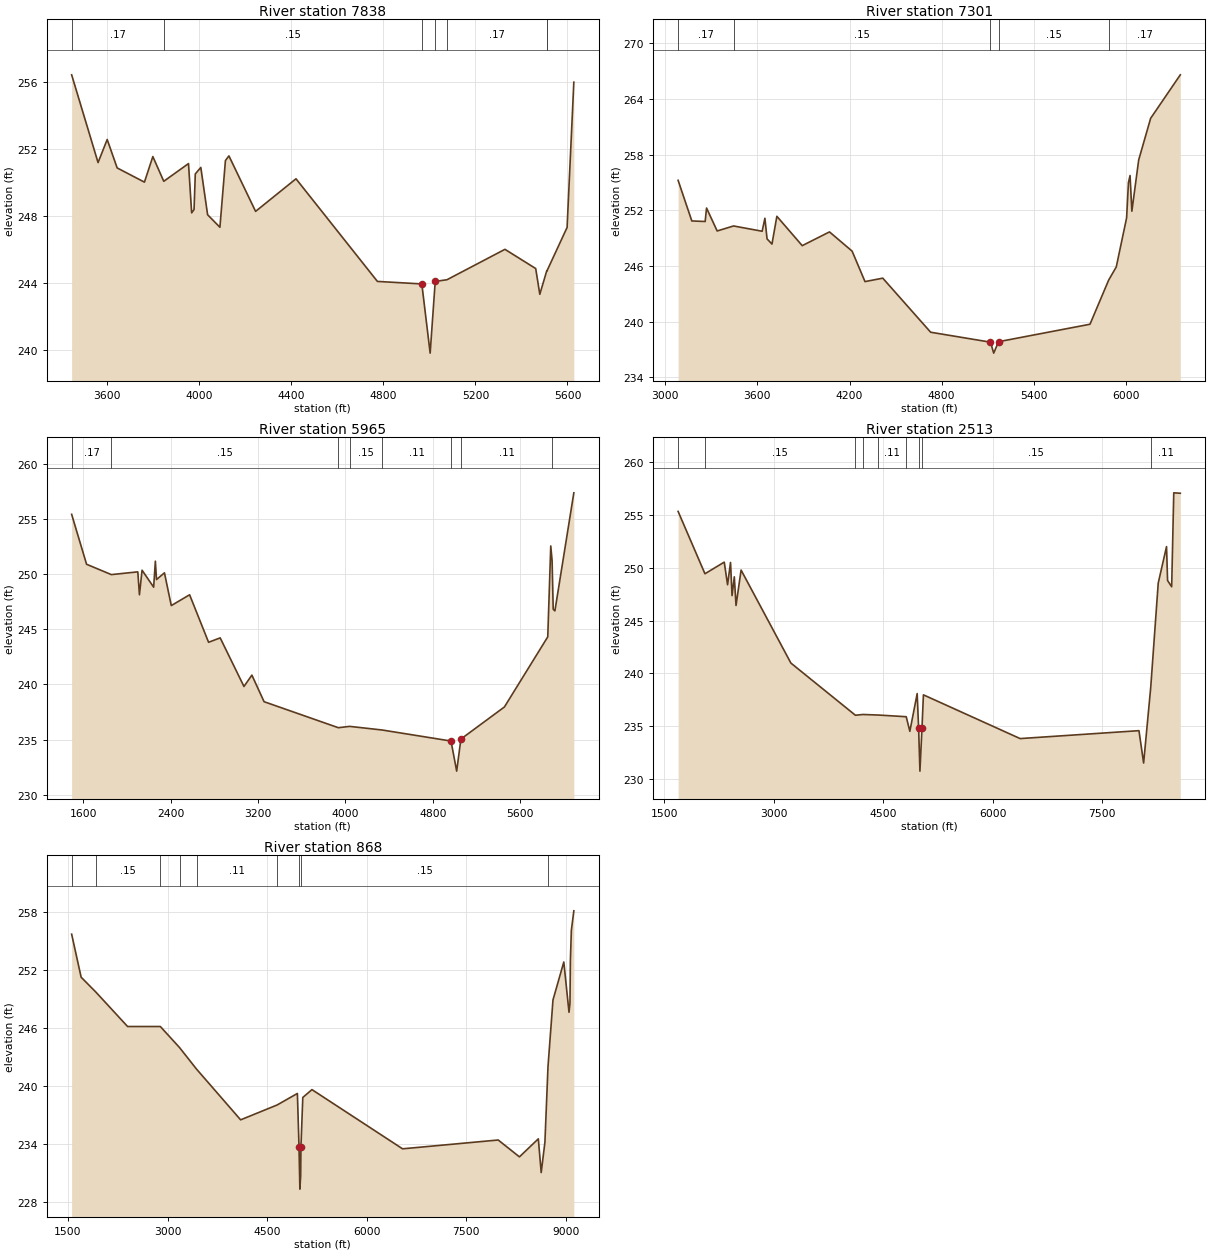
Type RM Length L Ch R = 1 ,7838    ,537,537,537
BEGIN DESCRIPTION:
Mapping XS 1f60e1d3
END DESCRIPTION:
XS GIS Cut Line= 3
      3723674.82     10167488.72      3724969.95     10166960.95
      3724859.05     10166184.66
#Sta/Elev= 30
    3445  256.44  3559.8  251.19  3599.5  252.57  3642.8  250.87  3761.4  250.02
  3797.9  251.55  3845.4  250.07  3952.9  251.13  3966.6  248.18    3977  248.38
  3982.4  250.51  4006.4   250.9  4035.9  248.07  4089.4  247.32  4113.4  251.31
  4128.6  251.59  4244.5  248.27  4420.1  250.22    4774  244.08    4967  243.93
  5003.2  239.79  5025.2  244.08  5076.2  244.18  5328.3     246    5462  244.85
  5479.8  243.31  5510.1  244.72  5510.9  244.71  5598.4  247.31  5627.7     256
#Mann= 7 ,-1 , 0
    3445     .17       0  3845.4     .15       0    4967     .09       0
  5025.2     .15       0  5076.2     .17       0  5510.1     .15       0
  5510.9     .17       0
Bank Sta=4967,5025.2
XS Rating Curve= 0 ,0
Exp/Cntr=0.3,0.1

Type RM Length L Ch R = 1 ,7301    ,1336,1336,1336
BEGIN DESCRIPTION:
CCLC 063 2.0
END DESCRIPTION:
XS GIS Cut Line= 4
      3723700.41      10167494.4       3725384.4     10166947.54
      3725523.29     10166713.16      3724967.71     10165619.37
#Sta/Elev= 30
    3084  255.22  3173.2  250.85  3260.1  250.79  3269.1  252.24  3338.3  249.77
  3445.1  250.31  3631.1  249.74  3649.1  251.14  3663.1  248.92  3695.1  248.36
    3727  251.35  3892.1  248.19  4069.6  249.67  4216.9   247.6  4300.9  244.32
  4416.6  244.69  4728.3  238.87  5117.8   237.8  5138.8  236.62  5170.4  237.85
  5765.7  239.73  5887.3  244.48  5936.9   245.9  6004.2  251.18  6016.1  254.97
  6026.6  255.74  6038.4   251.9  6082.9  257.42  6160.7   261.9  6353.8  266.58
#Mann= 5 ,-1 , 0
    3084     .17       0  3445.1     .15       0  5117.8     .09       0
  5170.4     .15       0  5887.3     .17       0
Bank Sta=5117.8,5170.4
XS Rating Curve= 0 ,0
Exp/Cntr=0.3,0.1

Type RM Length L Ch R = 1 ,5965    ,3452,3452,3452
BEGIN DESCRIPTION:
Mapping XS 770ae8f5
END DESCRIPTION:
XS GIS Cut Line= 4
      3723691.71     10167563.85      3726252.45     10166826.01
      3726304.54     10166174.97      3725688.48     10165055.65
#Sta/Elev= 30
  1494.5  255.44    1631  250.91  1857.8  249.97  2099.9  250.22  2114.9  248.14
  2138.8  250.37    2245  248.83  2260.6  251.19    2271  249.52  2343.8  250.13
  2406.3  247.16    2574  248.14  2747.6  243.83  2853.8  244.23  3071.4  239.82
  3143.9  240.85  3255.4  238.44  3935.1  236.08  4038.9   236.2  4336.6  235.87
  4966.2  234.87    5018  232.14  5056.7  235.05  5454.7  237.96  5851.5  244.32
    5879  252.57  5891.2  251.24  5901.4  246.83  5916.9  246.68  6090.2  257.39
#Mann= 8 ,-1 , 0
  1494.5     .17       0  1857.8     .15       0  3935.1     .11       0
  4038.9     .15       0  4336.6     .11       0  4966.2     .06       0
  5056.7     .11       0  5891.2     .17       0
Bank Sta=4966.2,5056.7
XS Rating Curve= 0 ,0
Exp/Cntr=0.3,0.1

Type RM Length L Ch R = 1 ,2513    ,1645,1645,1645
BEGIN DESCRIPTION:
Mapping XS 1f881643
END DESCRIPTION:
XS GIS Cut Line= 5
      3723682.98     10167607.27       3726721.2     10166808.65
       3727528.5     10166504.83      3727545.86     10165003.09
      3726686.48      10163926.7
#Sta/Elev= 30
  1690.5  255.33  2058.4  249.43  2322.8  250.53  2368.3  248.39    2409   250.5
  2429.7  247.36  2460.7  249.14  2484.2  246.43  2553.7  249.78  3236.1  240.98
  4120.3  236.04  4223.4  236.11  4429.6  236.06  4816.9   235.9  4866.7  234.52
  4967.2  238.09 4986.86  234.82  5004.9  230.75 5033.16234.8378  5052.7  237.97
  6378.3  233.83    8007  234.58    8071  231.52  8168.6   238.7  8271.2  248.55
  8384.9     252  8399.3  248.79  8455.3   248.2  8484.1  257.09  8573.7  257.05
#Mann= 9 ,-1 , 0
  1690.5     .17       0  2058.4     .15       0  4120.3     .11       0
  4223.4     .15       0  4429.6     .11       0  4816.9     .15       0
 4986.86     .09       0 5033.16     .15       0  8168.6     .11       0
Bank Sta=4986.86,5033.16
XS Rating Curve= 0 ,0
Exp/Cntr=0.3,0.1

Type RM Length L Ch R = 1 ,868     ,0,0,0
BEGIN DESCRIPTION:
CCLC 063 1.0
END DESCRIPTION:
XS GIS Cut Line= 5
      3723665.64     10167728.79      3727103.15     10167390.24
       3727615.3     10167121.15      3727641.34     10165011.77
      3726747.27     10163909.38
#Sta/Elev= 30
  1556.1  255.68    1699  251.24  1924.1  249.68  2398.7  246.15  2891.6  246.15
  3180.7  243.98    3436  241.76  4100.6  236.52  4648.9  238.05  4955.2  239.24
 4979.56233.7407  4992.6  229.37  5004.9  230.81 5008.56 233.731  5036.6  238.83
  5174.5  239.64  6538.9  233.53  7978.9  234.44  8298.6   232.7  8583.1  234.56
  8626.2  231.08  8682.2   234.2  8728.5     242  8803.6  248.89  8966.7  252.81
    9045  247.62  9059.4  248.52  9065.8  252.95  9080.2  256.07  9117.7  258.09
#Mann= 9 ,-1 , 0
  1556.1     .17       0  1924.1     .15       0  2891.6     .17       0
  3180.7     .15       0    3436     .11       0  4648.9     .15       0
 4979.56     .09       0 5008.56     .15       0  8728.5     .11       0
Bank Sta=4979.56,5008.56
XS Rating Curve= 0 ,0
Exp/Cntr=0.3,0.1

Chan Stop Cuts=-1
Use User Specified Reach Order=0
Composite Channel Slope=5