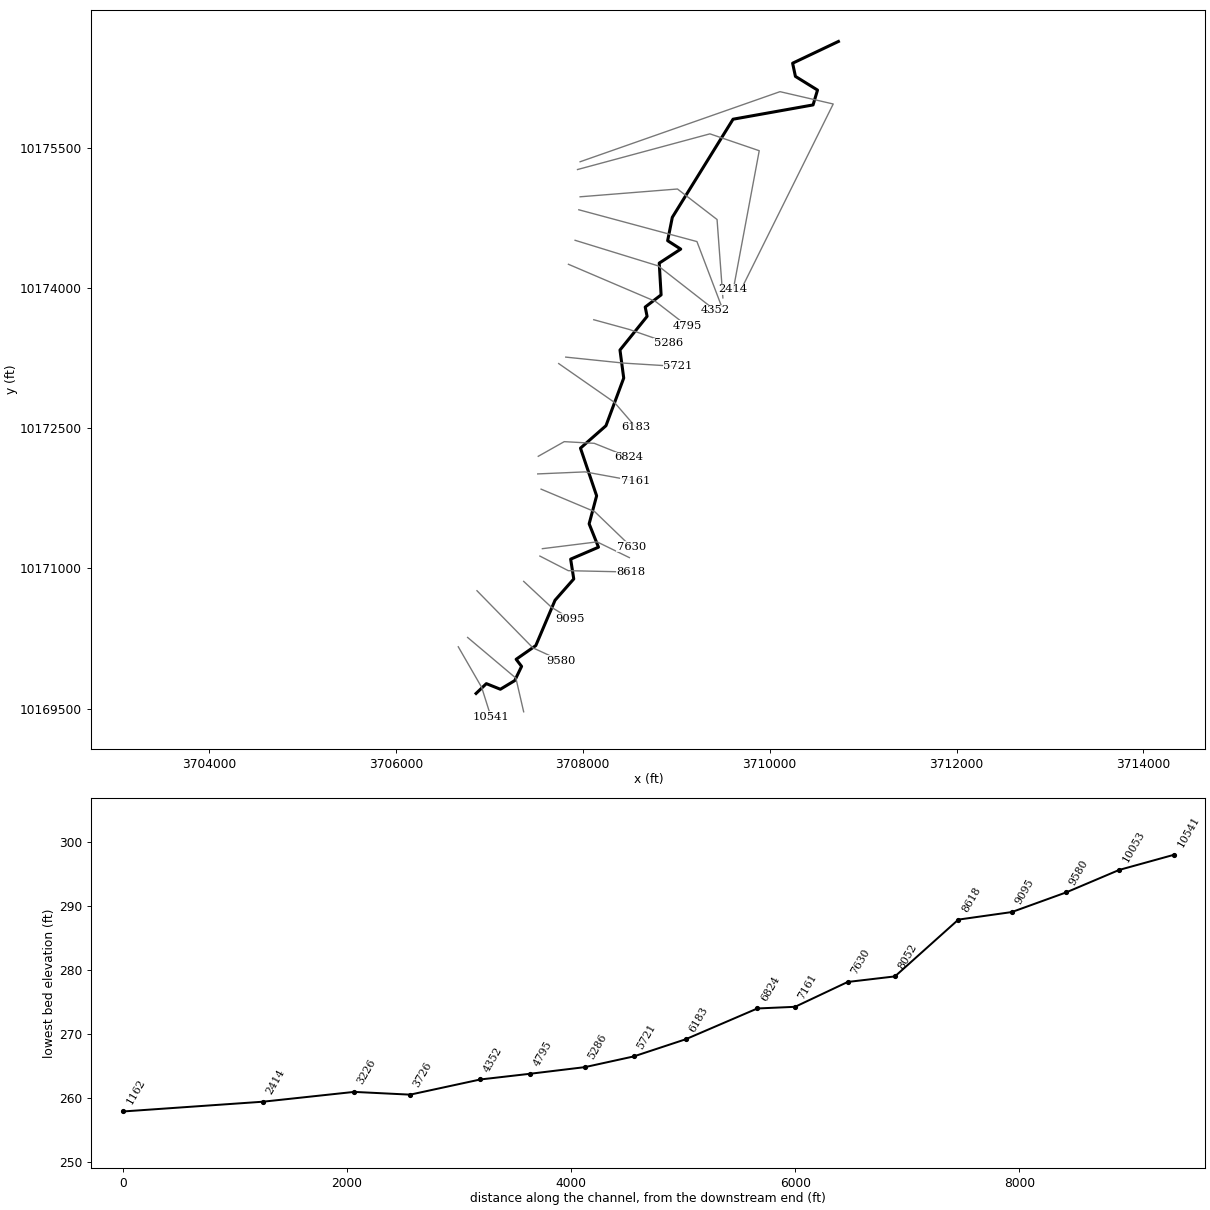
--- CCLC 064.prj (project) ---

Proj Title=CCLC 064 Base Level Engineering
Current Plan=p02
Default Exp/Contr=0.3,0.1
English Units
Geom File=g01
Flow File=f01
Flow File=f02
Plan File=p01
Plan File=p02
Y Axis Title=Elevation
X Axis Title(PF)=Main Channel Distance
X Axis Title(XS)=Station
BEGIN DESCRIPTION:
CCLC 064
END DESCRIPTION:
DSS Export Rating Curves= 0
DSS Export Rating Curve Sorted= 0
DSS Export Volume Flow Curves= 0
DXF OffsetX= 0
DXF OffsetY= 0
DXF ScaleX= 1
DXF ScaleY= 10

--- CCLC 064.p02 (plan) ---

Plan Title=Plan 02
Program Version=4.10
Short Identifier=Plan 02
Geom File=g01
Flow File=f02
Subcritical Flow
K Sum by GR= 0
Std Step Tol= 0.01
Critical Tol= 0.01
Num of Std Step Trials= 20
Max Error Tol= 0.3
Flow Tol Ratio= 0.001
Split Flow NTrial= 30
Split Flow Tol= 0.02
Split Flow Ratio= 0.02
Log Output Level= 0
Friction Slope Method= 1
Unsteady Friction Slope Method= 2
Unsteady Bridges Friction Slope Method= 1
Parabolic Critical Depth
Global Vel Dist= 1 , 1 , 1
Global Log Level= 0
CheckData=True
Encroach Param=-1 ,0,0, 0
BEGIN DESCRIPTION:
Multiple Run
END DESCRIPTION:
Computation Interval=1HOUR
Output Interval=1HOUR
Run HTab= 0
Run UNet= 0
Run PostProcess= 0
Run WQNet= 0
UNET Theta= 1
UNET Theta Warmup= 1
UNET ZTol= 0.02
UNET ZSATol= 0.05
UNET MxIter= 20
UNET MaxInSteps= 0
UNET DtIC= 0
UNET DtMin= 0
UNET MaxCRTS= 20
UNET WFStab= 2
UNET SFStab= 1
UNET WFX= 1
UNET SFX= 1
UNET DSS MLevel= 4
UNET DZMax Abort= 100
UNET Convert EG Bridges= 0
UNET Use Existing IB Tables=-1
UNET Froude Reduction=False
UNET Froude Limit= 1
UNET Froude Power= 10
UNET Time Slicing=0,0, 5
UNET Junction Losses=0
Instantaneous Interval=1HOUR
Write IC File= 0
Write IC File at Sim End=0
Echo Input=False
Echo Parameters=False
Echo Output=False
Write Detailed= 0
WQ AD Non Conservative
WQ ULTIMATE=-1
WQ Max Comp Step=1HOUR
WQ Output Interval=15MIN
WQ Output Selected Increments= 0
WQ Output face flow=0
WQ Output face velocity=0
WQ Output face area=0
WQ Output face dispersion=0
WQ Output cell volume=0
WQ Output cell surface area=0
WQ Output cell continuity=0
WQ Output cumulative cell continuity=0
WQ Output face conc=0
WQ Output face dconc_dx=0
WQ Output face courant=0
WQ Output face peclet=0
WQ Output face adv mass=0
WQ Output face disp mass=0
WQ Output cell mass=0
WQ Output cell source sink temp=0
WQ Output cell source sink nsm=0
WQ Output MaxMinRange=-1
WQ Daily Max Min Mean=-1
WQ Daily Range=0
WQ Daily Time=0
WQ Create Restart=0
WQ Fixed Restart=0
WQ System Summary=0
WQ Use Fixed Temperature=0
Sorting and Armoring Iterations= 10
XS Update Threshold= 0.02
Hydraulics Update Threshold= 0.02
Energy Slope Method= 1
Volume Change Method= 0
XS Weighting Method= 0
Number of US Weighted Cross Sections= 1
Number of DS Weighted Cross Sections= 1
Upstream XS Weight=0.25
Main XS Weight=0.5
Downstream XS Weight=0.25
Number of DS XS's Weighted with US Boundary= 1
Upstream Boundary Weight= 1
Weight of XSs Associated with US Boundary= 0
Number of US XS's Weighted with DS Boundary= 1
Downstream Boundary Weight= 0.5
Weight of XSs Associated with DS Boundary= 0.5
Sediment Output Level= 4
Mass or Volume Output= 0
Output Increment Type= 1
Profile and TS Output Increment= 10
XS Output Flag= 0
XS Output Increment= 10
Disregard all LS=0
Disregard all Conn=0
Disregard all Breaches=0
Disregard all Pumps=0

--- CCLC 064.p01 (plan) ---

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Plan Title=Multiple Run
Short Identifier=Multiple
Geom File=g01
Flow File=f01
Global Vel Dist=  1 , 1 , 1
Encroach Param= -1, 0, 0, 0

--- CCLC 064.f02 (steady flow) ---

Flow Title=Orig_BLE_Flows
Program Version=4.10
Number of Profiles= 7
Profile Names=10-year,25-year,50-year,1pct_min,100-year,1pct_plu,500-year
River Rch & RM=CCLC 064,Reach-1         ,10541
     557     755    1021     455    1374    4149    2573
River Rch & RM=CCLC 064,Reach-1         ,9580
     684     931    1262     562    1698    5128    3180
River Rch & RM=CCLC 064,Reach-1         ,6183
    1142    1600    2213    1004    3032    9156    5894
River Rch & RM=CCLC 064,Reach-1         ,4795
    1121    1561    2147     969    2926    8836    5631
Boundary for River Rch & Prof#=CCLC 064,Reach-1         , 1
Up Type= 0
Dn Type= 3
Dn Slope=0.005
Boundary for River Rch & Prof#=CCLC 064,Reach-1         , 2
Up Type= 0
Dn Type= 3
Dn Slope=0.005
Boundary for River Rch & Prof#=CCLC 064,Reach-1         , 3
Up Type= 0
Dn Type= 3
Dn Slope=0.005
Boundary for River Rch & Prof#=CCLC 064,Reach-1         , 4
Up Type= 0
Dn Type= 3
Dn Slope=0.005
Boundary for River Rch & Prof#=CCLC 064,Reach-1         , 5
Up Type= 0
Dn Type= 3
Dn Slope=0.005
Boundary for River Rch & Prof#=CCLC 064,Reach-1         , 6
Up Type= 0
Dn Type= 3
Dn Slope=0.005
Boundary for River Rch & Prof#=CCLC 064,Reach-1         , 7
Up Type= 0
Dn Type= 3
Dn Slope=0.005
DSS Import GetInterval= 0
DSS Import GetPeak= 0
DSS Import FillOption= 0

--- CCLC 064.f01 (steady flow) ---

Flow Title=Multiple
Number of Profiles=7
Profile Names=10-year,25-year,50-year,1pct_min,100-year,1pct_plu,500-year
River Rch & RM= CCLC 064,Reach-1,10541
     557     740     888     350    1057    3192    1496
River Rch & RM= CCLC 064,Reach-1,9580
     684     913    1097     432    1306    3944    1849
River Rch & RM= CCLC 064,Reach-1,6183
    1142    1569    1924     772    2332    7044    3427
River Rch & RM= CCLC 064,Reach-1,4795
    1121    1530    1867     746    2251    6799    3274
Boundary for River Rch & Prof#=CCLC 064,Reach-1,1
Up Type=0
Dn Type=3
Dn Slope=0.005
Boundary for River Rch & Prof#=CCLC 064,Reach-1,2
Up Type=0
Dn Type=3
Dn Slope=0.005
Boundary for River Rch & Prof#=CCLC 064,Reach-1,3
Up Type=0
Dn Type=3
Dn Slope=0.005
Boundary for River Rch & Prof#=CCLC 064,Reach-1,4
Up Type=0
Dn Type=3
Dn Slope=0.005
Boundary for River Rch & Prof#=CCLC 064,Reach-1,5
Up Type=0
Dn Type=3
Dn Slope=0.005
Boundary for River Rch & Prof#=CCLC 064,Reach-1,6
Up Type=0
Dn Type=3
Dn Slope=0.005
Boundary for River Rch & Prof#=CCLC 064,Reach-1,7
Up Type=0
Dn Type=3
Dn Slope=0.005

--- CCLC 064.g01 (geometry) ---

Geom Title=Existing Conditions
Program Version=4.10

River Reach=CCLC 064        ,Reach-1
Reach XY= 30
      3706858.23     10169661.84      3706968.23     10169766.84
      3707118.23     10169706.84      3707271.94     10169799.45
      3707345.19     10169951.48      3707287.14      10170027.5
      3707497.22       10170174.      3707703.15     10170659.11
      3707903.55     10170887.15      3707870.38       10171099.
      3708168.23     10171226.84      3708068.23     10171476.84
      3708148.23     10171776.84      3707975.42     10172286.84
      3708248.23     10172526.84      3708438.23     10173036.84
      3708398.23     10173336.84      3708688.23     10173696.84
      3708668.23     10173796.84      3708838.23     10173926.84
      3708818.23     10174266.84      3709048.23     10174416.84
      3708908.23     10174506.84      3708958.23     10174756.84
      3709608.23     10175806.84      3710464.39     10175959.74
      3710512.03     10176118.51      3710275.62     10176264.94
      3710245.63     10176406.08      3710735.77     10176638.91

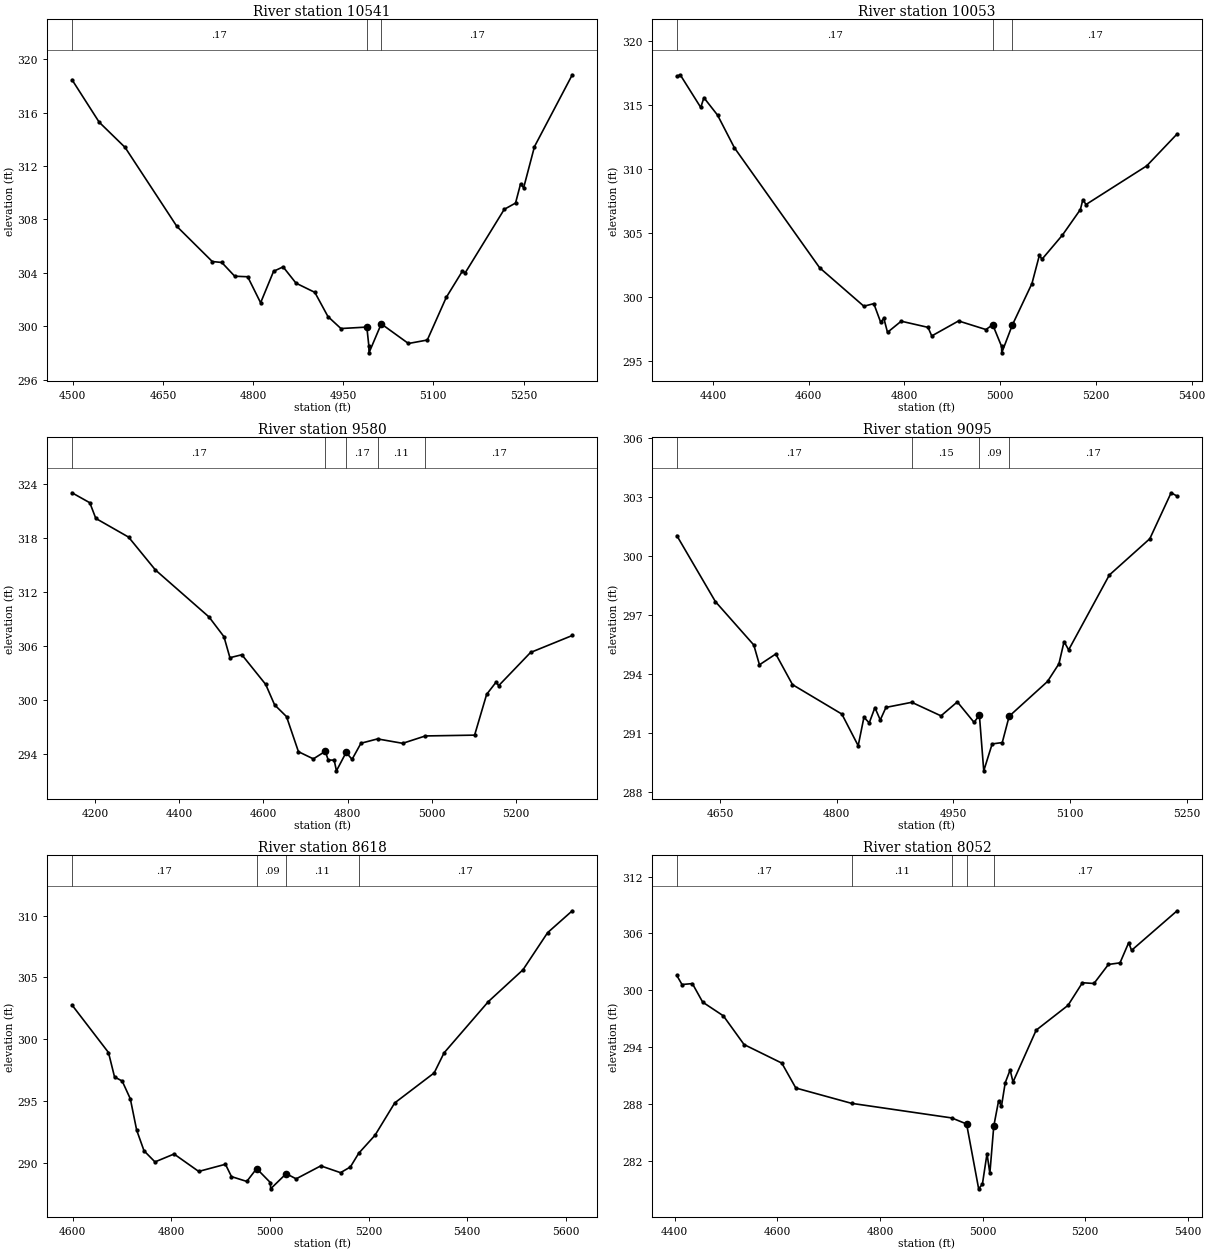
Type RM Length L Ch R = 1 ,10541   ,488,488,488
BEGIN DESCRIPTION:
CCLC 064 16.0
END DESCRIPTION:
XS GIS Cut Line= 3
      3706667.87     10170161.04      3706918.23     10169726.84
      3707017.85     10169411.09
#Sta/Elev= 30
  4498.8  318.46    4544  315.28  4587.1  313.39  4673.3  307.47  4732.2  304.84
    4748  304.77  4769.5  303.74  4791.1   303.7  4812.6  301.75  4834.2  304.11
    4850  304.44  4871.5  303.22  4902.8  302.53  4924.6  300.72  4946.2  299.82
  4989.3  299.93  4992.7   298.5  4992.9     298  5013.3  300.17  5058.5   298.7
  5089.9  298.96  5121.4  302.15    5148   304.1  5153.2  304.01  5217.9  308.75
  5236.7  309.22    5245  310.65  5250.2  310.37  5268.2  313.45  5331.1  318.83
#Mann= 3 , 0 , 0
  4498.8     .17       0  4989.3     .09       0  5013.3     .17       0
Bank Sta=4989.3,5013.3
XS Rating Curve= 0 ,0
Exp/Cntr=0.3,0.1

Type RM Length L Ch R = 1 ,10053   ,473,473,473
BEGIN DESCRIPTION:
CCLC 064 15.0
END DESCRIPTION:
XS GIS Cut Line= 3
      3706767.87     10170261.05      3707284.38     10169825.71
      3707367.44     10169465.67
#Sta/Elev= 30
  4324.5  317.22  4331.6  317.35  4374.5   314.8  4381.1  315.56  4409.6   314.2
  4444.8  311.65  4622.9  302.28  4715.2  299.28    4736  299.48  4750.3  298.03
  4756.9  298.34  4764.6  297.24  4793.2  298.11  4849.2  297.63    4857  296.96
    4913  298.13  4970.1  297.46  4984.4  297.83  5002.9  296.14  5003.2  295.64
  5025.3  297.81  5066.3  301.05    5082  303.28  5087.1  302.94  5129.9  304.83
  5167.5  306.83  5172.6   307.6  5179.2  307.22  5306.1  310.24  5369.5  312.73
#Mann= 3 , 0 , 0
  4324.5     .17       0  4984.4     .09       0  5025.3     .17       0
Bank Sta=4984.4,5025.3
XS Rating Curve= 0 ,0
Exp/Cntr=0.3,0.1

Type RM Length L Ch R = 1 ,9580    ,485,485,485
BEGIN DESCRIPTION:
CCLC 064 14.0
END DESCRIPTION:
XS GIS Cut Line= 3
      3706867.88     10170761.04      3707465.43      10170150.5
      3707767.84     10170011.08
#Sta/Elev= 30
  4145.7  323.05    4188  321.94  4202.2   320.2    4280  318.12  4343.6  314.47
  4470.9  309.24  4506.3  307.05  4520.5  304.71  4548.8  305.04  4605.4  301.74
  4626.5  299.47  4654.8  298.16  4683.1  294.26  4718.5  293.46  4746.8   294.3
  4753.8  293.33  4767.9  293.32  4773.3  292.13  4796.2  294.17  4810.4  293.41
  4831.5   295.2  4870.8  295.68  4930.5  295.19  4984.3  296.01  5101.2   296.1
  5129.7  300.63  5152.6  302.02  5158.1  301.59  5233.9  305.29    5333  307.18
#Mann= 5 ,-1 , 0
  4145.7     .17       0  4746.8     .09       0  4796.2     .17       0
  4870.8     .11       0  4984.3     .17       0
Bank Sta=4746.8,4796.2
XS Rating Curve= 0 ,0
Exp/Cntr=0.3,0.1

Type RM Length L Ch R = 1 ,9095    ,477,477,477
BEGIN DESCRIPTION:
CCLC 064 13.0
END DESCRIPTION:
XS GIS Cut Line= 3
      3707367.82      10170861.1      3707664.45     10170584.48
      3707867.84     10170461.08
#Sta/Elev= 30
  4594.4  301.04    4644  297.68  4693.4  295.47  4700.7  294.46  4721.7  295.01
  4743.2  293.45  4806.7  291.95  4827.7  290.34  4835.1  291.79  4841.9   291.5
  4849.2  292.28  4856.1  291.65  4863.4  292.29  4896.6  292.55  4934.2  291.86
  4955.2  292.57  4976.7  291.53  4983.6  291.89  4989.2  289.06    5000  290.43
    5013   290.5  5021.9  291.84  5071.2  293.61  5085.9  294.51  5092.5  295.64
  5098.4  295.22  5150.7  299.03  5202.8  300.88  5230.2  303.22  5237.9  303.05
#Mann= 4 ,-1 , 0
  4594.4     .17       0  4896.6     .15       0  4983.6     .09       0
  5021.9     .17       0
Bank Sta=4983.6,5021.9
XS Rating Curve= 0 ,0
Exp/Cntr=0.3,0.1

Type RM Length L Ch R = 1 ,8618    ,566,566,566
BEGIN DESCRIPTION:
CCLC 064 12.0
END DESCRIPTION:
XS GIS Cut Line= 3
      3707541.15     10171131.98      3707844.95     10170975.74
      3708517.87     10170961.07
#Sta/Elev= 30
  4598.4  302.77  4672.4  298.92  4684.7  296.94  4700.2  296.61  4716.7  295.17
  4729.6  292.63  4744.5  290.96  4766.7  290.06  4805.4   290.7  4855.4  289.29
  4909.6  289.87  4921.9  288.87  4952.9  288.48  4972.9  289.52  5000.9  288.38
  5001.2  287.88  5032.9  289.11    5053  288.69    5103  289.74    5143  289.19
    5163  289.65  5179.9  290.76    5213  292.22    5253  294.84    5333  297.27
    5353  298.89    5443  303.05  5513.1  305.62  5563.1  308.63  5613.1   310.4
#Mann= 4 ,-1 , 0
  4598.4     .17       0  4972.9     .09       0  5032.9     .11       0
  5179.9     .17       0
Bank Sta=4972.9,5032.9
XS Rating Curve= 0 ,0
Exp/Cntr=0.3,0.1

Type RM Length L Ch R = 1 ,8052    ,422,422,422
BEGIN DESCRIPTION:
CCLC 064 11.0
END DESCRIPTION:
XS GIS Cut Line= 3
      3707567.82     10171211.07      3708153.11      10171283.9
      3708498.81     10171115.37
#Sta/Elev= 30
  4404.5  301.55  4414.6  300.59  4434.8  300.69  4454.9  298.73  4495.2  297.28
  4535.5  294.25    4609  292.29  4636.3  289.66  4744.9  288.04  4939.9   286.5
  4968.9  285.86  4992.4  279.01  4999.7  279.51  5008.7  282.73  5014.2  280.64
  5021.8  285.62  5031.2   288.3  5036.8  287.73  5044.1  290.21  5053.7  291.57
  5059.3  290.29  5104.4  295.77  5166.4  298.39  5194.5  300.78    5217   300.7
  5245.1  302.71  5267.7  302.88  5284.6  305.01  5290.2   304.2  5378.9  308.38
#Mann= 5 ,-1 , 0
  4404.5     .17       0  4744.9     .11       0  4939.9     .17       0
  4968.9     .09       0  5021.8     .17       0
Bank Sta=4968.9,5021.8
XS Rating Curve= 0 ,0
Exp/Cntr=0.3,0.1

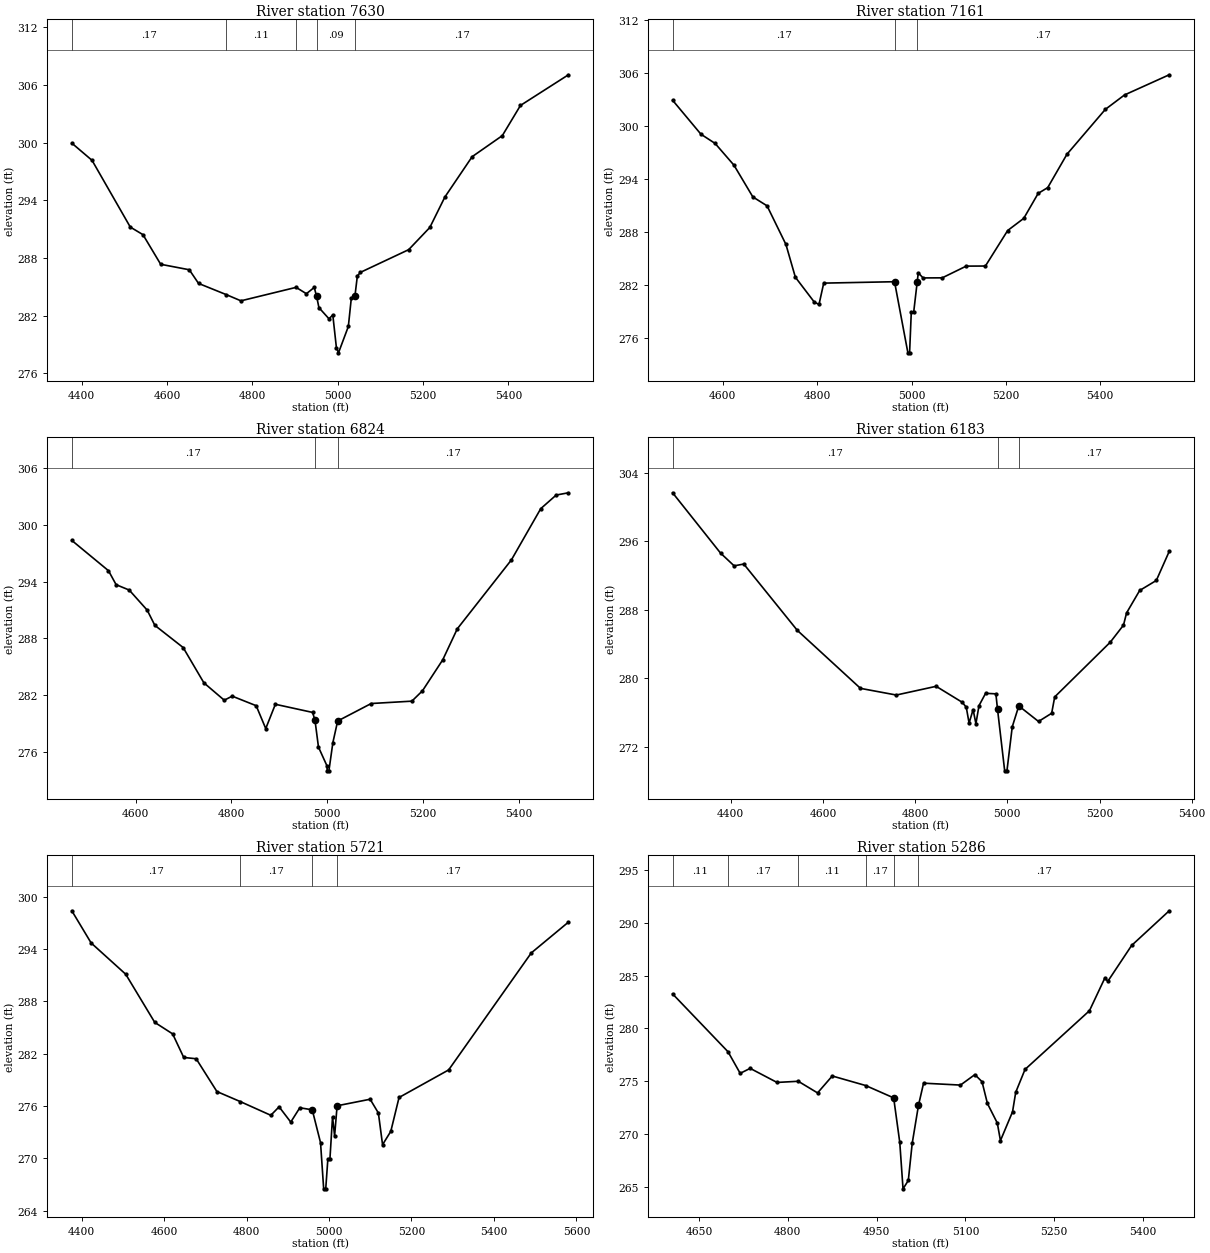
Type RM Length L Ch R = 1 ,7630    ,469,469,469
BEGIN DESCRIPTION:
CCLC 064 10.0
END DESCRIPTION:
XS GIS Cut Line= 3
      3707554.18     10171848.13      3708128.23     10171606.84
      3708517.71      10171231.8
#Sta/Elev= 30
  4377.3  299.95  4424.7  298.16  4514.3  291.22    4544  290.43  4585.5  287.35
  4652.5  286.78  4674.2  285.36  4739.4  284.19  4773.5  283.55  4902.7  284.95
  4926.8  284.29  4945.2  284.94  4950.6  284.05  4956.2  282.84  4979.8  281.68
  4988.7  282.08  4997.1  278.69    5002  278.14  5025.1  280.88  5032.1  283.85
 5040.54284.0465  5046.2  286.13  5053.4  286.51  5166.4  288.87    5216  291.18
  5251.3  294.35  5315.1  298.54  5385.8  300.73  5428.3  303.87  5540.7  307.06
#Mann= 5 ,-1 , 0
  4377.3     .17       0  4739.4     .11       0  4902.7     .17       0
  4950.6     .09       0 5040.54     .17       0
Bank Sta=4950.6,5040.54
XS Rating Curve= 0 ,0
Exp/Cntr=0.3,0.1

Type RM Length L Ch R = 1 ,7161    ,337,337,337
BEGIN DESCRIPTION:
CCLC 064 9.0
END DESCRIPTION:
XS GIS Cut Line= 3
      3707517.86     10172011.07      3708023.79      10172032.9
      3708561.13     10171934.94
#Sta/Elev= 30
  4493.6  302.92  4553.6  299.07  4583.7  298.02  4623.7  295.55  4663.7  291.95
  4693.8  290.94  4733.8  286.56  4753.8  282.84  4793.9  280.02  4803.9  279.75
  4813.9  282.17    4964  282.33  4992.3  274.26  4995.9  274.26  4999.5  278.88
  5004.6  278.88 5012.03282.2962  5014.3  283.34  5024.5  282.76  5065.1  282.77
  5115.9   284.1  5156.6  284.11  5203.8  288.14  5237.9  289.52  5268.4  292.35
  5288.7  293.01  5329.4  296.79  5410.7  301.88  5451.4  303.52  5546.2  305.81
#Mann= 3 , 0 , 0
  4493.6     .17       0    4964     .09       0 5012.03     .17       0
Bank Sta=4964,5012.03
XS Rating Curve= 0 ,0
Exp/Cntr=0.3,0.1

Type RM Length L Ch R = 1 ,6824    ,641,641,641
BEGIN DESCRIPTION:
CCLC 064 8.0
END DESCRIPTION:
XS GIS Cut Line= 4
      3707523.79     10172199.71      3707801.58     10172356.42
      3708122.73     10172338.59      3708491.62     10172191.03
#Sta/Elev= 30
  4466.4  298.37    4543  295.17    4559  293.69  4586.4  293.12  4623.9     291
  4639.9  289.39  4699.1  287.04  4742.4  283.31    4785  281.47  4801.6   281.9
  4851.7  280.89  4871.7  278.47  4891.8  281.04  4969.5  280.18  4974.5  279.39
  4981.9  276.51  4999.9   274.5  5000.1     274  5003.7     274    5012  276.99
    5022  279.27  5092.1  281.12  5177.1  281.37  5199.3  282.47  5241.7  285.75
    5272  289.02  5385.1  296.31  5446.4  301.73  5478.7  303.17  5504.3  303.41
#Mann= 3 , 0 , 0
  4466.4     .17       0  4974.5     .09       0    5022     .17       0
Bank Sta=4974.5,5022
XS Rating Curve= 0 ,0
Exp/Cntr=0.3,0.1

Type RM Length L Ch R = 1 ,6183    ,462,462,462
BEGIN DESCRIPTION:
CCLC 064 7.0
END DESCRIPTION:
XS GIS Cut Line= 3
      3707742.55     10173191.87      3708338.23     10172776.84
      3708567.83     10172511.09
#Sta/Elev= 30
    4274  301.68    4378  294.63  4407.5  293.14  4428.4  293.35  4544.5   285.6
  4681.5  278.82  4759.2  278.04  4845.6  279.06  4902.3  277.19    4911  276.61
  4917.1  274.76  4925.8  276.34  4931.9  274.69  4938.6   276.8  4952.9  278.24
  4975.2  278.18 4978.73276.3912  4994.3  269.18  4999.2  269.18  5010.7  274.32
  5024.9  276.77  5067.7  274.95  5096.2  275.91  5102.8  277.82  5223.4  284.22
    5252  286.21  5258.7  287.64  5287.1  290.26  5323.2  291.43  5351.2  294.83
#Mann= 3 , 0 , 0
    4274     .17       0 4978.73     .09       0  5024.9     .17       0
Bank Sta=4978.73,5024.9
XS Rating Curve= 0 ,0
Exp/Cntr=0.3,0.1

Type RM Length L Ch R = 1 ,5721    ,435,435,435
BEGIN DESCRIPTION:
CCLC 064 6.0
END DESCRIPTION:
XS GIS Cut Line= 3
      3707817.85     10173261.07      3708438.23     10173196.84
      3709017.83     10173161.07
#Sta/Elev= 30
  4376.3  298.38  4423.2  294.69    4507  291.11  4577.4  285.59  4620.8  284.27
  4647.7  281.57  4677.9  281.42  4728.2  277.66  4784.9  276.51  4858.9  274.94
    4879  275.91  4907.3  274.16  4929.2   275.8  4959.4  275.57  4979.5   271.8
  4987.1  266.51  4992.1  266.51  4997.3  269.95  5002.3  269.95  5008.6  274.76
  5013.6  272.58  5019.7  276.03  5099.8  276.78  5119.8   275.2  5129.9  271.57
  5149.9   273.1  5169.9  276.98  5290.2  280.14  5490.6  293.55  5580.7  297.08
#Mann= 4 ,-1 , 0
  4376.3     .17       0  4784.9     .17       0  4959.4     .09       0
  5019.7     .17       0
Bank Sta=4959.4,5019.7
XS Rating Curve= 0 ,0
Exp/Cntr=0.3,0.1

Type RM Length L Ch R = 1 ,5286    ,491,491,491
BEGIN DESCRIPTION:
CCLC 064 5.0
END DESCRIPTION:
XS GIS Cut Line= 3
      3708117.85     10173661.07      3708498.23     10173556.84
      3708917.83     10173411.08
#Sta/Elev= 30
  4605.6  283.27  4699.2   277.8  4719.7  275.76  4736.6  276.23  4781.9   274.9
  4817.8  275.01  4850.4  273.91  4875.2  275.51  4931.5  274.61  4978.9  273.44
  4989.2  269.23  4994.7  264.84  5003.6  265.63  5010.2  269.14  5020.8  272.74
  5029.4  274.83  5091.7  274.65    5116  275.64  5128.1  274.97  5137.2  272.91
  5153.9  271.06  5159.2   269.4  5179.6  272.12    5185  273.97  5200.7  276.13
  5309.5  281.68  5335.3  284.75  5340.6  284.47  5380.7  287.85  5444.2  291.13
#Mann= 6 ,-1 , 0
  4605.6     .11       0  4699.2     .17       0  4817.8     .11       0
  4931.5     .17       0  4978.9     .09       0  5020.8     .17       0
Bank Sta=4978.9,5020.8
XS Rating Curve= 0 ,0
Exp/Cntr=0.3,0.1

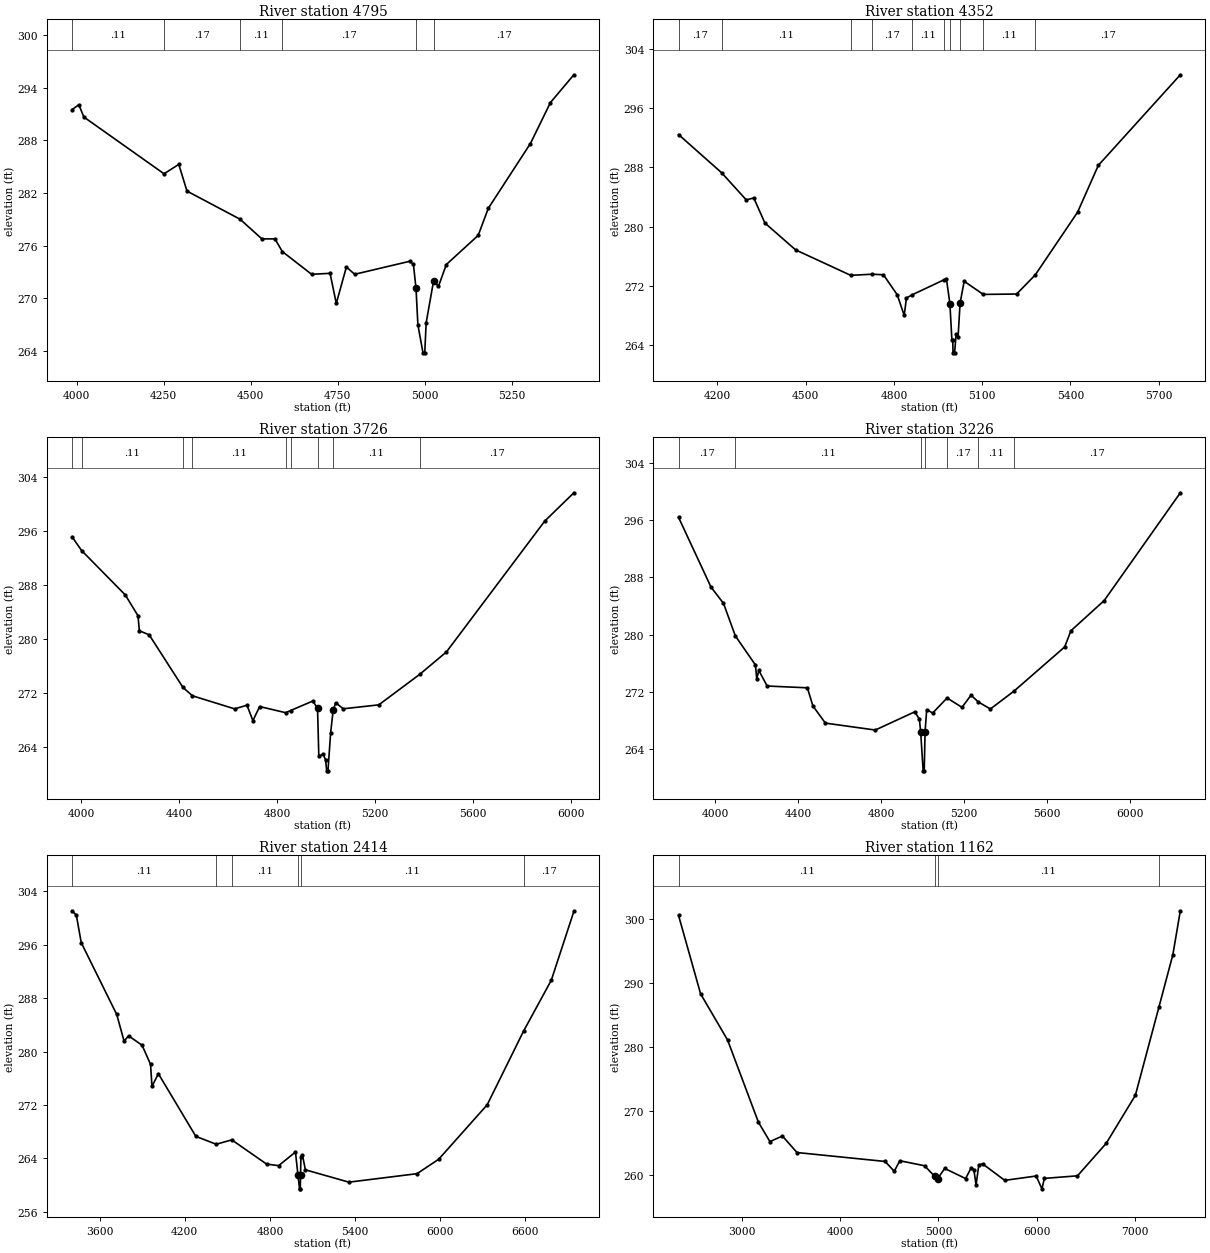
Type RM Length L Ch R = 1 ,4795    ,443,443,443
BEGIN DESCRIPTION:
CCLC 064 4.0
END DESCRIPTION:
XS GIS Cut Line= 3
      3707846.71     10174254.38      3708778.23     10173856.84
      3709116.58     10173595.39
#Sta/Elev= 30
  3987.2  291.49  4006.6  292.04  4021.1  290.64  4251.2  284.18  4293.5  285.25
  4317.1  282.21  4469.4  279.01  4532.1  276.77  4569.5  276.77  4590.7  275.33
  4674.8  272.74  4727.8  272.85  4745.6  269.42  4774.7  273.58  4798.3  272.74
  4956.3  274.22    4967   273.9  4974.5  271.13  4979.9  266.99  4994.5   263.8
  4999.6   263.8  5003.6  267.21  5024.8  271.96  5038.9  271.36  5061.5  273.85
    5153  277.17    5182  280.25  5302.8  287.62  5360.4  292.29  5427.6  295.45
#Mann= 6 ,-1 , 0
  3987.2     .11       0  4251.2     .17       0  4469.4     .11       0
  4590.7     .17       0  4974.5     .09       0  5024.8     .17       0
Bank Sta=4974.5,5024.8
XS Rating Curve= 0 ,0
Exp/Cntr=0.3,0.1

Type RM Length L Ch R = 1 ,4352    ,626,626,626
BEGIN DESCRIPTION:
CCLC 064 3.0
END DESCRIPTION:
XS GIS Cut Line= 3
      3707917.81     10174511.09      3708808.23     10174236.84
      3709417.85     10173761.07
#Sta/Elev= 30
  4068.3  292.46  4214.4   287.3  4298.5  283.61  4323.9  283.88  4361.8  280.48
    4466  276.85  4653.4   273.4  4724.7  273.55  4764.5  273.48  4811.3  270.78
  4835.1  267.97  4842.7  270.34  4862.4  270.77  4968.8  272.77  4978.7  272.88
 4990.31269.5762  4997.2   264.6    5000   264.6    5001  262.91  5006.2  262.91
  5011.7  265.47    5018  264.99  5024.9  269.61  5038.8   272.6  5103.7  270.82
    5217  270.87  5280.4  273.46  5424.2  281.95  5494.7  288.29  5773.3  300.55
#Mann= 10 ,-1 , 0
  4068.3     .17       0  4214.4     .11       0  4653.4     .15       0
  4724.7     .17       0  4862.4     .11       0  4968.8     .17       0
 4990.31     .09       0  5024.9     .17       0  5103.7     .11       0
  5280.4     .17       0
Bank Sta=4990.31,5024.9
XS Rating Curve= 0 ,0
Exp/Cntr=0.3,0.1

Type RM Length L Ch R = 1 ,3726    ,500,500,500
BEGIN DESCRIPTION:
CCLC 064 2.0
END DESCRIPTION:
XS GIS Cut Line= 3
       3707957.8     10174837.72      3709221.69     10174497.44
      3709484.98     10173804.57
#Sta/Elev= 30
  3962.7  295.12  4001.5   293.1  4180.2  286.53    4232  283.46  4237.7  281.24
  4277.7  280.64  4415.7  272.87  4454.4  271.63  4626.8   269.7  4677.3  270.24
  4701.5  267.96  4729.1  270.04  4835.7  269.13  4855.4  269.45  4946.6  270.86
  4965.6  269.77  4970.8  262.67    4988  263.05  4998.4  262.15    5003  260.54
  5008.2  260.54  5019.1  266.16  5029.4  269.48  5039.8   270.6  5070.9  269.71
  5215.8  270.29  5383.1   274.8  5492.4  278.12  5893.9  297.45  6012.8  301.63
#Mann= 9 ,-1 , 0
  3962.7     .17       0  4001.5     .11       0  4415.7     .15       0
  4454.4     .11       0  4835.7     .17       0  4855.4     .11       0
  4965.6     .07       0  5029.4     .11       0  5383.1     .17       0
Bank Sta=4965.6,5029.4
XS Rating Curve= 0 ,0
Exp/Cntr=0.3,0.1

Type RM Length L Ch R = 1 ,3226    ,812,812,812
BEGIN DESCRIPTION:
Mapping XS 29090d57
END DESCRIPTION:
XS GIS Cut Line= 4
      3707971.68     10174976.61      3709013.36     10175059.94
      3709436.97     10174733.55      3709499.36     10173894.64
#Sta/Elev= 30
  3822.6  296.39  3979.3  286.64  4039.5  284.37  4096.7  279.82  4193.5  275.77
    4200  273.84    4210     275  4250.1  272.82  4444.3  272.57  4470.8  270.04
    4531  267.64  4771.8  266.67  4961.9  269.21  4984.6  268.21  4990.9  266.38
  5002.8  260.97    5008  260.97  5012.1  266.42  5019.9  269.52  5048.9  269.05
  5118.2  271.15  5190.2  269.84  5233.7  271.54  5268.9   270.6  5327.1  269.61
  5441.2  272.11  5685.6  278.28  5715.7  280.54  5876.2  284.76  6243.6  299.82
#Mann= 7 ,-1 , 0
  3822.6     .17       0  4096.7     .11       0  4990.9     .07       0
  5012.1     .11       0  5118.2     .17       0  5268.9     .11       0
  5441.2     .17       0
Bank Sta=4990.9,5012.1
XS Rating Curve= 0 ,0
Exp/Cntr=0.3,0.1

Type RM Length L Ch R = 1 ,2414    ,1252,1252,1252
BEGIN DESCRIPTION:
Mapping XS 1347119b
END DESCRIPTION:
XS GIS Cut Line= 4
      3707943.87     10175268.27      3709360.58     10175650.22
      3709888.36     10175469.66      3709610.81     10173984.78
#Sta/Elev= 30
  3405.9  301.08  3435.9  300.43  3470.6   296.3  3720.7  285.55  3772.5  281.54
  3803.6  282.36  3899.4  280.94  3958.9  278.08  3968.9  274.78    4014  276.68
  4277.9   267.3  4421.3  266.12  4531.4  266.77  4776.2  263.15  4861.2  262.91
    4980  264.95  4997.1  261.57  5008.7  259.44  5013.9  259.44 5015.85  261.56
  5018.3  264.18  5028.8  264.53    5050  262.29  5356.5  260.44  5836.5  261.71
  5989.1  263.87  6330.8  272.02  6587.2  283.06  6782.6  290.68  6941.6  300.99
#Mann= 6 ,-1 , 0
  3405.9     .11       0  4421.3     .15       0  4531.4     .11       0
  4997.1     .06       0 5015.85     .11       0  6587.2     .17       0
Bank Sta=4997.1,5015.85
XS Rating Curve= 0 ,0
Exp/Cntr=0.3,0.1

Type RM Length L Ch R = 1 ,1162    ,0,0,0
BEGIN DESCRIPTION:
CCLC 064 1.0
END DESCRIPTION:
XS GIS Cut Line= 4
      3707971.69     10175351.61      3710110.58     10176101.61
      3710680.02     10175969.66      3709680.11     10173955.96
#Sta/Elev= 30
  2358.9  300.54  2583.3   288.3  2857.1  281.12  3170.8  268.29  3287.4  265.28
  3414.5  266.14  3562.9  263.57    4458  262.18    4551  260.65  4607.7  262.29
  4858.8  261.51  4963.3  259.84  4992.2  259.51  5064.1  261.09  5276.1  259.51
  5331.2  261.13  5360.1   260.9  5382.5  258.52  5410.5  261.64  5449.7   261.8
  5673.8  259.23  5993.1  259.91  6051.9  257.91  6077.1  259.54  6413.2  259.94
  6704.5  264.99  7001.4  272.49  7241.3  286.27  7382.4  294.41  7458.3  301.26
#Mann= 4 ,-1 , 0
  2358.9     .11       0  4963.3     .06       0  4992.2     .11       0
  7241.3     .17       0
Bank Sta=4963.3,4992.2
XS Rating Curve= 0 ,0
Exp/Cntr=0.3,0.1

Chan Stop Cuts=-1
Use User Specified Reach Order=0
Composite Channel Slope=5