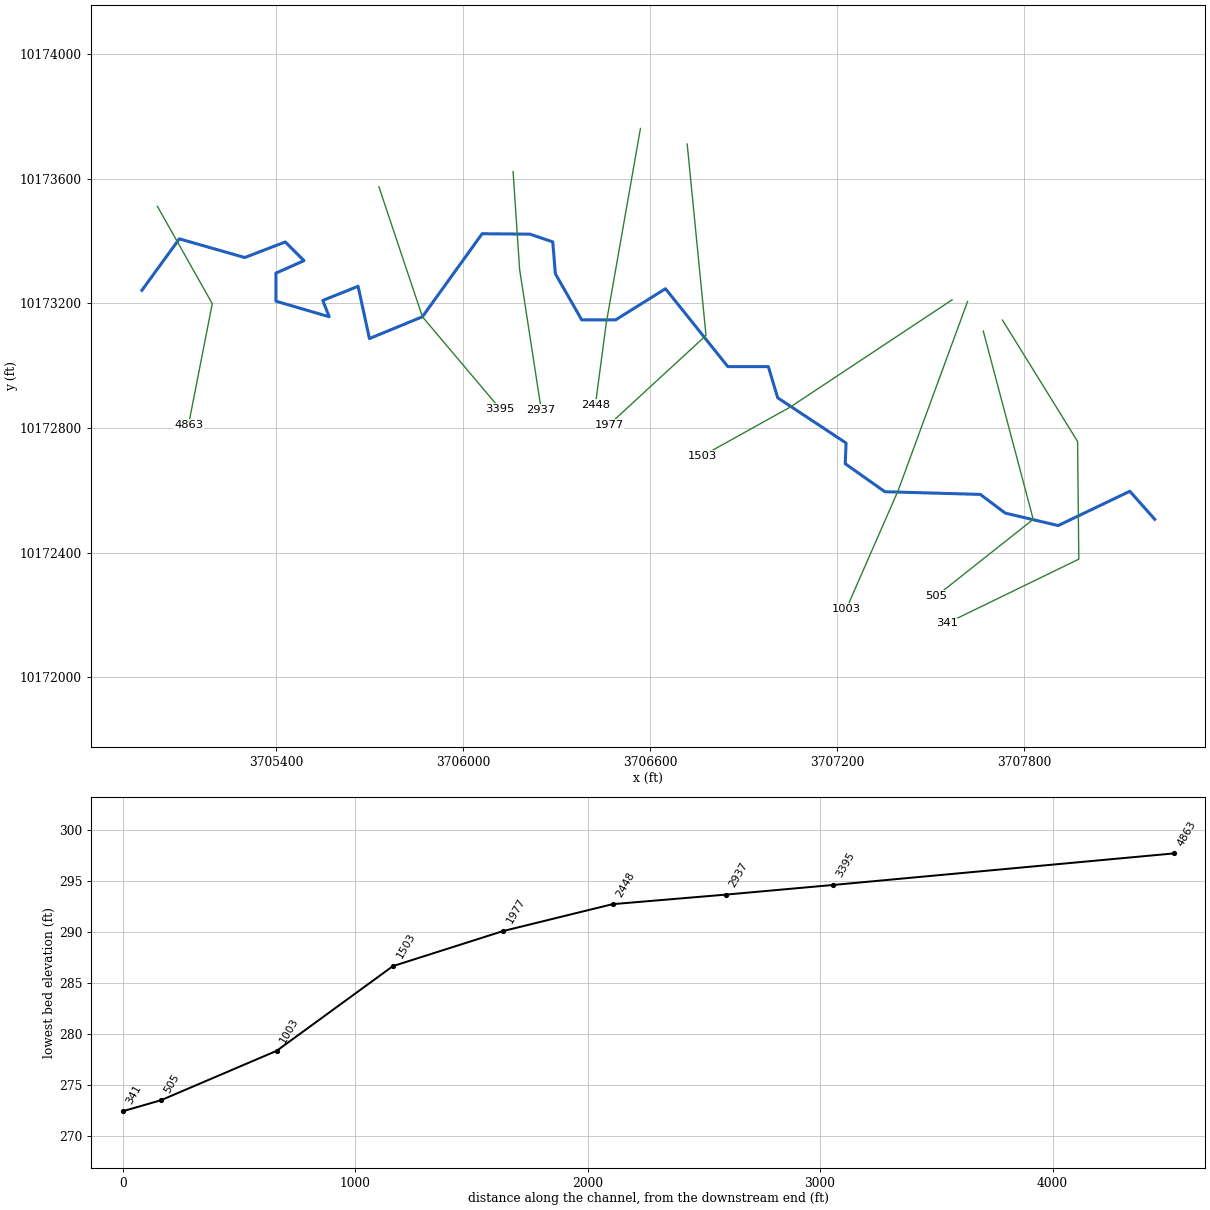
--- CCLC 065.prj (project) ---

Proj Title=CCLC 065 Base Level Engineering
Current Plan=p01
Default Exp/Contr=0.3,0.1
English Units
Geom File=g01
Flow File=f01
Flow File=f02
Plan File=p01
Y Axis Title=Elevation
X Axis Title(PF)=Main Channel Distance
X Axis Title(XS)=Station
BEGIN DESCRIPTION:
CCLC 065
END DESCRIPTION:
DSS Export Rating Curves= 0
DSS Export Rating Curve Sorted= 0
DSS Export Volume Flow Curves= 0
DXF OffsetX= 0
DXF OffsetY= 0
DXF ScaleX= 1
DXF ScaleY= 10

--- CCLC 065.p01 (plan) ---

Plan Title=Multiple Run
Program Version=4.10
Short Identifier=Multiple
Geom File=g01
Flow File=f01
Subcritical Flow
K Sum by GR= 0
Std Step Tol= 0.01
Critical Tol= 0.01
Num of Std Step Trials= 20
Max Error Tol= 0.3
Flow Tol Ratio= 0.001
Split Flow NTrial= 30
Split Flow Tol= 0.02
Split Flow Ratio= 0.02
Log Output Level= 0
Friction Slope Method= 1
Unsteady Friction Slope Method= 2
Unsteady Bridges Friction Slope Method= 1
Parabolic Critical Depth
Global Vel Dist= 1 , 1 , 1
Global Log Level= 0
CheckData=True
Encroach Param=-1 ,0,0, 0
BEGIN DESCRIPTION:
Multiple Run
END DESCRIPTION:
Computation Interval=1HOUR
Output Interval=1HOUR
Run HTab= 0
Run UNet= 0
Run PostProcess= 0
Run WQNet= 0
UNET Theta= 1
UNET Theta Warmup= 1
UNET ZTol= 0.02
UNET ZSATol= 0.05
UNET MxIter= 20
UNET MaxInSteps= 0
UNET DtIC= 0
UNET DtMin= 0
UNET MaxCRTS= 20
UNET WFStab= 2
UNET SFStab= 1
UNET WFX= 1
UNET SFX= 1
UNET DSS MLevel= 4
UNET DZMax Abort= 100
UNET Convert EG Bridges= 0
UNET Use Existing IB Tables=-1
UNET Froude Reduction=False
UNET Froude Limit= 1
UNET Froude Power= 10
UNET Time Slicing=0,0, 5
UNET Junction Losses=0
Instantaneous Interval=1HOUR
Write IC File= 0
Write IC File at Sim End=0
Echo Input=False
Echo Parameters=False
Echo Output=False
Write Detailed= 0
WQ AD Non Conservative
WQ ULTIMATE=-1
WQ Max Comp Step=1HOUR
WQ Output Interval=15MIN
WQ Output Selected Increments= 0
WQ Output face flow=0
WQ Output face velocity=0
WQ Output face area=0
WQ Output face dispersion=0
WQ Output cell volume=0
WQ Output cell surface area=0
WQ Output cell continuity=0
WQ Output cumulative cell continuity=0
WQ Output face conc=0
WQ Output face dconc_dx=0
WQ Output face courant=0
WQ Output face peclet=0
WQ Output face adv mass=0
WQ Output face disp mass=0
WQ Output cell mass=0
WQ Output cell source sink temp=0
WQ Output cell source sink nsm=0
WQ Output MaxMinRange=-1
WQ Daily Max Min Mean=-1
WQ Daily Range=0
WQ Daily Time=0
WQ Create Restart=0
WQ Fixed Restart=0
WQ System Summary=0
WQ Use Fixed Temperature=0
Sorting and Armoring Iterations= 10
XS Update Threshold= 0.02
Hydraulics Update Threshold= 0.02
Energy Slope Method= 1
Volume Change Method= 0
XS Weighting Method= 0
Number of US Weighted Cross Sections= 1
Number of DS Weighted Cross Sections= 1
Upstream XS Weight=0.25
Main XS Weight=0.5
Downstream XS Weight=0.25
Number of DS XS's Weighted with US Boundary= 1
Upstream Boundary Weight= 1
Weight of XSs Associated with US Boundary= 0
Number of US XS's Weighted with DS Boundary= 1
Downstream Boundary Weight= 0.5
Weight of XSs Associated with DS Boundary= 0.5
Sediment Output Level= 4
Mass or Volume Output= 0
Output Increment Type= 1
Profile and TS Output Increment= 10
XS Output Flag= 0
XS Output Increment= 10
Disregard all LS=0
Disregard all Conn=0
Disregard all Breaches=0
Disregard all Pumps=0

--- CCLC 065.f01 (steady flow) ---

Flow Title=Multiple
Program Version=4.10
Number of Profiles= 7
Profile Names=10-year,25-year,50-year,1pct_min,100-year,1pct_plu,500-year
River Rch & RM=CCLC 065,Reach-1         ,4863
     532     709     948     417    1258    3799    2296
Boundary for River Rch & Prof#=CCLC 065,Reach-1         , 1
Up Type= 0
Dn Type= 3
Dn Slope=0.009
Boundary for River Rch & Prof#=CCLC 065,Reach-1         , 2
Up Type= 0
Dn Type= 3
Dn Slope=0.009
Boundary for River Rch & Prof#=CCLC 065,Reach-1         , 3
Up Type= 0
Dn Type= 3
Dn Slope=0.009
Boundary for River Rch & Prof#=CCLC 065,Reach-1         , 4
Up Type= 0
Dn Type= 3
Dn Slope=0.009
Boundary for River Rch & Prof#=CCLC 065,Reach-1         , 5
Up Type= 0
Dn Type= 3
Dn Slope=0.009
Boundary for River Rch & Prof#=CCLC 065,Reach-1         , 6
Up Type= 0
Dn Type= 3
Dn Slope=0.009
Boundary for River Rch & Prof#=CCLC 065,Reach-1         , 7
Up Type= 0
Dn Type= 3
Dn Slope=0.009
DSS Import GetInterval= 0
DSS Import GetPeak= 0
DSS Import FillOption= 0

--- CCLC 065.f02 (steady flow) ---

Flow Title=Orig_BLE_Flows
Program Version=4.10
Number of Profiles= 7
Profile Names=10-year,25-year,50-year,1pct_min,100-year,1pct_plu,500-year
River Rch & RM=CCLC 065,Reach-1         ,4863
     532     695     824     321     968    2925    1335
Boundary for River Rch & Prof#=CCLC 065,Reach-1         , 1
Up Type= 0
Dn Type= 3
Dn Slope=0.009
Boundary for River Rch & Prof#=CCLC 065,Reach-1         , 2
Up Type= 0
Dn Type= 3
Dn Slope=0.009
Boundary for River Rch & Prof#=CCLC 065,Reach-1         , 3
Up Type= 0
Dn Type= 3
Dn Slope=0.009
Boundary for River Rch & Prof#=CCLC 065,Reach-1         , 4
Up Type= 0
Dn Type= 3
Dn Slope=0.009
Boundary for River Rch & Prof#=CCLC 065,Reach-1         , 5
Up Type= 0
Dn Type= 3
Dn Slope=0.009
Boundary for River Rch & Prof#=CCLC 065,Reach-1         , 6
Up Type= 0
Dn Type= 3
Dn Slope=0.009
Boundary for River Rch & Prof#=CCLC 065,Reach-1         , 7
Up Type= 0
Dn Type= 3
Dn Slope=0.009
DSS Import GetInterval= 0
DSS Import GetPeak= 0
DSS Import FillOption= 0

--- CCLC 065.g01 (geometry) ---

Geom Title=Existing Conditions
Program Version=4.10

River Reach=CCLC 065        ,Reach-1
Reach XY= 30
      3704968.23     10173241.84      3705088.23     10173406.84
      3705298.23     10173346.84      3705428.23     10173396.84
      3705488.23     10173336.84      3705398.23     10173296.84
      3705398.23     10173206.84      3705569.08     10173156.84
      3705548.47     10173209.06       3705661.8     10173254.67
      3705698.23     10173086.84      3705868.23     10173156.84
      3706059.85     10173423.28      3706213.26      10173421.9
      3706286.51     10173397.02       3706294.8     10173294.75
      3706379.45     10173146.84      3706488.23     10173146.84
      3706648.23     10173246.84      3706848.23     10172996.84
      3706978.23     10172996.84      3707008.23     10172896.84
      3707227.71     10172751.59      3707224.95     10172685.25
       3707352.1     10172595.41      3707658.23     10172586.84
      3707738.23     10172526.84      3707908.23     10172486.84
      3708138.23     10172596.84      3708218.23     10172506.84

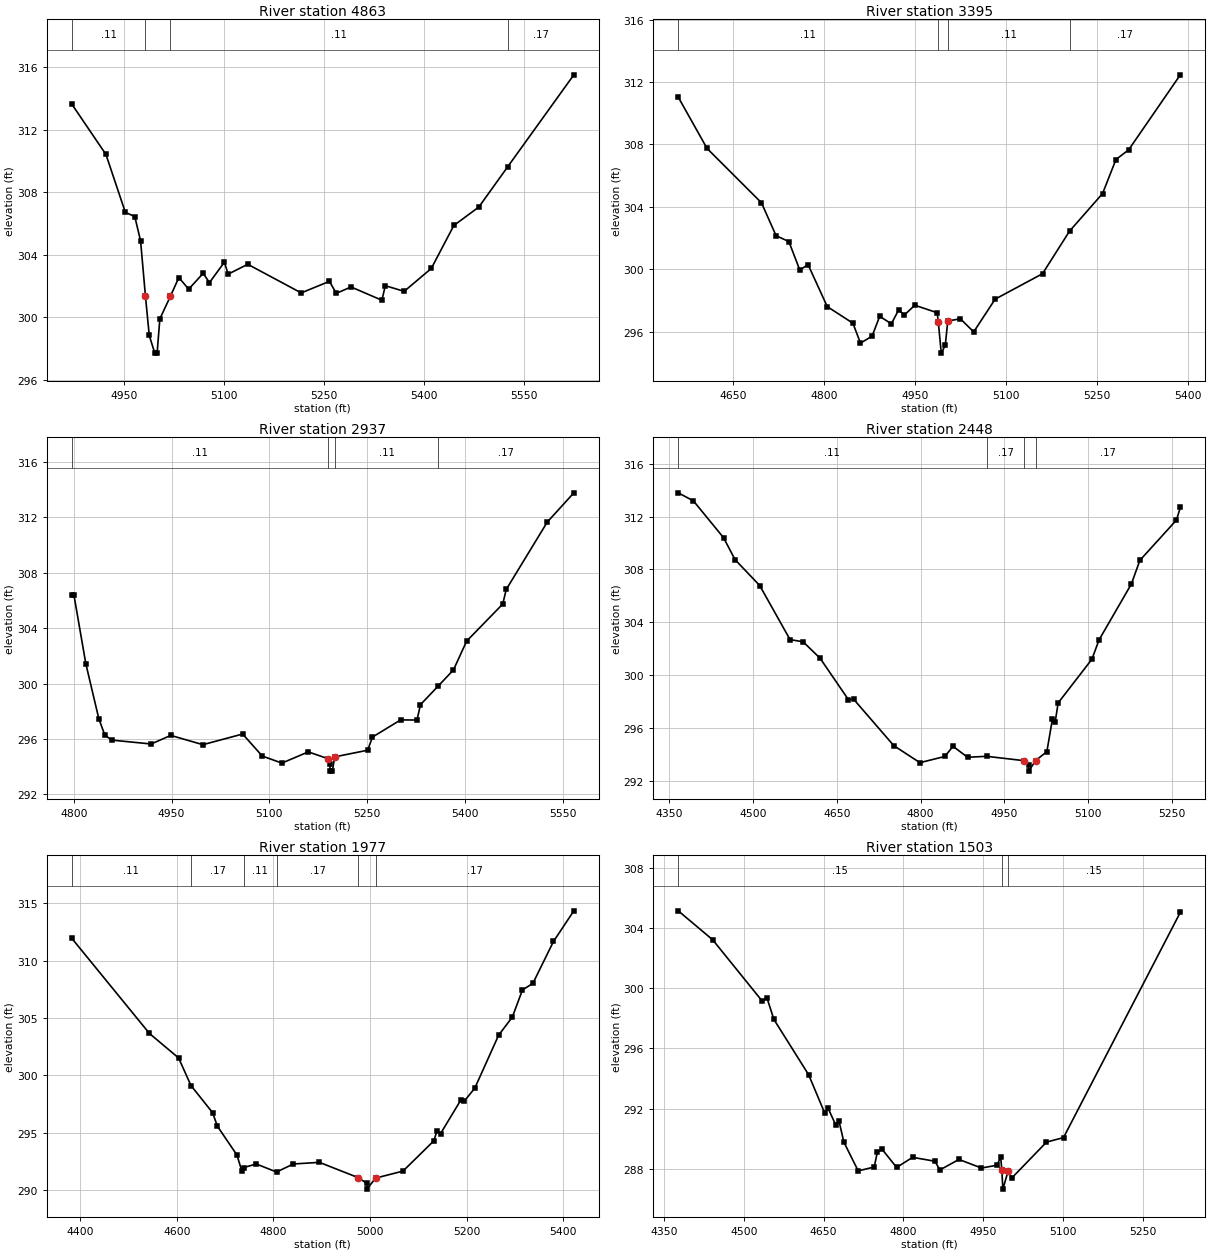
Type RM Length L Ch R = 1 ,4863    ,1468,1468,1468
BEGIN DESCRIPTION:
CCLC 065 8.0
END DESCRIPTION:
XS GIS Cut Line= 3
      3705017.84     10173511.09      3705193.91     10173198.83
      3705117.86      10172811.1
#Sta/Elev= 30
  4871.8  313.64  4923.1  310.42  4952.2  306.72  4966.4  306.45  4975.1  304.89
  4982.3   301.4  4988.1  298.85  4996.4  297.72  4999.9  297.72    5004  299.91
  5019.9  301.36  5032.5  302.55  5047.3  301.81    5069  302.82  5078.5  302.23
  5100.8  303.53  5106.6  302.77  5135.9   303.4  5216.2  301.57  5258.6  302.31
  5268.8  301.54    5291  301.95  5337.3   301.1  5342.4  302.03  5370.7  301.67
  5411.4  303.13  5445.3  305.88  5482.8  307.06  5525.9  309.62  5625.4  315.51
#Mann= 4 ,-1 , 0
  4871.8     .11       0  4982.3     .07       0  5019.9     .11       0
  5525.9     .17       0
Bank Sta=4982.3,5019.9
XS Rating Curve= 0 ,0
Exp/Cntr=0.3,0.1

Type RM Length L Ch R = 1 ,3395    ,458,458,458
BEGIN DESCRIPTION:
CCLC 065 7.0
END DESCRIPTION:
XS GIS Cut Line= 3
      3705728.64      10173573.8      3705868.23     10173156.84
      3706117.83     10172861.09
#Sta/Elev= 30
  4560.3  311.03  4607.8  307.74  4697.3  304.26  4721.4  302.15  4742.5  301.77
  4760.4  299.95  4774.1  300.29  4805.7   297.6  4847.9  296.54  4860.4  295.26
  4879.5  295.71    4892  296.98  4911.2   296.5  4923.5  297.41  4932.3  297.05
  4949.8  297.69  4986.7  297.21  4988.5296.6222  4993.4  294.62    5000  295.12
  5004.1  296.68  5024.9  296.82  5046.8  295.98  5082.1  298.08  5160.1  299.71
  5204.6  302.44    5259  304.85    5281  307.03  5301.9  307.65    5387  312.46
#Mann= 4 ,-1 , 0
  4560.3     .11       0  4988.5     .06       0  5004.1     .11       0
  5204.6     .17       0
Bank Sta=4988.5,5004.1
XS Rating Curve= 0 ,0
Exp/Cntr=0.3,0.1

Type RM Length L Ch R = 1 ,2937    ,489,489,489
BEGIN DESCRIPTION:
CCLC 065 6.0
END DESCRIPTION:
XS GIS Cut Line= 3
      3706159.19     10173622.49      3706180.02     10173309.94
      3706249.46     10172858.59
#Sta/Elev= 30
  4796.9  306.43  4800.1  306.43  4818.4  301.45  4838.4  297.46  4847.7  296.27
  4858.5  295.92  4918.6  295.64  4948.7  296.26    4998  295.59  5058.9  296.36
    5089  294.77  5119.1  294.26  5159.6  295.07  5189.7  294.58  5192.8  294.18
    5193  293.68  5196.5  293.68  5200.1  294.71  5250.6  295.19    5258  296.14
  5301.2  297.38  5326.3  297.37  5331.6  298.48  5358.9  299.83  5382.2  300.99
  5402.4  303.07  5457.8  305.75  5463.1   306.8  5526.1  311.67  5566.8  313.78
#Mann= 4 ,-1 , 0
  4796.9     .11       0  5189.7     .06       0  5200.1     .11       0
  5358.9     .17       0
Bank Sta=5189.7,5200.1
XS Rating Curve= 0 ,0
Exp/Cntr=0.3,0.1

Type RM Length L Ch R = 1 ,2448    ,471,471,471
BEGIN DESCRIPTION:
CCLC 065 5.0
END DESCRIPTION:
XS GIS Cut Line= 3
      3706567.86     10173761.09      3706458.23     10173136.84
      3706423.32     10172874.26
#Sta/Elev= 30
  4366.2   313.8  4393.4  313.19  4447.4   310.4  4467.8  308.75  4512.1  306.78
  4566.4  302.69  4589.6  302.53    4620  301.29  4670.8  298.15    4680  298.19
    4752  294.67  4798.8  293.38  4843.4  293.85  4858.1  294.62    4884  293.79
  4918.2  293.86  4985.6  293.53  4993.3  293.24  4993.6  292.74  5005.8  293.54
    5026  294.21  5035.9  296.65    5041  296.47  5046.2   297.9  5106.7  301.21
  5119.3  302.66  5177.3   306.9  5192.5  308.69    5258  311.74  5264.9  312.69
#Mann= 4 ,-1 , 0
  4366.2     .11       0  4918.2     .17       0  4985.6     .09       0
  5005.8     .17       0
Bank Sta=4985.6,5005.8
XS Rating Curve= 0 ,0
Exp/Cntr=0.3,0.1

Type RM Length L Ch R = 1 ,1977    ,474,474,474
BEGIN DESCRIPTION:
CCLC 065 4.0
END DESCRIPTION:
XS GIS Cut Line= 3
      3706717.85     10173711.08      3706778.23     10173096.84
      3706467.85     10172811.07
#Sta/Elev= 30
  4382.8  311.94  4543.6  303.65  4603.9  301.52  4629.5  299.12  4674.2  296.76
  4684.3  295.57  4724.5  293.08  4734.5  291.72  4738.9  291.98  4764.6  292.29
  4806.6  291.59  4841.4  292.29  4895.3  292.43  4975.7   291.1  4993.4   290.6
  4993.6   290.1  5011.6  291.06  5068.3  291.67  5131.8  294.29  5138.6  295.13
    5146  294.93  5188.5  297.89  5195.3  297.77  5216.9  298.89  5266.2   303.5
  5294.6  305.08  5315.6  307.45  5337.1  308.01  5379.7  311.66  5421.9  314.33
#Mann= 6 ,-1 , 0
  4382.8     .11       0  4629.5     .17       0  4738.9     .11       0
  4806.6     .17       0  4975.7     .09       0  5011.6     .17       0
Bank Sta=4975.7,5011.6
XS Rating Curve= 0 ,0
Exp/Cntr=0.3,0.1

Type RM Length L Ch R = 1 ,1503    ,500,500,500
BEGIN DESCRIPTION:
CCLC 065 3.0
END DESCRIPTION:
XS GIS Cut Line= 3
      3707567.85     10173211.07      3707048.23     10172866.84
      3706767.89     10172711.09
#Sta/Elev= 30
  4376.7  305.13  4441.4  303.21  4534.6  299.14  4543.7  299.33  4556.6  297.92
  4621.9  294.25    4652  291.72    4658  292.06    4673  290.91    4679  291.17
  4688.1  289.78  4715.1  287.87  4745.2  288.13  4751.2  289.14  4760.3  289.29
  4787.3   288.1  4817.4  288.77  4859.5  288.51  4868.5  287.93  4904.5  288.63
  4946.8  288.06  4976.5  288.25  4982.9  288.82 4985.05287.9278  4987.1  286.66
  4997.2  287.89  5003.9   287.4  5069.1  289.78  5101.1  290.08  5320.7  305.03
#Mann= 3 , 0 , 0
  4376.7     .15       0 4985.05     .09       0  4997.2     .15       0
Bank Sta=4985.05,4997.2
XS Rating Curve= 0 ,0
Exp/Cntr=0.3,0.1

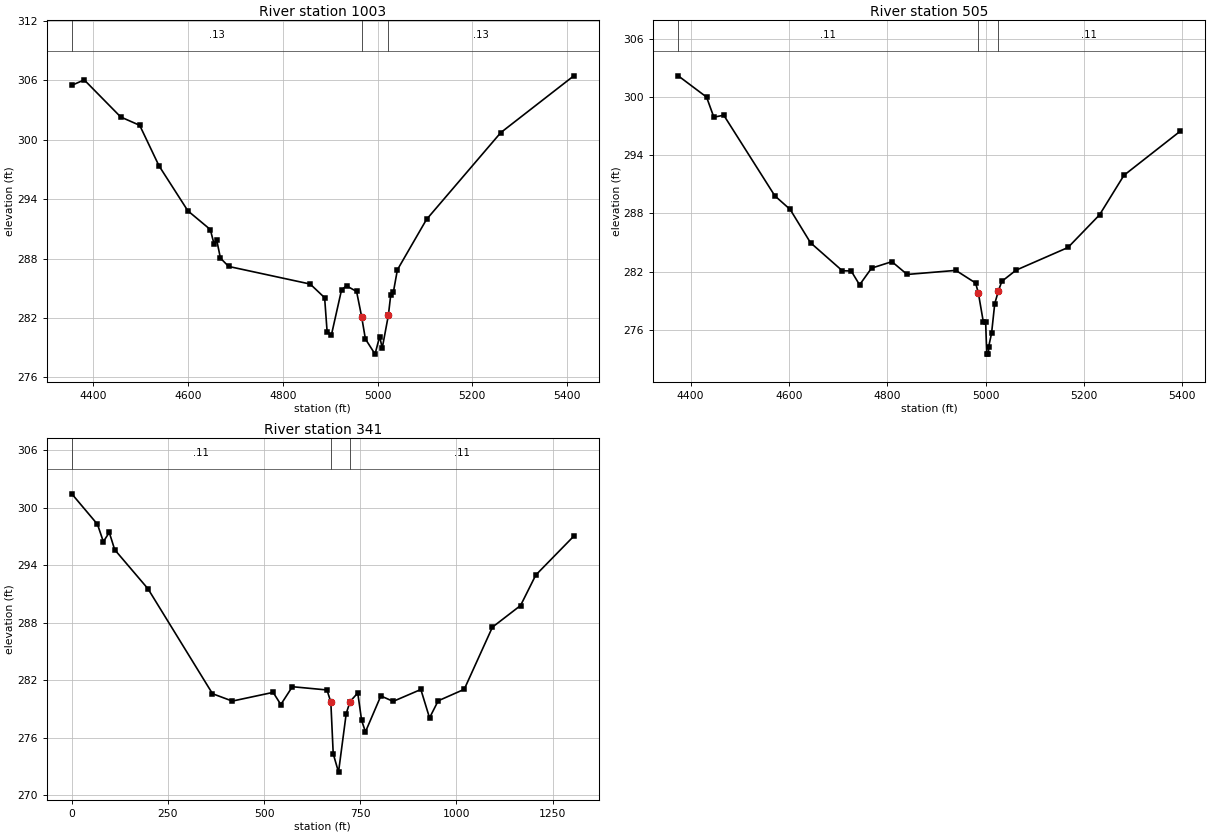
Type RM Length L Ch R = 1 ,1003    ,498,498,498
BEGIN DESCRIPTION:
CCLC 065 2.0
END DESCRIPTION:
XS GIS Cut Line= 3
      3707617.53     10173205.79      3707394.94     10172599.56
      3707228.63     10172219.67
#Sta/Elev= 30
  4354.2  305.51  4380.5  306.06  4457.6  302.31  4497.7  301.47  4538.4  297.38
  4599.4  292.83  4646.8  290.94    4655  289.43  4660.4  289.86  4668.2  288.05
  4685.5  287.21  4857.8  285.43  4888.3  284.05  4893.6  280.58  4902.5  280.26
  4924.1  284.86  4934.5  285.25  4955.8  284.68  4966.4  282.15  4974.4  279.88
  4994.8  278.35  5004.5  280.13    5010  278.96 5022.98282.2881  5027.9  284.32
  5033.4  284.59    5042  286.87  5103.5  291.96  5260.3  300.73  5414.7  306.47
#Mann= 3 , 0 , 0
  4354.2     .13       0  4966.4     .08       0 5022.98     .13       0
Bank Sta=4966.4,5022.98
XS Rating Curve= 0 ,0
Exp/Cntr=0.3,0.1

Type RM Length L Ch R = 1 ,505     ,164,164,164
BEGIN DESCRIPTION:
CCLC 065 1.0
END DESCRIPTION:
XS GIS Cut Line= 3
      3707667.86     10173111.02      3707828.23     10172506.84
      3707517.85     10172261.07
#Sta/Elev= 30
  4374.9  302.18  4432.5  299.99  4447.3  297.92  4467.5  298.12  4571.4  289.81
  4602.5  288.41  4643.9  284.98  4708.6  282.09  4726.6  282.07  4743.7  280.64
    4768  282.36  4809.4  283.03  4840.4  281.71  4939.4  282.13  4979.6  280.83
  4985.3  279.77  4995.2  276.85    5000  276.85  5002.3   273.5  5005.8   273.5
  5006.1  274.25  5012.1  275.66  5018.5  278.69    5026  280.02  5032.9     281
  5061.8  282.15  5167.5  284.49  5231.6  287.85  5281.3  291.93  5395.9  296.48
#Mann= 3 , 0 , 0
  4374.9     .11       0  4985.3     .07       0    5026     .11       0
Bank Sta=4985.3,5026
XS Rating Curve= 0 ,0
Exp/Cntr=0.3,0.1

Type RM Length L Ch R = 1 ,341     ,0,0,0
XS GIS Cut Line= 4
      3707729.66     10173145.97      3707970.55     10172756.65
      3707974.45     10172379.04      3707551.27     10172173.32
#Sta/Elev= 30
       0  301.45    66.8  298.27    82.1  296.46    97.5  297.42   111.6  295.62
     198  291.55   365.8   280.6   417.3  279.83   523.4  280.74   543.4  279.47
   573.4  281.33   663.4  280.99   673.4  279.72   679.6  274.34   693.4  272.42
   713.4  278.53   723.4  279.78   743.4  280.68   753.4  277.82   763.4  276.62
   803.4  280.37   835.4   279.8   907.4  281.04     930  278.08   952.5  279.86
  1020.2  281.06  1093.4  287.54  1166.6   289.8  1206.2  292.98  1305.1  297.04
#Mann= 3 , 0 , 0
       0     .11       0   673.4     .06       0   723.4     .11       0
Bank Sta=673.4,723.4
XS Rating Curve= 0 ,0
Exp/Cntr=0.3,0.1

Chan Stop Cuts=-1
Use User Specified Reach Order=0
Composite Channel Slope=5