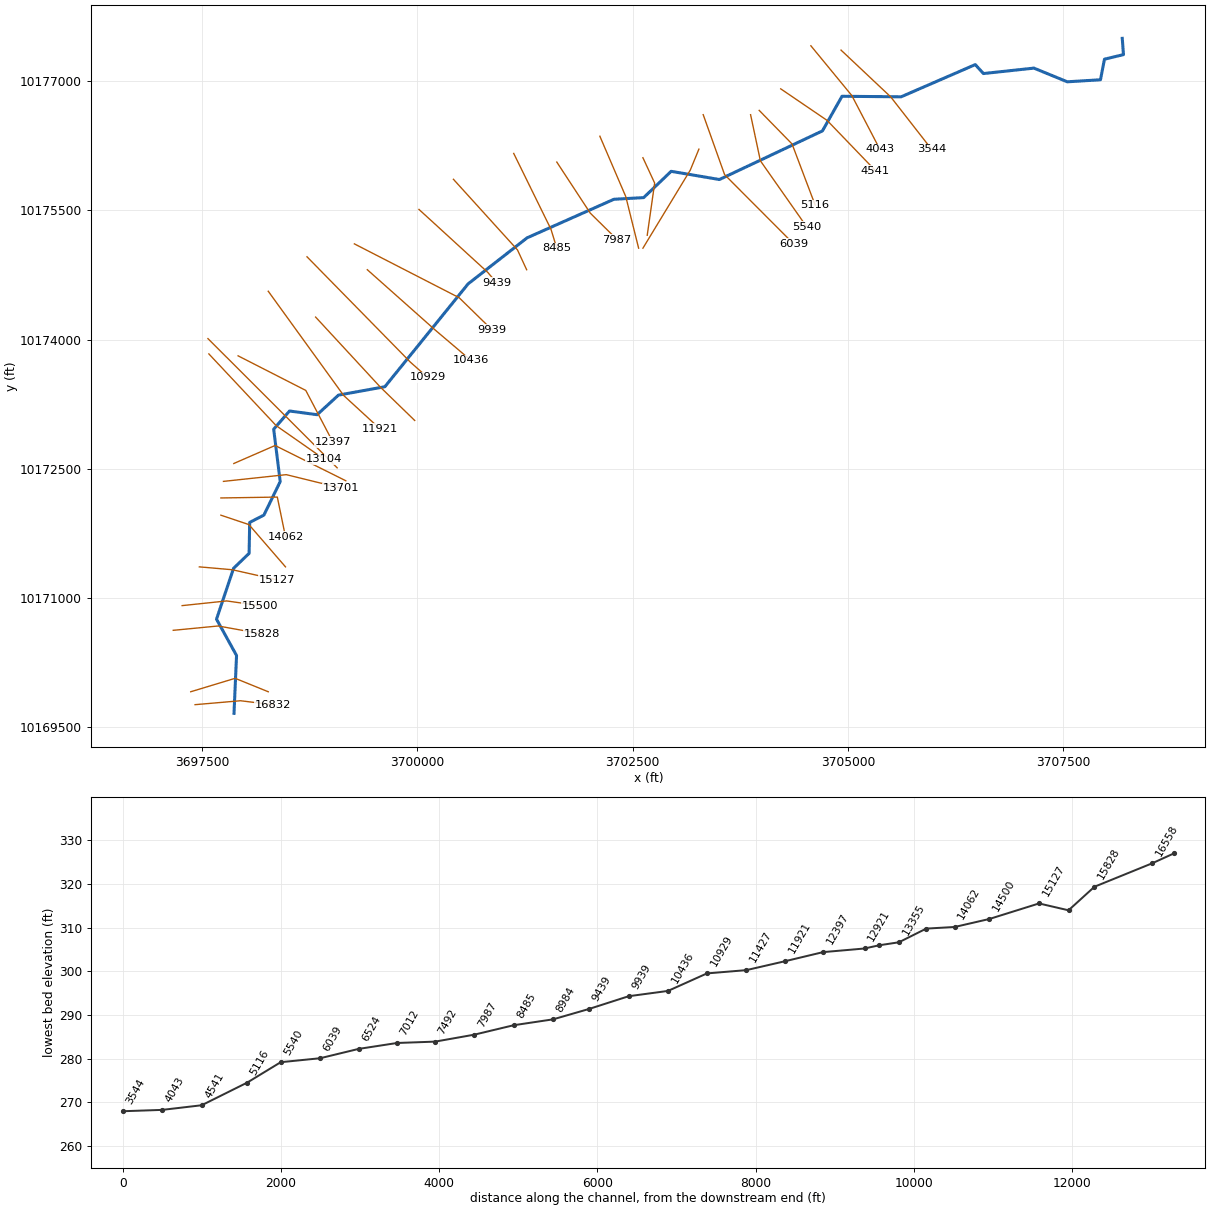
--- CCLC 066.prj (project) ---

Proj Title=CCLC 066 Base Level Engineering
Current Plan=p01
Default Exp/Contr=0.3,0.1
English Units
Geom File=g01
Flow File=f01
Flow File=f02
Plan File=p01
Y Axis Title=Elevation
X Axis Title(PF)=Main Channel Distance
X Axis Title(XS)=Station
BEGIN DESCRIPTION:
CCLC 066
END DESCRIPTION:
DSS Export Rating Curves= 0
DSS Export Rating Curve Sorted= 0
DSS Export Volume Flow Curves= 0
DXF OffsetX= 0
DXF OffsetY= 0
DXF ScaleX= 1
DXF ScaleY= 10

--- CCLC 066.p01 (plan) ---

Plan Title=Multiple Run
Short Identifier=Multiple
Geom File=g01
Flow File=f01
Subcritical Flow
K Sum by GR= 0
Std Step Tol= 0.01
Critical Tol= 0.01
Num of Std Step Trials= 20
Max Error Tol= 0.3
Flow Tol Ratio= 0.001
Split Flow NTrial= 30
Split Flow Tol= 0.02
Split Flow Ratio= 0.02
Log Output Level= 0
Friction Slope Method= 1
Unsteady Friction Slope Method= 2
Unsteady Bridges Friction Slope Method= 1
Parabolic Critical Depth
Global Vel Dist=  1 , 1 , 1
Global Log Level= 0
CheckData=True
Encroach Param= -1, 0, 0, 0
BEGIN DESCRIPTION:
Multiple Run
END DESCRIPTION:

--- CCLC 066.f01 (steady flow) ---

Flow Title=Multiple
Program Version=4.10
Number of Profiles= 7
Profile Names=10-year,25-year,50-year,1pct_min,100-year,1pct_plu,500-year
River Rch & RM=CCLC 066,Reach-1         ,16832
     401     533     712     314     948    2863    1730
River Rch & RM=CCLC 066,Reach-1         ,13701
     594     810    1099     492    1485    4485    2800
River Rch & RM=CCLC 066,Reach-1         ,13104
    1309    1859    2592    1186    3583   10820    7088
River Rch & RM=CCLC 066,Reach-1         ,10436
    1528    2183    3056    1402    4235   12789    8433
River Rch & RM=CCLC 066,Reach-1         ,7492
    1721    2448    3419    1564    4723   14263    9338
Boundary for River Rch & Prof#=CCLC 066,Reach-1         , 1
Up Type= 0
Dn Type= 3
Dn Slope=0.005
Boundary for River Rch & Prof#=CCLC 066,Reach-1         , 2
Up Type= 0
Dn Type= 3
Dn Slope=0.005
Boundary for River Rch & Prof#=CCLC 066,Reach-1         , 3
Up Type= 0
Dn Type= 3
Dn Slope=0.005
Boundary for River Rch & Prof#=CCLC 066,Reach-1         , 4
Up Type= 0
Dn Type= 3
Dn Slope=0.005
Boundary for River Rch & Prof#=CCLC 066,Reach-1         , 5
Up Type= 0
Dn Type= 3
Dn Slope=0.005
Boundary for River Rch & Prof#=CCLC 066,Reach-1         , 6
Up Type= 0
Dn Type= 3
Dn Slope=0.005
Boundary for River Rch & Prof#=CCLC 066,Reach-1         , 7
Up Type= 0
Dn Type= 3
Dn Slope=0.005
DSS Import GetInterval= 0
DSS Import GetPeak= 0
DSS Import FillOption= 0

--- CCLC 066.f02 (steady flow) ---

Flow Title=Orig_BLE_Flows
Program Version=4.10
Number of Profiles= 7
Profile Names=10-year,25-year,50-year,1pct_min,100-year,1pct_plu,500-year
River Rch & RM=CCLC 066,Reach-1         ,16832
     401     523     619     241     729    2201    1006
River Rch & RM=CCLC 066,Reach-1         ,13701
     594     794     956     378    1142    3449    1628
River Rch & RM=CCLC 066,Reach-1         ,13104
    1309    1823    2254     913    2756    8324    4121
River Rch & RM=CCLC 066,Reach-1         ,10436
    1528    2140    2657    1079    3258    9839    4903
River Rch & RM=CCLC 066,Reach-1         ,7492
    1721    2400    2973    1203    3633   10972    5429
Boundary for River Rch & Prof#=CCLC 066,Reach-1         , 1
Up Type= 0
Dn Type= 3
Dn Slope=0.005
Boundary for River Rch & Prof#=CCLC 066,Reach-1         , 2
Up Type= 0
Dn Type= 3
Dn Slope=0.005
Boundary for River Rch & Prof#=CCLC 066,Reach-1         , 3
Up Type= 0
Dn Type= 3
Dn Slope=0.005
Boundary for River Rch & Prof#=CCLC 066,Reach-1         , 4
Up Type= 0
Dn Type= 3
Dn Slope=0.005
Boundary for River Rch & Prof#=CCLC 066,Reach-1         , 5
Up Type= 0
Dn Type= 3
Dn Slope=0.005
Boundary for River Rch & Prof#=CCLC 066,Reach-1         , 6
Up Type= 0
Dn Type= 3
Dn Slope=0.005
Boundary for River Rch & Prof#=CCLC 066,Reach-1         , 7
Up Type= 0
Dn Type= 3
Dn Slope=0.005
DSS Import GetInterval= 0
DSS Import GetPeak= 0
DSS Import FillOption= 0

--- CCLC 066.g01 (geometry) ---

Geom Title=Existing Conditions
Program Version=4.10

River Reach=CCLC 066        ,Reach-1
Reach XY= 30
      3697870.15     10169660.03      3697899.66      10170331.9
      3697667.02     10170753.78      3697864.94     10171344.05
      3698045.49     10171517.67      3698052.44     10171877.04
      3698217.37     10171962.11      3698406.57     10172351.14
      3698330.85     10172959.46       3698514.3     10173170.59
      3698834.93     10173127.74      3699083.48     10173355.36
      3699621.69      10173452.5      3700588.23     10174646.84
      3701272.72     10175181.14      3702281.83     10175629.14
      3702626.44     10175648.24      3702945.92     10175953.45
       3703505.8     10175858.22      3704702.26     10176422.89
      3704929.13     10176824.66      3705615.75     10176818.66
      3706476.61     10177192.38       3706571.5     10177088.66
      3707157.69     10177151.71      3707544.85     10176992.86
      3707930.26      10177016.3      3707976.53     10177255.47
      3708197.17     10177308.17       3708183.1     10177497.47

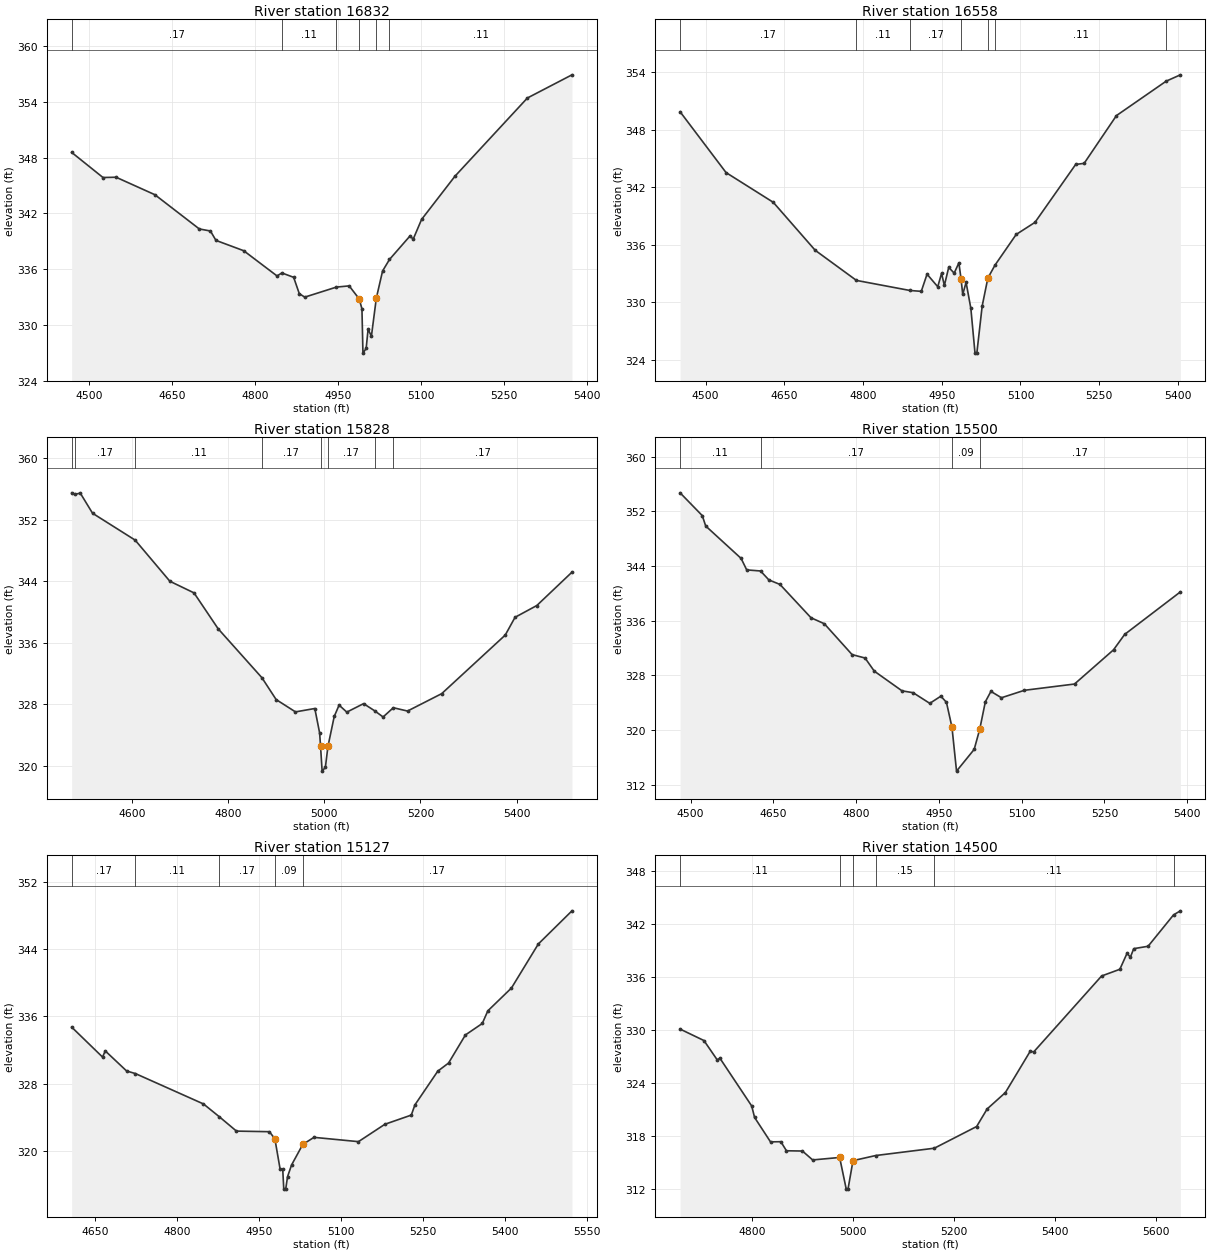
Type RM Length L Ch R = 1 ,16832   ,274,274,274
BEGIN DESCRIPTION:
CCLC 066 34.0
END DESCRIPTION:
XS GIS Cut Line= 3
      3697417.89     10169761.08      3697945.92     10169806.68
      3698317.84     10169761.07
#Sta/Elev= 30
  4467.9  348.56  4524.5  345.86  4548.2  345.89  4618.4  344.01  4698.7  340.33
  4718.8  340.11  4728.8   339.1    4779  337.99  4839.2  335.28    4848   335.6
  4869.3  335.13  4879.5  333.37  4889.4     333  4946.7  334.08  4969.7  334.21
  4987.8  332.81  4992.8  331.74  4994.6  326.98  5000.4  327.48  5003.9  329.55
  5009.9   328.8 5018.83332.9025  5030.1  335.81  5042.6  337.05  5080.2  339.61
  5085.3  339.21  5100.6  341.35    5161     346    5292  354.41  5372.6   356.9
#Mann= 6 ,-1 , 0
  4467.9     .17       0    4848     .11       0  4946.7     .17       0
  4987.8     .09       0 5018.83     .17       0  5042.6     .11       0
Bank Sta=4987.8,5018.83
XS Rating Curve= 0 ,0
Exp/Cntr=0.3,0.1

Type RM Length L Ch R = 1 ,16558   ,730,730,730
BEGIN DESCRIPTION:
CCLC 066 33.0
END DESCRIPTION:
XS GIS Cut Line= 3
      3697367.85     10169911.07      3697883.42      10170067.1
      3698267.89     10169911.05
#Sta/Elev= 30
  4451.3  349.88  4538.9  343.54  4628.9  340.44  4708.8  335.44  4787.4   332.3
  4889.4  331.25    4911  331.16    4922  332.95  4942.4  331.64  4949.7  333.04
    4955  331.77  4963.3  333.66  4973.7  333.06  4982.7  334.13 4986.77332.4707
    4990  330.84  4996.4   332.1  5005.5  329.38  5013.4  324.72  5016.9  324.72
  5027.1  329.64  5037.9  332.54  5051.6   333.9  5091.9  337.09  5127.7  338.35
  5205.3  344.39  5221.4   344.5    5283  349.48  5377.8  353.07  5404.9  353.73
#Mann= 7 ,-1 , 0
  4451.3     .17       0  4787.4     .11       0  4889.4     .17       0
 4986.77     .09       0  5037.9     .17       0  5051.6     .11       0
  5377.8     .17       0
Bank Sta=4986.77,5037.9
XS Rating Curve= 0 ,0
Exp/Cntr=0.3,0.1

Type RM Length L Ch R = 1 ,15828   ,328,328,328
BEGIN DESCRIPTION:
CCLC 066 32.0
END DESCRIPTION:
XS GIS Cut Line= 3
      3697164.63     10170624.39      3697686.72     10170674.66
       3698194.4       10170583.
#Sta/Elev= 30
  4474.7  355.48  4482.3   355.3  4492.6  355.44  4518.1  352.83  4606.7  349.34
  4678.9     344  4729.1  342.49  4779.3  337.83  4870.4  331.47  4899.9  328.64
  4940.1  327.04  4980.3  327.48  4990.3  324.31 4992.24322.5791  4995.5  319.35
  5002.3  319.85  5007.6322.5518  5020.7  326.45  5030.8  327.92  5046.8  327.01
  5081.7  328.11  5104.6  327.19  5122.3  326.38  5143.6  327.58  5173.1  327.15
  5244.2  329.41  5376.3  337.01  5396.7  339.32    5442  340.85  5515.1  345.18
#Mann= 8 ,-1 , 0
  4474.7     .11       0  4482.3     .17       0  4606.7     .11       0
  4870.4     .17       0 4992.24     .09       0  5007.6     .17       0
  5104.6     .11       0  5143.6     .17       0
Bank Sta=4992.24,5007.6
XS Rating Curve= 0 ,0
Exp/Cntr=0.3,0.1

Type RM Length L Ch R = 1 ,15500   ,373,373,373
BEGIN DESCRIPTION:
CCLC 066 31.0
END DESCRIPTION:
XS GIS Cut Line= 3
      3697267.86     10170911.07        3697784.     10170965.54
      3698167.85     10170911.07
#Sta/Elev= 30
    4481  354.73  4521.2  351.39  4527.4  349.87  4591.6  345.12  4601.7  343.44
  4626.8  343.28  4641.9  341.97    4662  341.31  4718.2  336.43  4742.4  335.55
  4792.7  331.03  4816.2  330.53  4832.9  328.61  4883.2  325.72  4903.3  325.45
  4933.5  323.89  4953.6  324.94  4963.7  324.04  4973.7   320.4    4982  313.96
    5014  317.15  5024.1  320.12  5034.2  324.12  5044.3  325.64  5063.4  324.71
  5104.9   325.8  5195.8  326.72  5266.5  331.73  5286.7  333.99  5387.7  340.22
#Mann= 4 ,-1 , 0
    4481     .11       0  4626.8     .17       0  4973.7     .09       0
  5024.1     .17       0
Bank Sta=4973.7,5024.1
XS Rating Curve= 0 ,0
Exp/Cntr=0.3,0.1

Type RM Length L Ch R = 1 ,15127   ,627,627,627
BEGIN DESCRIPTION:
CCLC 066 30.0
END DESCRIPTION:
XS GIS Cut Line= 3
      3697467.82     10171361.07      3697852.17     10171327.52
      3698367.87     10171211.07
#Sta/Elev= 30
  4607.9  334.74  4664.3  331.19  4669.3  331.92  4708.3  329.54  4724.5  329.23
  4848.8  325.63  4877.8  324.11  4909.1  322.41  4969.3  322.34  4979.3   321.5
    4989  317.86  4993.7  317.86  4995.6  315.53  4999.1  315.53  5002.5  317.01
  5009.8  318.39  5030.3  320.83  5050.8  321.67  5132.1  321.16  5180.4  323.22
  5228.7  324.31  5235.3  325.52  5277.1  329.52  5296.8  330.48  5327.6  333.81
  5358.4  335.17  5368.6  336.67  5411.8  339.38  5460.9   344.6  5522.4  348.53
#Mann= 5 ,-1 , 0
  4607.9     .17       0  4724.5     .11       0  4877.8     .17       0
  4979.3     .09       0  5030.3     .17       0
Bank Sta=4979.3,5030.3
XS Rating Curve= 0 ,0
Exp/Cntr=0.3,0.1

Type RM Length L Ch R = 1 ,14500   ,438,438,438
BEGIN DESCRIPTION:
CCLC 066 29.0
END DESCRIPTION:
XS GIS Cut Line= 3
      3697717.85     10171961.07      3698043.06     10171852.02
      3698467.84     10171361.09
#Sta/Elev= 30
    4657  330.13  4704.3  328.83  4730.6  326.64  4735.9  326.83    4799  321.41
  4804.7  320.11  4836.3  317.34  4856.8  317.36  4867.9  316.33  4899.6   316.3
  4919.9  315.29  4973.4  315.57  4986.5  311.98    4990  311.98  4999.9  315.21
  5044.9  315.79  5161.2  316.62  5245.1  319.08  5265.9  321.07  5302.1  322.93
  5351.4  327.62  5358.3  327.54  5492.9  336.15  5529.1  336.91  5543.3  338.71
    5550  338.29  5556.7  339.25  5585.1  339.52  5635.6  343.08  5649.2  343.54
#Mann= 6 ,-1 , 0
    4657     .11       0  4973.4     .06       0  4999.9     .11       0
  5044.9     .15       0  5161.2     .11       0  5635.6     .17       0
Bank Sta=4973.4,4999.9
XS Rating Curve= 0 ,0
Exp/Cntr=0.3,0.1

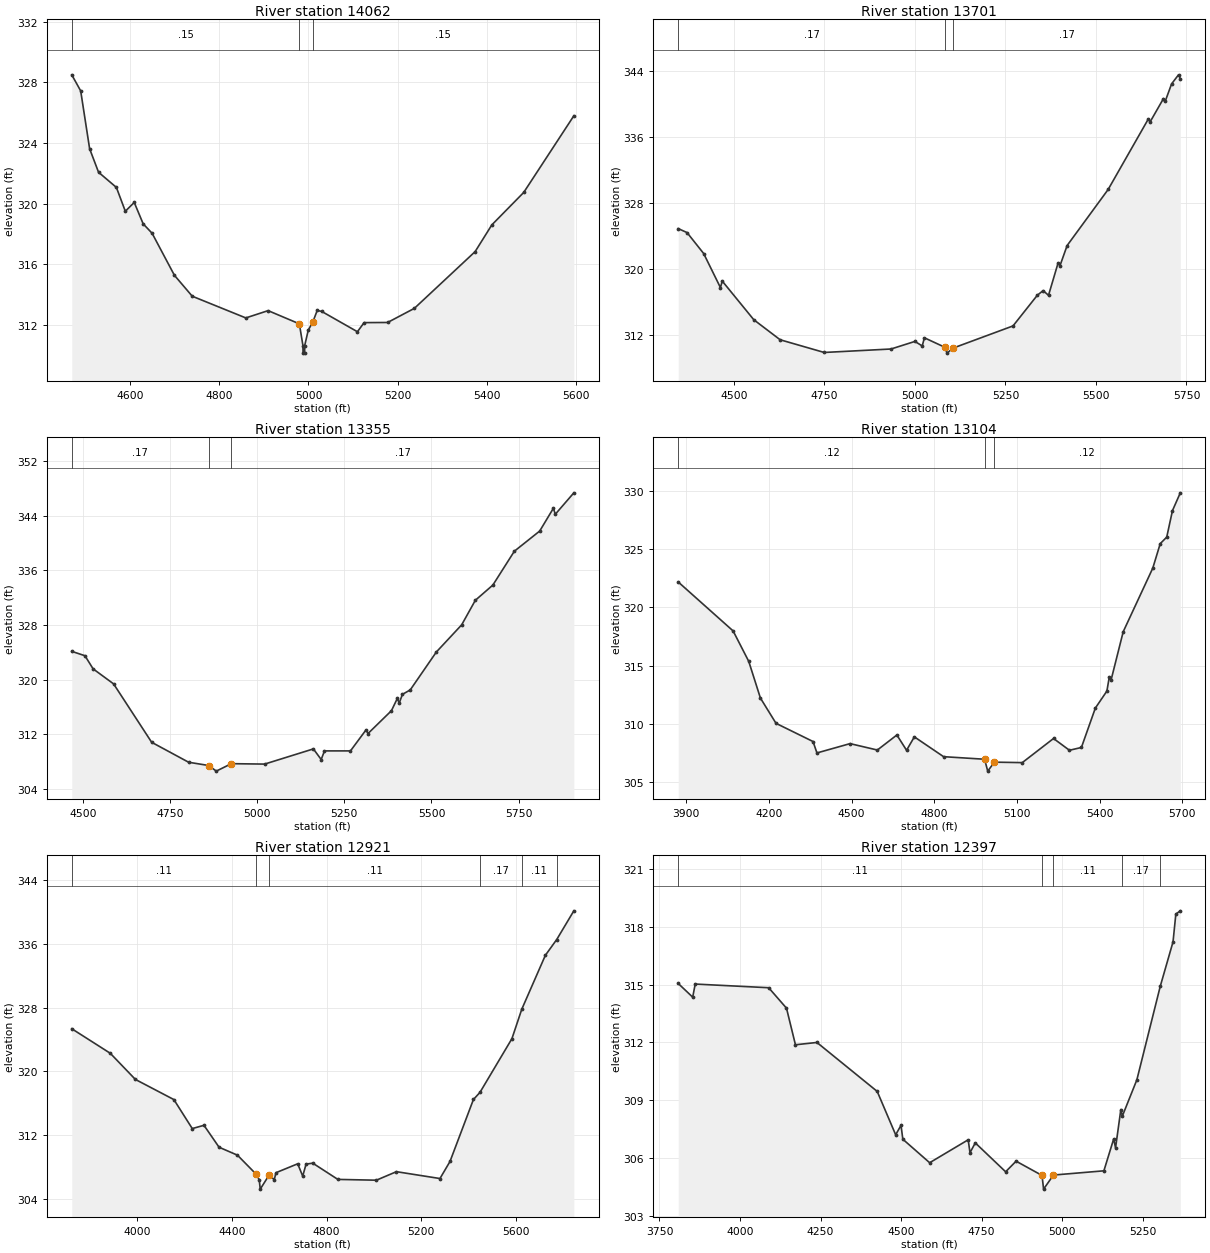
Type RM Length L Ch R = 1 ,14062   ,361,361,361
BEGIN DESCRIPTION:
CCLC 066 28.0
END DESCRIPTION:
XS GIS Cut Line= 3
      3697717.87     10172161.07        3698373.     10172171.27
      3698467.86     10171711.05
#Sta/Elev= 30
  4469.6  328.49  4489.6  327.43  4509.6  323.62  4529.6  322.07  4569.6  321.07
  4589.6   319.5  4609.6  320.08  4629.6  318.67  4649.6  318.05  4699.6  315.28
  4739.6   313.9  4859.6  312.47  4909.6  312.95  4979.6  312.08  4987.6  310.65
  4987.9  310.15  4991.4  310.15  4991.6  310.65  4999.6  311.67  5009.6  312.19
  5019.6  312.96  5029.6   312.9  5109.7  311.56  5124.7  312.16  5177.4  312.17
  5237.3   313.1  5373.5  316.84  5410.9   318.6  5482.4  320.74  5594.7  325.79
#Mann= 3 , 0 , 0
  4469.6     .15       0  4979.6     .09       0  5009.6     .15       0
Bank Sta=4979.6,5009.6
XS Rating Curve= 0 ,0
Exp/Cntr=0.3,0.1

Type RM Length L Ch R = 1 ,13701   ,346,346,346
BEGIN DESCRIPTION:
Mapping XS eaeb0e37
END DESCRIPTION:
XS GIS Cut Line= 3
      3697748.03     10172353.56      3698477.17     10172431.68
      3699111.27     10172275.76
#Sta/Elev= 30
  4346.7  324.87    4371  324.39  4416.9  321.85  4463.2  317.72  4468.2  318.51
  4555.3  313.82  4628.1  311.39  4749.8  309.85  4934.2  310.27  5000.2  311.19
  5020.4  310.64  5026.4  311.63  5082.9  310.48    5089  309.77    5105  310.37
  5271.1  313.07  5338.2  316.79  5354.2  317.35  5369.1  316.78  5395.7  320.73
  5400.9  320.39  5420.5  322.82  5533.8  329.62  5644.9  338.18  5650.1  337.85
  5686.5  340.64  5691.6  340.34  5708.9  342.42    5728  343.52    5733  343.06
#Mann= 3 , 0 , 0
  4346.7     .17       0  5082.9     .09       0    5105     .17       0
Bank Sta=5082.9,5105
XS Rating Curve= 0 ,0
Exp/Cntr=0.3,0.1

Type RM Length L Ch R = 1 ,13355   ,251,251,251
BEGIN DESCRIPTION:
CCLC 066 27.0
END DESCRIPTION:
XS GIS Cut Line= 3
      3697867.89     10172561.09      3698346.96     10172770.22
      3699167.82     10172361.09
#Sta/Elev= 30
  4468.4  324.16  4506.2  323.52  4529.6   321.6  4588.4   319.4  4697.5  310.86
  4803.5  307.94  4861.2  307.46  4882.9  306.64    4926  307.73  5021.5  307.67
  5161.3  309.89  5183.7  308.34  5193.2   309.6  5267.7   309.6  5312.4  312.68
    5318  312.14  5385.2  315.48    5402  317.27  5407.5  316.59  5416.7  317.87
  5439.1  318.52  5513.9  324.06  5586.6  328.04  5625.8  331.63  5676.1  333.86
  5737.7  338.81  5810.4  341.76  5849.6  345.09  5855.2  344.22  5908.3  347.35
#Mann= 3 , 0 , 0
  4468.4     .17       0  4861.2     .09       0    4926     .17       0
Bank Sta=4861.2,4926
XS Rating Curve= 0 ,0
Exp/Cntr=0.3,0.1

Type RM Length L Ch R = 1 ,13104   ,183,183,183
BEGIN DESCRIPTION:
CCLC 066 23.0
END DESCRIPTION:
XS GIS Cut Line= 3
      3697578.46     10173833.38      3698360.58     10173000.05
      3698917.88     10172611.05
#Sta/Elev= 30
  3870.8  322.18    4070  317.98  4126.7  315.37  4169.1  312.22  4225.8  310.05
  4360.1  308.49  4374.3  307.51  4494.5  308.31  4593.6  307.76  4664.4  309.05
  4699.6  307.74  4727.9  308.89    4834  307.19  4982.9  306.97  4994.2  305.95
  5018.5  306.72  5119.7  306.68  5233.1  308.75  5290.8  307.74  5334.3  307.98
  5384.9  311.36  5426.8  312.82  5435.5  314.03  5441.6  313.73    5486  317.91
  5593.4  323.37  5620.4  325.47    5644  326.03  5664.9  328.31  5693.3  329.83
#Mann= 3 , 0 , 0
  3870.8     .12       0  4982.9     .08       0  5018.5     .12       0
Bank Sta=4982.9,5018.5
XS Rating Curve= 0 ,0
Exp/Cntr=0.3,0.1

Type RM Length L Ch R = 1 ,12921   ,524,524,524
BEGIN DESCRIPTION:
CCLC 066 22.0
END DESCRIPTION:
XS GIS Cut Line= 3
      3697567.83     10174011.09      3698470.96      10173108.7
      3699067.89     10172511.04
#Sta/Elev= 30
  3723.3  325.35    3886  322.27    3992  318.99  4154.7  316.46  4232.4  312.82
  4281.9  313.23  4345.6  310.48  4423.4  309.48  4501.1  307.13  4515.3  306.41
  4519.6  305.22  4557.7  307.01  4578.9   306.4    4586  307.28  4677.9   308.4
  4699.1  306.85  4713.3  308.36  4741.6  308.48  4847.6  306.44  5010.3  306.34
  5095.1  307.41    5279  306.55  5321.4  308.69  5420.4  316.47    5448  317.36
    5583   324.1  5624.7   327.8  5724.4  334.57  5772.4  336.55  5844.7  340.15
#Mann= 6 ,-1 , 0
  3723.3     .11       0  4501.1     .06       0  4557.7     .11       0
    5448     .17       0  5624.7     .11       0  5772.4     .17       0
Bank Sta=4501.1,4557.7
XS Rating Curve= 0 ,0
Exp/Cntr=0.3,0.1

Type RM Length L Ch R = 1 ,12397   ,476,476,476
BEGIN DESCRIPTION:
CCLC 066 21.0
END DESCRIPTION:
XS GIS Cut Line= 3
      3697917.86     10173811.07      3698703.46     10173409.77
      3699017.86     10172811.06
#Sta/Elev= 30
  3808.4  315.06  3853.3  314.35  3861.1  315.03  4089.1  314.84  4144.4  313.78
  4172.2  311.88  4238.9     312    4426  309.46  4483.3  307.21  4499.9   307.7
  4505.5  306.98  4588.8  305.76  4708.4  306.95    4714  306.28  4730.4  306.79
  4824.6  305.29  4857.1  305.84  4937.6   305.1  4942.4  304.39    4973  305.12
  5129.6  305.34  5160.1     307  5165.8  306.53  5182.2  308.52  5186.9  308.18
  5231.9  310.06  5304.5  314.91  5344.2  317.22  5352.9  318.66  5366.8  318.83
#Mann= 5 ,-1 , 0
  3808.4     .11       0  4937.6     .06       0    4973     .11       0
  5186.9     .17       0  5304.5     .11       0
Bank Sta=4937.6,4973
XS Rating Curve= 0 ,0
Exp/Cntr=0.3,0.1

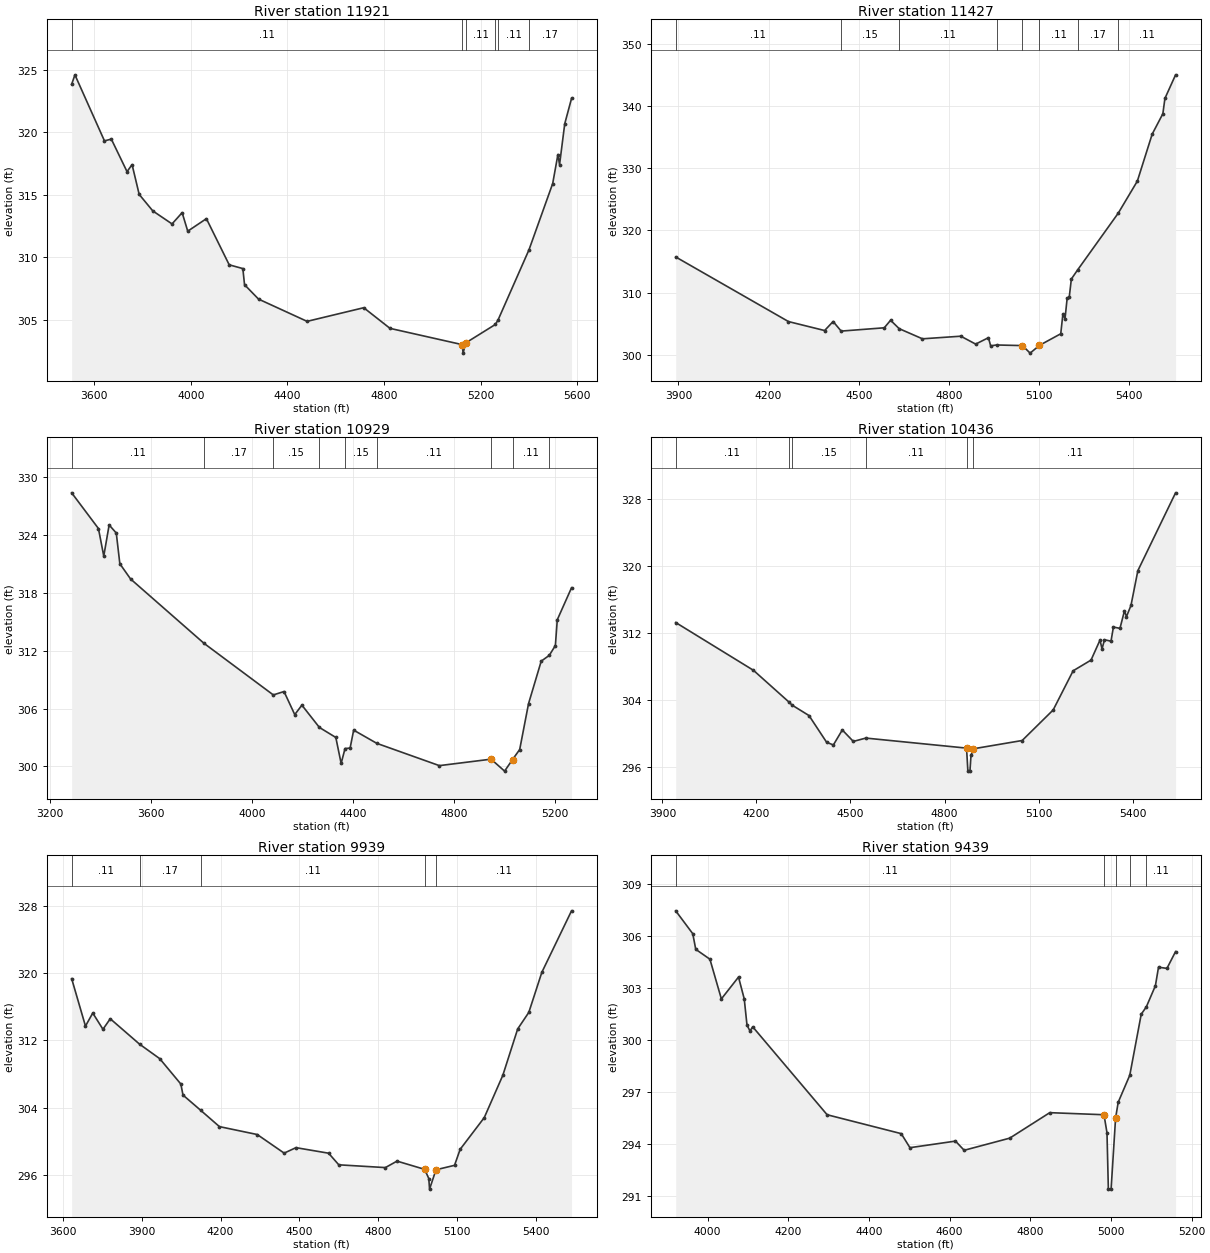
Type RM Length L Ch R = 1 ,11921   ,494,494,494
BEGIN DESCRIPTION:
CCLC 066 20.0
END DESCRIPTION:
XS GIS Cut Line= 3
      3698267.86     10174561.07      3699143.18     10173351.09
      3699567.86     10172961.07
#Sta/Elev= 30
  3506.6  323.82  3520.1  324.58  3642.4   319.3  3670.9  319.44  3735.9  316.84
  3756.8   317.4  3786.2  315.02  3842.6   313.7  3922.3  312.66  3964.1  313.56
  3987.3  312.08  4064.6  313.08    4159  309.39  4215.5  309.09  4222.5   307.8
  4280.4  306.65  4481.5  304.87  4716.1  305.96  4824.9  304.31  5123.7  303.01
  5127.7  302.33  5137.9  303.14    5261  304.62  5272.1  304.97  5400.4  310.59
  5498.6  315.89  5520.2  318.21    5527   317.4  5548.5  320.67  5576.6  322.69
#Mann= 6 ,-1 , 0
  3506.6     .11       0  5123.7     .06       0  5137.9     .11       0
    5261     .17       0  5272.1     .11       0  5400.4     .17       0
Bank Sta=5123.7,5137.9
XS Rating Curve= 0 ,0
Exp/Cntr=0.3,0.1

Type RM Length L Ch R = 1 ,11427   ,498,498,498
BEGIN DESCRIPTION:
CCLC 066 19.0
END DESCRIPTION:
XS GIS Cut Line= 3
      3698817.86     10174261.06       3699570.5     10173446.69
      3699967.85     10173061.08
#Sta/Elev= 30
  3891.1  315.72  4266.2  305.34  4386.4   303.9  4414.7  305.35  4441.4  303.81
  4584.8  304.34  4605.8  305.55  4634.4   304.2  4711.8  302.57  4839.4  302.99
  4888.8  301.72  4931.3  302.75  4938.6  301.44  4958.2  301.58  5044.5  301.48
  5069.9  300.27  5101.1  301.52  5171.8  303.38  5178.8   306.5    5186   305.8
    5193  309.05  5200.1  309.28  5207.1  312.18  5227.5  313.61  5363.2  322.77
  5426.5   327.9  5475.9  335.45  5511.4  338.73  5518.3  341.19  5553.7  344.98
#Mann= 8 ,-1 , 0
  3891.1     .11       0  4441.4     .15       0  4634.4     .11       0
  4958.2     .15       0  5044.5     .09       0  5101.1     .11       0
  5227.5     .17       0  5363.2     .11       0
Bank Sta=5044.5,5101.1
XS Rating Curve= 0 ,0
Exp/Cntr=0.3,0.1

Type RM Length L Ch R = 1 ,10929   ,493,493,493
BEGIN DESCRIPTION:
CCLC 066 18.0
END DESCRIPTION:
XS GIS Cut Line= 3
      3698717.86     10174961.07      3699918.98     10173736.78
      3700117.87     10173561.06
#Sta/Elev= 30
  3284.9  328.37    3391  324.67  3412.1  321.81  3433.4  325.04  3461.7   324.2
  3475.8  321.02  3518.3  319.44  3809.2  312.77  4083.8  307.42  4126.3  307.77
  4168.8  305.38  4197.1  306.36  4266.4  304.05  4331.5  303.01  4352.6  300.32
    4368  301.86  4388.1  301.91  4402.2  303.77  4493.9   302.4  4741.7  300.09
  4946.7  300.76  5000.2  299.52  5031.6  300.72    5060  301.76  5095.1  306.52
  5145.3  310.92  5177.2  311.52  5201.4  312.54  5208.9  315.21  5265.4  318.53
#Mann= 9 ,-1 , 0
  3284.9     .11       0  3809.2     .17       0  4083.8     .15       0
  4266.4     .11       0    4368     .15       0  4493.9     .11       0
  4946.7     .06       0  5031.6     .11       0  5177.2     .17       0
Bank Sta=4946.7,5031.6
XS Rating Curve= 0 ,0
Exp/Cntr=0.3,0.1

Type RM Length L Ch R = 1 ,10436   ,497,497,497
BEGIN DESCRIPTION:
CCLC 066 17.0
END DESCRIPTION:
XS GIS Cut Line= 3
      3699417.82      10174811.1      3700208.48     10174108.69
      3700617.89     10173761.04
#Sta/Elev= 30
  3942.4  313.27  4190.4  307.56  4302.4  303.81  4313.7   303.4  4367.7  302.15
    4424  298.95  4445.4  298.64  4473.9  300.43    4509  299.06    4549  299.46
  4870.3  298.26  4874.5  295.51  4881.1  295.51  4884.5   297.4    4892  298.18
  5047.7  299.17  5146.6  302.82  5210.3   307.5  5267.4  308.78    5296  311.17
  5302.5  310.12  5310.3  311.21  5331.1  311.04  5338.8  312.73  5359.7  312.57
  5373.9  314.65  5380.5  313.98  5394.8  315.31  5416.8  319.47  5537.1  328.77
#Mann= 6 ,-1 , 0
  3942.4     .11       0  4302.4     .17       0  4313.7     .15       0
    4549     .11       0  4870.3     .06       0    4892     .11       0
Bank Sta=4870.3,4892
XS Rating Curve= 0 ,0
Exp/Cntr=0.3,0.1

Type RM Length L Ch R = 1 ,9939    ,500,500,500
BEGIN DESCRIPTION:
CCLC 066 16.0
END DESCRIPTION:
XS GIS Cut Line= 3
      3699267.88     10175111.06      3700484.07     10174486.24
      3700867.86     10174111.07
#Sta/Elev= 30
  3632.7  319.32  3685.3  313.68  3713.1  315.23  3751.9   313.3  3779.7  314.55
  3891.4  311.53  3968.1  309.81  4048.6  306.79  4056.8  305.48  4124.5  303.66
  4195.6  301.73  4339.6  300.79  4442.1  298.58  4487.1  299.23  4611.4  298.57
  4650.2  297.19  4827.6  296.86    4872  297.63  4977.3  296.65    4993  295.56
  4995.9   294.3  5020.4   296.6  5091.1  297.13  5112.4  299.03  5204.3   302.8
    5275  307.83  5331.6  313.34    5374  315.31  5423.6  320.07  5536.7  327.38
#Mann= 5 ,-1 , 0
  3632.7     .11       0  3891.4     .17       0  4124.5     .11       0
  4977.3     .06       0  5020.4     .11       0
Bank Sta=4977.3,5020.4
XS Rating Curve= 0 ,0
Exp/Cntr=0.3,0.1

Type RM Length L Ch R = 1 ,9439    ,455,455,455
BEGIN DESCRIPTION:
CCLC 066 15.0
END DESCRIPTION:
XS GIS Cut Line= 3
      3700017.84     10175511.08      3700813.89      10174782.7
      3700917.85     10174661.07
#Sta/Elev= 30
    3921  307.44  3963.3  306.12  3970.7  305.22  4005.8  304.65  4034.2  302.36
  4076.7  303.62  4090.9  302.36  4097.7  300.85  4105.1  300.51  4111.9  300.75
  4296.3  295.68    4480  294.59  4501.6  293.78  4614.5  294.16    4636  293.63
  4748.9  294.33  4848.2   295.8  4982.6  295.68    4990  294.64  4993.4  291.39
  5000.2  291.39  5011.3  295.49  5017.8   296.4  5046.5  297.96  5074.9  301.48
  5087.5   301.9    5110  303.12  5117.7  304.19  5138.6  304.12    5160  305.09
#Mann= 5 ,-1 , 0
    3921     .11       0  4982.6     .06       0  5011.3     .11       0
  5046.5     .15       0  5087.5     .11       0
Bank Sta=4982.6,5011.3
XS Rating Curve= 0 ,0
Exp/Cntr=0.3,0.1

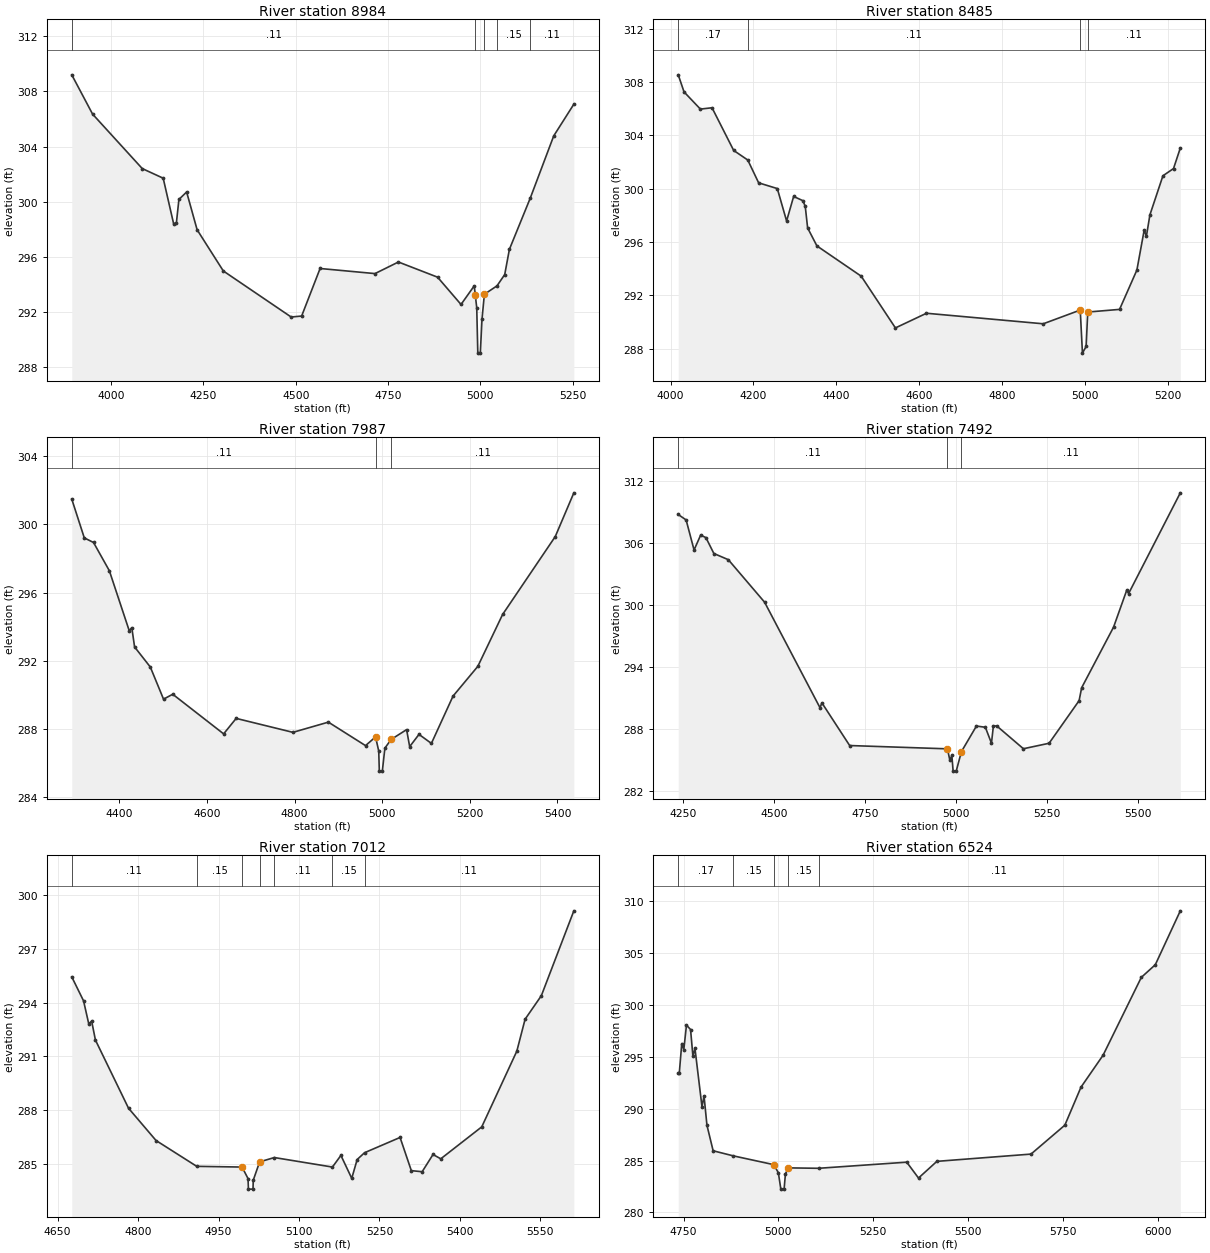
Type RM Length L Ch R = 1 ,8984    ,499,499,499
BEGIN DESCRIPTION:
CCLC 066 14.0
END DESCRIPTION:
XS GIS Cut Line= 3
      3700417.85     10175861.07      3701161.35     10175041.05
      3701267.84     10174811.11
#Sta/Elev= 30
  3893.1   309.2  3949.5  306.35    4084   302.4  4140.8   301.7  4169.2  298.38
  4176.6  298.47  4183.4  300.16  4204.3   300.7  4232.7  297.96  4303.7  294.97
  4487.5  291.63  4515.9   291.7  4565.9  295.15  4714.6  294.78  4778.1  295.62
  4884.2  294.52  4947.7  292.54  4983.5  293.89 4986.37293.2189  4990.3   292.3
  4993.2  289.01    5000  289.01  5004.5  291.45    5011  293.28  5045.2  293.89
  5066.1  294.71  5078.8  296.54  5135.1  300.24  5198.9  304.77  5253.4  307.07
#Mann= 5 ,-1 , 0
  3893.1     .11       0 4986.37     .06       0    5011     .11       0
  5045.2     .15       0  5135.1     .11       0
Bank Sta=4986.37,5011
XS Rating Curve= 0 ,0
Exp/Cntr=0.3,0.1

Type RM Length L Ch R = 1 ,8485    ,498,498,498
BEGIN DESCRIPTION:
CCLC 066 13.0
END DESCRIPTION:
XS GIS Cut Line= 3
      3701117.85     10176161.08      3701550.53     10175280.22
      3701617.87     10175061.03
#Sta/Elev= 30
  4018.6  308.53  4032.6  307.25    4072  305.96  4100.1  306.06  4152.3  302.86
  4186.3  302.14  4212.5  300.43  4257.5     300  4279.9  297.57  4296.9  299.41
  4319.3  299.09  4324.9  298.66  4330.6  297.05    4353   295.7  4459.8  293.43
  4542.3  289.55  4617.2  290.65  4898.8  289.86    4988  290.89  4993.3  287.66
  5002.2  288.16  5006.1  290.74  5082.8  290.94  5124.6  293.89  5142.2  296.89
  5147.5  296.42    5156  298.03  5187.4  300.96  5212.9   301.5  5229.3  303.04
#Mann= 4 ,-1 , 0
  4018.6     .17       0  4186.3     .11       0    4988     .06       0
  5006.1     .11       0
Bank Sta=4988,5006.1
XS Rating Curve= 0 ,0
Exp/Cntr=0.3,0.1

Type RM Length L Ch R = 1 ,7987    ,495,495,495
BEGIN DESCRIPTION:
CCLC 066 12.0
END DESCRIPTION:
XS GIS Cut Line= 3
      3701617.87     10176061.04      3702006.44     10175468.24
      3702317.84     10175161.08
#Sta/Elev= 30
  4291.2  301.49  4319.8  299.21  4340.9  298.94    4377  297.28  4422.3  293.76
  4428.3  293.93  4434.6   292.8  4470.5  291.62  4500.7  289.73  4521.7  290.02
  4637.9  287.69  4666.5   288.6  4796.1  287.78    4877  288.38  4961.8     287
  4984.7  287.51    4992  286.68  4993.3   285.5  5000.2   285.5    5006  286.85
  5020.2  287.36  5055.6  287.94  5062.6  286.94  5083.9  287.66  5112.2  287.13
  5161.6  289.91  5218.2  291.66  5274.8  294.71    5395  299.29  5437.4  301.86
#Mann= 3 , 0 , 0
  4291.2     .11       0  4984.7     .06       0  5020.2     .11       0
Bank Sta=4984.7,5020.2
XS Rating Curve= 0 ,0
Exp/Cntr=0.3,0.1

Type RM Length L Ch R = 1 ,7492    ,480,480,480
BEGIN DESCRIPTION:
CCLC 066 11.0
END DESCRIPTION:
XS GIS Cut Line= 3
      3702117.87     10176361.03      3702418.98     10175659.53
      3702567.85     10175061.07
#Sta/Elev= 30
  4236.6  308.78  4258.3  308.25  4280.1  305.34  4298.2  306.78  4312.7  306.54
  4334.5     305  4374.3   304.4    4474  300.28  4626.2  290.06  4631.6  290.52
  4707.8  286.39  4976.6  286.07  4983.2  284.97  4988.7  285.43  4992.2  283.91
  5000.7  283.91    5015   285.8  5056.3  288.28  5080.8  288.16  5097.6  286.62
  5102.8  288.26  5111.8   288.3  5185.4  286.08    5256  286.61  5338.5  290.74
  5345.5  291.99  5433.3  297.87  5469.5  301.45  5474.6  301.12  5616.7  310.88
#Mann= 3 ,-1 , 0
  4236.6     .11       0  4976.6     .07       0    5015     .11       0
Bank Sta=4976.6,5015
XS Rating Curve= 0 ,0
Exp/Cntr=0.3,0.1

Type RM Length L Ch R = 1 ,7012    ,488,488,488
BEGIN DESCRIPTION:
CCLC 066 10.0
END DESCRIPTION:
XS GIS Cut Line= 3
      3702617.86     10176111.06      3702754.05     10175817.51
      3702667.86     10175211.11
#Sta/Elev= 30
  4676.4  295.43  4698.4  294.09    4708  292.82  4713.5  292.96  4720.5  291.91
  4782.2  288.11  4833.5  286.31  4909.4  284.87  4993.9  284.83    5005  284.19
  5005.8   283.6  5014.3   283.6  5014.8   284.1  5026.7  285.12  5054.1  285.36
  5162.4  284.83  5178.2  285.48  5198.4   284.2  5208.5  285.25  5222.3  285.63
  5288.5  286.48  5309.5  284.63  5329.7  284.57  5349.9  285.53  5364.4  285.29
  5440.8  287.07  5506.2  291.29  5521.6  293.07  5551.9  294.38  5612.5  299.11
#Mann= 7 ,-1 , 0
  4676.4     .11       0  4909.4     .15       0  4993.9     .09       0
  5026.7     .15       0  5054.1     .11       0  5162.4     .15       0
  5222.3     .11       0
Bank Sta=4993.9,5026.7
XS Rating Curve= 0 ,0
Exp/Cntr=0.3,0.1

Type RM Length L Ch R = 1 ,6524    ,485,485,485
BEGIN DESCRIPTION:
CCLC 066 9.0
END DESCRIPTION:
XS GIS Cut Line= 3
      3703267.87      10176211.1       3703167.5     10175967.04
      3702617.83     10175061.04
#Sta/Elev= 30
  4736.1   293.4  4738.8   293.4  4745.4  296.28  4750.8   295.7  4757.8  298.06
  4768.6  297.64  4774.8  295.06  4780.2  295.81  4798.7  290.19  4804.1  291.23
  4811.8   288.4  4828.1  285.94  4881.2  285.45  4988.1   284.6    5000  283.82
  5006.6  282.24  5015.2  282.24  5018.7  283.71  5026.4  284.29    5106  284.25
  5338.5  284.84  5369.5  283.31    5418  284.92  5666.1  285.62  5755.3  288.41
  5797.9  292.08  5856.1  295.16  5956.9  302.67  5993.8  303.89  6059.7  309.09
#Mann= 5 ,-1 , 0
  4736.1     .17       0  4881.2     .15       0  4988.1     .09       0
  5026.4     .15       0    5106     .11       0
Bank Sta=4988.1,5026.4
XS Rating Curve= 0 ,0
Exp/Cntr=0.3,0.1

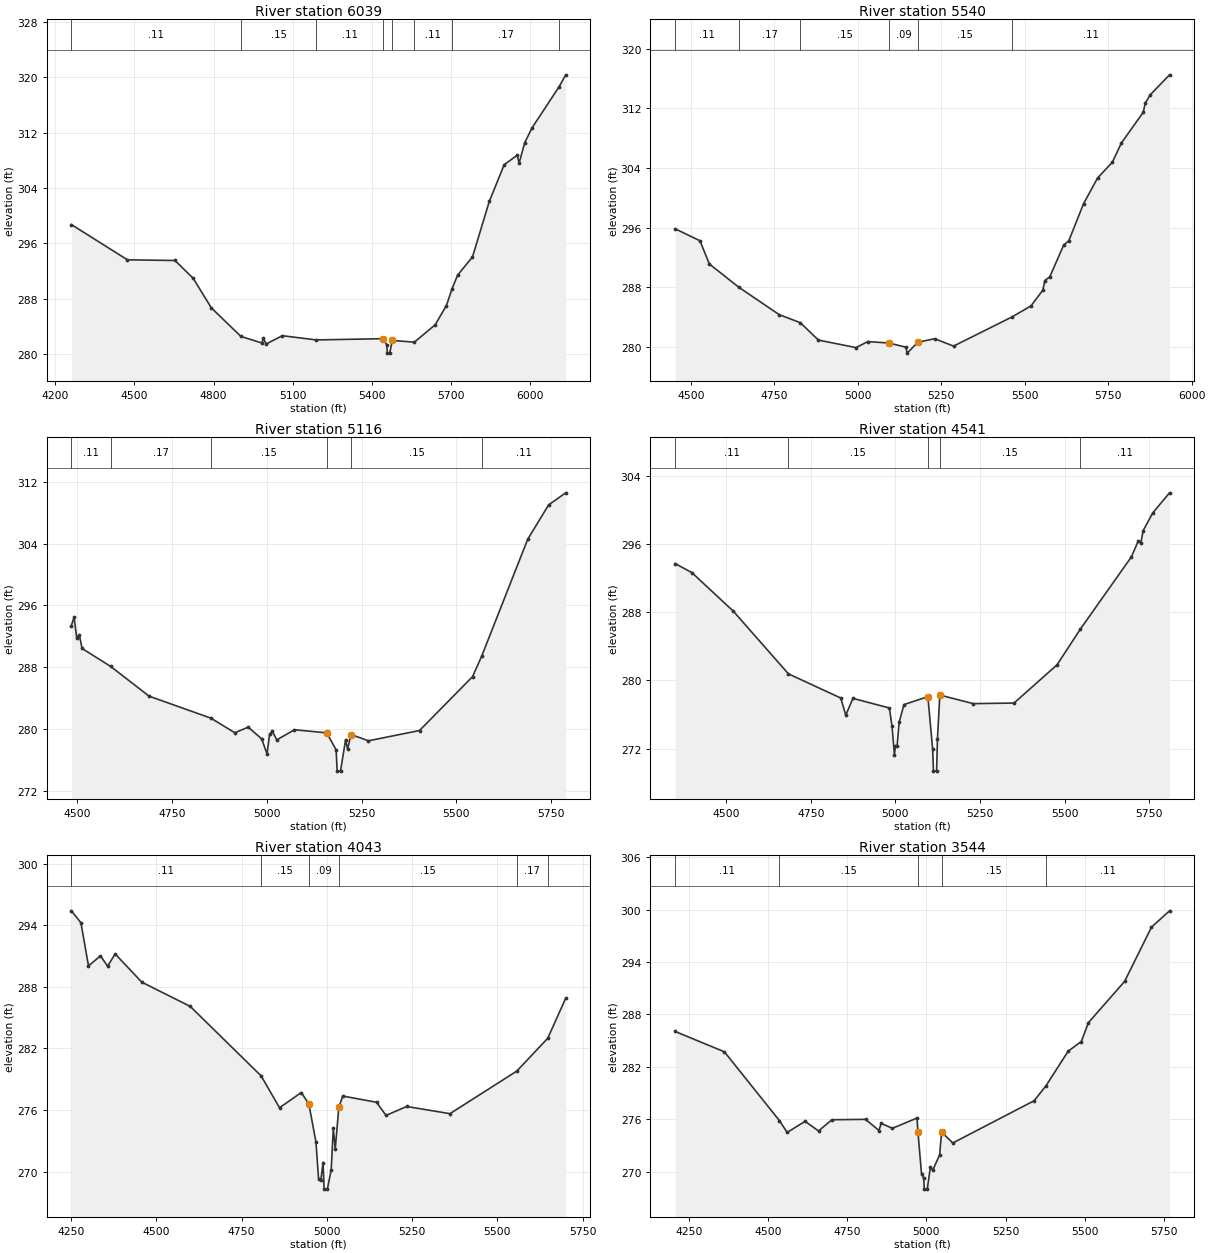
Type RM Length L Ch R = 1 ,6039    ,499,499,499
BEGIN DESCRIPTION:
CCLC 066 8.0
END DESCRIPTION:
XS GIS Cut Line= 3
      3703317.84     10176611.11      3703566.08     10175914.95
      3704367.88     10175111.05
#Sta/Elev= 30
  4260.9  298.71  4473.3  293.61  4653.8  293.51  4722.6  290.94  4791.8  286.65
  4903.7  282.53  4982.9  281.58  4989.3  282.25  4999.4  281.43  5060.6  282.63
  5189.7  282.02  5442.4   282.2  5456.5  281.32  5459.3  280.11  5467.9  280.11
  5477.8  281.94  5561.4   281.7  5640.4  284.21  5682.8  286.98  5704.6  289.44
  5725.3  291.39  5781.8  294.02  5845.5  302.05    5902  307.37  5951.5  308.74
  5958.6  307.59  5979.8  310.55  6008.1  312.73  6110.1  318.64  6135.4  320.37
#Mann= 8 ,-1 , 0
  4260.9     .11       0  4903.7     .15       0  5189.7     .11       0
  5442.4     .09       0  5477.8     .11       0  5561.4     .11       0
  5704.6     .17       0  6110.1     .11       0
Bank Sta=5442.4,5477.8
XS Rating Curve= 0 ,0
Exp/Cntr=0.3,0.1

Type RM Length L Ch R = 1 ,5540    ,424,424,424
BEGIN DESCRIPTION:
CCLC 066 7.0
END DESCRIPTION:
XS GIS Cut Line= 3
      3703867.86     10176611.03      3703981.69     10176075.49
      3704517.85     10175311.08
#Sta/Elev= 30
  4452.5  295.86  4526.9  294.25  4554.7  291.15  4643.1  288.03  4764.7  284.34
    4827  283.29  4881.8  280.95  4994.3  279.94  5029.8  280.75  5093.1  280.55
  5143.6     280  5147.6   279.2  5179.3  280.65  5229.9  281.13  5286.6  280.14
  5461.7  284.05  5518.4  285.52  5554.1  287.64  5560.2  288.93    5575  289.43
  5616.9  293.72  5631.7  294.24  5676.1  299.22    5718  302.66  5762.4  304.78
  5789.5  307.36  5854.8  311.46  5860.9  312.69  5875.7   313.8  5933.7  316.49
#Mann= 6 ,-1 , 0
  4452.5     .11       0  4643.1     .17       0    4827     .15       0
  5093.1     .09       0  5179.3     .15       0  5461.7     .11       0
Bank Sta=5093.1,5179.3
XS Rating Curve= 0 ,0
Exp/Cntr=0.3,0.1

Type RM Length L Ch R = 1 ,5116    ,575,575,575
BEGIN DESCRIPTION:
CCLC 066 6.0
END DESCRIPTION:
XS GIS Cut Line= 3
      3703967.86     10176661.06      3704349.29     10176270.88
      3704617.86     10175561.04
#Sta/Elev= 30
  4484.3  293.39  4491.4  294.46  4498.4  291.79  4505.5  292.12  4512.5  290.42
    4588  288.09  4689.4  284.24  4852.5  281.39  4915.7   279.5    4951  280.23
  4986.4  278.71  5000.6  276.77  5007.6  279.35  5014.7  279.69  5026.3  278.58
  5073.1  279.89  5158.2  279.49    5183  277.28  5185.7  274.53  5194.5  274.53
  5207.9  278.58  5213.2  277.39  5222.2  279.27  5268.2  278.46    5403  279.79
    5543  286.77  5567.3  289.45  5688.6  304.57  5743.6  309.01  5788.9  310.58
#Mann= 6 ,-1 , 0
  4484.3     .11       0    4588     .17       0  4852.5     .15       0
  5158.2     .09       0  5222.2     .15       0  5567.3     .11       0
Bank Sta=5158.2,5222.2
XS Rating Curve= 0 ,0
Exp/Cntr=0.3,0.1

Type RM Length L Ch R = 1 ,4541    ,498,498,498
BEGIN DESCRIPTION:
CCLC 066 5.0
END DESCRIPTION:
XS GIS Cut Line= 3
      3704217.81      10176911.1      3704756.04     10176544.88
      3705317.83     10175961.09
#Sta/Elev= 30
    4349  293.74  4398.5  292.67  4521.2  288.13  4683.7  280.78  4838.4  277.94
  4853.3  275.92  4874.3   277.9  4982.1  276.77  4990.1   274.6    4997  271.27
    5000  272.32  5004.9  272.32    5011  275.08  5025.2  277.17  5095.9   278.1
  5110.1  271.91  5112.4  269.35  5121.7  269.35  5124.2   273.1  5131.2  278.29
  5230.2  277.28  5350.6  277.35  5477.7  281.84  5546.1  286.01  5697.2  294.51
  5718.3  296.44  5725.5   296.2  5732.4  297.62  5760.7   299.7  5810.2  302.05
#Mann= 5 ,-1 , 0
    4349     .11       0  4683.7     .15       0  5095.9     .09       0
  5131.2     .15       0  5546.1     .11       0
Bank Sta=5095.9,5131.2
XS Rating Curve= 0 ,0
Exp/Cntr=0.3,0.1

Type RM Length L Ch R = 1 ,4043    ,499,499,499
BEGIN DESCRIPTION:
CCLC 066 4.0
END DESCRIPTION:
XS GIS Cut Line= 3
      3704567.87     10177411.05      3705043.77     10176832.41
      3705367.86     10176211.05
#Sta/Elev= 30
  4250.8   295.4  4278.8  294.24    4301  290.04  4336.1  291.01    4357  290.01
  4379.2   291.2  4457.4  288.45  4599.4  286.09  4807.1  279.33  4861.3  276.22
  4925.2   277.7  4947.4  276.58  4968.2  272.88  4975.8  269.31  4982.6   269.2
    4989  270.88  4992.2  268.29  5001.6  268.29  5012.8  270.16    5019   274.2
  5024.7  272.21  5035.3  276.27  5046.8  277.36  5145.9  276.75  5173.7  275.47
  5234.3  276.34  5361.2  275.64  5557.3  279.79  5648.1  282.99  5700.8   286.9
#Mann= 6 ,-1 , 0
  4250.8     .11       0  4807.1     .15       0  4947.4     .09       0
  5035.3     .15       0  5557.3     .17       0  5648.1     .11       0
Bank Sta=4947.4,5035.3
XS Rating Curve= 0 ,0
Exp/Cntr=0.3,0.1

Type RM Length L Ch R = 1 ,3544    ,497,497,497
BEGIN DESCRIPTION:
CCLC 066 3.0
END DESCRIPTION:
XS GIS Cut Line= 3
      3704917.88     10177361.05      3705495.46      10176816.8
      3705967.88     10176211.04
#Sta/Elev= 30
  4206.4  286.05  4361.9  283.72  4535.8  275.83  4560.2  274.48  4616.8  275.75
  4659.3  274.65  4701.4  275.93  4807.8  275.98  4850.3   274.7  4857.1  275.52
  4892.7  274.95  4970.4  276.13 4973.48274.4828  4984.6  269.76  4991.5  269.22
  4993.5  267.98  5002.9  267.98  5012.8  270.54    5020  270.14  5041.8   271.9
  5048.1  274.52  5083.4  273.27  5340.3  278.11  5377.6  279.81  5447.9  283.79
  5489.5   284.9  5512.1  287.07  5626.1  291.78  5711.2  298.01  5768.2  299.88
#Mann= 5 ,-1 , 0
  4206.4     .11       0  4535.8     .15       0 4973.48     .09       0
  5048.1     .15       0  5377.6     .11       0
Bank Sta=4973.48,5048.1
XS Rating Curve= 0 ,0
Exp/Cntr=0.3,0.1