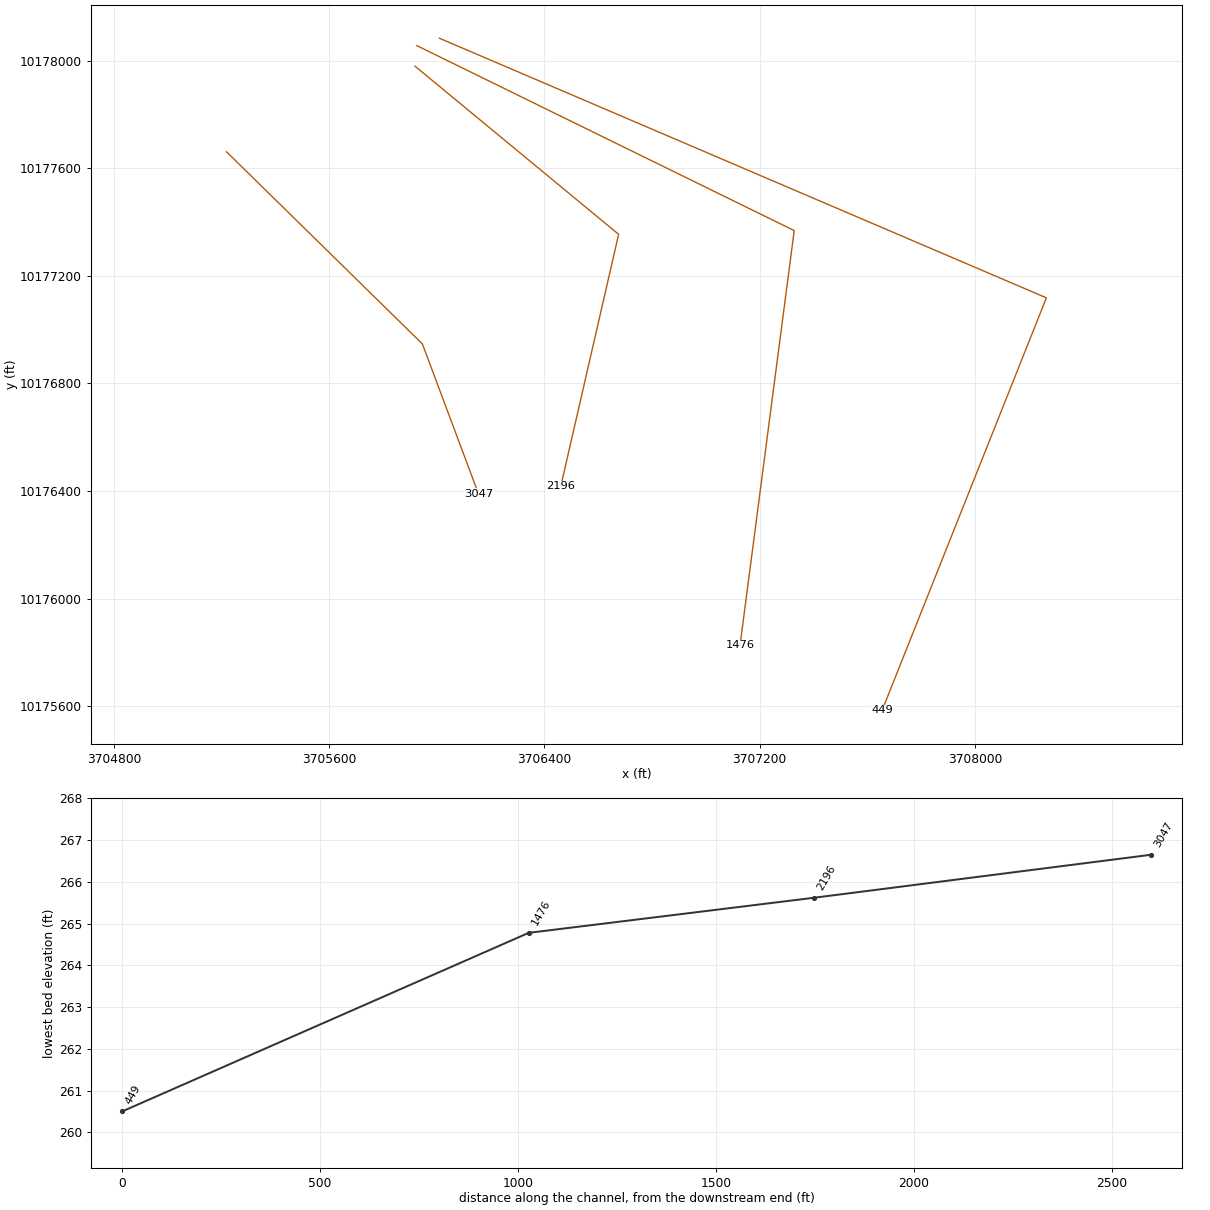
HEC-RAS study CCLC 066.prj: CCLC 066 Base Level Engineering

--- CCLC 066.g01 (geometry) --- (continued)

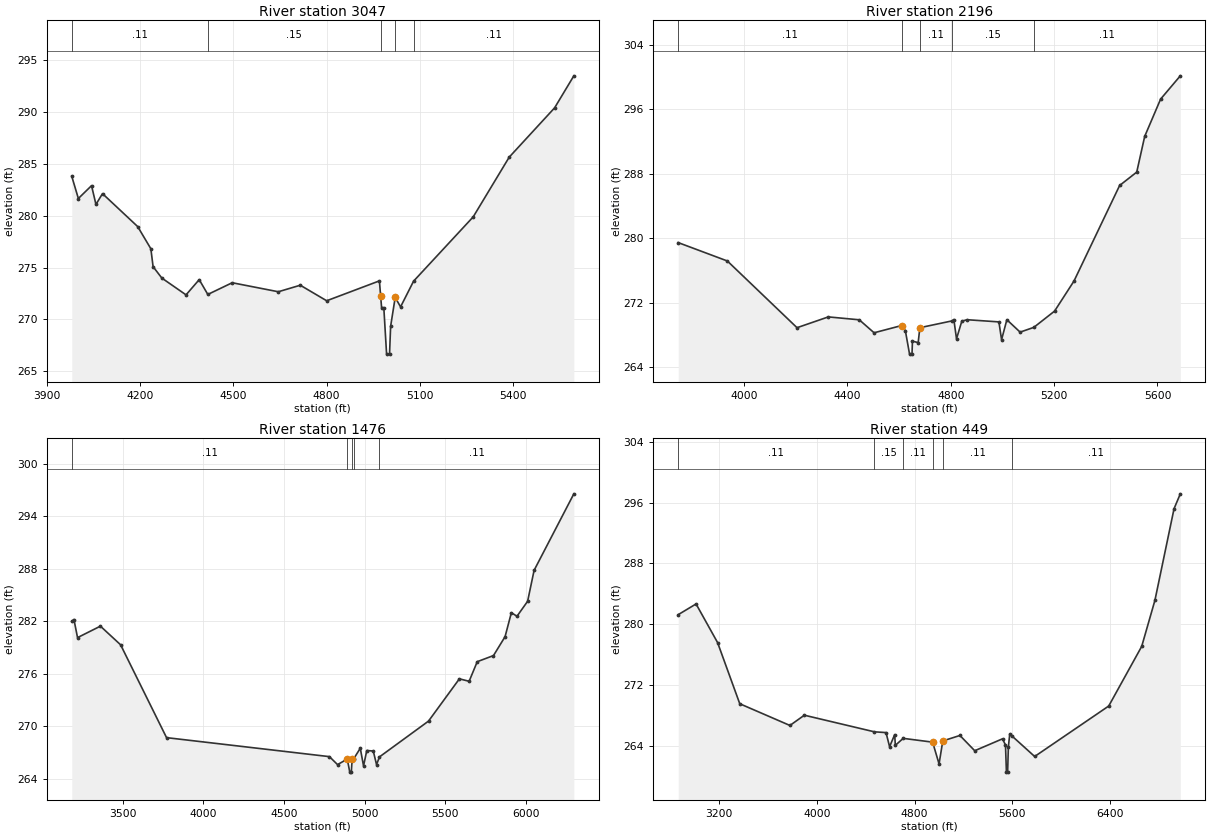
Type RM Length L Ch R = 1 ,3047    ,851,851,851
BEGIN DESCRIPTION:
CCLC 066 2.0
END DESCRIPTION:
XS GIS Cut Line= 3
      3705217.86     10177661.07      3705946.07      10176946.7
      3706154.86      10176388.9
#Sta/Elev= 30
  3979.9  283.81  4001.1  281.67  4043.5  282.91  4057.7   281.1  4078.8  282.14
    4192  278.96  4234.4  276.82  4241.6  275.09  4269.8  273.99  4347.6  272.37
    4390  273.84  4417.7  272.41  4496.2  273.54  4644.6  272.67  4715.3   273.3
  4800.2   271.8  4969.9  273.72 4973.82272.2752  4976.9  271.14  4984.1  271.13
    4993  266.65  5002.5  266.65    5006  269.34  5020.7  272.12    5038  271.21
  5079.8  273.69  5271.8   279.9  5387.6  285.66  5533.7  290.42  5595.6  293.51
#Mann= 5 ,-1 , 0
  3979.9     .11       0  4417.7     .15       0 4973.82     .09       0
  5020.7     .15       0  5079.8     .11       0
Bank Sta=4973.82,5020.7
XS Rating Curve= 0 ,0
Exp/Cntr=0.3,0.1

Type RM Length L Ch R = 1 ,2196    ,720,720,720
BEGIN DESCRIPTION:
Mapping XS d71c4f0e
END DESCRIPTION:
XS GIS Cut Line= 3
      3705918.77     10177979.19      3706675.68     10177354.21
       3706460.4      10176416.7
#Sta/Elev= 30
  3744.9  279.46    3935  277.18  4204.7   268.9  4325.9  270.24  4445.7  269.88
    4503  268.27  4609.9  269.17  4624.2  268.51  4640.3  265.62  4649.8  265.62
  4651.5  267.23  4673.7  267.05  4680.2   268.9  4805.5  269.75  4811.8  269.91
  4822.1  267.52  4842.6  269.71  4863.1  269.89  4986.2  269.62  4996.5  267.41
    5017  269.89  5068.3  268.35  5121.3  268.94  5201.7  270.96    5277   274.7
  5453.5  286.55  5519.7  288.21  5550.5  292.64  5612.1  297.27  5688.4  300.16
#Mann= 5 ,-1 , 0
  3744.9     .11       0  4609.9     .09       0  4680.2     .11       0
  4805.5     .15       0  5121.3     .11       0
Bank Sta=4609.9,4680.2
XS Rating Curve= 0 ,0
Exp/Cntr=0.3,0.1

Type RM Length L Ch R = 1 ,1476    ,1027,1027,1027
BEGIN DESCRIPTION:
Mapping XS d3128919
END DESCRIPTION:
XS GIS Cut Line= 3
      3705925.71     10178055.59      3707328.46      10177368.1
      3707127.07     10175826.45
#Sta/Elev= 30
  3182.3  282.01  3195.8  282.22  3218.1  280.15  3360.1  281.46  3485.4  279.33
  3770.7  268.72  4781.8  266.55  4832.2  265.64  4892.7  266.27  4908.1  264.78
  4917.7  264.78    4923  266.32  4933.1  266.32  4973.4  267.51  4993.6  265.49
  5013.8  267.25  5054.1  267.19  5074.3  265.64  5092.5  266.52    5397  270.61
  5588.6  275.44  5649.1  275.16  5699.5   277.4  5800.4   278.1  5872.3  280.26
  5911.3     283  5946.2  282.59  6012.2   284.3  6052.5  287.84  6299.2  296.58
#Mann= 5 ,-1 , 0
  3182.3     .11       0  4892.7     .09       0    4923     .12       0
  4933.1     .15       0  5092.5     .11       0
Bank Sta=4892.7,4923
XS Rating Curve= 0 ,0
Exp/Cntr=0.3,0.1

Type RM Length L Ch R = 1 ,449     ,0,0,0
BEGIN DESCRIPTION:
CCLC 066 1.0
END DESCRIPTION:
XS GIS Cut Line= 3
      3706008.99     10178083.39      3708265.96      10177118.1
      3707655.38     10175584.72
#Sta/Elev= 30
  2867.6  281.25  3013.3  282.66  3189.3  277.57  3370.7  269.51  3780.8  266.65
  3898.8     268  4471.9  265.81  4566.5  265.71  4595.7  263.85  4637.3  265.44
  4642.8  264.03    4707  264.95  4947.6  264.45  5000.2  261.58  5030.7  264.61
  5170.8  265.33  5291.8  263.32  5519.1  264.89  5543.4  264.07    5551   260.5
  5560.9   260.5  5566.7   263.8  5578.4  265.53  5598.6  265.23    5782  262.56
  6387.5  269.21  6657.2  277.07  6765.1  283.13  6921.6  295.21  6972.8  297.17
#Mann= 6 ,-1 , 0
  2867.6     .11       0  4471.9     .15       0    4707     .11       0
  4947.6    .065       0  5030.7     .11       0  5598.6     .11       0
Bank Sta=4947.6,5030.7
XS Rating Curve= 0 ,0
Exp/Cntr=0.3,0.1

Chan Stop Cuts=-1
Use User Specified Reach Order=0
Composite Channel Slope=5