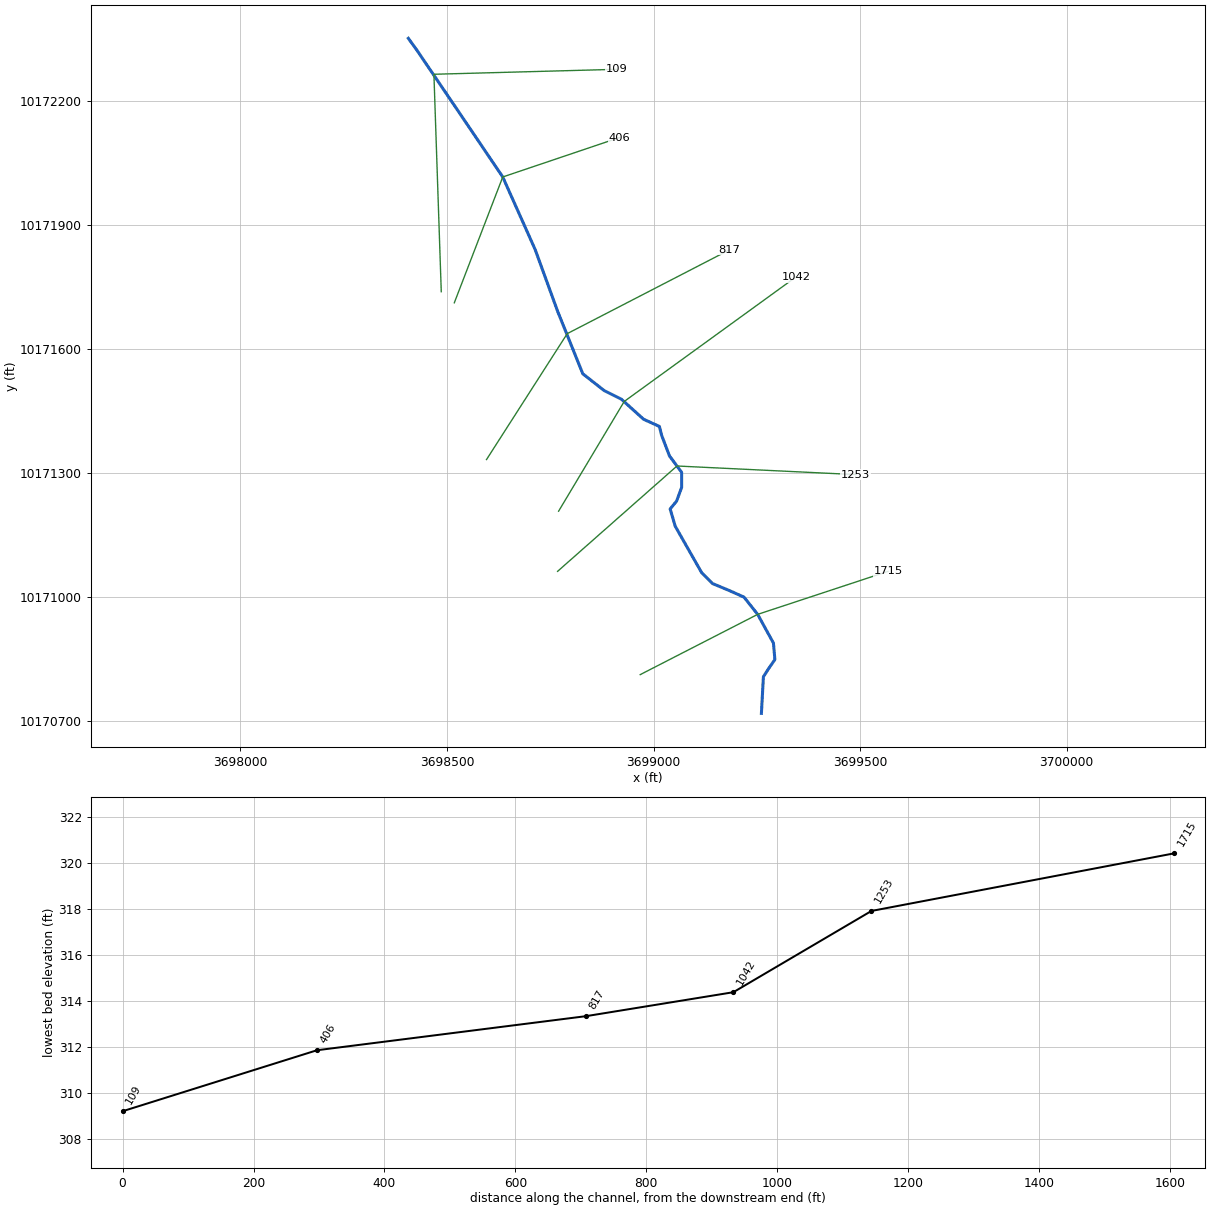
--- CCLC 067.prj (project) ---

Proj Title=CCLC 067 Base Level Engineering
Current Plan=p01
Default Exp/Contr=0.3,0.1
English Units
Geom File=g01
Flow File=f01
Flow File=f02
Plan File=p01
Y Axis Title=Elevation
X Axis Title(PF)=Main Channel Distance
X Axis Title(XS)=Station
BEGIN DESCRIPTION:
CCLC 067
END DESCRIPTION:
DSS Export Rating Curves= 0
DSS Export Rating Curve Sorted= 0
DSS Export Volume Flow Curves= 0
DXF OffsetX= 0
DXF OffsetY= 0
DXF ScaleX= 1
DXF ScaleY= 10

--- CCLC 067.p01 (plan) ---

Plan Title=Multiple Run
Short Identifier=Multiple
Geom File=g01
Flow File=f01
Subcritical Flow
K Sum by GR= 0
Std Step Tol= 0.01
Critical Tol= 0.01
Num of Std Step Trials= 20
Max Error Tol= 0.3
Flow Tol Ratio= 0.001
Split Flow NTrial= 30
Split Flow Tol= 0.02
Split Flow Ratio= 0.02
Log Output Level= 0
Friction Slope Method= 1
Unsteady Friction Slope Method= 2
Unsteady Bridges Friction Slope Method= 1
Parabolic Critical Depth
Global Vel Dist=  1 , 1 , 1
Global Log Level= 0
CheckData=True
Encroach Param= -1, 0, 0, 0
BEGIN DESCRIPTION:
Multiple Run
END DESCRIPTION:

--- CCLC 067.f01 (steady flow) ---

Flow Title=Multiple
Program Version=4.10
Number of Profiles= 7
Profile Names=10-year,25-year,50-year,1pct_min,100-year,1pct_plu,500-year
River Rch & RM=CCLC 067,Reach-1         ,1715
     240     307     399     171     517    1561     900
Boundary for River Rch & Prof#=CCLC 067,Reach-1         , 1
Up Type= 0
Dn Type= 3
Dn Slope=0.01
Boundary for River Rch & Prof#=CCLC 067,Reach-1         , 2
Up Type= 0
Dn Type= 3
Dn Slope=0.01
Boundary for River Rch & Prof#=CCLC 067,Reach-1         , 3
Up Type= 0
Dn Type= 3
Dn Slope=0.01
Boundary for River Rch & Prof#=CCLC 067,Reach-1         , 4
Up Type= 0
Dn Type= 3
Dn Slope=0.01
Boundary for River Rch & Prof#=CCLC 067,Reach-1         , 5
Up Type= 0
Dn Type= 3
Dn Slope=0.01
Boundary for River Rch & Prof#=CCLC 067,Reach-1         , 6
Up Type= 0
Dn Type= 3
Dn Slope=0.01
Boundary for River Rch & Prof#=CCLC 067,Reach-1         , 7
Up Type= 0
Dn Type= 3
Dn Slope=0.01
DSS Import GetInterval= 0
DSS Import GetPeak= 0
DSS Import FillOption= 0

--- CCLC 067.f02 (steady flow) ---

Flow Title=Orig_BLE_Flows
Program Version=4.10
Number of Profiles= 7
Profile Names=10-year,25-year,50-year,1pct_min,100-year,1pct_plu,500-year
River Rch & RM=CCLC 067,Reach-1         ,1715
     240     301     347     132     398    1203     523
Boundary for River Rch & Prof#=CCLC 067,Reach-1         , 1
Up Type= 0
Dn Type= 3
Dn Slope=0.006
Boundary for River Rch & Prof#=CCLC 067,Reach-1         , 2
Up Type= 0
Dn Type= 3
Dn Slope=0.006
Boundary for River Rch & Prof#=CCLC 067,Reach-1         , 3
Up Type= 0
Dn Type= 3
Dn Slope=0.006
Boundary for River Rch & Prof#=CCLC 067,Reach-1         , 4
Up Type= 0
Dn Type= 3
Dn Slope=0.006
Boundary for River Rch & Prof#=CCLC 067,Reach-1         , 5
Up Type= 0
Dn Type= 3
Dn Slope=0.006
Boundary for River Rch & Prof#=CCLC 067,Reach-1         , 6
Up Type= 0
Dn Type= 3
Dn Slope=0.006
Boundary for River Rch & Prof#=CCLC 067,Reach-1         , 7
Up Type= 0
Dn Type= 3
Dn Slope=0.006
DSS Import GetInterval= 0
DSS Import GetPeak= 0
DSS Import FillOption= 0

--- CCLC 067.g01 (geometry) ---

Geom Title=Existing Conditions
Program Version=4.10

River Reach=CCLC 067        ,Reach-1
Reach XY= 28
      3699261.13     10170717.27      3699265.98     10170805.86
      3699278.13     10170824.96      3699293.76     10170847.53
      3699290.29     10170887.46      3699252.09      10170956.9
      3699219.11     10170998.57      3699184.38     10171014.19
      3699142.72     10171031.55      3699116.68      10171057.6
      3699052.44     10171170.44      3699040.29     10171212.11
      3699055.91     10171231.21      3699068.06     10171264.19
      3699068.06     10171300.65      3699038.55     10171340.58
      3699019.45     10171390.93      3699014.24     10171411.76
      3698976.05     10171429.12      3698922.23     10171477.74
      3698880.56     10171498.57      3698828.83     10171539.19
      3698768.41     10171689.19      3698713.55     10171839.89
      3698635.08     10172015.58      3698535.08      10172163.5
      3698426.74     10172323.22      3698406.57     10172351.14

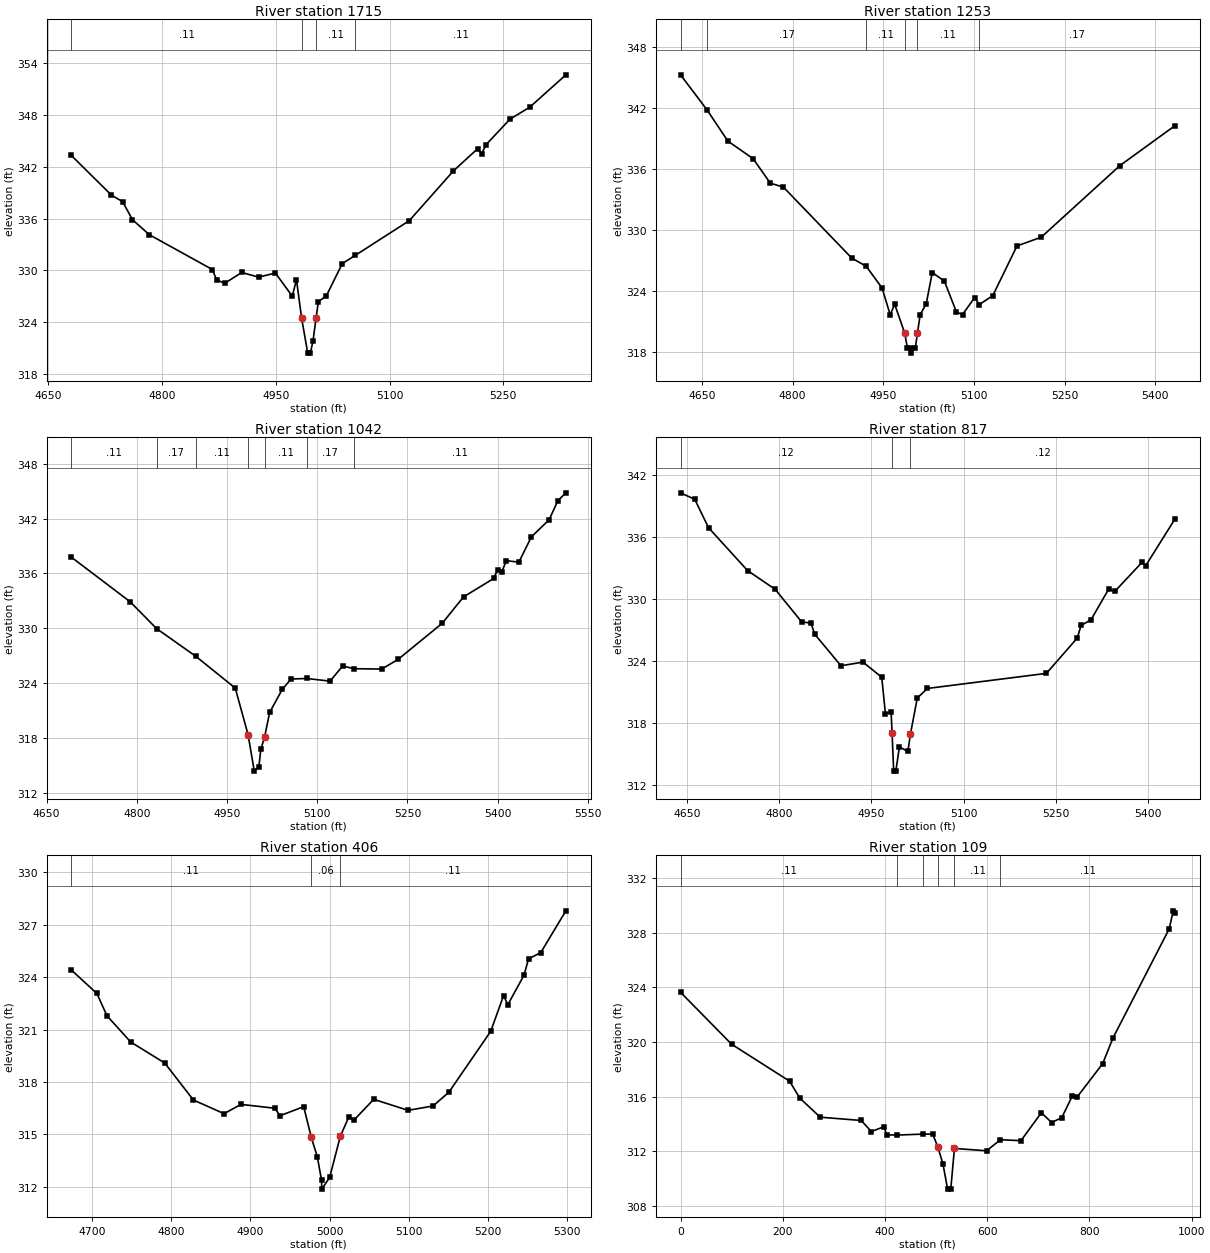
Type RM Length L Ch R = 1 ,1715    ,462,462,462
BEGIN DESCRIPTION:
CCLC 067 4.0
END DESCRIPTION:
XS GIS Cut Line= 3
      3698967.82     10170811.06      3699252.09      10170956.9
      3699567.85     10171061.07
#Sta/Elev= 30
  4680.5  343.33  4733.2  338.74    4748  337.98    4761  335.89  4783.2  334.15
  4866.4  330.11    4872   328.9  4882.8  328.52  4905.1  329.77  4927.3  329.23
  4949.5   329.7  4971.7  327.03  4977.3  328.92    4984  324.52  4992.1  320.42
  4995.6  320.42  4999.1  321.86 5003.12324.4865  5006.1  326.38  5016.6  327.05
  5037.7   330.8  5055.1  331.77  5126.1  335.78  5184.3  341.55  5216.1  344.11
  5221.4  343.51  5227.2  344.58  5258.8  347.54  5284.9  348.93  5332.5  352.68
#Mann= 4 ,-1 , 0
  4680.5     .11       0    4984     .09       0 5003.12     .11       0
  5055.1     .11       0
Bank Sta=4984,5003.12
XS Rating Curve= 0 ,0
Exp/Cntr=0.3,0.1

Type RM Length L Ch R = 1 ,1253    ,211,211,211
BEGIN DESCRIPTION:
CCLC 067 3.0
END DESCRIPTION:
XS GIS Cut Line= 3
      3698767.83     10171061.05      3699056.76     10171316.02
      3699489.01     10171295.19
#Sta/Elev= 30
  4614.7  345.26  4658.1  341.85    4693  338.75  4734.8  337.02  4763.2  334.62
    4785  334.22  4897.9  327.26  4921.9  326.45  4948.1  324.32  4961.5  321.69
    4969  322.72 4985.58319.8803  4989.9  318.46  4995.4  318.42  4995.7  317.92
  5003.1  318.42 5006.68319.8834  5011.1  321.69  5021.2  322.78  5031.2  325.84
  5051.2  324.99  5071.2  321.95  5081.2  321.71  5101.3  323.38  5108.9  322.69
  5131.3  323.57  5171.3  328.45  5211.5  329.31  5341.5  336.34  5432.8  340.27
#Mann= 6 ,-1 , 0
  4614.7     .11       0  4658.1     .17       0  4921.9     .11       0
 4985.58     .07       0 5006.68     .11       0  5108.9     .17       0
Bank Sta=4985.58,5006.68
XS Rating Curve= 0 ,0
Exp/Cntr=0.3,0.1

Type RM Length L Ch R = 1 ,1042    ,225,225,225
BEGIN DESCRIPTION:
CCLC 067 2.0
END DESCRIPTION:
XS GIS Cut Line= 3
       3698770.3     10171206.65      3698929.15     10171472.27
      3699344.33     10171773.27
#Sta/Elev= 30
  4691.1  337.78  4788.6  332.92  4832.7  329.98  4898.1  326.94  4963.6  323.47
    4985  318.35  4995.2  314.39  5002.9  314.89  5006.1  316.76  5012.3  318.09
  5020.8  320.81  5041.7  323.32  5056.4  324.46  5082.2  324.52  5121.3  324.23
  5142.2  325.89  5160.7  325.59  5207.2  325.55  5234.2   326.6  5307.7  330.55
  5343.2  333.44  5393.5  335.46  5399.7  336.41  5406.6  336.15  5414.4   337.4
  5435.2  337.24  5456.1  340.01  5485.5  341.87  5500.2  343.97  5513.4  344.82
#Mann= 7 ,-1 , 0
  4691.1     .11       0  4832.7     .17       0  4898.1     .11       0
    4985     .07       0  5012.3     .11       0  5082.2     .17       0
  5160.7     .11       0
Bank Sta=4985,5012.3
XS Rating Curve= 0 ,0
Exp/Cntr=0.3,0.1

Type RM Length L Ch R = 1 ,817     ,411,411,411
BEGIN DESCRIPTION:
Mapping XS a68070ec
END DESCRIPTION:
XS GIS Cut Line= 3
      3698595.81     10171331.63      3698791.13     10171636.33
      3699183.63     10171839.08
#Sta/Elev= 30
  4639.7  340.31  4662.8  339.68  4685.2  336.93  4748.6  332.78  4793.5  330.96
  4836.5  327.81  4851.7  327.69  4857.7  326.62  4900.4  323.56  4936.3  323.91
  4966.7  322.44  4972.7  318.91  4981.9  319.12 4983.51 316.999  4986.1  313.35
  4989.6  313.35  4995.4  315.69  5009.2  315.26 5013.37 316.951  5024.5  320.44
    5041  321.36  5234.3  322.82  5284.6  326.25  5290.6  327.46  5306.8  328.01
  5335.6  330.99  5345.5  330.76  5389.8  333.58  5395.4  333.22  5443.4  337.79
#Mann= 3 ,-1 , 0
  4639.7     .12       0 4983.51     .07       0 5013.37     .12       0
Bank Sta=4983.51,5013.37
XS Rating Curve= 0 ,0
Exp/Cntr=0.3,0.1

Type RM Length L Ch R = 1 ,406     ,297,297,297
BEGIN DESCRIPTION:
CCLC 067 1.0
END DESCRIPTION:
XS GIS Cut Line= 3
      3698517.85     10171711.07      3698635.08     10172015.58
      3698917.89     10172111.08
#Sta/Elev= 30
  4673.7  324.41  4705.9  323.07  4718.7  321.79  4748.7  320.29  4791.6  319.09
  4827.9  316.97  4866.6  316.19    4888  316.72  4930.9   316.5  4937.2  316.07
  4967.2  316.59 4976.81 314.835  4984.5  313.71  4989.8  312.37  4990.1  311.87
    5000  312.54  5013.5  314.89    5024  315.98  5031.1  315.84  5055.7  317.01
  5099.2  316.38  5130.7  316.63  5150.7  317.42  5203.5   320.9  5219.8  322.95
  5225.1  322.42  5245.7  324.13  5251.3  325.05  5266.8  325.41  5298.5   327.8
#Mann= 3 , 0 , 0
  4673.7     .11       0 4976.81     .06       0  5013.5     .11       0
Bank Sta=4976.81,5013.5
XS Rating Curve= 0 ,0
Exp/Cntr=0.3,0.1

Type RM Length L Ch R = 1 ,109     ,0,0,0
BEGIN DESCRIPTION:
CCLC 067 1.0
END DESCRIPTION:
XS GIS Cut Line= 3
      3698486.28     10171737.92      3698468.48     10172264.18
       3698910.1     10172276.12
#Sta/Elev= 30
       0  323.64    99.8  319.84   213.3  317.13   233.3  315.89   273.3  314.49
   353.4  314.25   373.4  313.44   397.8  313.79   403.4   313.2   423.4  313.18
   473.4  313.25   493.4  313.25   503.4  312.31   513.4  311.07   522.5  309.22
   528.7  309.22   535.9   312.2   598.7  312.03     626  312.84     666  312.77
     706  314.82     726   314.1     746  314.46     766  316.01     776  315.97
     826  318.42     846  320.29   956.1  328.29   963.9  329.61   967.5  329.45
#Mann= 6 ,-1 , 0
       0     .11       0   423.4     .11       0   473.4     .11       0
   503.4     .06       0   535.9     .11       0     626     .11       0
Bank Sta=503.4,535.9
XS Rating Curve= 0 ,0
Exp/Cntr=0.3,0.1

Chan Stop Cuts=-1
Use User Specified Reach Order=0
Composite Channel Slope=5