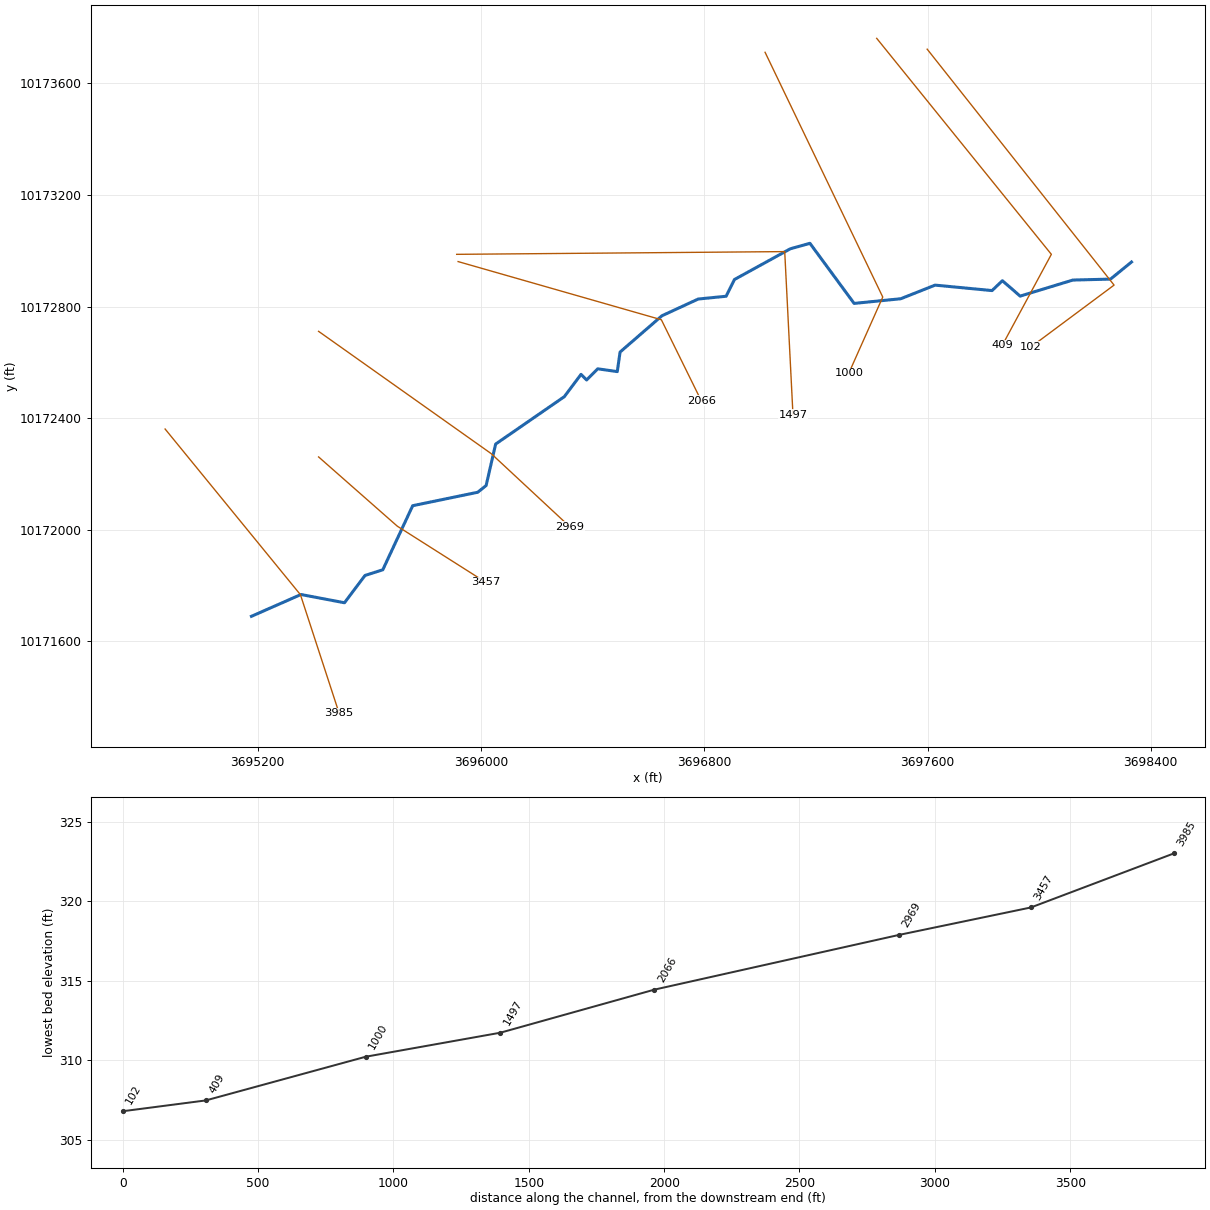
--- CCLC 068.prj (project) ---

Proj Title=CCLC 068 Base Level Engineering
Current Plan=p01
Default Exp/Contr=0.3,0.1
English Units
Geom File=g01
Flow File=f01
Flow File=f02
Plan File=p01
Y Axis Title=Elevation
X Axis Title(PF)=Main Channel Distance
X Axis Title(XS)=Station
BEGIN DESCRIPTION:
CCLC 068
END DESCRIPTION:
DSS Export Rating Curves= 0
DSS Export Rating Curve Sorted= 0
DSS Export Volume Flow Curves= 0
DXF OffsetX= 0
DXF OffsetY= 0
DXF ScaleX= 1
DXF ScaleY= 10

--- CCLC 068.p01 (plan) ---

Plan Title=Multiple Run
Short Identifier=Multiple
Geom File=g01
Flow File=f01
Subcritical Flow
K Sum by GR= 0
Std Step Tol= 0.01
Critical Tol= 0.01
Num of Std Step Trials= 20
Max Error Tol= 0.3
Flow Tol Ratio= 0.001
Split Flow NTrial= 30
Split Flow Tol= 0.02
Split Flow Ratio= 0.02
Log Output Level= 0
Friction Slope Method= 1
Unsteady Friction Slope Method= 2
Unsteady Bridges Friction Slope Method= 1
Parabolic Critical Depth
Global Vel Dist=  1 , 1 , 1
Global Log Level= 0
CheckData=True
Encroach Param= -1, 0, 0, 0
BEGIN DESCRIPTION:
Multiple Run
END DESCRIPTION:

--- CCLC 068.f01 (steady flow) ---

Flow Title=Multiple
Program Version=4.10
Number of Profiles= 7
Profile Names=10-year,25-year,50-year,1pct_min,100-year,1pct_plu,500-year
River Rch & RM=CCLC 068,Reach-1         ,3985
     496     671     906     403    1218    3678    2277
River Rch & RM=CCLC 068,Reach-1         ,1000
     945    1318    1817     823    2484    7502    4811
Boundary for River Rch & Prof#=CCLC 068,Reach-1         , 1
Up Type= 0
Dn Type= 3
Dn Slope=0.0055
Boundary for River Rch & Prof#=CCLC 068,Reach-1         , 2
Up Type= 0
Dn Type= 3
Dn Slope=0.0055
Boundary for River Rch & Prof#=CCLC 068,Reach-1         , 3
Up Type= 0
Dn Type= 3
Dn Slope=0.0055
Boundary for River Rch & Prof#=CCLC 068,Reach-1         , 4
Up Type= 0
Dn Type= 3
Dn Slope=0.0055
Boundary for River Rch & Prof#=CCLC 068,Reach-1         , 5
Up Type= 0
Dn Type= 3
Dn Slope=0.0055
Boundary for River Rch & Prof#=CCLC 068,Reach-1         , 6
Up Type= 0
Dn Type= 3
Dn Slope=0.0055
Boundary for River Rch & Prof#=CCLC 068,Reach-1         , 7
Up Type= 0
Dn Type= 3
Dn Slope=0.0055
DSS Import GetInterval= 0
DSS Import GetPeak= 0
DSS Import FillOption= 0

--- CCLC 068.f02 (steady flow) ---

Flow Title=Orig_BLE_Flows
Program Version=4.10
Number of Profiles= 7
Profile Names=10-year,25-year,50-year,1pct_min,100-year,1pct_plu,500-year
River Rch & RM=CCLC 068,Reach-1         ,3985
     496     658     788     310     937    2831    1324
River Rch & RM=CCLC 068,Reach-1         ,1000
     945    1292    1580     633    1911    5773    2797
Boundary for River Rch & Prof#=CCLC 068,Reach-1         , 1
Up Type= 0
Dn Type= 3
Dn Slope=0.0055
Boundary for River Rch & Prof#=CCLC 068,Reach-1         , 2
Up Type= 0
Dn Type= 3
Dn Slope=0.0055
Boundary for River Rch & Prof#=CCLC 068,Reach-1         , 3
Up Type= 0
Dn Type= 3
Dn Slope=0.0055
Boundary for River Rch & Prof#=CCLC 068,Reach-1         , 4
Up Type= 0
Dn Type= 3
Dn Slope=0.0055
Boundary for River Rch & Prof#=CCLC 068,Reach-1         , 5
Up Type= 0
Dn Type= 3
Dn Slope=0.0055
Boundary for River Rch & Prof#=CCLC 068,Reach-1         , 6
Up Type= 0
Dn Type= 3
Dn Slope=0.0055
Boundary for River Rch & Prof#=CCLC 068,Reach-1         , 7
Up Type= 0
Dn Type= 3
Dn Slope=0.0055
DSS Import GetInterval= 0
DSS Import GetPeak= 0
DSS Import FillOption= 0

--- CCLC 068.g01 (geometry) ---

Geom Title=Existing Conditions
Program Version=4.10

River Reach=CCLC 068        ,Reach-1
Reach XY= 30
      3695177.26     10171689.91      3695354.76     10171768.02
      3695510.64     10171738.48      3695584.23     10171836.29
      3695647.92     10171856.57      3695755.08     10172086.25
      3695988.09     10172134.45      3696018.21     10172158.54
      3696052.34     10172307.11      3696298.23     10172476.84
      3696358.23     10172556.84      3696378.23     10172536.84
      3696418.23     10172576.84      3696488.23     10172566.84
      3696498.23     10172636.84      3696648.23     10172766.84
      3696778.23     10172826.84      3696878.23     10172836.84
      3696908.23     10172896.84      3697108.23     10173006.84
      3697178.58     10173026.53       3697336.9     10172811.19
      3697503.91     10172827.87      3697627.24     10172876.67
      3697831.27     10172857.16      3697868.24     10172892.57
       3697931.9     10172837.32      3698120.73     10172894.85
      3698255.73     10172898.25      3698330.85     10172959.46

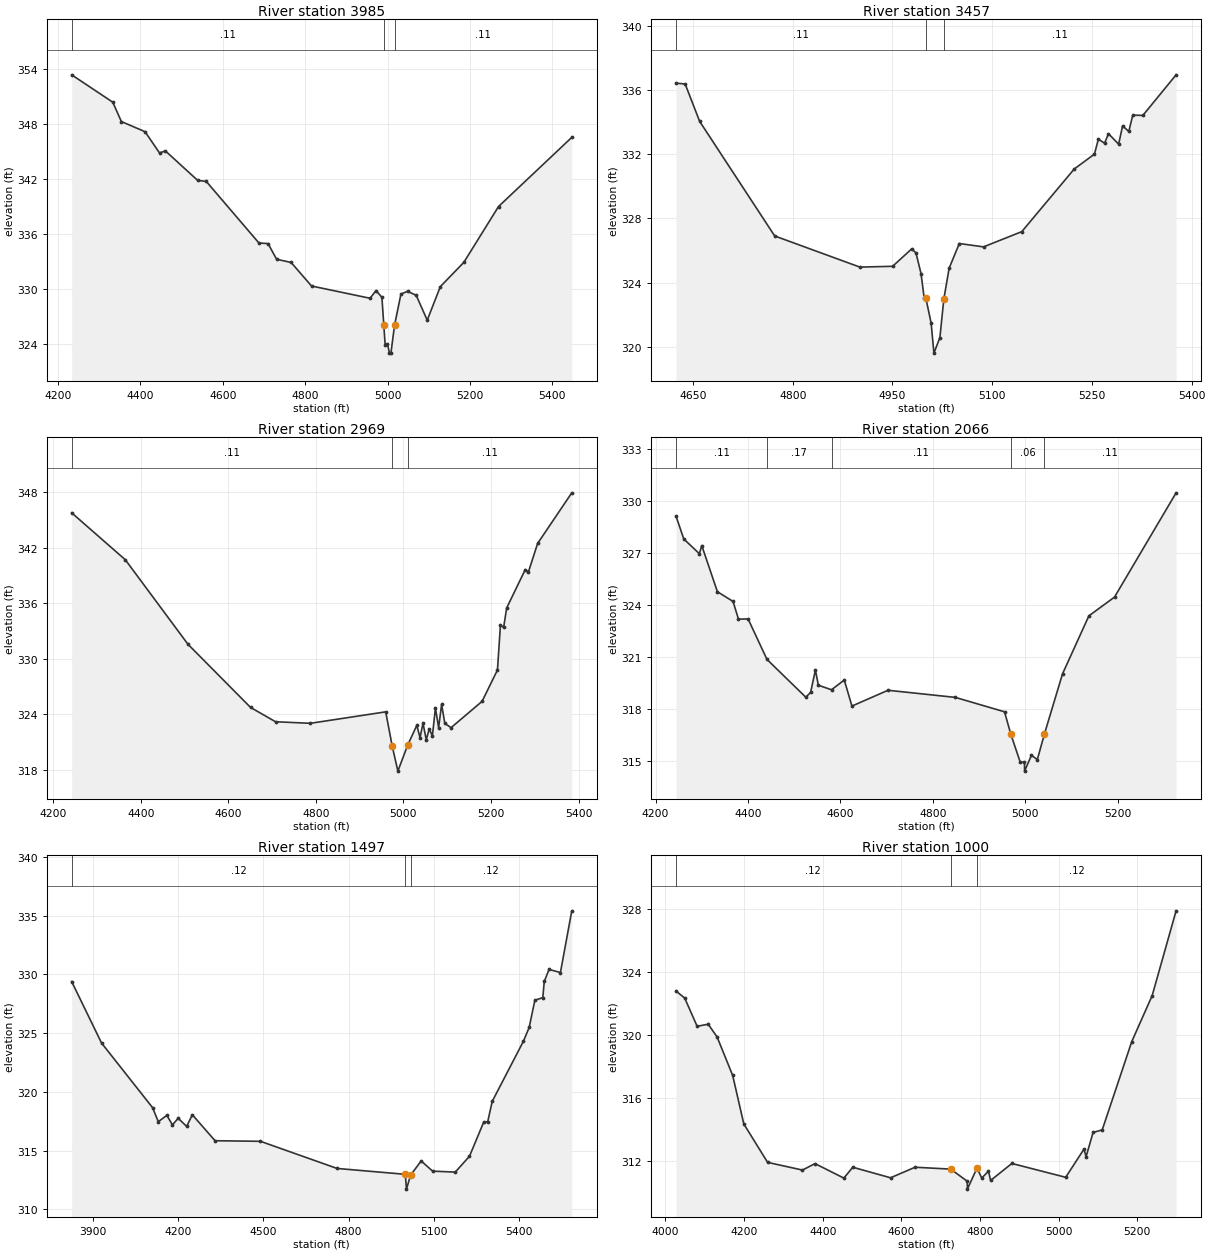
Type RM Length L Ch R = 1 ,3985    ,528,528,528
BEGIN DESCRIPTION:
CCLC 068 7.0
END DESCRIPTION:
XS GIS Cut Line= 3
      3694867.84     10172361.08      3695352.76     10171767.41
      3695491.65     10171342.06
#Sta/Elev= 30
    4233  353.39  4332.8   350.4  4353.6  348.29  4411.1  347.18  4446.2  344.86
  4460.6  345.08  4538.9  341.86  4559.7  341.75  4687.5  335.03  4709.7  334.96
  4730.5  333.25  4765.7   332.9  4815.3  330.33  4957.4  328.99  4971.8  329.83
  4986.1  329.09 4990.68326.0752    4994  323.89  4999.6  323.99  5004.5     323
    5008     323  5016.7  326.04  5032.3  329.45  5048.3  329.75  5069.4  329.31
  5096.1   326.6  5127.9  330.26  5185.1  332.92  5269.2  339.01    5447  346.56
#Mann= 3 , 0 , 0
    4233     .11       0 4990.68     .06       0  5016.7     .11       0
Bank Sta=4990.68,5016.7
XS Rating Curve= 0 ,0
Exp/Cntr=0.3,0.1

Type RM Length L Ch R = 1 ,3457    ,488,488,488
BEGIN DESCRIPTION:
CCLC 068 6.0
END DESCRIPTION:
XS GIS Cut Line= 3
      3695417.84     10172261.08      3695699.89     10172012.89
      3696017.85     10171811.07
#Sta/Elev= 30
  4624.3  336.42  4638.1  336.37  4659.9  334.04  4772.8   326.9  4900.9  324.96
  4950.2  325.01  4978.7  326.09  4985.3  325.85  4992.9  324.56  4997.6  323.06
    5000  323.06  5008.1  321.48  5012.3   319.6  5021.3  320.57 5027.21322.9636
  5035.2  324.89  5050.5  326.43  5086.9  326.22  5144.5  327.17  5223.3  331.07
  5253.8     332  5259.7  332.93    5269  332.68  5274.9  333.27  5290.2  332.62
  5296.1  333.76  5305.5  333.41  5311.4  334.43  5326.6  334.41  5376.6  336.94
#Mann= 3 , 0 , 0
  4624.3     .11       0    5000     .06       0 5027.21     .11       0
Bank Sta=5000,5027.21
XS Rating Curve= 0 ,0
Exp/Cntr=0.3,0.1

Type RM Length L Ch R = 1 ,2969    ,903,903,903
BEGIN DESCRIPTION:
CCLC 068 5.0
END DESCRIPTION:
XS GIS Cut Line= 3
      3695417.83     10172711.09      3696036.28     10172272.98
      3696317.89     10172011.04
#Sta/Elev= 30
  4242.1   345.8  4364.7  340.72  4507.9  331.58  4650.7  324.76  4707.8  323.21
  4787.3  323.04  4959.5  324.28  4974.3  320.59  4987.3  317.87  5009.6  320.67
  5030.6  322.82  5037.9  321.48  5044.7  323.05  5052.1  321.27  5058.9  322.41
  5066.2   321.7  5073.1   324.7  5080.4  322.58  5087.2  325.08  5094.6  323.03
  5108.8  322.57  5179.6  325.41  5214.8   328.8  5221.6  333.66  5228.9   333.4
  5235.8   335.5  5278.3  339.66  5285.6  339.41  5306.6  342.49  5384.6  347.96
#Mann= 3 , 0 , 0
  4242.1     .11       0  4974.3     .06       0  5009.6     .11       0
Bank Sta=4974.3,5009.6
XS Rating Curve= 0 ,0
Exp/Cntr=0.3,0.1

Type RM Length L Ch R = 1 ,2066    ,569,569,569
BEGIN DESCRIPTION:
CCLC 068 4.0
END DESCRIPTION:
XS GIS Cut Line= 3
      3695917.88     10172961.06      3696646.17     10172752.65
       3696789.4     10172461.84
#Sta/Elev= 30
  4244.2  329.13  4261.1  327.81  4294.8  326.96    4300  327.43  4333.8  324.77
  4367.6  324.21  4379.4  323.19  4400.2   323.2    4441  320.87    4525  318.69
  4535.4  318.97  4545.8  320.26  4552.1  319.38  4580.6  319.12  4608.2  319.68
  4624.8  318.18  4702.8  319.09  4848.3  318.68  4954.8  317.85 4968.11316.5865
  4988.6  314.96    4998  314.93  4998.2  314.43    5013  315.34  5025.8   315.1
    5041  316.56  5080.3  320.04  5137.3  323.38  5192.7  324.46  5325.9  330.47
#Mann= 5 ,-1 , 0
  4244.2     .11       0    4441     .17       0  4580.6     .11       0
 4968.11     .06       0    5041     .11       0
Bank Sta=4968.11,5041
XS Rating Curve= 0 ,0
Exp/Cntr=0.3,0.1

Type RM Length L Ch R = 1 ,1497    ,497,497,497
BEGIN DESCRIPTION:
CCLC 068 3.0
END DESCRIPTION:
XS GIS Cut Line= 3
      3695912.67     10172987.03      3697088.23     10172996.84
      3697117.85     10172411.09
#Sta/Elev= 30
  3824.4  329.39  3929.6  324.16  4109.6  318.65  4129.6  317.46  4159.6     318
  4179.6  317.19  4199.6  317.75  4229.6  317.06  4249.6  318.05  4329.6  315.84
  4489.6  315.79  4759.6  313.48    5000  312.98    5004  311.72 5018.35312.8999
  5055.8  314.12  5096.2  313.25    5176  313.17  5226.1  314.52  5276.1  317.42
  5290.3  317.46  5306.2  319.19  5416.3  324.32  5436.3  325.48  5456.4   327.8
  5484.5  328.02  5489.5   329.4  5506.4  330.42  5546.5  330.16  5586.5  335.41
#Mann= 3 , 0 , 0
  3824.4     .12       0    5000     .07       0 5018.35     .12       0
Bank Sta=5000,5018.35
XS Rating Curve= 0 ,0
Exp/Cntr=0.3,0.1

Type RM Length L Ch R = 1 ,1000    ,591,591,591
BEGIN DESCRIPTION:
CCLC 068 2.0
END DESCRIPTION:
XS GIS Cut Line= 3
      3697017.86     10173711.04      3697439.55     10172833.95
      3697317.84     10172561.05
#Sta/Elev= 30
  4026.8  322.79    4049  322.34  4080.6  320.55  4108.8  320.68  4131.4  319.87
    4171  317.43  4199.3  314.35  4259.8  311.91  4348.5  311.42  4380.4  311.83
  4453.8  310.91  4476.5   311.6  4572.6  310.93  4634.9   311.6  4725.5  311.48
  4767.7  310.71    4768  310.21  4792.4  311.55  4804.5  310.91  4821.6  311.35
  4827.1  310.76  4881.1  311.84    5018  310.96  5064.5  312.75  5069.9  312.27
  5087.7  313.81  5110.9  313.97  5186.1  319.58    5238   322.5  5298.8  327.88
#Mann= 3 , 0 , 0
  4026.8     .12       0  4725.5     .07       0  4792.4     .12       0
Bank Sta=4725.5,4792.4
XS Rating Curve= 0 ,0
Exp/Cntr=0.3,0.1

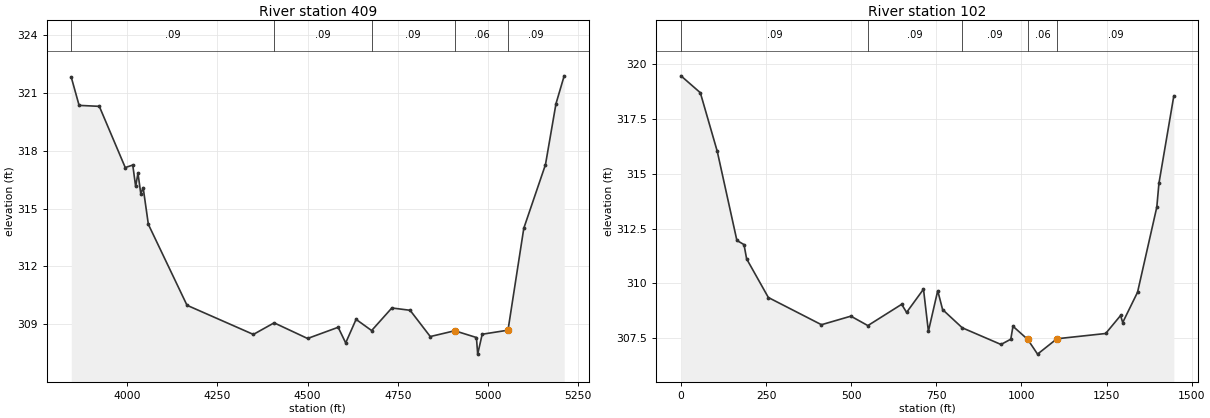
Type RM Length L Ch R = 1 ,409     ,307,307,307
BEGIN DESCRIPTION:
CCLC 068 1.0
END DESCRIPTION:
XS GIS Cut Line= 3
      3697417.85     10173761.07      3698043.74     10172987.03
      3697867.86     10172661.08
#Sta/Elev= 30
  3845.5  321.79  3867.1  320.34  3923.1  320.29    3995  317.12  4015.8  317.25
  4023.8  316.14  4030.2  316.83  4038.1  315.76  4044.6  316.08    4059  314.18
  4166.1  309.99    4350  308.48  4407.5  309.08  4500.2  308.27    4585  308.85
  4605.8  308.04  4634.6  309.26  4677.7  308.68  4733.7  309.85  4784.3  309.73
  4840.2  308.37  4908.1  308.67  4968.1  308.32  4971.6  307.46  4984.1  308.49
  5055.6   308.7  5099.4  313.98  5159.4  317.27  5188.6  320.43  5211.3  321.87
#Mann= 5 ,-1 , 0
  3845.5     .09       0  4407.5     .09       0  4677.7     .09       0
  4908.1     .06       0  5055.6     .09       0
Bank Sta=4908.1,5055.6
XS Rating Curve= 0 ,0
Exp/Cntr=0.3,0.1

Type RM Length L Ch R = 1 ,102     ,0,0,0
BEGIN DESCRIPTION:
CCLC 068 1.0
END DESCRIPTION:
XS GIS Cut Line= 3
      3697598.73     10173722.27      3698268.47     10172876.78
      3697970.86     10172655.34
#Sta/Elev= 30
       0  319.46    56.9  318.69   106.6  316.02   164.3  311.96   185.2  311.77
   192.9  311.12   256.7  309.36   412.7  308.12   499.1  308.51     549  308.08
   648.3  309.05   662.7  308.68   712.4  309.74   726.8  307.82   754.2  309.67
   768.5  308.81   826.2  307.98     940  307.22   968.8  307.46   975.2  308.05
  1018.5  307.45  1047.4  306.78  1104.3  307.48  1247.5  307.72  1291.3  308.54
  1297.5  308.22  1341.1   309.6  1397.7  313.48  1403.9  314.56  1447.7  318.55
#Mann= 5 ,-1 , 0
       0     .09       0     549     .09       0   826.2     .09       0
  1018.5     .06       0  1104.3     .09       0
Bank Sta=1018.5,1104.3
XS Rating Curve= 0 ,0
Exp/Cntr=0.3,0.1

Chan Stop Cuts=-1
Use User Specified Reach Order=0
Composite Channel Slope=5