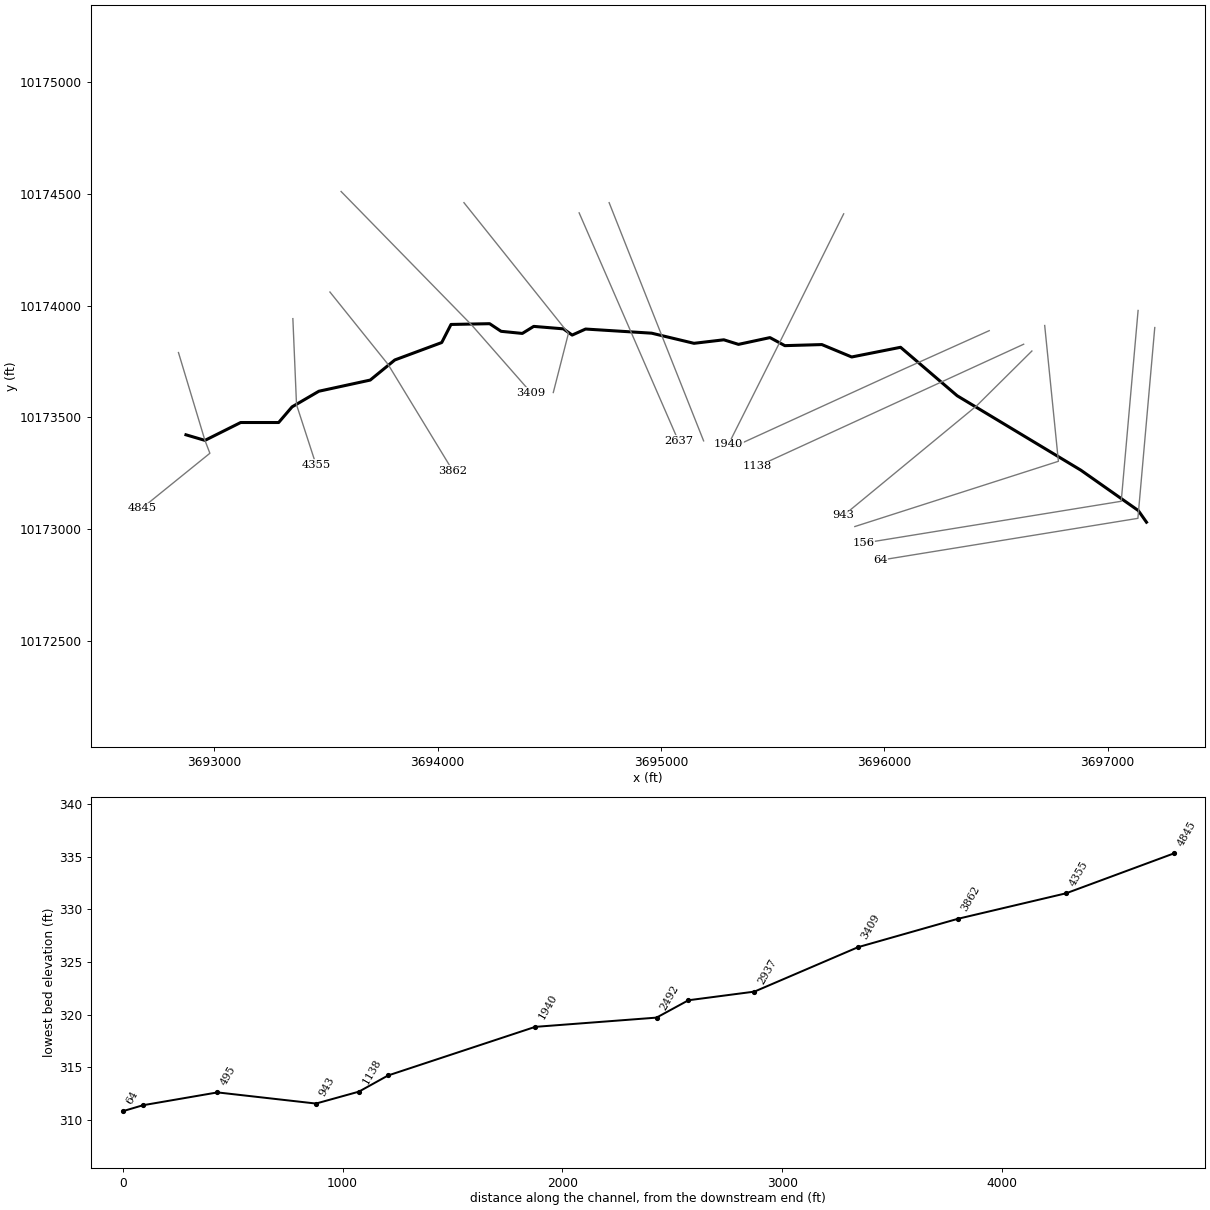
--- CCLC 069.prj (project) ---

Proj Title=CCLC 069 Base Level Engineering
Current Plan=p01
Default Exp/Contr=0.3,0.1
English Units
Geom File=g01
Flow File=f01
Flow File=f02
Plan File=p01
Y Axis Title=Elevation
X Axis Title(PF)=Main Channel Distance
X Axis Title(XS)=Station
BEGIN DESCRIPTION:
CCLC 069
END DESCRIPTION:
DSS Export Rating Curves= 0
DSS Export Rating Curve Sorted= 0
DSS Export Volume Flow Curves= 0
DXF OffsetX= 0
DXF OffsetY= 0
DXF ScaleX= 1
DXF ScaleY= 10

--- CCLC 069.p01 (plan) ---

Plan Title=Multiple Run
Short Identifier=Multiple
Geom File=g01
Flow File=f01
Subcritical Flow
K Sum by GR= 0
Std Step Tol= 0.01
Critical Tol= 0.01
Num of Std Step Trials= 20
Max Error Tol= 0.3
Flow Tol Ratio= 0.001
Split Flow NTrial= 30
Split Flow Tol= 0.02
Split Flow Ratio= 0.02
Log Output Level= 0
Friction Slope Method= 1
Unsteady Friction Slope Method= 2
Unsteady Bridges Friction Slope Method= 1
Parabolic Critical Depth
Global Vel Dist=  1 , 1 , 1
Global Log Level= 0
CheckData=True
Encroach Param= -1, 0, 0, 0
BEGIN DESCRIPTION:
Multiple Run
END DESCRIPTION:

--- CCLC 069.f01 (steady flow) ---

Flow Title=Multiple
Program Version=4.10
Number of Profiles= 7
Profile Names=10-year,25-year,50-year,1pct_min,100-year,1pct_plu,500-year
River Rch & RM=CCLC 069,Reach-1         ,4845
     719     990    1355     609    1840    5557    3514
Boundary for River Rch & Prof#=CCLC 069,Reach-1         , 1
Up Type= 0
Dn Type= 3
Dn Slope=0.005
Boundary for River Rch & Prof#=CCLC 069,Reach-1         , 2
Up Type= 0
Dn Type= 3
Dn Slope=0.005
Boundary for River Rch & Prof#=CCLC 069,Reach-1         , 3
Up Type= 0
Dn Type= 3
Dn Slope=0.005
Boundary for River Rch & Prof#=CCLC 069,Reach-1         , 4
Up Type= 0
Dn Type= 3
Dn Slope=0.005
Boundary for River Rch & Prof#=CCLC 069,Reach-1         , 5
Up Type= 0
Dn Type= 3
Dn Slope=0.005
Boundary for River Rch & Prof#=CCLC 069,Reach-1         , 6
Up Type= 0
Dn Type= 3
Dn Slope=0.005
Boundary for River Rch & Prof#=CCLC 069,Reach-1         , 7
Up Type= 0
Dn Type= 3
Dn Slope=0.005
DSS Import GetInterval= 0
DSS Import GetPeak= 0
DSS Import FillOption= 0

--- CCLC 069.f02 (steady flow) ---

Flow Title=Orig_BLE_Flows
Program Version=4.10
Number of Profiles= 7
Profile Names=10-year,25-year,50-year,1pct_min,100-year,1pct_plu,500-year
River Rch & RM=CCLC 069,Reach-1         ,4845
     719     971    1178     469    1415    4275    2043
Boundary for River Rch & Prof#=CCLC 069,Reach-1         , 1
Up Type= 0
Dn Type= 3
Dn Slope=0.005
Boundary for River Rch & Prof#=CCLC 069,Reach-1         , 2
Up Type= 0
Dn Type= 3
Dn Slope=0.005
Boundary for River Rch & Prof#=CCLC 069,Reach-1         , 3
Up Type= 0
Dn Type= 3
Dn Slope=0.005
Boundary for River Rch & Prof#=CCLC 069,Reach-1         , 4
Up Type= 0
Dn Type= 3
Dn Slope=0.005
Boundary for River Rch & Prof#=CCLC 069,Reach-1         , 5
Up Type= 0
Dn Type= 3
Dn Slope=0.005
Boundary for River Rch & Prof#=CCLC 069,Reach-1         , 6
Up Type= 0
Dn Type= 3
Dn Slope=0.005
Boundary for River Rch & Prof#=CCLC 069,Reach-1         , 7
Up Type= 0
Dn Type= 3
Dn Slope=0.005
DSS Import GetInterval= 0
DSS Import GetPeak= 0
DSS Import FillOption= 0

--- CCLC 069.g01 (geometry) ---

Geom Title=Existing Conditions
Program Version=4.10

River Reach=CCLC 069        ,Reach-1
Reach XY= 30
      3692873.23     10173421.84      3692958.23     10173396.84
      3693118.23     10173476.84      3693288.23     10173476.84
      3693348.23     10173546.84      3693468.23     10173616.84
      3693698.23     10173666.84      3693808.23     10173756.84
      3694018.36     10173834.88      3694059.83     10173915.83
      3694232.87     10173919.27      3694284.18     10173885.12
      3694379.16     10173875.67      3694430.19     10173907.18
      3694563.05     10173896.21      3694602.28     10173868.29
      3694662.37     10173895.31      3694958.17     10173876.77
      3695147.67      10173831.4      3695281.28     10173847.14
      3695346.87     10173826.67      3695487.91     10173856.98
      3695554.41     10173820.97      3695720.19     10173825.76
      3695853.87      10173770.2      3696072.62     10173813.61
       3696326.1     10173596.59      3696879.92     10173263.26
      3697136.86      10173082.7      3697173.62     10173030.51

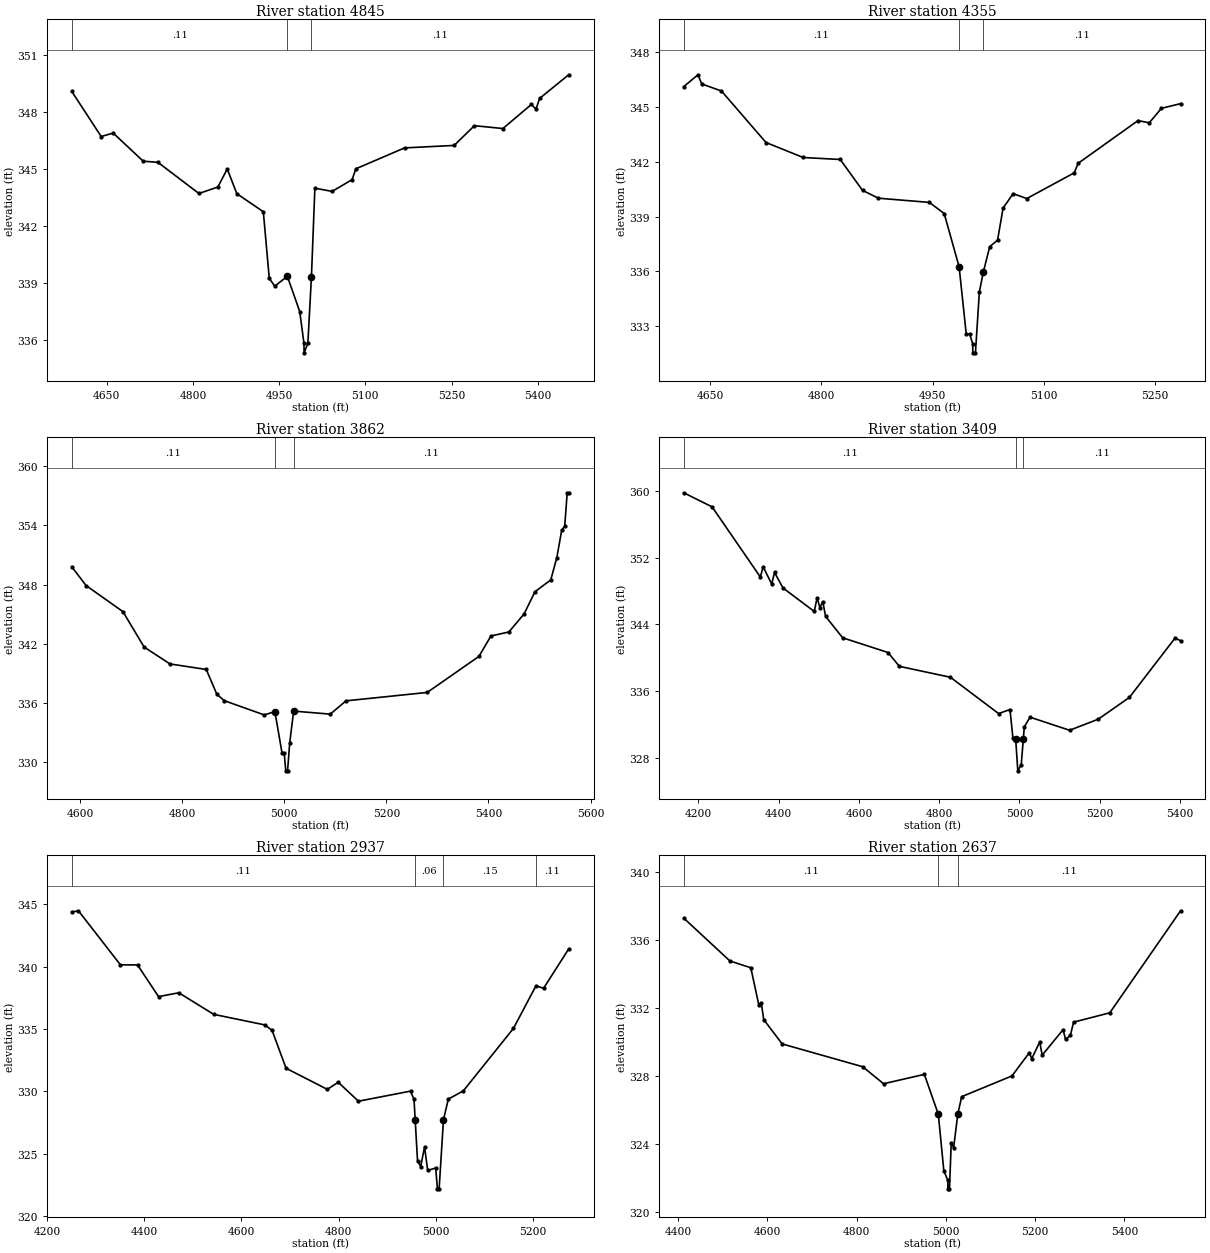
Type RM Length L Ch R = 1 ,4845    ,490,490,490
BEGIN DESCRIPTION:
CCLC 069 10.0
END DESCRIPTION:
XS GIS Cut Line= 4
      3692839.74     10173789.98      3692958.23     10173396.84
      3692980.36     10173339.14      3692675.62     10173092.74
#Sta/Elev= 30
  4589.4  349.09  4640.5  346.72  4661.4   346.9  4713.6  345.42  4739.2  345.36
  4810.5  343.72  4843.4  344.06  4859.8  345.01  4876.4  343.71  4922.5  342.76
  4932.9  339.25  4942.4  338.84  4964.3  339.36  4985.9   337.5  4993.2  335.83
  4993.4  335.33    5000  335.83  5006.2  339.31  5012.2     344  5042.2  343.83
    5077  344.45  5083.5  345.02  5168.2  346.12  5254.5  346.25  5289.7  347.29
  5339.3  347.14  5388.9  348.41  5396.8  348.16  5403.3  348.73  5453.7  349.97
#Mann= 3 , 0 , 0
  4589.4     .11       0  4964.3     .06       0  5006.2     .11       0
Bank Sta=4964.3,5006.2
XS Rating Curve= 0 ,0
Exp/Cntr=0.3,0.1

Type RM Length L Ch R = 1 ,4355    ,493,493,493
BEGIN DESCRIPTION:
CCLC 069 9.0
END DESCRIPTION:
XS GIS Cut Line= 3
       3693351.9      10173941.9      3693368.23     10173556.84
      3693456.08     10173286.46
#Sta/Elev= 30
  4614.6  346.12  4633.8  346.77  4638.8  346.27  4665.5  345.88  4725.5  343.06
  4775.6  342.24  4825.6  342.13  4855.6  340.44  4876.9  340.01  4945.7  339.78
  4965.7  339.17  4985.8  336.25  4995.4  332.57    5000  332.57  5004.1  332.04
  5004.3  331.54  5007.8  331.54  5013.1  334.88  5018.4  335.96  5027.1  337.36
  5037.6  337.71  5045.1  339.47  5058.6  340.26    5077  339.99    5141   341.4
  5146.2  341.92  5226.9  344.26  5242.1  344.14  5258.4  344.93  5284.3  345.19
#Mann= 3 , 0 , 0
  4614.6     .11       0  4985.8     .06       0  5018.4     .11       0
Bank Sta=4985.8,5018.4
XS Rating Curve= 0 ,0
Exp/Cntr=0.3,0.1

Type RM Length L Ch R = 1 ,3862    ,453,453,453
BEGIN DESCRIPTION:
CCLC 069 8.0
END DESCRIPTION:
XS GIS Cut Line= 3
      3693517.87     10174061.04      3693778.23     10173736.84
      3694067.86     10173261.07
#Sta/Elev= 30
  4584.2   349.8  4612.2   347.9  4684.2  345.26  4725.8  341.66  4776.5  339.95
  4847.4  339.39  4868.2  336.87  4882.6  336.23    4961  334.78  4981.8  335.12
  4995.7  330.94    5000  330.94  5003.1  329.11  5006.6  329.11  5010.8  331.93
  5018.5  335.17  5090.2  334.86  5121.1  336.21    5280  337.06  5381.4  340.72
  5404.8  342.79  5439.9  343.19  5469.8  345.03  5491.1  347.28  5521.9  348.47
  5533.8  350.73  5543.4  353.52  5549.3  353.94  5554.1  357.31    5557  357.31
#Mann= 3 , 0 , 0
  4584.2     .11       0  4981.8     .06       0  5018.5     .11       0
Bank Sta=4981.8,5018.5
XS Rating Curve= 0 ,0
Exp/Cntr=0.3,0.1

Type RM Length L Ch R = 1 ,3409    ,472,472,472
BEGIN DESCRIPTION:
CCLC 069 7.0
END DESCRIPTION:
XS GIS Cut Line= 3
      3693567.82     10174511.11      3694152.78     10173912.87
      3694417.87     10173611.06
#Sta/Elev= 30
  4163.3  359.79    4234   358.1  4354.3  349.68  4361.3  350.91  4382.6  348.83
  4389.6  350.23  4410.9  348.36  4488.6  345.55  4495.8  347.19  4502.7  346.02
  4509.9  346.71  4516.9  344.96  4559.3  342.39  4672.5  340.62  4700.8  338.96
  4828.1  337.65  4948.2  333.29  4976.5  333.78  4983.7  330.42  4990.7  330.24
    4996  326.42  5004.6  327.18 5009.75 330.236  5012.2  331.69  5026.4  332.86
  5125.1  331.29  5196.2  332.61  5274.1  335.23  5387.9  342.35  5401.7  342.04
#Mann= 3 , 0 , 0
  4163.3     .11       0  4990.7     .06       0 5009.75     .11       0
Bank Sta=4990.7,5009.75
XS Rating Curve= 0 ,0
Exp/Cntr=0.3,0.1

Type RM Length L Ch R = 1 ,2937    ,300,300,300
BEGIN DESCRIPTION:
CCLC 069 6.0
END DESCRIPTION:
XS GIS Cut Line= 3
      3694117.86     10174461.06      3694585.64     10173876.22
      3694517.85     10173611.05
#Sta/Elev= 30
  4251.1  344.37  4264.7  344.47  4351.1  340.14  4386.4  340.13  4429.6  337.59
  4471.2   337.9  4543.2  336.17  4648.9  335.32  4663.3  334.88  4692.1  331.85
    4777  330.16  4799.4  330.73    4841  329.21  4948.2  330.02  4955.4  329.35
 4957.77327.7403  4962.6  324.46  4969.1  323.97  4977.1  325.55  4983.5  323.66
    5000  323.86  5003.6  322.19  5007.1  322.19    5016  327.73    5026  329.38
  5056.9  330.04  5160.1  335.05  5206.4  338.46  5222.1  338.26  5273.7  341.41
#Mann= 4 ,-1 , 0
  4251.1     .11       0 4957.77     .06       0    5016     .15       0
  5206.4     .11       0
Bank Sta=4957.77,5016
XS Rating Curve= 0 ,0
Exp/Cntr=0.3,0.1

Type RM Length L Ch R = 1 ,2637    ,145,145,145
BEGIN DESCRIPTION:
Mapping XS 54d046c2
END DESCRIPTION:
XS GIS Cut Line= 2
      3694633.58     10174415.46      3695077.88     10173394.66
#Sta/Elev= 30
  4412.5  337.29  4515.9  334.77  4562.8  334.37  4580.7  332.19  4586.2  332.32
  4591.8  331.32  4633.1  329.89  4813.5  328.55  4860.3  327.55  4951.7   328.1
    4983  325.75  4995.3  322.44  5004.2  321.87  5004.5  321.37    5008  321.37
  5011.9  324.08  5017.3  323.79 5026.69325.7731  5035.3  326.79    5148  328.01
  5186.8  329.37  5192.3  329.02  5210.2  330.01  5215.7  329.23  5262.6  330.73
    5268  330.16  5278.9  330.39    5286  331.17  5367.2  331.72  5525.8  337.72
#Mann= 3 , 0 , 0
  4412.5     .11       0    4983     .09       0 5026.69     .11       0
Bank Sta=4983,5026.69
XS Rating Curve= 0 ,0
Exp/Cntr=0.3,0.1

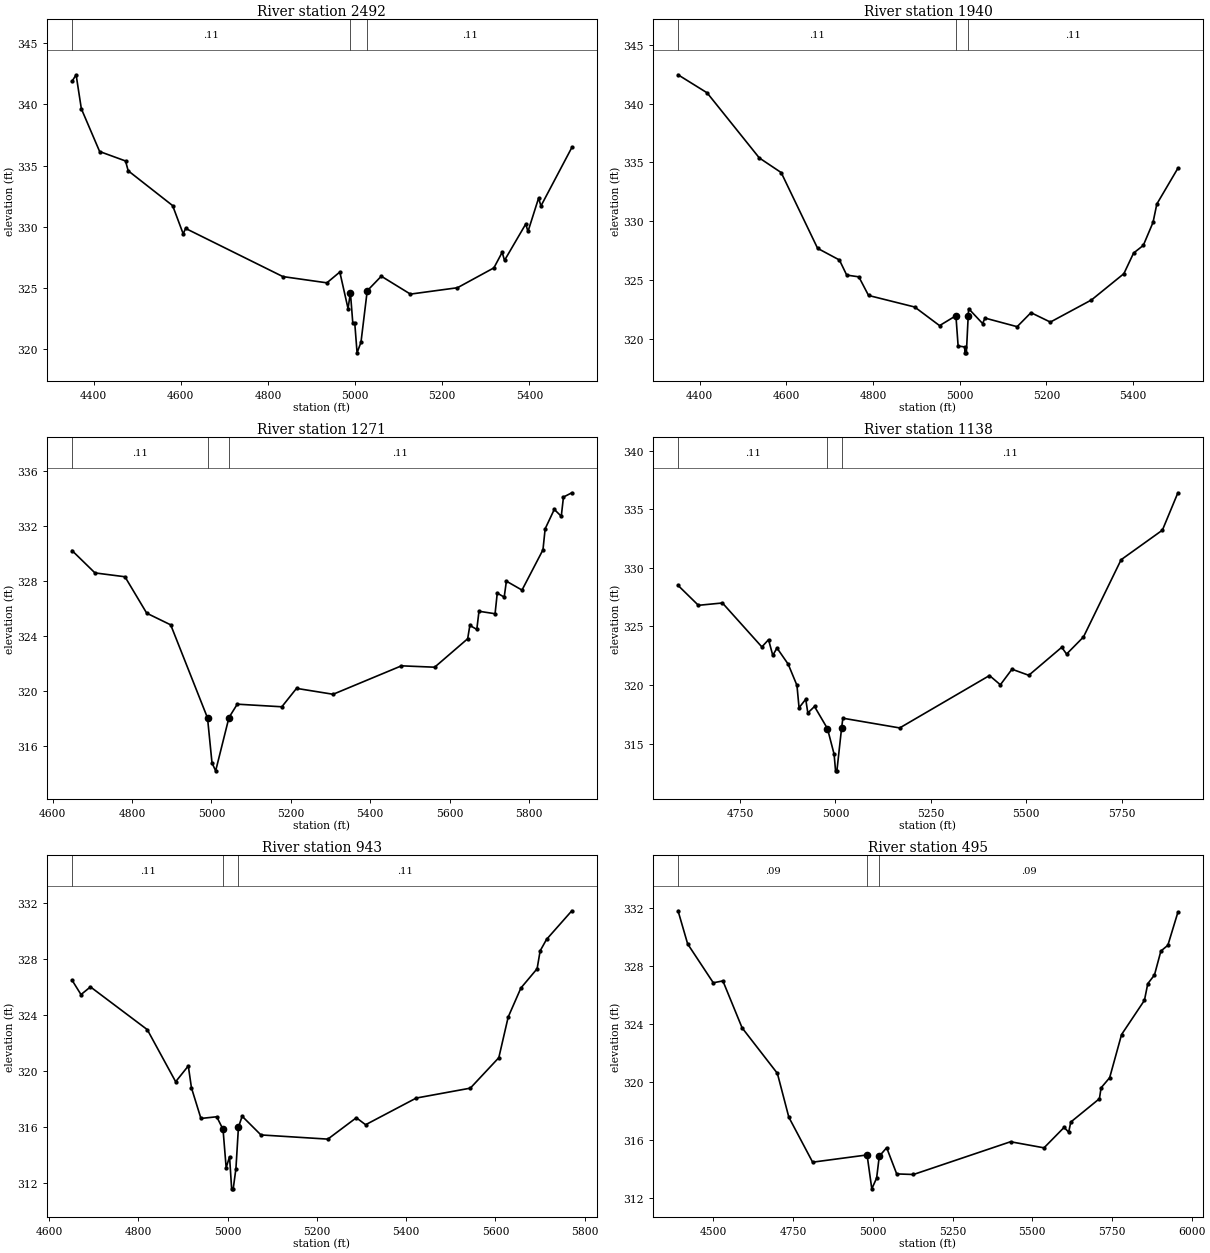
Type RM Length L Ch R = 1 ,2492    ,552,552,552
BEGIN DESCRIPTION:
CCLC 069 5.0
END DESCRIPTION:
XS GIS Cut Line= 3
      3694767.86     10174461.05      3695006.86     10173857.69
      3695190.78     10173394.65
#Sta/Elev= 30
  4350.4  341.86  4359.9   342.4  4371.9  339.63  4413.9  336.14  4473.3  335.37
  4479.4  334.57  4581.4  331.73  4605.7  329.42  4611.1  329.87  4834.4  325.94
  4935.4  325.43  4965.1  326.31    4984  323.33  4989.4  324.63  4994.9  322.15
  4999.4  322.15  5004.7  319.72  5013.7  320.59    5028  324.78  5060.3  325.97
  5127.1  324.51  5235.1  325.03  5318.7  326.65  5337.7  327.92  5343.1  327.26
  5391.7  330.22    5397  329.62  5421.3  332.34  5426.7   331.7  5497.6  336.47
#Mann= 3 , 0 , 0
  4350.4     .11       0  4989.4     .06       0    5028     .11       0
Bank Sta=4989.4,5028
XS Rating Curve= 0 ,0
Exp/Cntr=0.3,0.1

Type RM Length L Ch R = 1 ,1940    ,669,669,669
BEGIN DESCRIPTION:
CCLC 069 4.0
END DESCRIPTION:
XS GIS Cut Line= 3
      3695817.85     10174411.06      3695528.31     10173829.33
      3695302.54     10173379.73
#Sta/Elev= 30
  4350.2  342.44  4417.2  340.91  4537.7  335.38  4588.1  334.14  4672.1  327.71
  4722.4  326.72  4739.2  325.44  4767.2  325.29  4789.6  323.71    4896  322.73
  4953.4  321.15  4991.1  321.99  4996.2  319.42  5011.5  319.34  5011.7  318.84
  5015.2  318.84 5019.45321.9601  5020.4  322.59  5052.6  321.33  5058.2  321.79
  5132.3  321.06  5164.2  322.25  5208.9  321.45  5303.8  323.33  5378.5  325.56
  5400.9  327.31  5423.3  327.96  5445.7  329.91  5454.5  331.47  5503.1  334.51
#Mann= 3 , 0 , 0
  4350.2     .11       0  4991.1     .06       0 5019.45     .11       0
Bank Sta=4991.1,5019.45
XS Rating Curve= 0 ,0
Exp/Cntr=0.3,0.1

Type RM Length L Ch R = 1 ,1271    ,133,133,133
BEGIN DESCRIPTION:
CCLC 069 3.0
END DESCRIPTION:
XS GIS Cut Line= 3
      3696469.49     10173888.06      3696083.25     10173714.46
      3695323.71     10173367.25
#Sta/Elev= 30
  4648.9  330.25  4706.8  328.62  4782.3  328.34  4837.1  325.69  4897.5  324.84
  4990.2  318.07  5001.5  314.79  5010.7  314.22 5044.19 318.098  5065.1  319.07
  5177.3  318.88  5214.3  320.22  5306.4  319.79  5478.5  321.86  5562.1  321.76
  5645.2  323.83  5650.7   324.8  5668.2  324.51  5673.7  325.83  5714.2  325.65
  5719.7  327.15  5737.2  326.86  5742.7  328.02    5782  327.37  5834.8   330.3
  5840.3  331.83  5863.3  333.24  5880.9  332.74  5886.4  334.14  5907.5  334.45
#Mann= 3 ,-1 , 0
  4648.9     .11       0  4990.2     .07       0 5044.19     .11       0
Bank Sta=4990.2,5044.19
XS Rating Curve= 0 ,0
Exp/Cntr=0.3,0.1

Type RM Length L Ch R = 1 ,1138    ,195,195,195
BEGIN DESCRIPTION:
Mapping XS 380bfe07
END DESCRIPTION:
XS GIS Cut Line= 2
      3696623.64     10173827.32      3695432.53     10173280.58
#Sta/Elev= 30
  4587.2   328.5  4640.6   326.8  4703.6     327    4807  323.25  4824.5  323.87
  4835.6  322.53  4846.6  323.16    4876  321.78    4899  319.97  4904.5  318.06
    4922  318.79  4927.5  317.62    4945  318.17    4979  316.28  4996.4   314.1
  5000.2  312.68  5003.7  312.68 5015.97316.3192  5019.4  317.17  5168.4  316.34
  5403.8  320.81  5432.3  320.02  5462.8  321.35  5506.8  320.83  5593.2  323.22
  5605.9  322.64  5650.2   324.1  5748.9  330.69  5857.1  333.21  5897.8   336.4
#Mann= 3 ,-1 , 0
  4587.2     .11       0    4979     .06       0 5015.97     .11       0
Bank Sta=4979,5015.97
XS Rating Curve= 0 ,0
Exp/Cntr=0.3,0.1

Type RM Length L Ch R = 1 ,943     ,448,448,448
BEGIN DESCRIPTION:
CCLC 069 2.0
END DESCRIPTION:
XS GIS Cut Line= 3
      3696660.53     10173796.95       3696412.9     10173551.45
      3695817.83     10173061.06
#Sta/Elev= 30
  4651.3   326.5  4671.5  325.46  4692.7  326.01    4820  322.95  4883.6  319.22
  4911.9  320.35    4919  318.78  4940.2  316.59  4975.6  316.71  4989.7  315.81
  4996.7  313.06  5004.3  313.85    5009  311.55  5012.5  311.55  5018.6     313
 5024.21315.9603  5032.5  316.75  5074.6  315.41  5224.5  315.11  5288.3  316.64
  5309.1  316.14  5422.5  318.05  5543.7  318.76  5607.5  320.94  5628.5  323.85
    5657  325.93  5693.3  327.31  5700.1  328.59  5714.4  329.41  5771.1  331.46
#Mann= 3 , 0 , 0
  4651.3     .11       0  4989.7     .06       0 5024.21     .11       0
Bank Sta=4989.7,5024.21
XS Rating Curve= 0 ,0
Exp/Cntr=0.3,0.1

Type RM Length L Ch R = 1 ,495     ,339,339,339
BEGIN DESCRIPTION:
CCLC 069 1.0
END DESCRIPTION:
XS GIS Cut Line= 3
      3696717.85      10173911.1      3696779.22     10173303.19
      3695867.89     10173011.08
#Sta/Elev= 30
    4389   331.8  4419.2  329.51  4499.6  326.83  4529.7  326.96    4590  323.72
  4700.6  320.58  4736.6  317.55  4811.2  314.45    4982  314.95  4996.8  312.61
  5011.9  313.35  5020.3  314.86  5043.4  315.45  5074.9  313.64  5127.5   313.6
    5432  315.86    5537  315.44    5600  316.85  5614.4  316.52    5621  317.22
  5710.8  318.83    5716  319.58  5742.9  320.28  5780.3  323.26    5852  325.62
  5862.5  326.77  5883.5  327.37  5903.6  329.02  5925.5  329.42    5957   331.7
#Mann= 3 , 0 , 0
    4389     .09       0    4982     .06       0  5020.3     .09       0
Bank Sta=4982,5020.3
XS Rating Curve= 0 ,0
Exp/Cntr=0.3,0.1

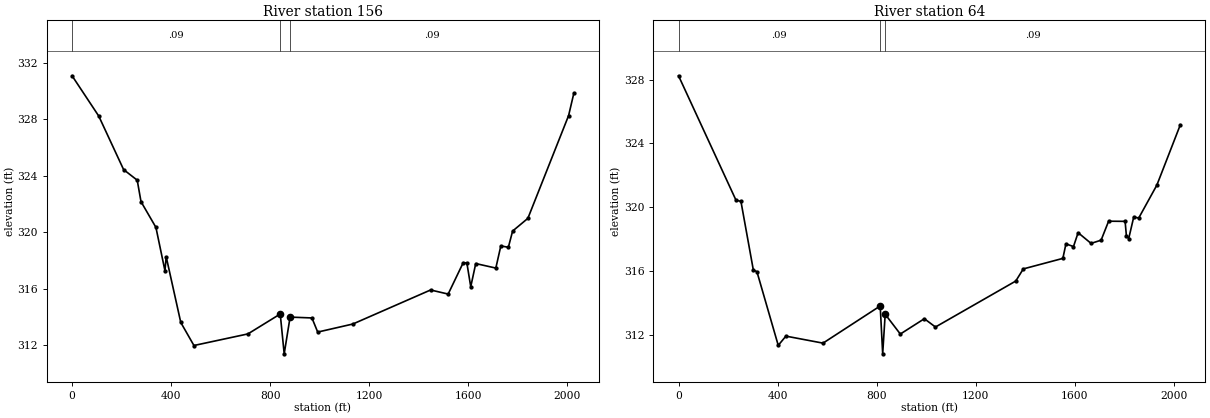
Type RM Length L Ch R = 1 ,156     ,92,92,92
BEGIN DESCRIPTION:
CCLC 069 0.5
END DESCRIPTION:
XS GIS Cut Line= 3
        3697136.     10173978.38      3697060.48     10173124.21
      3695906.83     10172936.71
#Sta/Elev= 30
       0  331.07   107.7  328.22   208.1  324.43   263.1  323.68   278.4  322.16
   338.6  320.34   375.1  317.27   380.1  318.26     439  313.61   492.1  311.98
   710.1   312.8   840.6  314.21   856.6  311.39   880.4  313.99   968.6  313.93
   991.9  312.93  1133.7   313.5  1447.8  315.91  1518.7  315.62  1579.5  317.84
  1594.3  317.82  1609.9  316.14  1630.1  317.78  1711.2  317.46  1731.4  319.03
  1761.8  318.93    1779  320.08  1840.6  320.98    2005  328.25  2026.3  329.84
#Mann= 3 , 0 , 0
       0     .09       0   840.6     .06       0   880.4     .09       0
Bank Sta=840.6,880.4
XS Rating Curve= 0 ,0
Exp/Cntr=0.3,0.1

Type RM Length L Ch R = 1 ,64      ,0,0,0
XS GIS Cut Line= 3
      3697210.65     10173901.99      3697135.13     10173047.82
      3695981.49     10172860.32
#Sta/Elev= 30
       0  328.24   231.8  320.45   251.9  320.37   302.1  316.06   316.4  315.97
   402.5  311.35   433.4  311.93   583.2  311.49   814.1  313.82   824.1  310.82
   834.2   313.3   895.3  312.06   992.3  313.02  1037.1   312.5  1361.3  315.38
  1391.7  316.14  1551.4   316.8  1563.9  317.71  1594.3  317.54    1613  318.41
  1665.2  317.74  1705.8  317.94  1736.1  319.13  1802.7  319.12  1807.8  318.23
  1817.2  318.04  1837.5  319.39  1857.7  319.33  1930.9  321.39  2025.6  325.17
#Mann= 3 , 0 , 0
       0     .09       0   814.1     .06       0   834.2     .09       0
Bank Sta=814.1,834.2
XS Rating Curve= 0 ,0
Exp/Cntr=0.3,0.1

Chan Stop Cuts=-1
Use User Specified Reach Order=0
Composite Channel Slope=5