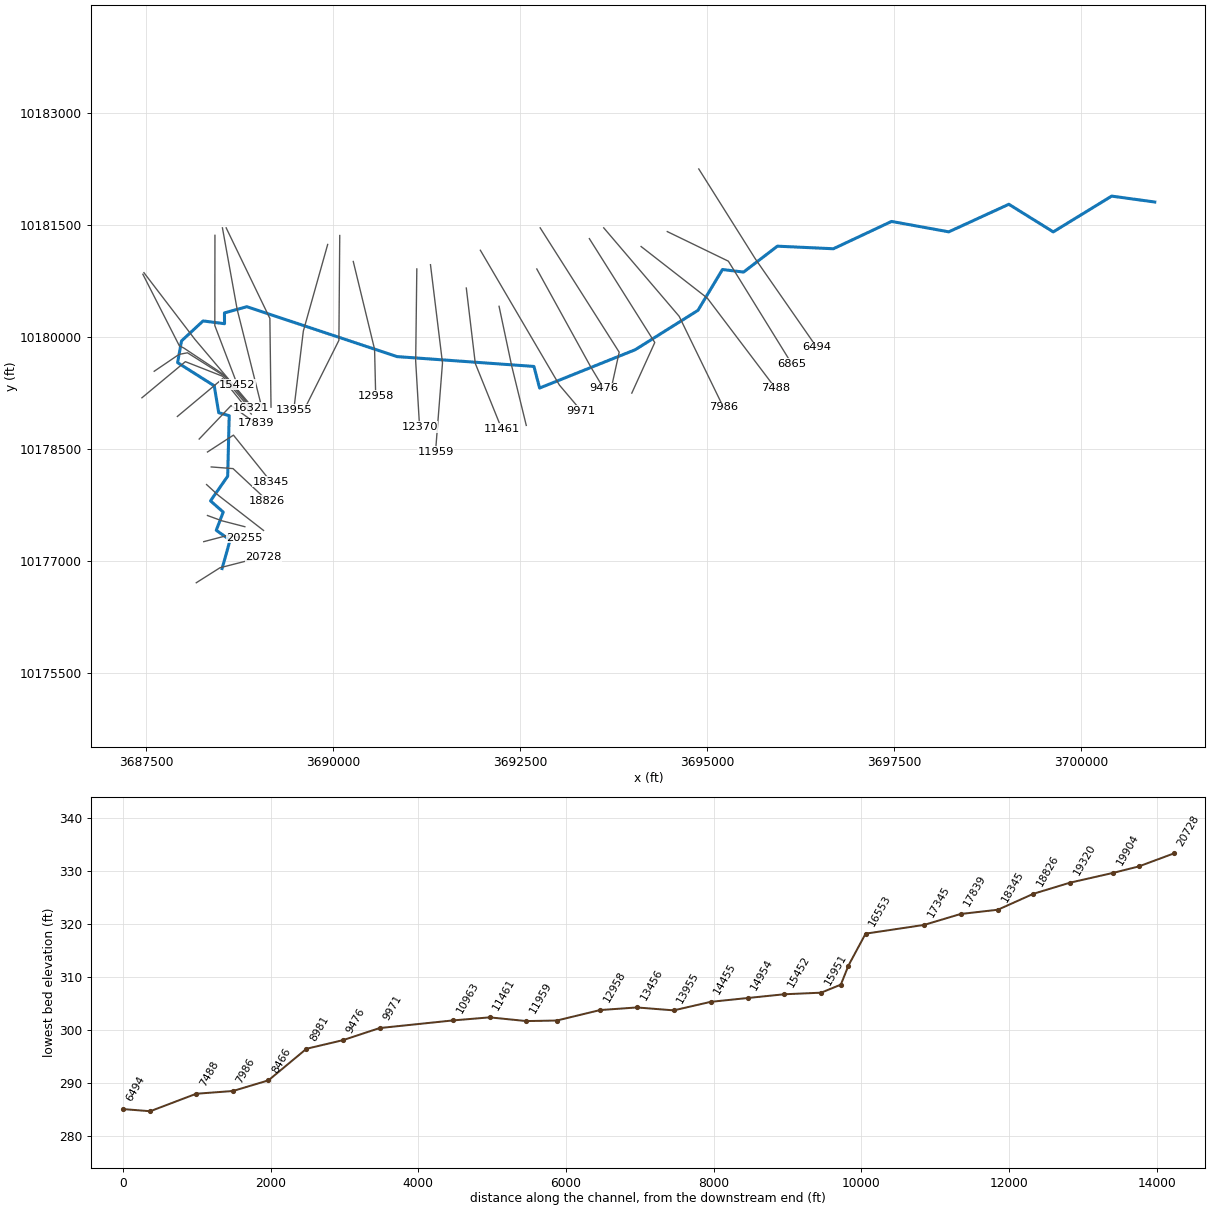
--- CCLC 070.prj (project) ---

Proj Title=CCLC 070 Base Level Engineering
Current Plan=p01
Default Exp/Contr=0.3,0.1
English Units
Geom File=g01
Flow File=f01
Flow File=f02
Plan File=p01
Y Axis Title=Elevation
X Axis Title(PF)=Main Channel Distance
X Axis Title(XS)=Station
BEGIN DESCRIPTION:
CCLC 070
END DESCRIPTION:
DSS Export Rating Curves= 0
DSS Export Rating Curve Sorted= 0
DSS Export Volume Flow Curves= 0
DXF OffsetX= 0
DXF OffsetY= 0
DXF ScaleX= 1
DXF ScaleY= 10

--- CCLC 070.p01 (plan) ---

Plan Title=Multiple Run
Short Identifier=Multiple
Geom File=g01
Flow File=f01
Subcritical Flow
K Sum by GR= 0
Std Step Tol= 0.01
Critical Tol= 0.01
Num of Std Step Trials= 20
Max Error Tol= 0.3
Flow Tol Ratio= 0.001
Split Flow NTrial= 30
Split Flow Tol= 0.02
Split Flow Ratio= 0.02
Log Output Level= 0
Friction Slope Method= 1
Unsteady Friction Slope Method= 2
Unsteady Bridges Friction Slope Method= 1
Parabolic Critical Depth
Global Vel Dist=  1 , 1 , 1
Global Log Level= 0
CheckData=True
Encroach Param= -1, 0, 0, 0
BEGIN DESCRIPTION:
Multiple Run
END DESCRIPTION:

--- CCLC 070.f01 (steady flow) ---

Flow Title=Multiple
Program Version=4.10
Number of Profiles= 7
Profile Names=10-year,25-year,50-year,1pct_min,100-year,1pct_plu,500-year
River Rch & RM=CCLC 070,Reach-1         ,20728
     486     652     875     387    1169    3530    2157
River Rch & RM=CCLC 070,Reach-1         ,16321
    2010    2888    4057    1867    5637   17023   11273
River Rch & RM=CCLC 070,Reach-1         ,12958
    2089    2994    4199    1927    5820   17576   11586
River Rch & RM=CCLC 070,Reach-1         ,8466
    2279    3277    4607    2120    6401   19331   12802
River Rch & RM=CCLC 070,Reach-1         ,4504
    2381    3424    4813    2214    6685   20188   13358
Boundary for River Rch & Prof#=CCLC 070,Reach-1         , 1
Up Type= 0
Dn Type= 3
Dn Slope=0.005
Boundary for River Rch & Prof#=CCLC 070,Reach-1         , 2
Up Type= 0
Dn Type= 3
Dn Slope=0.005
Boundary for River Rch & Prof#=CCLC 070,Reach-1         , 3
Up Type= 0
Dn Type= 3
Dn Slope=0.005
Boundary for River Rch & Prof#=CCLC 070,Reach-1         , 4
Up Type= 0
Dn Type= 3
Dn Slope=0.005
Boundary for River Rch & Prof#=CCLC 070,Reach-1         , 5
Up Type= 0
Dn Type= 3
Dn Slope=0.005
Boundary for River Rch & Prof#=CCLC 070,Reach-1         , 6
Up Type= 0
Dn Type= 3
Dn Slope=0.005
Boundary for River Rch & Prof#=CCLC 070,Reach-1         , 7
Up Type= 0
Dn Type= 3
Dn Slope=0.005
DSS Import GetInterval= 0
DSS Import GetPeak= 0
DSS Import FillOption= 0

--- CCLC 070.f02 (steady flow) ---

Flow Title=Orig_BLE_Flows
Program Version=4.10
Number of Profiles= 7
Profile Names=10-year,25-year,50-year,1pct_min,100-year,1pct_plu,500-year
River Rch & RM=CCLC 070,Reach-1         ,20728
     486     639     761     298     899    2716    1254
River Rch & RM=CCLC 070,Reach-1         ,16321
    2010    2831    3528    1436    4336   13093    6554
River Rch & RM=CCLC 070,Reach-1         ,12958
    2089    2935    3651    1482    4477   13519    6736
River Rch & RM=CCLC 070,Reach-1         ,8466
    2279    3213    4006    1630    4924   14869    7443
River Rch & RM=CCLC 070,Reach-1         ,4504
    2381    3357    4185    1703    5142   15527    7766
Boundary for River Rch & Prof#=CCLC 070,Reach-1         , 1
Up Type= 0
Dn Type= 3
Dn Slope=0.005
Boundary for River Rch & Prof#=CCLC 070,Reach-1         , 2
Up Type= 0
Dn Type= 3
Dn Slope=0.005
Boundary for River Rch & Prof#=CCLC 070,Reach-1         , 3
Up Type= 0
Dn Type= 3
Dn Slope=0.005
Boundary for River Rch & Prof#=CCLC 070,Reach-1         , 4
Up Type= 0
Dn Type= 3
Dn Slope=0.005
Boundary for River Rch & Prof#=CCLC 070,Reach-1         , 5
Up Type= 0
Dn Type= 3
Dn Slope=0.005
Boundary for River Rch & Prof#=CCLC 070,Reach-1         , 6
Up Type= 0
Dn Type= 3
Dn Slope=0.005
Boundary for River Rch & Prof#=CCLC 070,Reach-1         , 7
Up Type= 0
Dn Type= 3
Dn Slope=0.005
DSS Import GetInterval= 0
DSS Import GetPeak= 0
DSS Import FillOption= 0

--- CCLC 070.g01 (geometry) ---

Geom Title=Existing Conditions
Program Version=4.10

River Reach=CCLC 070        ,Reach-1
Reach XY= 30
      3688513.31     10176901.04      3688620.28     10177282.42
      3688435.34     10177413.17      3688528.23     10177656.84
      3688358.23     10177806.84      3688588.23     10178136.84
      3688608.23     10178946.84      3688468.23     10178986.84
      3688408.23     10179346.84      3687918.23     10179656.84
      3687970.78     10179947.73      3688259.01     10180215.12
      3688545.81      10180178.2      3688545.15     10180322.82
      3688843.98     10180405.84      3690852.53     10179737.85
      3692684.08     10179606.25       3692760.2     10179317.22
      3694039.58     10179830.08      3694878.23     10180356.84
      3695205.87     10180903.39      3695488.24      10180869.1
      3695940.83     10181215.73      3696689.42     10181181.26
      3697467.29     10181546.75      3698232.98     10181407.61
      3699036.48     10181776.64      3699630.22     10181406.97
      3700411.59     10181885.73      3700988.23     10181806.84

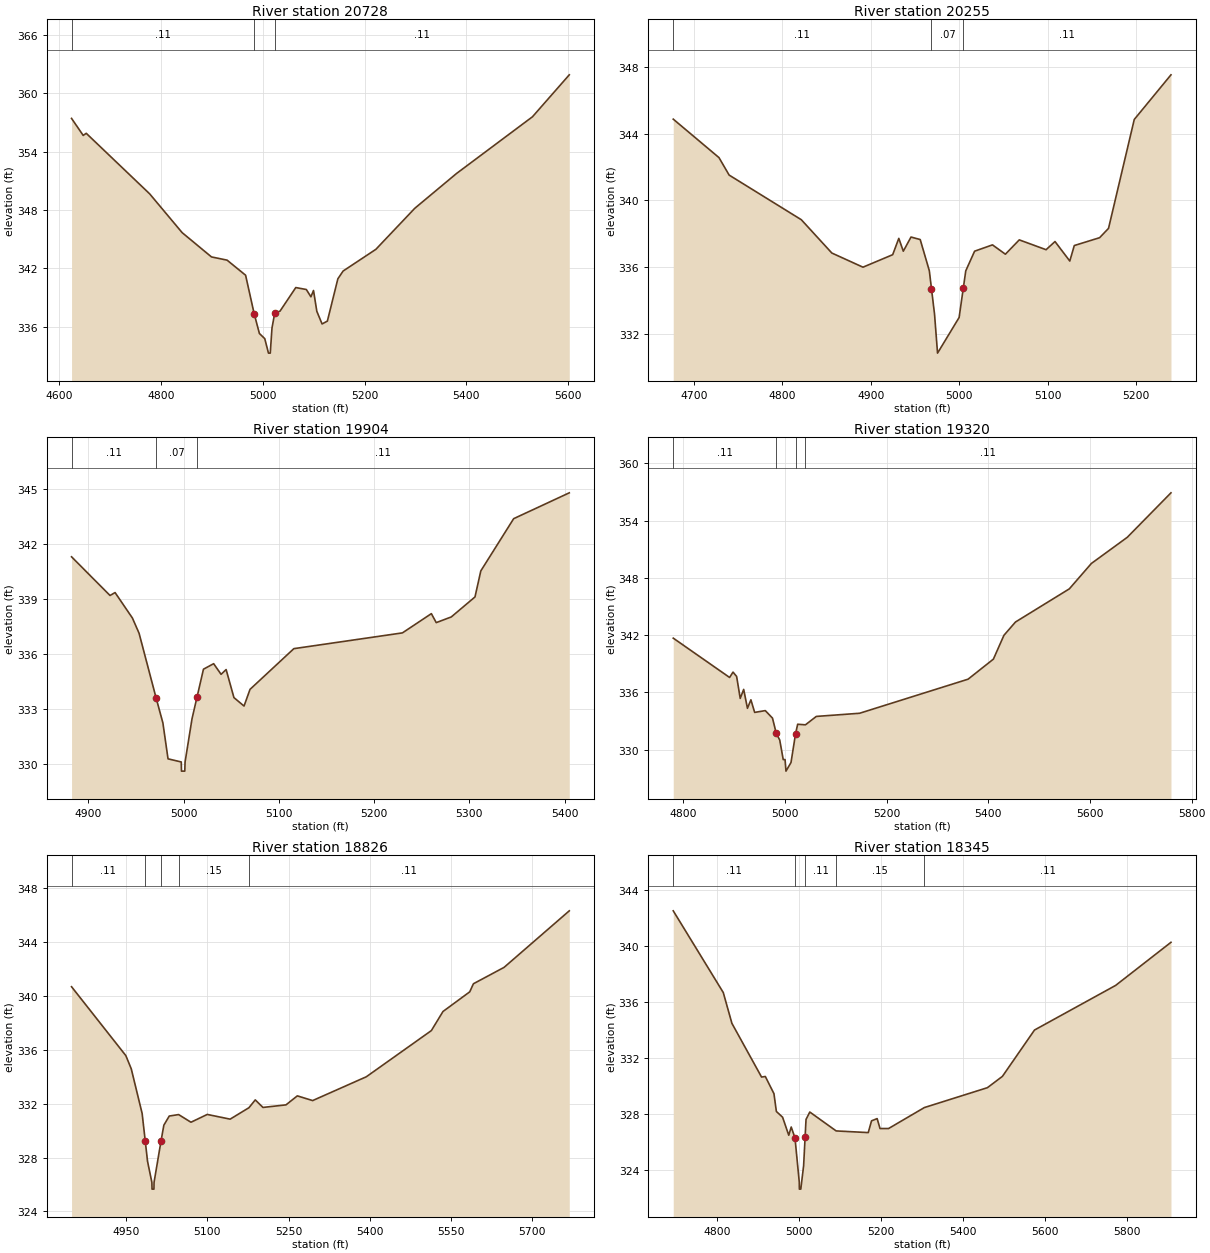
Type RM Length L Ch R = 1 ,20728   ,473,473,473
BEGIN DESCRIPTION:
CCLC 070 30.0
END DESCRIPTION:
XS GIS Cut Line= 3
      3688167.86     10176711.08      3688484.76     10176911.58
       3689067.8     10177061.06
#Sta/Elev= 30
    4625  357.41  4647.9  355.66  4653.8  355.88  4778.4  349.65    4842  345.67
  4899.6  343.17  4930.2  342.84  4966.6  341.29 4983.42337.3301  4993.7   335.3
  5004.2  334.77  5011.5  333.28    5015  333.28  5018.4  335.86  5023.8   337.4
  5034.2   337.6  5065.1  340.02  5085.8  339.82  5094.8  339.07  5099.9  339.72
  5106.4  337.58  5116.7  336.28  5127.1  336.57  5147.7  340.92    5158  341.72
  5222.3  343.95  5298.7  348.17  5380.2  351.73  5529.7  357.58  5601.9  361.89
#Mann= 3 , 0 , 0
    4625     .11       0 4983.42     .07       0  5023.8     .11       0
Bank Sta=4983.42,5023.8
XS Rating Curve= 0 ,0
Exp/Cntr=0.3,0.1

Type RM Length L Ch R = 1 ,20255   ,351,351,351
BEGIN DESCRIPTION:
CCLC 070 29.0
END DESCRIPTION:
XS GIS Cut Line= 3
       3688267.8     10177261.06      3688580.46     10177342.94
      3688817.83     10177311.07
#Sta/Elev= 30
  4676.8  344.88  4728.5  342.57    4740  341.52  4821.6  338.84  4856.1  336.84
  4891.3  335.99  4924.9  336.74  4931.8  337.72  4936.9  336.95  4945.6   337.8
    4956  337.65  4966.3  335.78 4968.72334.7094  4972.2  333.17  4975.6  330.83
    5000  332.97 5004.75334.7433  5007.5  335.77  5017.5  336.95  5037.7  337.33
  5052.3  336.77    5068  337.63  5098.3  337.04  5108.4  337.53  5125.1  336.36
  5130.2  337.29  5158.8  337.76  5168.9  338.32    5198  344.86  5239.5  347.54
#Mann= 3 ,-1 , 0
  4676.8     .11       0 4968.72     .07       0 5004.75     .11       0
Bank Sta=4968.72,5004.75
XS Rating Curve= 0 ,0
Exp/Cntr=0.3,0.1

Type RM Length L Ch R = 1 ,19904   ,584,584,584
BEGIN DESCRIPTION:
CCLC 070 28.0
END DESCRIPTION:
XS GIS Cut Line= 3
      3688317.85     10177611.07      3688508.93     10177540.85
      3688817.82     10177461.08
#Sta/Elev= 30
  4882.4  341.29  4922.8  339.18  4928.1  339.34  4946.3  337.95  4953.3  337.12
 4971.14333.6002  4978.3  332.23  4983.7  330.27  4997.6   330.1  4997.8   329.6
  5001.3   329.6  5001.6   330.1  5008.9  332.46 5014.15333.6412  5020.9  335.16
  5031.6  335.46  5039.4  334.88  5044.7  335.14  5052.9  333.61  5063.5  333.15
  5069.8  334.06  5115.8  336.28  5229.8  337.14  5260.2  338.19  5265.3   337.7
  5281.1  338.01    5306   339.1  5312.1  340.52  5346.6  343.37    5405  344.78
#Mann= 3 ,-1 , 0
  4882.4     .11       0 4971.14     .07       0 5014.15     .11       0
Bank Sta=4971.14,5014.15
XS Rating Curve= 0 ,0
Exp/Cntr=0.3,0.1

Type RM Length L Ch R = 1 ,19320   ,494,494,494
BEGIN DESCRIPTION:
CCLC 070 27.0
END DESCRIPTION:
XS GIS Cut Line= 3
       3688305.8     10178025.22      3688468.23     10177876.84
      3689067.88     10177411.05
#Sta/Elev= 30
    4780  341.68  4890.9  337.56  4897.6  338.12  4904.7  337.67  4911.8  335.37
  4918.6  336.31    4926  334.33  4932.8  335.22  4940.2   333.9  4961.1  334.09
  4975.3   333.3  4982.7   331.7  4989.5  331.01  4996.4  328.96    5000  328.96
  5001.8  327.75  5011.7  328.65  5020.7  331.67  5024.8  332.66  5040.1   332.6
  5061.5  333.48  5146.6  333.81  5360.1  337.38  5409.9  339.48  5430.7  341.98
  5453.4  343.37  5559.3  346.84  5602.7   349.5  5673.3  352.24  5759.3   356.9
#Mann= 4 ,-1 , 0
    4780     .11       0  4982.7     .07       0  5020.7     .17       0
  5040.1     .11       0
Bank Sta=4982.7,5020.7
XS Rating Curve= 0 ,0
Exp/Cntr=0.3,0.1

Type RM Length L Ch R = 1 ,18826   ,481,481,481
BEGIN DESCRIPTION:
CCLC 070 26.0
END DESCRIPTION:
XS GIS Cut Line= 3
      3688367.87     10178261.07      3688659.97     10178238.76
      3689117.84     10177811.08
#Sta/Elev= 30
  4849.2   340.7  4949.5  335.58  4959.5   334.6  4979.6  331.28 4985.35 329.233
  4989.6  327.72  4997.6  326.16  4997.9  325.66  5001.4  325.66  5001.6  326.16
 5014.57329.2519  5019.7  330.41  5029.7  331.09    5047   331.2  5069.8  330.63
  5099.9  331.21  5142.2  330.86  5176.9  331.71  5188.6  332.29  5202.8  331.73
  5245.3  331.92  5266.3  332.59  5294.6  332.24  5393.8  334.01  5513.9  337.44
  5535.4  338.86  5584.8  340.32  5591.6  340.92  5648.3  342.14  5768.7  346.34
#Mann= 5 ,-1 , 0
  4849.2     .11       0 4985.35     .06       0 5014.57     .11       0
    5047     .15       0  5176.9     .11       0
Bank Sta=4985.35,5014.57
XS Rating Curve= 0 ,0
Exp/Cntr=0.3,0.1

Type RM Length L Ch R = 1 ,18345   ,506,506,506
BEGIN DESCRIPTION:
CCLC 070 25.0
END DESCRIPTION:
XS GIS Cut Line= 3
      3688317.82     10178461.05      3688665.18     10178686.68
      3689167.82     10178061.11
#Sta/Elev= 30
  4691.9  342.54  4814.2   336.7  4835.3   334.5  4907.8  330.66    4917   330.7
  4938.1  329.47    4944   328.2  4959.2  327.79  4974.3   326.5  4980.3  327.09
  4989.5  326.31    5000  323.15  5000.2  322.65  5003.7  322.65  5010.6  324.32
 5014.21326.3452  5016.5  327.63  5025.7  328.16  5090.1  326.81  5168.6  326.69
  5176.6  327.53  5190.3  327.69  5197.4  326.98  5218.2  326.98  5305.8  328.48
  5459.9   329.9  5496.6  330.71    5575  334.02  5773.4  337.21  5908.6  340.29
#Mann= 5 ,-1 , 0
  4691.9     .11       0  4989.5     .06       0 5014.21     .11       0
  5090.1     .15       0  5305.8     .11       0
Bank Sta=4989.5,5014.21
XS Rating Curve= 0 ,0
Exp/Cntr=0.3,0.1

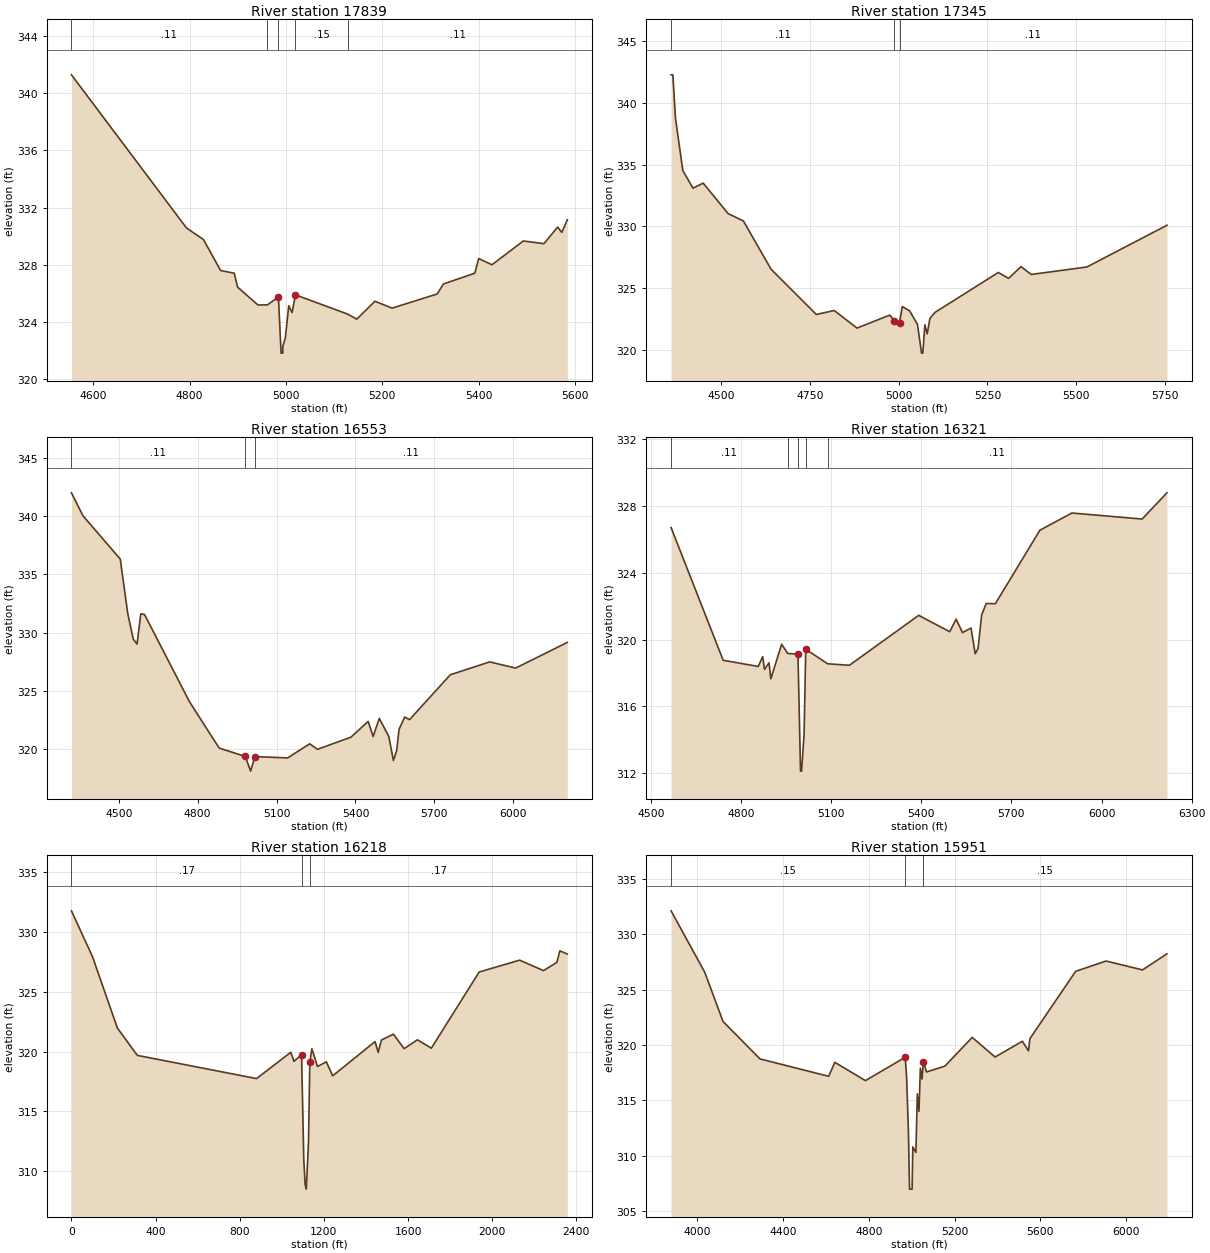
Type RM Length L Ch R = 1 ,17839   ,494,494,494
BEGIN DESCRIPTION:
Mapping XS 64e3be9e
END DESCRIPTION:
XS GIS Cut Line= 3
      3688206.82     10178634.56      3688633.93     10179082.51
      3688967.23     10178842.95
#Sta/Elev= 30
  4554.7  341.27  4793.5  330.58  4828.7  329.77  4864.3  327.61  4892.6  327.42
  4899.5  326.45  4941.9   325.2  4961.4  325.21  4984.4  325.76  4989.9  321.84
  4993.4  321.84  4993.6  322.34  4998.6  322.88  5005.8  325.15  5012.7  324.67
  5019.7  325.91  5128.4  324.56    5147  324.21  5184.6  325.46  5220.3  324.98
  5313.9  325.97  5327.1  326.67  5392.1  327.42  5400.1  328.44  5427.7  328.01
  5492.8  329.67  5535.6  329.48    5564  330.64  5572.6  330.27  5584.1  331.15
#Mann= 5 ,-1 , 0
  4554.7     .11       0  4961.4     .15       0  4984.4     .09       0
  5019.7     .15       0  5128.4     .11       0
Bank Sta=4984.4,5019.7
XS Rating Curve= 0 ,0
Exp/Cntr=0.3,0.1

Type RM Length L Ch R = 1 ,17345   ,792,792,792
BEGIN DESCRIPTION:
Mapping XS d8ea26cc
END DESCRIPTION:
XS GIS Cut Line= 3
      3687915.18     10178936.68      3688519.34     10179441.89
      3688903.79     10178969.12
#Sta/Elev= 30
  4358.8  342.24  4363.8  342.24  4371.1  338.75  4391.9  334.51  4420.6  333.09
  4449.2   333.5  4519.5  331.04  4562.4  330.45  4640.5  326.55    4768   322.9
  4818.5  323.22  4882.5   321.8  4974.9  322.85    4988  322.39  5002.3  322.21
  5010.1  323.54  5030.9  323.19    5053  322.09  5064.4  319.78  5067.9  319.78
  5073.8  322.06  5080.3  321.33  5088.1  322.59  5102.4  323.07  5280.7  326.29
  5309.5  325.81  5344.6  326.76  5373.4  326.13    5530  326.73  5755.7   330.1
#Mann= 3 , 0 , 0
  4358.8     .11       0    4988     .06       0  5002.3     .11       0
Bank Sta=4988,5002.3
XS Rating Curve= 0 ,0
Exp/Cntr=0.3,0.1

Type RM Length L Ch R = 1 ,16553   ,232,232,232
BEGIN DESCRIPTION:
Mapping XS b7877b7f
END DESCRIPTION:
XS GIS Cut Line= 4
      3687441.19     10179186.65      3688022.14     10179670.13
      3688519.81     10179474.95      3688903.83     10179021.11
#Sta/Elev= 30
  4320.3  341.98  4363.9  340.02  4505.8   336.3  4534.4  331.63  4555.3  329.44
  4569.6  329.02  4583.9  331.61  4598.2  331.55  4768.8  324.08    4882   320.1
    4981  319.39  5001.4  318.13  5017.4  319.38  5141.7  319.26  5225.7  320.47
  5255.5     320    5383  321.04  5448.1  322.39  5467.1  321.09  5490.4  322.65
  5526.7   321.1  5544.1  319.04  5556.5  319.88  5565.6  321.71  5587.1  322.77
  5605.4  322.54  5760.6  326.39    5910  327.49  6008.9  326.96  6205.2  329.16
#Mann= 3 , 0 , 0
  4320.3     .11       0    4981     .06       0  5017.4     .11       0
Bank Sta=4981,5017.4
XS Rating Curve= 0 ,0
Exp/Cntr=0.3,0.1

Type RM Length L Ch R = 1 ,16321   ,103,103,103
BEGIN DESCRIPTION:
Mapping XS 1454660f
END DESCRIPTION:
XS GIS Cut Line= 5
      3687605.25     10179541.44       3687937.3     10179767.15
      3688050.15     10179788.85      3688538.43     10179480.69
      3688898.34     10179055.74
#Sta/Elev= 30
    4567  326.71  4740.4  318.76  4857.1  318.39    4872  318.98  4878.1  318.21
    4893  318.61  4899.1  317.65    4935  319.72  4955.2  319.17  4989.4  319.12
  4997.9  312.12  5001.4  312.12  5009.8  314.34  5015.3  319.42  5088.2  318.55
  5160.6  318.46  5391.2  321.45  5494.6  320.47  5515.9  321.22  5537.1  320.42
  5565.5  320.69  5579.5  319.15  5588.9  319.47    5601  321.49    5616  322.16
  5646.6  322.15  5794.7  326.55  5901.2  327.58  6135.2  327.22  6217.7  328.79
#Mann= 5 ,-1 , 0
    4567     .11       0  4955.2     .15       0  4989.4     .09       0
  5015.3     .15       0  5088.2     .11       0
Bank Sta=4989.4,5015.3
XS Rating Curve= 0 ,0
Exp/Cntr=0.3,0.1

Type RM Length L Ch R = 1 ,16218   ,267,267,267
XS GIS Cut Line= 5
      3687453.67       10180840.      3687941.38     10179882.43
      3688002.02      10179852.1      3688538.52     10179494.95
      3688906.36     10179059.84
#Sta/Elev= 30
       0  331.75    99.8  327.93   218.1  321.97     313  319.68   879.7  317.74
  1042.5  319.94  1057.6  319.18  1093.7  319.74  1104.2  310.96  1110.5  308.91
  1116.1  308.51  1126.6   312.4  1132.9   319.1  1142.4  320.23  1169.4  318.75
  1211.5  319.14  1241.5  317.97  1442.9  320.83  1457.9  319.93    1473  320.96
  1530.1  321.45  1581.1  320.24  1644.3  320.98  1710.4  320.28  1937.8  326.64
  2130.2  327.63  2243.3  326.76    2307  327.44  2321.3  328.41  2356.7  328.14
#Mann= 3 , 0 , 0
       0     .17       0  1093.7     .09       0  1132.9     .17       0
Bank Sta=1093.7,1132.9
XS Rating Curve= 0 ,0
Exp/Cntr=0.3,0.1

Type RM Length L Ch R = 1 ,15951   ,499,499,499
BEGIN DESCRIPTION:
CCLC 070 24.0
END DESCRIPTION:
XS GIS Cut Line= 3
      3687467.84     10180861.08      3688149.03     10179969.53
      3688917.84     10179061.09
#Sta/Elev= 30
    3878   332.1  4034.9  326.56  4120.1  322.12  4292.5  318.74  4612.6  317.17
  4641.7  318.43  4784.1  316.78    4970  318.89  4976.3  317.08  4984.5  312.32
  4989.9  306.99  5001.8  306.99  5005.2   310.8  5019.5   310.3  5026.1  315.59
  5033.8  314.01  5040.4  317.91  5048.1  316.92  5054.6   318.5  5068.9  317.56
  5154.7  318.09  5282.1  320.68  5388.7  318.91  5516.1  320.33  5544.7  319.46
  5551.2  320.57  5764.4  326.64  5906.1  327.57  6076.4  326.77  6190.1  328.22
#Mann= 3 , 0 , 0
    3878     .15       0    4970     .09       0  5054.6     .15       0
Bank Sta=4970,5054.6
XS Rating Curve= 0 ,0
Exp/Cntr=0.3,0.1

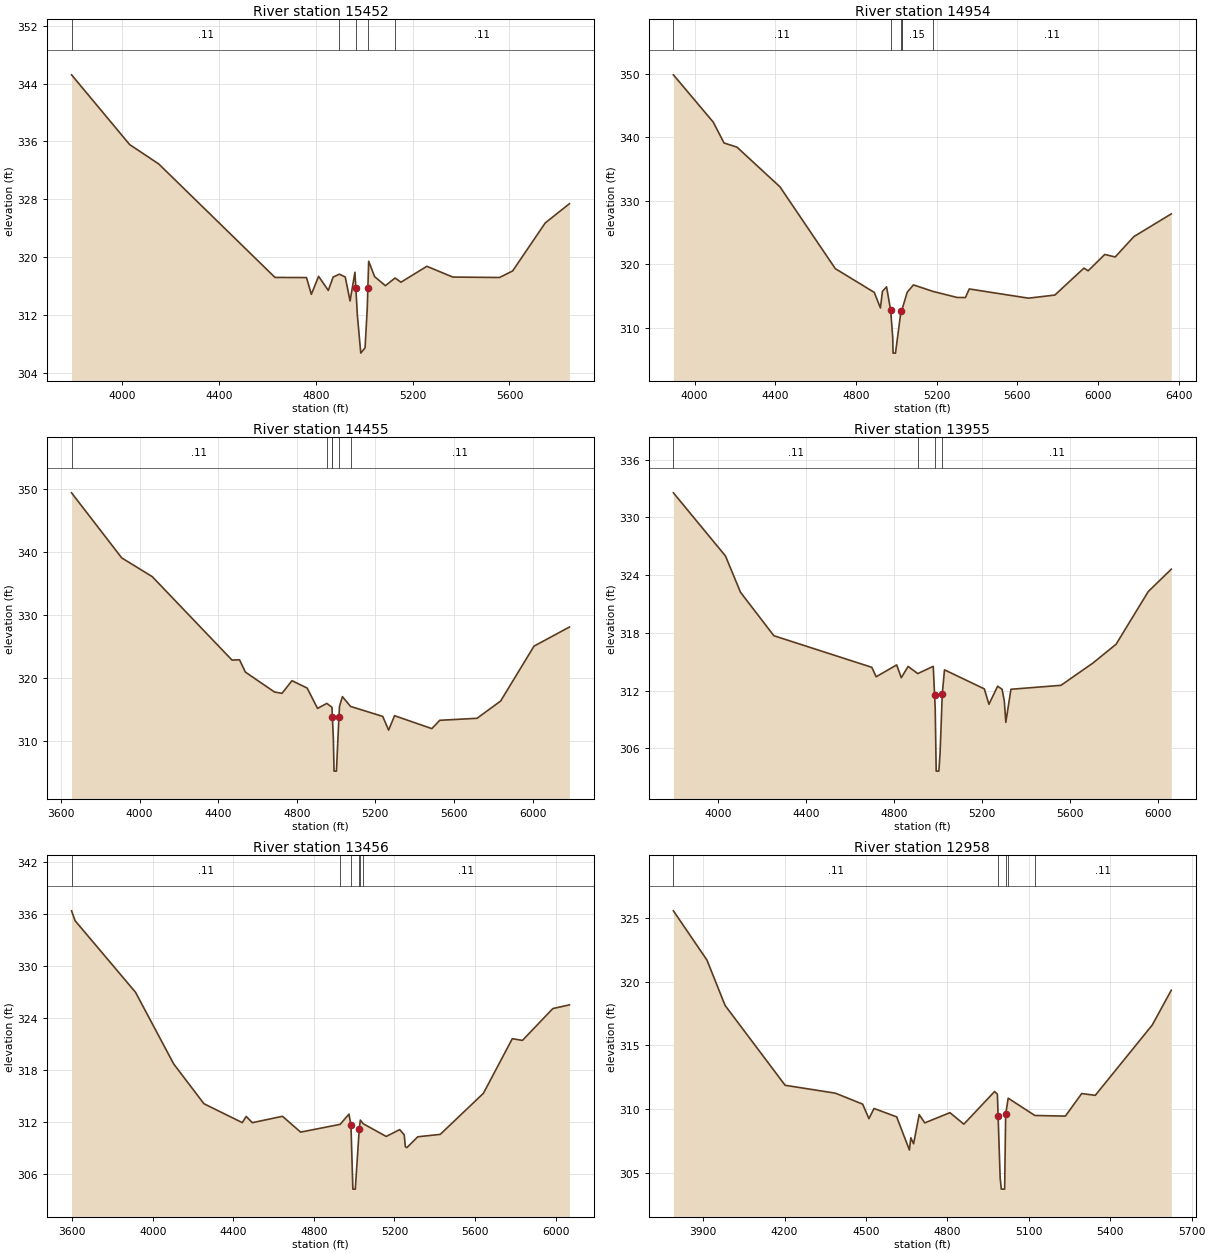
Type RM Length L Ch R = 1 ,15452   ,498,498,498
BEGIN DESCRIPTION:
CCLC 070 23.0
END DESCRIPTION:
XS GIS Cut Line= 3
      3688417.85     10181361.11      3688416.04     10180153.01
      3688717.85     10179361.08
#Sta/Elev= 30
  3791.9  345.22  4031.9  335.56  4151.9  332.88  4631.9  317.17  4761.9  317.15
  4781.9  314.83  4811.9  317.32  4851.9  315.37  4871.9  317.22  4897.9  317.62
  4921.9  317.23  4941.9  313.91  4961.9  317.89  4965.7315.6402  4971.9  311.97
    4986  306.69  5003.7  307.42  5012.8  312.89 5015.33315.7343  5018.6  319.41
  5043.4  317.27  5087.7  316.03  5127.6  317.09  5151.9  316.51  5258.9  318.71
  5365.9  317.22  5558.6  317.16  5613.1  318.07  5747.5  324.71  5847.5  327.38
#Mann= 5 ,-1 , 0
  3791.9     .11       0  4897.9     .15       0  4965.7     .09       0
 5015.33     .15       0  5127.6     .11       0
Bank Sta=4965.7,5015.33
XS Rating Curve= 0 ,0
Exp/Cntr=0.3,0.1

Type RM Length L Ch R = 1 ,14954   ,499,499,499
BEGIN DESCRIPTION:
CCLC 070 22.0
END DESCRIPTION:
XS GIS Cut Line= 3
      3688517.86     10181461.03       3688714.2     10180373.41
      3689045.39     10179051.26
#Sta/Elev= 30
  3894.8  349.83  4092.3  342.38  4145.9  339.09  4209.8  338.44  4423.2  332.18
  4697.5  319.29  4890.6  315.55  4921.1   313.1  4931.1  315.72  4951.6  316.42
  4971.9  312.71  4982.1  308.46  4983.8  305.98  4995.8  305.98    5023  312.59
  5026.3  312.65    5054  315.58  5084.9  316.73  5180.9  315.71  5301.4  314.75
  5342.6  314.74  5361.5  316.09    5655  314.64  5785.9  315.13  5930.2  319.38
  5950.8  318.95  6033.3  321.53  6084.9  321.13  6177.6  324.34    6363  327.92
#Mann= 6 ,-1 , 0
  3894.8     .11       0  4971.9     .06       0    5023     .09       0
  5026.3     .11       0  5026.3     .15       0  5180.9     .11       0
Bank Sta=4971.9,5023
XS Rating Curve= 0 ,0
Exp/Cntr=0.3,0.1

Type RM Length L Ch R = 1 ,14455   ,500,500,500
BEGIN DESCRIPTION:
CCLC 070 21.0
END DESCRIPTION:
XS GIS Cut Line= 3
      3688567.86     10181461.04      3689152.43     10180248.72
      3689167.85     10179061.02
#Sta/Elev= 30
  3654.1  349.45  3909.4  339.12  4064.8  336.14  4470.7  322.89  4508.9  322.94
  4538.6  320.99  4686.5  317.83    4725  317.61  4775.8  319.62  4853.1  318.45
  4905.9  315.22  4953.1  316.01  4979.3   315.4 4981.57313.8175  4986.3  310.52
  4989.9  305.26    5002  305.26 5014.71313.7898  5017.7  315.56  5032.5  317.09
  5074.1  315.53  5237.7  313.95  5267.7  311.77  5297.7  314.06  5487.7  312.01
  5527.7  313.33  5717.7  313.65  5837.7  316.39  6007.7  325.11  6187.8  328.14
#Mann= 6 ,-1 , 0
  3654.1     .11       0  4953.1     .15       0  4979.3     .12       0
 4981.57     .09       0 5014.71     .15       0  5074.1     .11       0
Bank Sta=4981.57,5014.71
XS Rating Curve= 0 ,0
Exp/Cntr=0.3,0.1

Type RM Length L Ch R = 1 ,13955   ,499,499,499
BEGIN DESCRIPTION:
CCLC 070 20.0
END DESCRIPTION:
XS GIS Cut Line= 3
      3689925.58     10181238.73      3689599.93     10180078.67
      3689472.71     10179027.24
#Sta/Elev= 30
  3795.1  332.55    4032  325.99  4100.1  322.23    4252  317.71  4697.3  314.43
  4717.1  313.45  4810.5  314.68  4831.3  313.35  4862.5  314.52  4906.2  313.78
  4976.7  314.53 4982.89311.5185  4985.6   310.2  4990.1  303.65  5002.2  303.65
  5007.7   305.5  5017.7  311.63  5027.8  314.17  5209.1  312.19  5229.9  310.59
  5269.5  312.47  5289.7  312.15  5299.8  310.94  5306.7  308.72    5330  312.15
  5557.5  312.56  5702.7  314.87  5808.3  316.83  5954.5   322.3  6059.1  324.62
#Mann= 4 ,-1 , 0
  3795.1     .11       0  4906.2     .15       0 4982.89     .09       0
  5017.7     .11       0
Bank Sta=4982.89,5017.7
XS Rating Curve= 0 ,0
Exp/Cntr=0.3,0.1

Type RM Length L Ch R = 1 ,13456   ,498,498,498
BEGIN DESCRIPTION:
CCLC 070 19.0
END DESCRIPTION:
XS GIS Cut Line= 3
      3690087.05     10181358.55      3690075.65     10179955.19
      3689597.48     10178999.21
#Sta/Elev= 30
  3596.6  336.37  3614.1  335.23  3914.1  326.96  4104.1  318.66  4254.1  314.07
  4444.1  311.89  4464.1   312.6  4494.1  311.88  4644.1  312.62  4734.1  310.79
  4930.5  311.69  4974.1  312.87  4984.1  311.57  4993.5   304.2  5005.6   304.2
    5025  311.11  5030.6  312.18  5044.9  311.76  5159.1  310.29  5226.2  311.08
  5248.6  310.47  5254.2  309.09  5261.8     309  5315.7  310.25  5427.4  310.53
  5641.9  315.28  5785.2  321.59  5835.5  321.39  5986.4  325.07  6068.9   325.5
#Mann= 6 ,-1 , 0
  3596.6     .11       0  4930.5     .15       0  4984.1     .09       0
    5025     .12       0  5030.6     .15       0  5044.9     .11       0
Bank Sta=4984.1,5025
XS Rating Curve= 0 ,0
Exp/Cntr=0.3,0.1

Type RM Length L Ch R = 1 ,12958   ,588,588,588
BEGIN DESCRIPTION:
CCLC 070 18.0
END DESCRIPTION:
XS GIS Cut Line= 3
      3690267.86     10181011.06      3690552.94     10179835.84
      3690567.85     10179211.12
#Sta/Elev= 30
  3790.7  325.55  3914.2  321.69  3981.3  318.12  4202.3  311.86  4387.5  311.24
  4487.9  310.38    4511  309.24  4529.7  310.04  4613.3  309.38  4660.2  306.78
  4665.4  307.74  4675.6  307.27  4696.2  309.56  4716.8  308.91  4809.4  309.71
  4860.8  308.81    4974  311.37  4984.3  311.16 4986.92309.4724  4994.5  304.59
  4998.8  303.71    5011  303.71  5014.8  309.57    5024  310.85  5122.2  309.49
  5234.8  309.44  5294.9  311.21  5344.9  311.07  5554.9  316.59  5624.9  319.32
#Mann= 5 ,-1 , 0
  3790.7     .11       0 4986.92     .06       0  5014.8     .11       0
    5024     .15       0  5122.2     .11       0
Bank Sta=4986.92,5014.8
XS Rating Curve= 0 ,0
Exp/Cntr=0.3,0.1

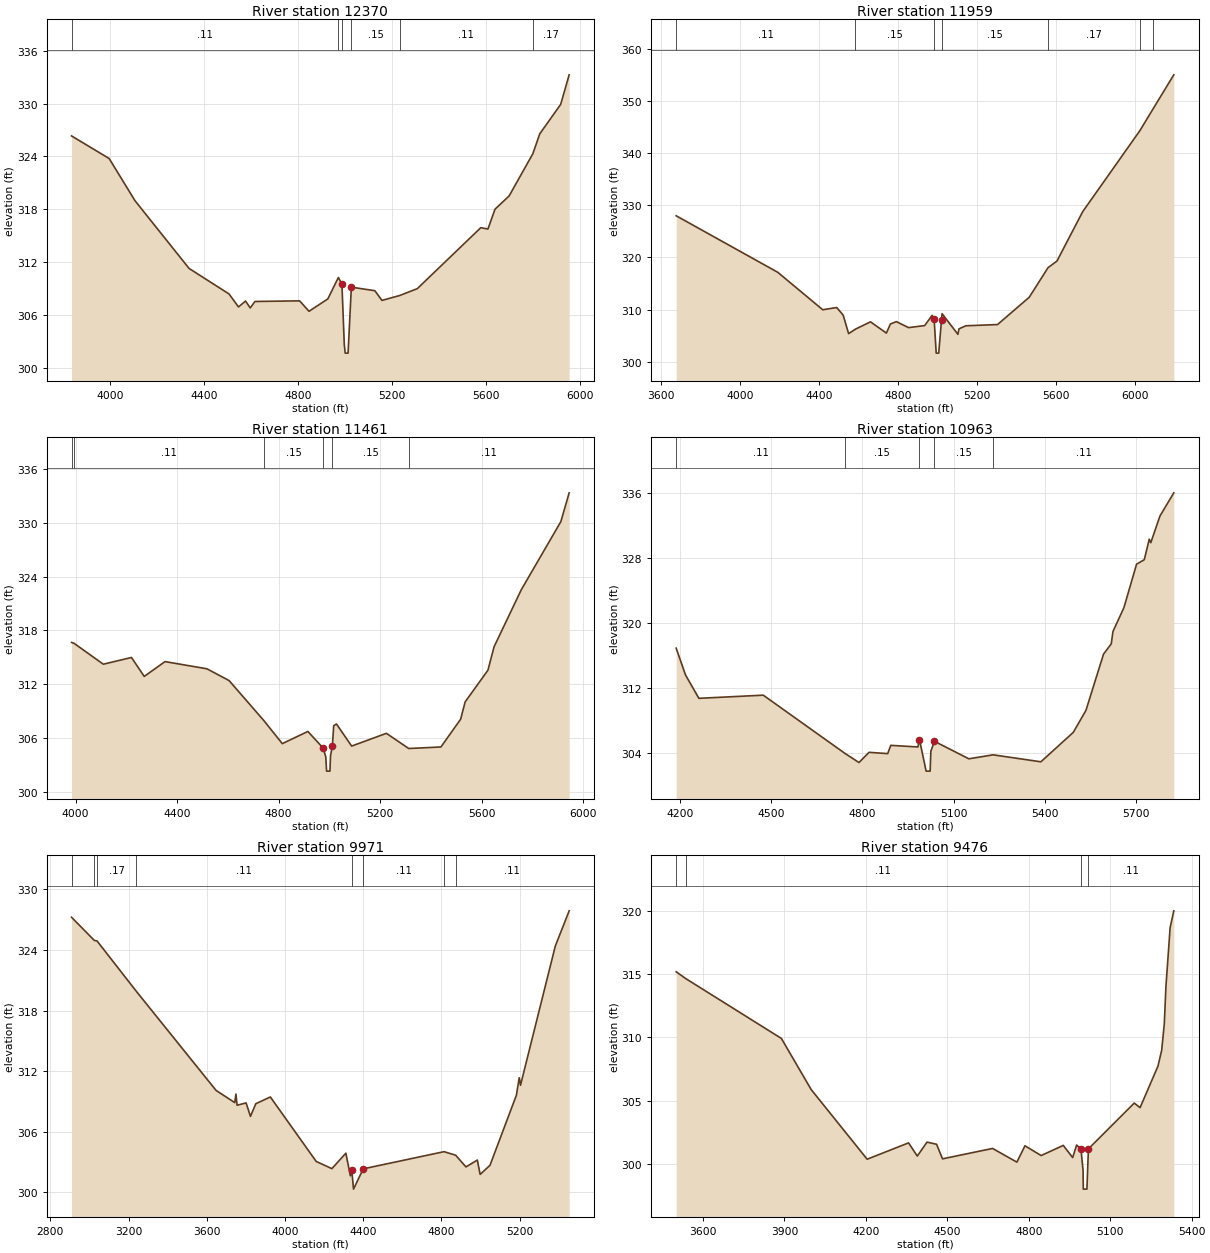
Type RM Length L Ch R = 1 ,12370   ,411,411,411
BEGIN DESCRIPTION:
CCLC 070 17.0
END DESCRIPTION:
XS GIS Cut Line= 3
      3691117.85     10180911.07      3691102.68     10179676.26
      3691154.76      10178796.1
#Sta/Elev= 30
  3836.6  326.33  3996.6  323.77  4106.6  318.99  4336.6  311.32  4506.6  308.43
  4546.7  306.96  4576.7  307.63  4596.7  306.85  4616.7  307.58  4806.7  307.65
  4846.7  306.47  4926.7  307.87  4971.6   310.3  4986.7  309.53  4996.7   302.7
  5000.6  301.73  5012.8  301.73  5026.7   309.2  5126.8   308.8  5156.8   307.7
  5231.7  308.25  5307.1  309.03  5577.4  315.94  5607.6  315.78  5637.7  318.03
  5697.8  319.53  5798.7  324.31    5828  326.56    5917   329.9  5953.2  333.25
#Mann= 6 ,-1 , 0
  3836.6     .11       0  4971.6     .15       0  4986.7     .09       0
  5026.7     .15       0  5231.7     .11       0  5798.7     .17       0
Bank Sta=4986.7,5026.7
XS Rating Curve= 0 ,0
Exp/Cntr=0.3,0.1

Type RM Length L Ch R = 1 ,11959   ,498,498,498
BEGIN DESCRIPTION:
CCLC 070 16.0
END DESCRIPTION:
XS GIS Cut Line= 3
      3691300.59     10180967.95      3691461.23     10179652.82
      3691367.85     10178461.07
#Sta/Elev= 30
  3675.1  328.01  4189.7  317.15  4417.5  309.96    4488  310.39  4520.9  308.92
  4548.4  305.38  4582.9  306.23  4659.2  307.64  4739.8  305.48    4760  307.22
  4790.2  307.68    4852  306.53  4933.6  306.92  4971.5  308.89  4981.6  308.14
    4992  301.63  5004.8  301.63 5018.96308.0669  5021.8   309.2  5102.1  305.24
  5107.2  306.29  5142.2  306.88  5302.7  307.12  5463.2  312.36  5558.5  318.05
  5603.6  319.31    5734   328.8    6024  344.38  6088.9  348.45  6195.4  355.08
#Mann= 7 ,-1 , 0
  3675.1     .11       0  4582.9     .15       0  4981.6     .09       0
 5018.96     .15       0  5558.5     .17       0    6024     .11       0
  6088.9     .17       0
Bank Sta=4981.6,5018.96
XS Rating Curve= 0 ,0
Exp/Cntr=0.3,0.1

Type RM Length L Ch R = 1 ,11461   ,498,498,498
BEGIN DESCRIPTION:
CCLC 070 15.0
END DESCRIPTION:
XS GIS Cut Line= 3
      3691779.76     10180655.43      3691899.95     10179646.66
      3692253.29     10178771.07
#Sta/Elev= 30
  3984.1  316.66  3993.8  316.57  4109.3  314.24  4220.1  314.99  4270.5  312.88
  4352.2  314.53  4517.3  313.73  4604.9  312.41  4741.6  307.96  4814.3  305.39
    4915  306.75  4975.4  304.89  4985.5  303.92  4988.7  302.33  5001.9  302.33
  5004.2  304.04 5011.44305.1269  5016.8  307.39  5027.6  307.58  5087.4  305.12
  5224.3  306.54  5312.3  304.85    5439  305.02  5516.9  308.12  5534.4  310.04
  5624.2  313.57  5648.4  316.18  5755.7  322.54  5911.4  330.12  5944.2  333.33
#Mann= 6 ,-1 , 0
  3984.1     .17       0  3993.8     .11       0  4741.6     .15       0
  4975.4     .09       0 5011.44     .15       0  5312.3     .11       0
Bank Sta=4975.4,5011.44
XS Rating Curve= 0 ,0
Exp/Cntr=0.3,0.1

Type RM Length L Ch R = 1 ,10963   ,992,992,992
BEGIN DESCRIPTION:
CCLC 070 14.0
END DESCRIPTION:
XS GIS Cut Line= 3
      3692217.84     10180411.11      3692386.03     10179616.61
      3692581.86     10178816.84
#Sta/Elev= 30
  4187.9  316.92  4218.6  313.61  4262.5  310.73  4474.1  311.12  4742.5  303.94
  4788.7  302.81  4821.7  304.07    4883  303.91  4893.2  304.93  4982.4  304.73
  4987.5  305.65  5009.4  301.75  5022.6  301.75  5024.9   304.2  5036.6  305.43
  5149.8  303.27  5229.5  303.76  5386.6   302.9    5493  306.53  5534.6  309.24
  5592.5  316.19  5617.8  317.45  5623.4  318.97  5659.4  321.91    5701  327.28
  5726.4  327.83  5742.7  330.36  5747.8  329.93  5777.9  333.22  5823.4  336.08
#Mann= 5 ,-1 , 0
  4187.9     .11       0  4742.5     .15       0  4987.5     .09       0
  5036.6     .15       0  5229.5     .11       0
Bank Sta=4987.5,5036.6
XS Rating Curve= 0 ,0
Exp/Cntr=0.3,0.1

Type RM Length L Ch R = 1 ,9971    ,495,495,495
BEGIN DESCRIPTION:
CCLC 070 13.0
END DESCRIPTION:
XS GIS Cut Line= 3
      3691967.86     10181161.05      3693025.06     10179356.65
      3693317.83      10179011.1
#Sta/Elev= 30
  2908.7  327.24  3025.1  324.95  3038.9   324.9  3240.6  319.89  3647.6  310.09
  3743.2  308.88  3749.2  309.73    3755  308.62  3801.1  308.85  3823.5  307.52
  3850.8  308.77  3925.1  309.44  4159.7  303.05  4239.8  302.34  4311.1  303.87
  4334.2  301.63  4341.4  302.18  4350.4  300.31  4400.1  302.32  4813.1  304.02
  4872.6  303.67  4925.3  302.51  4983.3  303.19  4997.8  301.77  5048.1  302.67
  5183.2  309.62  5197.5  311.34  5204.1   310.6  5382.1  324.39  5452.9  327.88
#Mann= 8 ,-1 , 0
  2908.7     .17       0  3025.1     .11       0  3038.9     .17       0
  3240.6     .11       0  4341.4     .06       0  4400.1     .11       0
  4813.1     .15       0  4872.6     .11       0
Bank Sta=4341.4,4400.1
XS Rating Curve= 0 ,0
Exp/Cntr=0.3,0.1

Type RM Length L Ch R = 1 ,9476    ,495,495,495
BEGIN DESCRIPTION:
CCLC 070 12.0
END DESCRIPTION:
XS GIS Cut Line= 3
      3692722.48     10180910.62      3693445.46      10179597.5
      3693617.85     10179311.07
#Sta/Elev= 30
    3501  315.18  3536.5  314.64  3888.6  309.92  3998.2  305.89  4204.6  300.39
  4357.1  301.68  4389.3  300.64  4425.1  301.74  4460.3  301.57  4482.2  300.42
  4666.7  301.24  4756.2  300.16    4786  301.45  4845.6  300.68  4927.1  301.48
  4961.7  300.52  4976.3  301.51  4992.4  301.17    5000  299.51  5000.8  298.03
  5014.2  298.03  5019.7  301.21  5188.6  304.82    5210  304.46  5275.9  307.73
  5289.6  308.98  5299.3  311.08  5305.2  313.98  5320.7  318.66  5334.3  319.99
#Mann= 4 ,-1 , 0
    3501     .17       0  3536.5     .11       0  4992.4     .06       0
  5019.7     .11       0
Bank Sta=4992.4,5019.7
XS Rating Curve= 0 ,0
Exp/Cntr=0.3,0.1

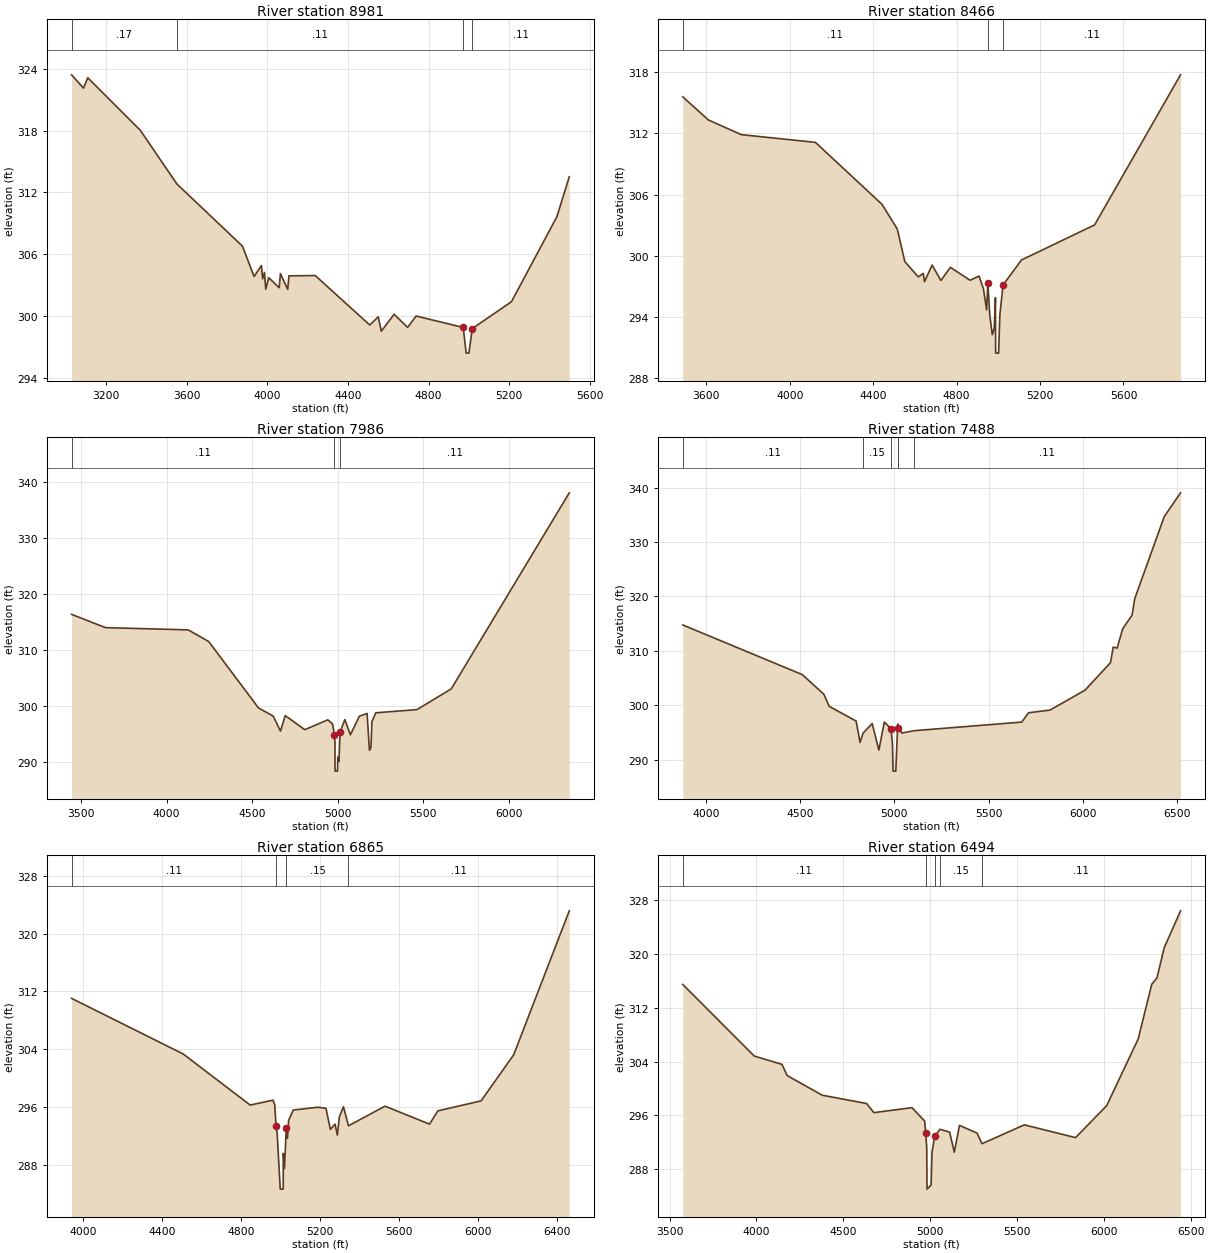
Type RM Length L Ch R = 1 ,8981    ,515,515,515
BEGIN DESCRIPTION:
CCLC 070 11.0
END DESCRIPTION:
XS GIS Cut Line= 3
      3692767.87     10181461.05      3693824.73     10179796.88
      3693717.86      10179311.1
#Sta/Elev= 30
  3028.6  323.41  3087.8  322.12    3109  323.13  3369.9  318.02    3551  312.82
  3876.4  306.78    3934  303.84  3970.5   304.9  3976.4  303.61  3985.7  304.23
  3991.6   302.6  4006.9  303.72  4058.5  302.75  4064.5  304.11  4100.9  302.59
  4106.8   303.9  4237.3  303.93  4507.5  299.13  4549.8  299.92  4565.1  298.53
  4628.6  300.17  4695.5   298.9  4737.8     300  4971.3  298.89    4986   296.4
  4999.5   296.4  5016.2  298.78  5210.7  301.39    5436  309.64  5497.4  313.52
#Mann= 4 ,-1 , 0
  3028.6     .17       0    3551     .11       0  4971.3     .06       0
  5016.2     .11       0
Bank Sta=4971.3,5016.2
XS Rating Curve= 0 ,0
Exp/Cntr=0.3,0.1

Type RM Length L Ch R = 1 ,8466    ,480,480,480
BEGIN DESCRIPTION:
CCLC 070 10.0
END DESCRIPTION:
XS GIS Cut Line= 3
      3693425.59     10181316.89      3694300.59     10179926.26
      3693993.29     10179249.15
#Sta/Elev= 30
    3487  315.59  3609.7  313.32  3767.5  311.88  4123.1  311.12  4442.2  305.04
  4515.2  302.63  4551.7  299.42  4616.3  297.92  4639.9  298.26  4645.9  297.45
  4682.4  299.08  4724.8  297.57  4769.9  298.86  4864.4  297.59  4907.3     298
  4928.5  296.76  4943.8  294.68  4949.7  297.33  4958.9  294.18  4970.9  292.25
  4980.3  292.86  4986.2  295.88  4986.9  290.94  4987.4  290.44  5001.3  290.44
  5007.4  294.23  5022.7  297.13    5111  299.58  5461.5  303.02  5873.6  317.75
#Mann= 3 , 0 , 0
    3487     .11       0  4949.7     .06       0  5022.7     .11       0
Bank Sta=4949.7,5022.7
XS Rating Curve= 0 ,0
Exp/Cntr=0.3,0.1

Type RM Length L Ch R = 1 ,7986    ,498,498,498
BEGIN DESCRIPTION:
CCLC 070 9.0
END DESCRIPTION:
XS GIS Cut Line= 3
      3693617.86     10181461.07      3694626.71     10180277.23
      3695217.85     10179061.08
#Sta/Elev= 30
  3444.6  316.41  3642.8  314.04    4126  313.64    4246  311.56  4536.6  299.71
  4622.3  298.26  4665.1  295.57  4692.8  298.35  4806.7  295.83  4941.8  297.58
  4969.2  296.86 4979.88294.9564  4983.5  293.47  4983.8  288.93  4984.3  288.43
  4998.2  288.43    5000  290.97  5006.8  290.15  5013.2  295.36  5041.3  297.63
  5073.6  294.92    5126  298.23  5171.1  298.72  5184.7  292.15  5193.7  292.67
  5199.2  297.25  5221.8  298.84  5462.7  299.41  5662.8  303.11  6352.2   338.1
#Mann= 3 ,-1 , 0
  3444.6     .11       0 4979.88     .06       0  5013.2     .11       0
Bank Sta=4979.88,5013.2
XS Rating Curve= 0 ,0
Exp/Cntr=0.3,0.1

Type RM Length L Ch R = 1 ,7488    ,623,623,623
BEGIN DESCRIPTION:
CCLC 070 8.0
END DESCRIPTION:
XS GIS Cut Line= 3
      3694117.87     10181211.06       3695002.9     10180521.25
      3695917.84     10179311.09
#Sta/Elev= 30
  3877.9  314.77  4511.8  305.64  4625.9  302.03  4654.1  299.82    4797  297.11
  4817.8  293.18  4833.7  294.89  4882.1  296.66  4917.5  291.77  4946.3  296.93
  4981.6  295.73  4989.7   292.9  4992.6  287.91  5007.3  287.91 5016.81295.8332
  5017.8  296.57  5038.6   294.9  5104.5  295.34  5675.3  296.92  5710.7  298.63
  5825.2  299.13  6010.4  302.78  6145.7  307.83  6160.2   310.7  6181.1  310.52
  6210.2  314.04  6260.1  316.57  6274.7  319.64  6430.8  334.68  6517.1  339.05
#Mann= 6 ,-1 , 0
  3877.9     .11       0  4833.7     .15       0  4981.6     .09       0
 5016.81     .12       0  5017.8     .15       0  5104.5     .11       0
Bank Sta=4981.6,5016.81
XS Rating Curve= 0 ,0
Exp/Cntr=0.3,0.1

Type RM Length L Ch R = 1 ,6865    ,371,371,371
BEGIN DESCRIPTION:
CCLC 070 7.0
END DESCRIPTION:
XS GIS Cut Line= 3
      3694467.87     10181411.06      3695284.97      10181014.8
      3696133.41     10179640.64
#Sta/Elev= 30
    3940  311.03  4506.9  303.31  4845.5  296.25  4961.2  296.93    4970  296.29
  4976.6  293.35  4982.5  292.26  4997.9  284.61  5012.6  284.61  5013.1  285.11
  5013.3  289.55  5019.2  287.46  5028.7  293.11  5034.5  291.65  5040.5  294.14
    5064  295.56  5187.1  295.95  5229.6  295.81  5252.1  292.87  5275.6  293.61
  5287.5  292.09  5297.1  294.58  5318.3  296.02  5343.9  293.38  5528.8   296.1
  5754.7  293.61  5797.2  295.45    6016  296.83  6181.5  303.22  6463.1  323.15
#Mann= 4 ,-1 , 0
    3940     .11       0  4976.6     .09       0  5028.7     .15       0
  5343.9     .11       0
Bank Sta=4976.6,5028.7
XS Rating Curve= 0 ,0
Exp/Cntr=0.3,0.1

Type RM Length L Ch R = 1 ,6494    ,543,543,543
BEGIN DESCRIPTION:
CCLC 070 6.0
END DESCRIPTION:
XS GIS Cut Line= 3
      3694889.13     10182249.19      3695646.69     10181043.89
      3696467.84     10179861.09
#Sta/Elev= 30
  3576.4  315.49  3987.6  304.83  4147.1   303.6  4176.5  301.94  4377.9  299.01
  4633.5  297.77  4675.9  296.41    4895  297.15  4967.9  295.15  4973.9  293.31
  4979.8  291.26  4981.3  285.52  4981.8  285.02  5004.8  285.62  5010.2  290.47
    5025  292.88  5056.1  293.93  5111.5  293.51  5138.5  290.52  5168.2  294.51
  5269.5  293.36  5297.8  291.78    5541  294.59  5836.1  292.69  6015.1  297.45
  6196.4  307.38  6274.5  315.53  6304.2  316.46    6346  320.96  6439.9  326.46
#Mann= 5 ,-1 , 0
  3576.4     .11       0  4973.9     .06       0    5025     .11       0
  5056.1     .15       0  5297.8     .11       0
Bank Sta=4973.9,5025
XS Rating Curve= 0 ,0
Exp/Cntr=0.3,0.1