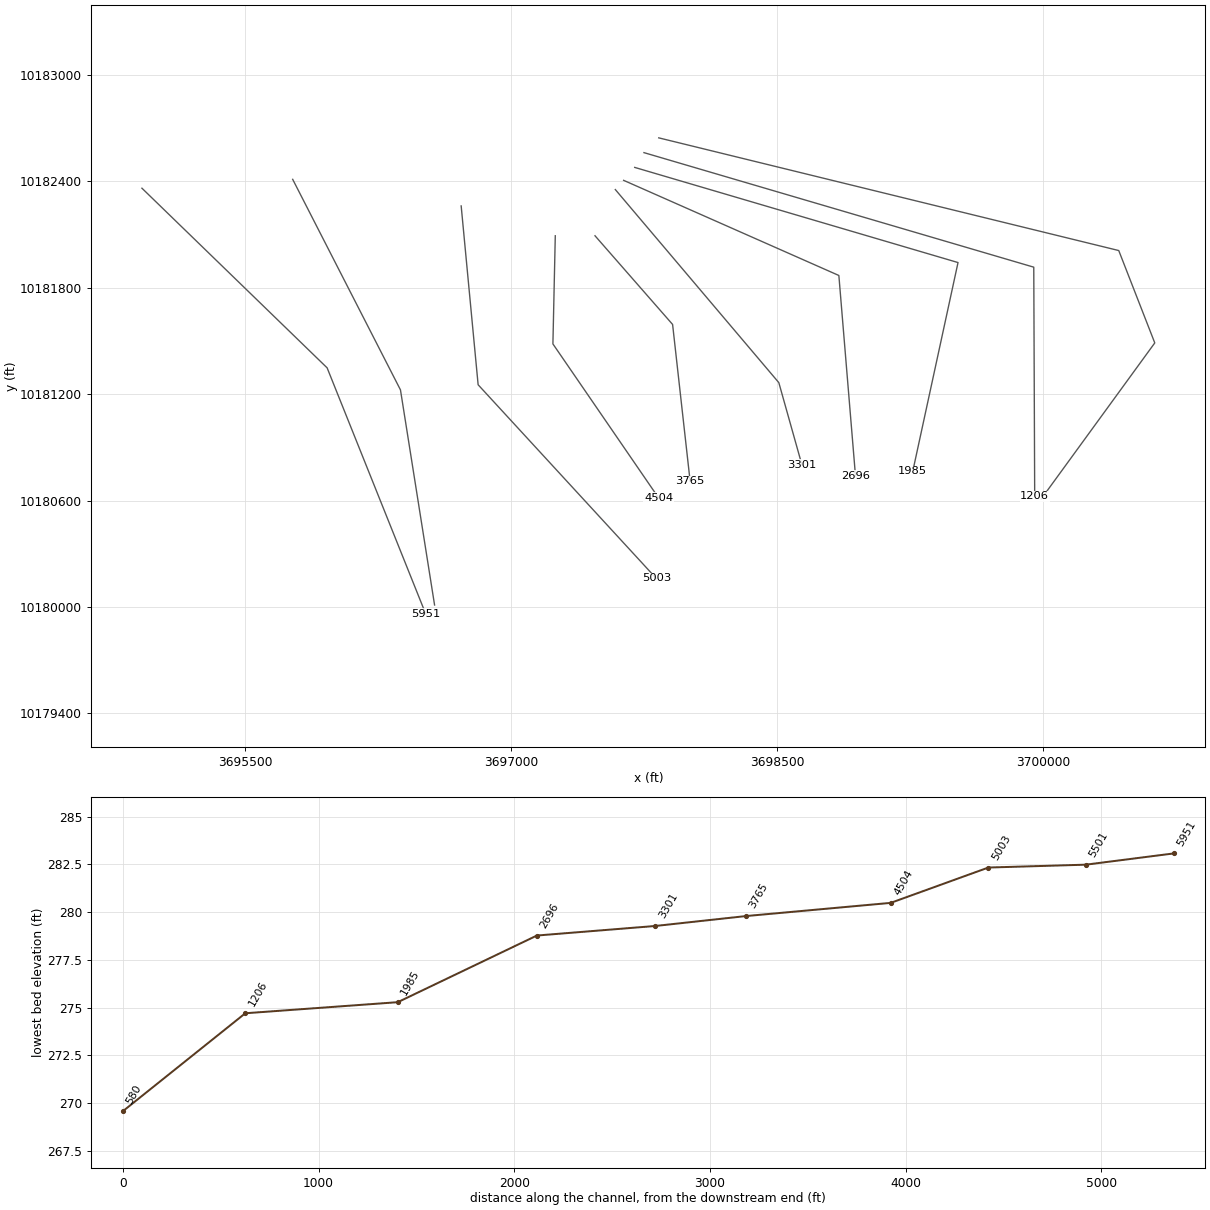
HEC-RAS study CCLC 070.prj: CCLC 070 Base Level Engineering

--- CCLC 070.g01 (geometry) --- (continued)

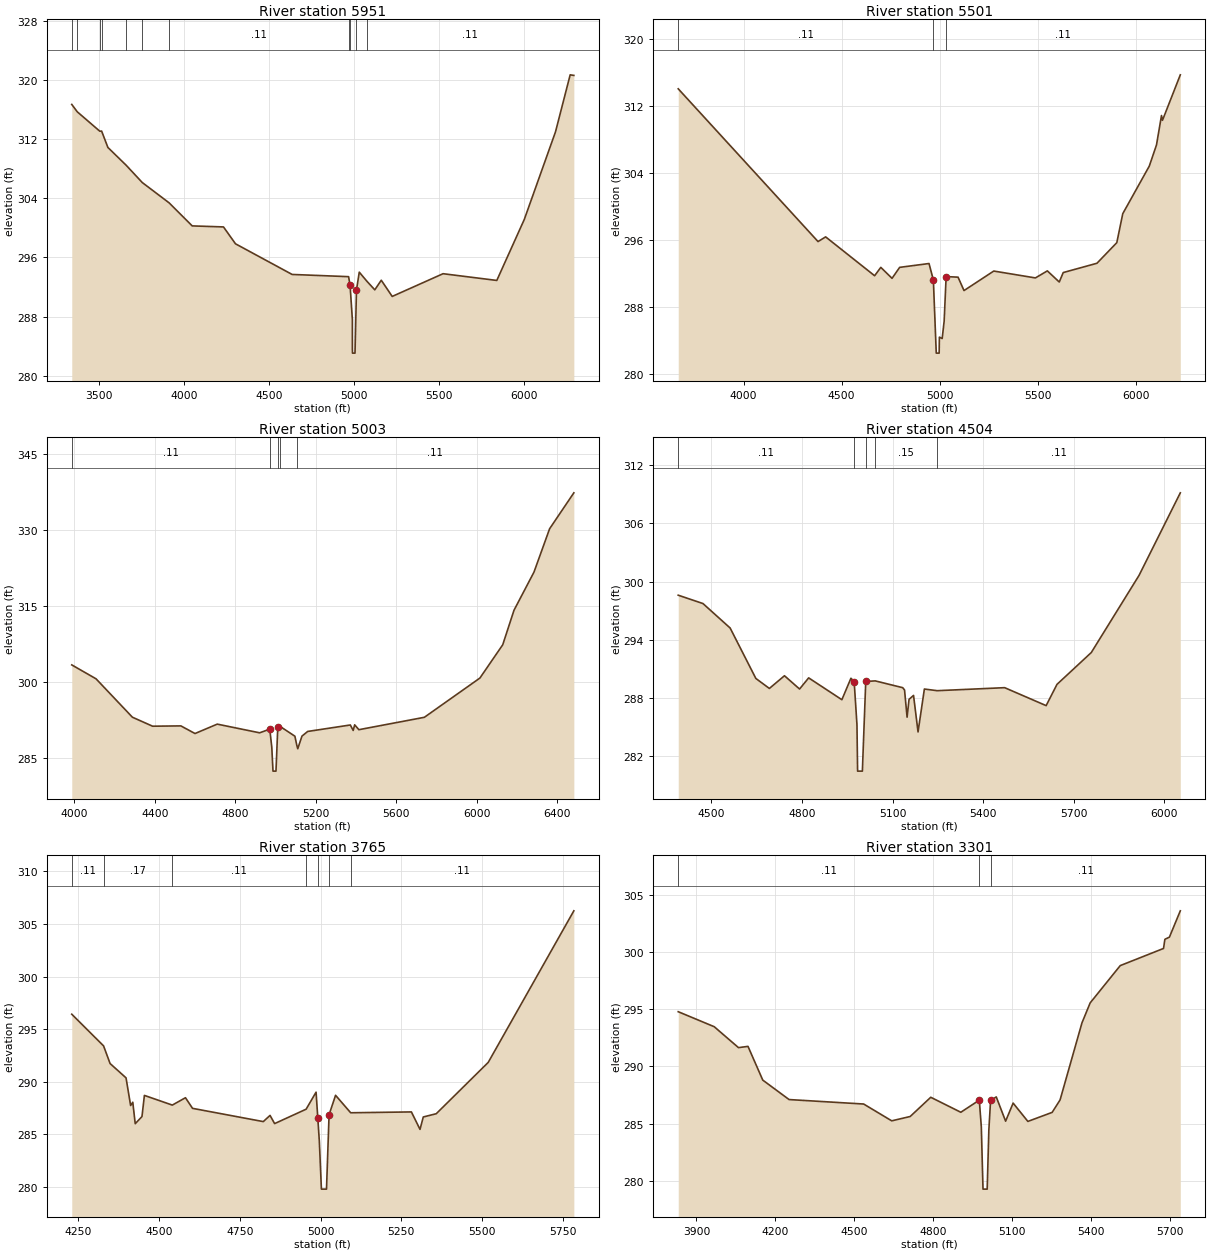
Type RM Length L Ch R = 1 ,5951    ,450,450,450
BEGIN DESCRIPTION:
CCLC 070 5.0
END DESCRIPTION:
XS GIS Cut Line= 3
      3694917.82      10182361.1      3695962.05     10181348.14
      3696517.85     10179961.07
#Sta/Elev= 30
  3341.2  316.67  3373.7  315.67    3506  313.05  3516.6  313.07  3553.3  310.86
  3660.9  308.45  3755.2  306.12  3913.2  303.37  4048.5  300.26  4232.4  300.12
  4302.9  297.84  4635.5   293.7  4967.2   293.4    4976  292.23  4989.3  287.63
  4989.6  283.57  4990.1  283.07  5004.9  283.07  5013.5  291.59  5029.9  294.01
  5075.2  292.77  5121.1  291.62  5159.1  292.92  5223.4  290.73  5522.1   293.8
  5837.8  292.89  5999.4  301.14  6182.6  312.97  6268.8  320.67  6290.3  320.59
#Mann= 11 ,-1 , 0
  3341.2     .11       0  3373.7     .17       0    3506     .11       0
  3516.6     .17       0  3660.9     .11       0  3755.2     .17       0
  3913.2     .11       0  4967.2     .15       0    4976     .09       0
  5013.5     .15       0  5075.2     .11       0
Bank Sta=4976,5013.5
XS Rating Curve= 0 ,0
Exp/Cntr=0.3,0.1

Type RM Length L Ch R = 1 ,5501    ,498,498,498
BEGIN DESCRIPTION:
CCLC 070 4.0
END DESCRIPTION:
XS GIS Cut Line= 3
      3695767.83      10182411.1      3696375.56     10181223.91
      3696567.85     10180011.06
#Sta/Elev= 30
  3666.3  314.04  4379.6   295.8  4418.4  296.36  4668.3  291.72  4699.9  292.72
  4757.2  291.41    4796  292.72  4945.8  293.18    4968  291.22  4982.8  282.48
  4997.6  282.48  4998.8  284.39    5013  284.22  5023.1  286.31  5033.2  291.62
    5094  291.55  5124.4  289.95  5276.2  292.28  5488.7  291.46  5549.6   292.3
  5610.4  290.97  5630.6   292.1  5802.7  293.21    5904  295.67  5934.4  299.13
  6069.7  304.81  6106.5  307.34    6132  310.85  6137.1  310.28    6228  315.71
#Mann= 3 ,-1 , 0
  3666.3     .11       0    4968     .06       0  5033.2     .11       0
Bank Sta=4968,5033.2
XS Rating Curve= 0 ,0
Exp/Cntr=0.3,0.1

Type RM Length L Ch R = 1 ,5003    ,499,499,499
BEGIN DESCRIPTION:
CCLC 070 3.0
END DESCRIPTION:
XS GIS Cut Line= 3
      3696717.85     10182261.11      3696813.47     10181252.84
      3697817.86     10180161.06
#Sta/Elev= 30
  3987.2  303.35  4107.8   300.6  4288.6     293    4389  291.22  4529.7  291.28
    4600  289.77  4710.5  291.63  4921.4  289.91  4971.6  290.64  4981.7  287.06
  4987.7  282.33  5002.5  282.33  5011.5  291.01  5024.4  291.14  5096.6  289.24
  5105.8   287.5  5110.8  286.76  5131.8  289.26  5160.1  290.18  5372.2  291.46
  5386.4  290.38  5393.8  291.49  5414.7  290.53  5740.3  292.98  6016.5  300.75
  6129.9  307.33    6186  314.17  6285.3  321.71    6363  330.29  6483.5   337.4
#Mann= 5 ,-1 , 0
  3987.2     .11       0  4971.6     .06       0  5011.5     .11       0
  5024.4     .15       0  5105.8     .11       0
Bank Sta=4971.6,5011.5
XS Rating Curve= 0 ,0
Exp/Cntr=0.3,0.1

Type RM Length L Ch R = 1 ,4504    ,739,739,739
BEGIN DESCRIPTION:
CCLC 070 2.0
END DESCRIPTION:
XS GIS Cut Line= 3
      3697248.51     10182092.92       3697235.1     10181483.17
      3697831.05     10180614.92
#Sta/Elev= 30
  4390.1  298.61    4472  297.75    4562  295.23  4647.2  290.03    4692     289
    4742  290.31    4792  288.94  4822.1  290.09  4932.1  287.84  4962.1  290.05
 4972.82289.7145  4982.1  285.26  4984.2  280.48    5000  280.48  5011.2  289.72
  5042.5  289.78  5133.6  289.08  5139.7  288.84  5148.1  286.04  5154.6  287.88
  5169.5  288.28  5184.4  284.52  5205.4  288.94  5247.9  288.77  5471.3  289.08
  5608.7  287.23  5644.6  289.42  5758.2   292.7  5916.6  300.66  6053.1  309.16
#Mann= 5 ,-1 , 0
  4390.1     .11       0 4972.82     .06       0  5011.2     .11       0
  5042.5     .15       0  5247.9     .11       0
Bank Sta=4972.82,5011.2
XS Rating Curve= 0 ,0
Exp/Cntr=0.3,0.1

Type RM Length L Ch R = 1 ,3765    ,464,464,464
BEGIN DESCRIPTION:
Mapping XS 24096e8a
END DESCRIPTION:
XS GIS Cut Line= 3
      3697472.47     10182092.93      3697909.97     10181592.93
      3698008.93     10180707.53
#Sta/Elev= 30
  4229.2  296.42  4327.7  293.41  4347.9  291.73  4397.3  290.37  4411.5  287.74
  4418.2  288.05  4425.8  286.01  4446.7  286.69  4454.2   288.7  4540.7  287.78
  4581.4  288.48  4603.3  287.47  4822.5  286.21  4843.4   286.8  4857.6  286.02
  4955.2  287.39    4986  289.01 4991.24286.5923  4996.1  284.35  5002.5  279.79
  5018.3  279.79  5026.3  286.87  5046.4  288.71  5093.2  287.05  5281.3  287.13
    5308  285.47  5318.1  286.65  5358.3  286.96  5519.3  291.84  5784.5  306.25
#Mann= 7 ,-1 , 0
  4229.2     .11       0  4327.7     .17       0  4540.7     .11       0
  4955.2     .15       0 4991.24     .09       0  5026.3     .15       0
  5093.2     .11       0
Bank Sta=4991.24,5026.3
XS Rating Curve= 0 ,0
Exp/Cntr=0.3,0.1

Type RM Length L Ch R = 1 ,3301    ,605,605,605
BEGIN DESCRIPTION:
Mapping XS 3e1ecfb5
END DESCRIPTION:
XS GIS Cut Line= 3
      3697587.03     10182353.38      3698508.93      10181264.8
      3698639.14     10180801.24
#Sta/Elev= 30
    3831  294.78  3967.7  293.47    4060  291.64  4096.1  291.75  4152.3   288.8
  4252.3   287.1  4535.7  286.71  4642.3  285.24  4712.5  285.62  4790.6   287.3
  4904.9  285.99  4975.1  287.05  4982.8  284.71  4989.2  279.27  5005.1  279.27
  5011.4  284.43    5018  287.02  5039.6  287.33  5075.1  285.21  5103.7  286.79
  5159.7  285.19    5252  285.98  5282.1  287.07  5365.2   293.8  5396.4  295.55
  5510.7  298.81  5675.2  300.31  5680.4  301.11  5697.6   301.3    5739   303.6
#Mann= 3 ,-1 , 0
    3831     .11       0  4975.1     .06       0    5018     .11       0
Bank Sta=4975.1,5018
XS Rating Curve= 0 ,0
Exp/Cntr=0.3,0.1

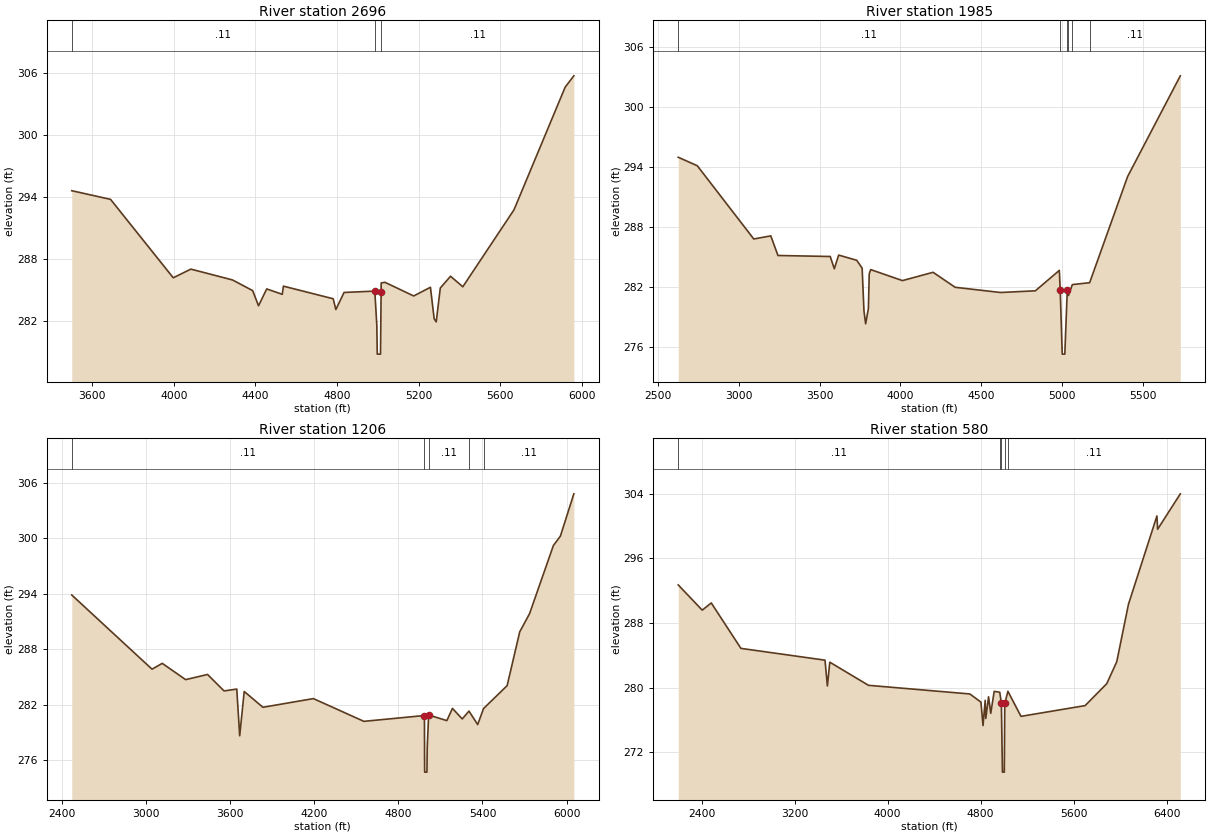
Type RM Length L Ch R = 1 ,2696    ,711,711,711
BEGIN DESCRIPTION:
Mapping XS 226df57c
END DESCRIPTION:
XS GIS Cut Line= 3
      3697633.94     10182405.42      3698847.47     10181868.97
      3698941.22     10180738.77
#Sta/Elev= 30
  3499.9  294.59    3690  293.75  3997.3  286.16  4083.7     287  4287.8  285.95
  4386.5  284.92  4415.3  283.45  4455.4  285.08  4531.8  284.56  4537.2  285.35
  4781.2  284.13  4794.3  283.09  4834.6  284.74  4985.2  284.87  4995.2  281.54
  4997.2  278.77  5013.2  278.77 5016.13284.8153  5016.5  285.66  5035.3  285.72
  5175.8   284.4  5257.9  285.24  5276.2  282.19  5286.2  281.89  5306.3  285.17
  5356.4  286.31  5416.6  285.29  5667.5  292.74  5918.4  304.62  5960.8  305.71
#Mann= 3 ,-1 , 0
  3499.9     .11       0  4985.2     .06       0 5016.13     .11       0
Bank Sta=4985.2,5016.13
XS Rating Curve= 0 ,0
Exp/Cntr=0.3,0.1

Type RM Length L Ch R = 1 ,1985    ,779,779,779
BEGIN DESCRIPTION:
Mapping XS 3acc458d
END DESCRIPTION:
XS GIS Cut Line= 3
       3697696.4     10182478.35      3699519.34     10181941.89
      3699264.28     10180765.46
#Sta/Elev= 30
  2625.9  294.96  2743.8  294.11  3092.9  286.79  3198.1   287.1  3242.4  285.14
  3565.6  285.04    3591  283.81  3617.7  285.18  3729.6  284.66  3762.9  283.87
  3774.1  279.61  3784.5  278.31  3801.5  279.84  3806.7   283.3  3815.8  283.73
    4012  282.63  4201.4  283.46  4338.2  281.96  4619.1  281.44  4833.9  281.61
  4981.9  283.65  4987.4  281.73  4999.9  275.28  5015.9  275.28  5031.1  281.68
  5038.6  281.14  5062.3  282.23  5169.4  282.42  5404.1  293.03  5729.9   303.1
#Mann= 6 ,-1 , 0
  2625.9     .11       0  4987.4     .06       0  5031.1     .09       0
  5038.6     .11       0  5062.3     .17       0  5169.4     .11       0
Bank Sta=4987.4,5031.1
XS Rating Curve= 0 ,0
Exp/Cntr=0.3,0.1

Type RM Length L Ch R = 1 ,1206    ,626,626,626
BEGIN DESCRIPTION:
Mapping XS a23286f4
END DESCRIPTION:
XS GIS Cut Line= 3
      3697748.53     10182561.67      3699946.43     10181915.85
      3699951.63     10180625.17
#Sta/Elev= 30
  2470.3  293.85  3042.8  285.83  3115.8  286.46  3282.6   284.7  3438.9  285.26
  3556.5  283.48  3647.4  283.68  3668.2  278.63  3700.4  283.42  3833.9  281.71
  4193.7  282.65  4554.1  280.19  4985.9  280.82  4987.3   275.2  4987.8   274.7
  5003.9   274.7  5005.9  277.34  5015.9  280.88  5145.9  280.27  5185.9  281.59
  5255.9  280.45  5303.8   281.3  5365.9  279.84  5407.5  281.57  5575.9  284.05
  5665.9  289.87  5735.9  291.83  5905.9   299.2  5955.9  300.22  6051.8  304.79
#Mann= 5 ,-1 , 0
  2470.3     .11       0  4985.9     .06       0  5015.9     .11       0
  5303.8     .15       0  5407.5     .11       0
Bank Sta=4985.9,5015.9
XS Rating Curve= 0 ,0
Exp/Cntr=0.3,0.1

Type RM Length L Ch R = 1 ,580     ,0,0,0
BEGIN DESCRIPTION:
CCLC 070 1.0
END DESCRIPTION:
XS GIS Cut Line= 4
      3697831.85     10182645.01      3700425.59      10182009.6
      3700628.72     10181488.76      3699988.12     10180608.58
#Sta/Elev= 30
  2198.8  292.73  2405.1  289.61    2483   290.5  2737.9  284.88  3461.1  283.42
  3481.6  280.23  3502.3  283.17  3835.1  280.31  4706.8  279.24  4802.3  278.23
  4820.1  275.33  4838.8  278.45  4843.9  276.21  4867.8  278.89  4886.5  276.84
  4916.3  279.56  4963.7  279.46 4977.89278.1295  4987.1  269.57  5003.2  269.57
  5007.2  278.07  5034.3  279.57  5146.7  276.47  5698.4   277.8  5884.7  280.52
  5970.4  283.23  6070.9  290.33  6315.8  301.26    6322  299.62  6516.9     304
#Mann= 5 ,-1 , 0
  2198.8     .11       0  4963.7     .15       0 4977.89     .09       0
  5007.2     .15       0  5034.3     .11       0
Bank Sta=4977.89,5007.2
XS Rating Curve= 0 ,0
Exp/Cntr=0.3,0.1

Chan Stop Cuts=-1
Use User Specified Reach Order=0
Composite Channel Slope=5