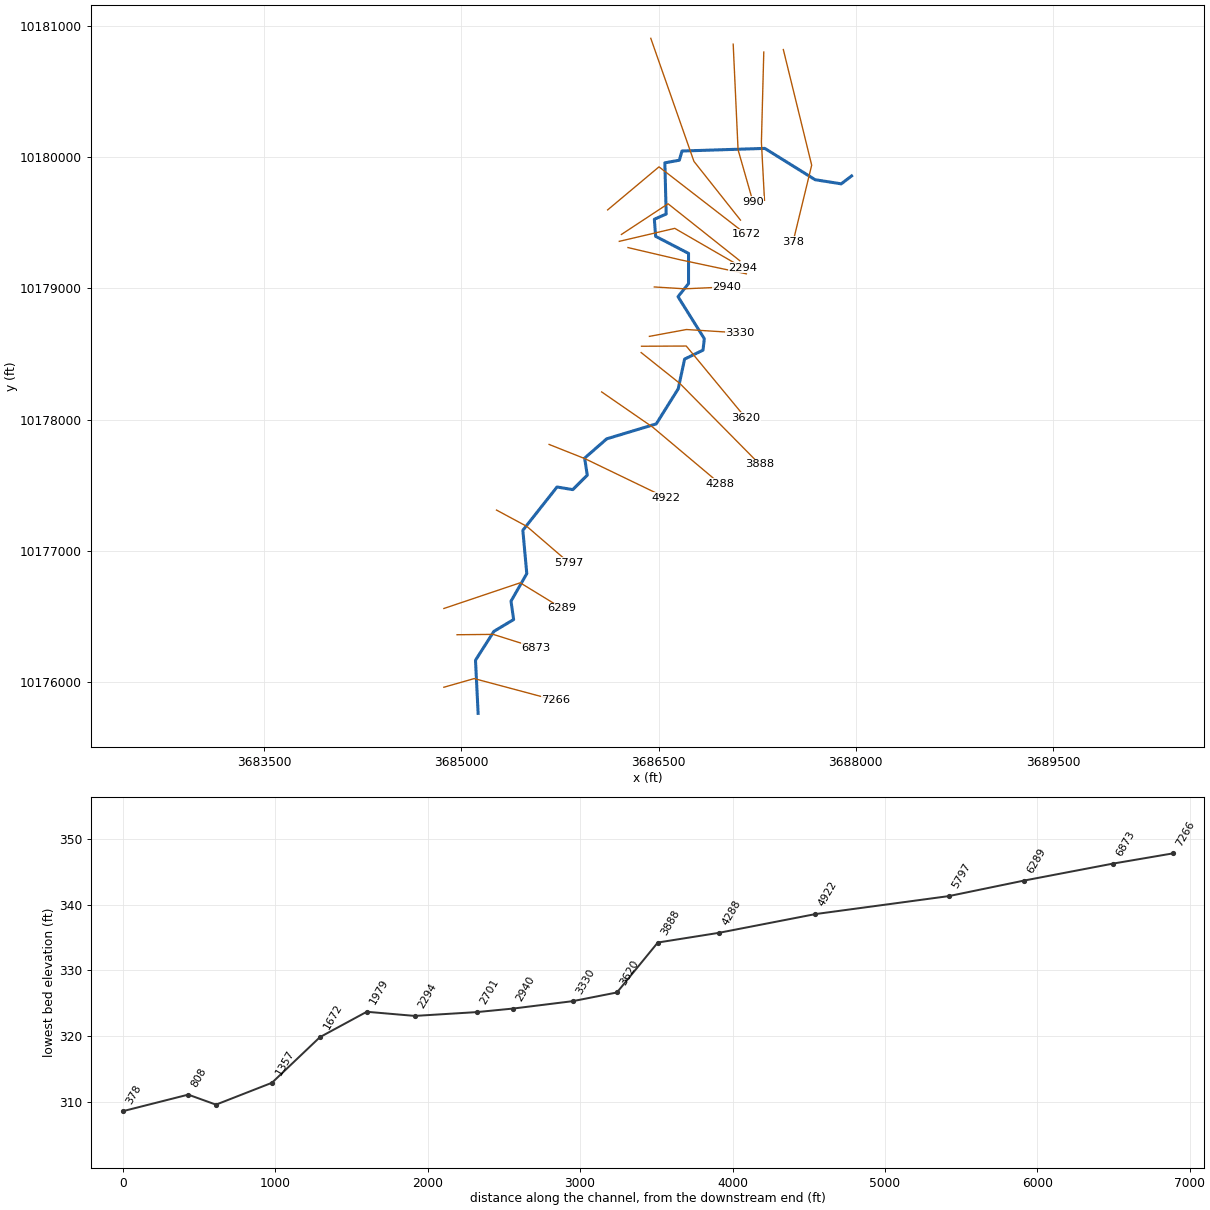
--- CCLC 071.prj (project) ---

Proj Title=CCLC 071 Base Level Engineering
Current Plan=p01
Default Exp/Contr=0.3,0.1
English Units
Geom File=g01
Flow File=f01
Flow File=f02
Plan File=p01
Y Axis Title=Elevation
X Axis Title(PF)=Main Channel Distance
X Axis Title(XS)=Station
BEGIN DESCRIPTION:
CCLC 071
END DESCRIPTION:
DSS Export Rating Curves= 0
DSS Export Rating Curve Sorted= 0
DSS Export Volume Flow Curves= 0
DXF OffsetX= 0
DXF OffsetY= 0
DXF ScaleX= 1
DXF ScaleY= 10

--- CCLC 071.p01 (plan) ---

Plan Title=Multiple Run
Short Identifier=Multiple
Geom File=g01
Flow File=f01
Subcritical Flow
K Sum by GR= 0
Std Step Tol= 0.01
Critical Tol= 0.01
Num of Std Step Trials= 20
Max Error Tol= 0.3
Flow Tol Ratio= 0.001
Split Flow NTrial= 30
Split Flow Tol= 0.02
Split Flow Ratio= 0.02
Log Output Level= 0
Friction Slope Method= 1
Unsteady Friction Slope Method= 2
Unsteady Bridges Friction Slope Method= 1
Parabolic Critical Depth
Global Vel Dist=  1 , 1 , 1
Global Log Level= 0
CheckData=True
Encroach Param= -1, 0, 0, 0
BEGIN DESCRIPTION:
Multiple Run
END DESCRIPTION:

--- CCLC 071.f01 (steady flow) ---

Flow Title=Multiple
Program Version=4.10
Number of Profiles= 7
Profile Names=10-year,25-year,50-year,1pct_min,100-year,1pct_plu,500-year
River Rch & RM=CCLC 071,Reach-1         ,7266
     562     758    1021     453    1368    4131    2535
River Rch & RM=CCLC 071,Reach-1         ,1357
    1818    2603    3648    1675    5057   15272   10072
Boundary for River Rch & Prof#=CCLC 071,Reach-1         , 1
Up Type= 0
Dn Type= 3
Dn Slope=0.006
Boundary for River Rch & Prof#=CCLC 071,Reach-1         , 2
Up Type= 0
Dn Type= 3
Dn Slope=0.006
Boundary for River Rch & Prof#=CCLC 071,Reach-1         , 3
Up Type= 0
Dn Type= 3
Dn Slope=0.006
Boundary for River Rch & Prof#=CCLC 071,Reach-1         , 4
Up Type= 0
Dn Type= 3
Dn Slope=0.006
Boundary for River Rch & Prof#=CCLC 071,Reach-1         , 5
Up Type= 0
Dn Type= 3
Dn Slope=0.006
Boundary for River Rch & Prof#=CCLC 071,Reach-1         , 6
Up Type= 0
Dn Type= 3
Dn Slope=0.006
Boundary for River Rch & Prof#=CCLC 071,Reach-1         , 7
Up Type= 0
Dn Type= 3
Dn Slope=0.006
DSS Import GetInterval= 0
DSS Import GetPeak= 0
DSS Import FillOption= 0

--- CCLC 071.f02 (steady flow) ---

Flow Title=Orig_BLE_Flows
Program Version=4.10
Number of Profiles= 7
Profile Names=10-year,25-year,50-year,1pct_min,100-year,1pct_plu,500-year
River Rch & RM=CCLC 071,Reach-1         ,7266
     562     743     888     348    1052    3176    1474
River Rch & RM=CCLC 071,Reach-1         ,1357
    1818    2552    3172    1288    3890   11748    5856
Boundary for River Rch & Prof#=CCLC 071,Reach-1         , 1
Up Type= 0
Dn Type= 3
Dn Slope=0.005
Boundary for River Rch & Prof#=CCLC 071,Reach-1         , 2
Up Type= 0
Dn Type= 3
Dn Slope=0.005
Boundary for River Rch & Prof#=CCLC 071,Reach-1         , 3
Up Type= 0
Dn Type= 3
Dn Slope=0.005
Boundary for River Rch & Prof#=CCLC 071,Reach-1         , 4
Up Type= 0
Dn Type= 3
Dn Slope=0.005
Boundary for River Rch & Prof#=CCLC 071,Reach-1         , 5
Up Type= 0
Dn Type= 3
Dn Slope=0.005
Boundary for River Rch & Prof#=CCLC 071,Reach-1         , 6
Up Type= 0
Dn Type= 3
Dn Slope=0.005
Boundary for River Rch & Prof#=CCLC 071,Reach-1         , 7
Up Type= 0
Dn Type= 3
Dn Slope=0.005
DSS Import GetInterval= 0
DSS Import GetPeak= 0
DSS Import FillOption= 0

--- CCLC 071.g01 (geometry) ---

Geom Title=Existing Conditions
Program Version=4.10

River Reach=CCLC 071        ,Reach-1
Reach XY= 30
      3685128.23     10175761.84      3685108.23     10176166.84
      3685248.23     10176386.84      3685398.23     10176476.84
      3685378.23     10176616.84      3685498.23     10176826.84
      3685468.23     10177156.84      3685728.23     10177486.84
      3685848.23     10177466.84      3685958.23     10177576.84
      3685938.23     10177706.84      3686106.02      10177853.7
      3686482.75     10177967.63      3686649.85     10178234.98
      3686698.46     10178461.32      3686838.23      10178529.7
      3686848.23     10178616.84      3686648.23     10178936.84
      3686728.23     10179036.84      3686728.23     10179266.84
      3686478.23     10179396.84      3686468.23     10179526.84
      3686558.23     10179566.84      3686548.23     10179956.84
      3686658.23     10179976.84      3686678.23     10180046.84
      3687308.23     10180066.84      3687690.72     10179828.24
      3687889.42     10179796.78      3687968.23     10179856.84

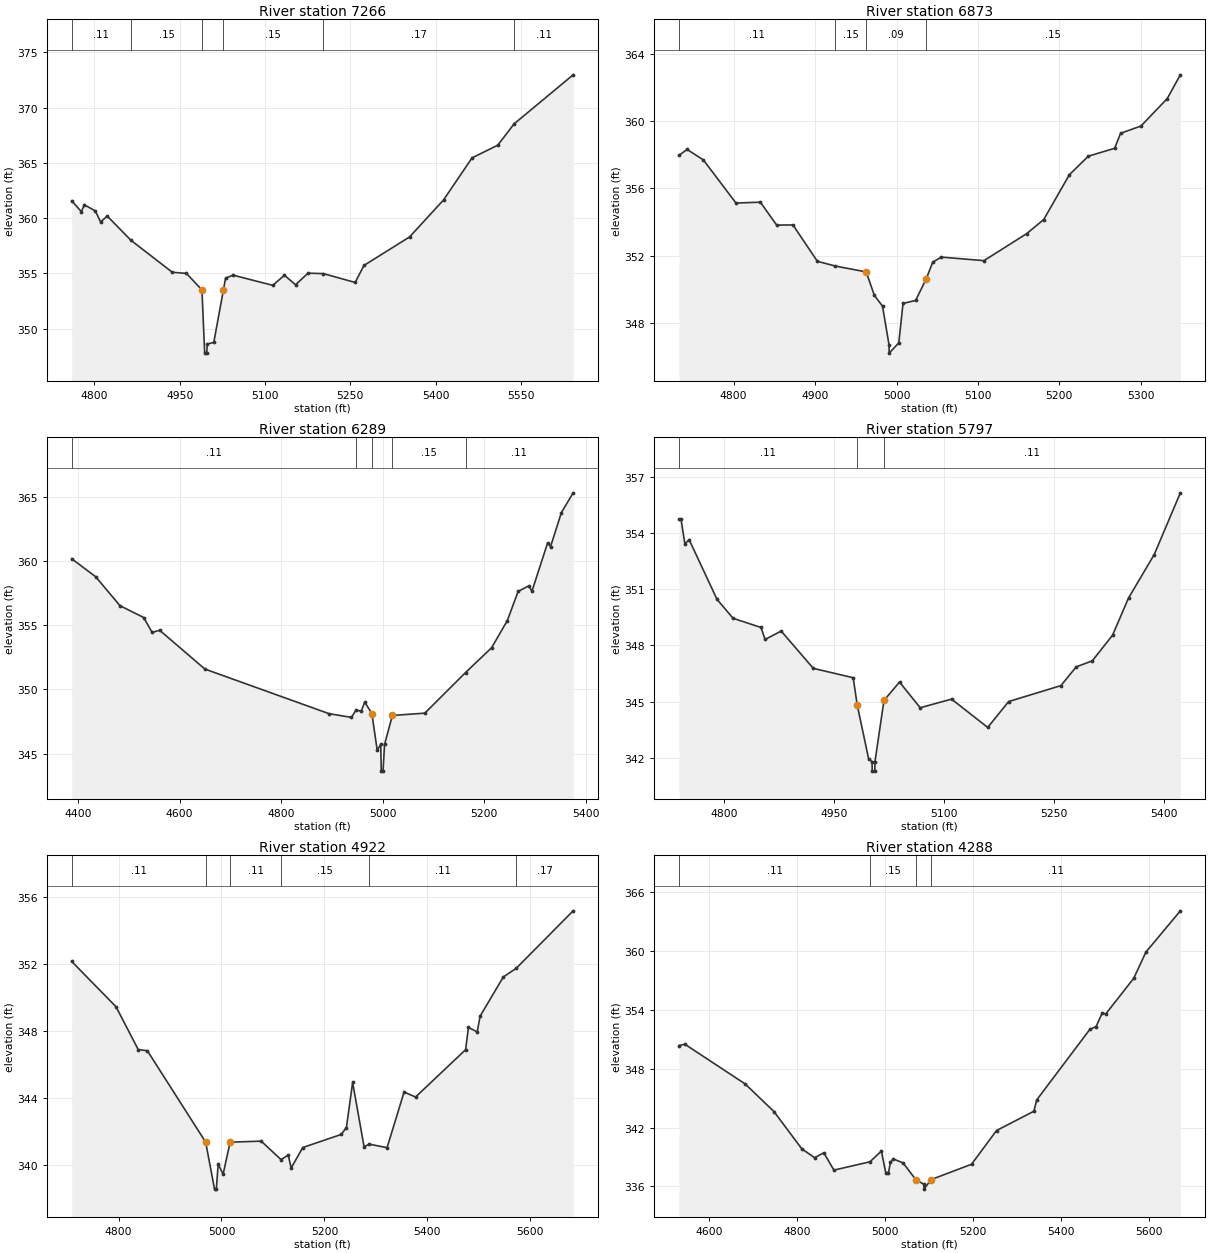
Type RM Length L Ch R = 1 ,7266    ,393,393,393
BEGIN DESCRIPTION:
CCLC 071 14.0
END DESCRIPTION:
XS GIS Cut Line= 3
      3684867.84     10175961.07      3685098.23     10176026.84
      3685717.84     10175861.08
#Sta/Elev= 30
  4760.4  361.56  4777.3  360.58  4782.5   361.2    4802  360.64  4811.1  359.65
  4822.8  360.18  4864.6  357.98  4937.2  355.09    4962  354.99  4989.2  353.49
    4994  347.77  4997.5  347.77  4998.6   348.6    5010  348.74 5026.83353.4586
  5030.7  354.56  5043.9  354.83  5113.5  353.91  5134.2  354.82  5153.7  353.96
  5175.6  355.01  5202.5  354.97  5258.4  354.17  5273.9  355.71    5354  358.29
  5413.7  361.64  5463.8  365.45    5509   366.6  5537.7  368.53  5641.4  372.97
#Mann= 6 ,-1 , 0
  4760.4     .11       0  4864.6     .15       0  4989.2     .09       0
 5026.83     .15       0  5202.5     .17       0  5537.7     .11       0
Bank Sta=4989.2,5026.83
XS Rating Curve= 0 ,0
Exp/Cntr=0.3,0.1

Type RM Length L Ch R = 1 ,6873    ,584,584,584
BEGIN DESCRIPTION:
CCLC 071 13.0
END DESCRIPTION:
XS GIS Cut Line= 3
      3684967.88     10176361.07       3685243.3     10176363.76
      3685567.81     10176261.08
#Sta/Elev= 30
  4732.8  357.96  4742.8  358.31  4762.8  357.69  4802.8  355.13  4832.8  355.18
  4852.8  353.82  4872.8  353.83  4902.8  351.67  4924.8  351.39  4962.8  351.04
  4972.8  349.65  4982.8  349.01  4990.8  346.72    4991  346.22  5002.8  346.83
    5008  349.17  5023.5  349.35  5036.5  350.63  5044.5  351.62    5055  351.92
  5107.4  351.71  5159.8  353.31  5180.8  354.15  5212.3  356.81  5235.6  357.91
  5267.9  358.38  5275.2  359.27  5300.2   359.7  5332.5  361.33  5348.6  362.74
#Mann= 4 ,-1 , 0
  4732.8     .11       0  4924.8     .15       0  4962.8     .09       0
  5036.5     .15       0
Bank Sta=4962.8,5036.5
XS Rating Curve= 0 ,0
Exp/Cntr=0.3,0.1

Type RM Length L Ch R = 1 ,6289    ,492,492,492
BEGIN DESCRIPTION:
CCLC 071 12.0
END DESCRIPTION:
XS GIS Cut Line= 3
      3684867.86     10176561.07      3685448.23     10176756.84
      3685767.84     10176561.08
#Sta/Elev= 30
  4387.5  360.16  4434.7  358.76  4482.5  356.51  4529.1  355.59  4545.8  354.43
  4560.6   354.6  4649.7  351.58  4894.1  348.11  4938.3  347.82  4947.4   348.4
  4957.4   348.3  4964.5  349.01  4978.5  348.12    4989  345.27    4996  345.72
    4997  343.64  5000.5  343.64  5003.5  345.72  5018.9  347.97  5082.8  348.15
    5163  351.31  5214.3  353.24  5245.2  355.35  5266.5  357.62  5287.8  358.06
  5293.6  357.62  5324.5  361.39  5330.4  361.11  5351.7  363.75  5374.8  365.29
#Mann= 5 ,-1 , 0
  4387.5     .11       0  4947.4     .15       0  4978.5     .09       0
  5018.9     .15       0    5163     .11       0
Bank Sta=4978.5,5018.9
XS Rating Curve= 0 ,0
Exp/Cntr=0.3,0.1

Type RM Length L Ch R = 1 ,5797    ,875,875,875
BEGIN DESCRIPTION:
CCLC 071 11.0
END DESCRIPTION:
XS GIS Cut Line= 3
      3685267.88     10177311.05      3685498.23     10177186.84
      3685817.82      10176911.1
#Sta/Elev= 30
  4738.3  354.73  4741.1  354.73  4746.4   353.4  4752.1  353.64  4790.2  350.45
  4812.1  349.44  4850.2  348.95  4855.8  348.31  4877.7  348.76  4921.5  346.77
  4975.9  346.27  4981.5   344.8  4996.9  341.96  5001.6  341.79  5001.9  341.29
  5005.4  341.29  5005.6  341.79  5017.9  345.06  5039.1  346.04  5067.3  344.67
  5110.1  345.13  5159.4  343.62  5187.9     345  5259.2  345.85  5280.1  346.85
    5302  347.17  5329.7  348.54  5351.4  350.52  5386.5  352.84  5422.1  356.13
#Mann= 3 , 0 , 0
  4738.3     .11       0  4981.5     .06       0  5017.9     .11       0
Bank Sta=4981.5,5017.9
XS Rating Curve= 0 ,0
Exp/Cntr=0.3,0.1

Type RM Length L Ch R = 1 ,4922    ,634,634,634
BEGIN DESCRIPTION:
CCLC 071 10.0
END DESCRIPTION:
XS GIS Cut Line= 3
      3685667.85     10177811.07      3685941.22      10177702.3
      3686553.69     10177406.45
#Sta/Elev= 30
    4709  352.13  4795.1  349.43  4838.2  346.88    4856  346.81  4969.3  341.36
  4986.5  338.56    4990  338.56  4993.6  340.05  5003.2  339.45  5016.8  341.36
  5077.2  341.42  5115.8  340.32  5129.8  340.59  5135.4  339.82    5158  341.04
  5232.7  341.82  5242.8  342.23  5254.9  344.92  5277.1  341.09  5287.4  341.24
  5321.8  341.03  5354.9  344.35  5377.1  344.05  5474.4  346.87    5480   348.2
    5497  347.93  5502.6  348.87  5547.8  351.21  5572.7  351.72  5683.4  355.15
#Mann= 6 ,-1 , 0
    4709     .11       0  4969.3     .06       0  5016.8     .11       0
  5115.8     .15       0  5287.4     .11       0  5572.7     .17       0
Bank Sta=4969.3,5016.8
XS Rating Curve= 0 ,0
Exp/Cntr=0.3,0.1

Type RM Length L Ch R = 1 ,4288    ,400,400,400
BEGIN DESCRIPTION:
CCLC 071 9.0
END DESCRIPTION:
XS GIS Cut Line= 3
      3686067.84     10178211.08      3686456.84     10177941.89
      3686967.82      10177511.1
#Sta/Elev= 30
  4530.6  350.37  4544.1   350.5  4681.3  346.45  4746.9  343.63  4810.3  339.82
  4839.4  338.92  4860.4  339.42  4883.3  337.65  4965.4   338.5  4991.5   339.6
  5001.2   337.4  5007.6   337.4  5012.1  338.46  5018.6  338.79  5040.7  338.39
 5070.07336.6663  5088.1  336.21  5088.4  335.71  5104.4  336.68  5196.7  338.25
  5253.5  341.69  5338.5  343.66  5345.1  344.82    5466  352.02  5480.2  352.31
  5494.5  353.72    5502  353.58    5566  357.24  5593.6  359.91    5672  364.12
#Mann= 4 ,-1 , 0
  4530.6     .11       0  4965.4     .15       0 5070.07     .09       0
  5104.4     .11       0
Bank Sta=5070.07,5104.4
XS Rating Curve= 0 ,0
Exp/Cntr=0.3,0.1

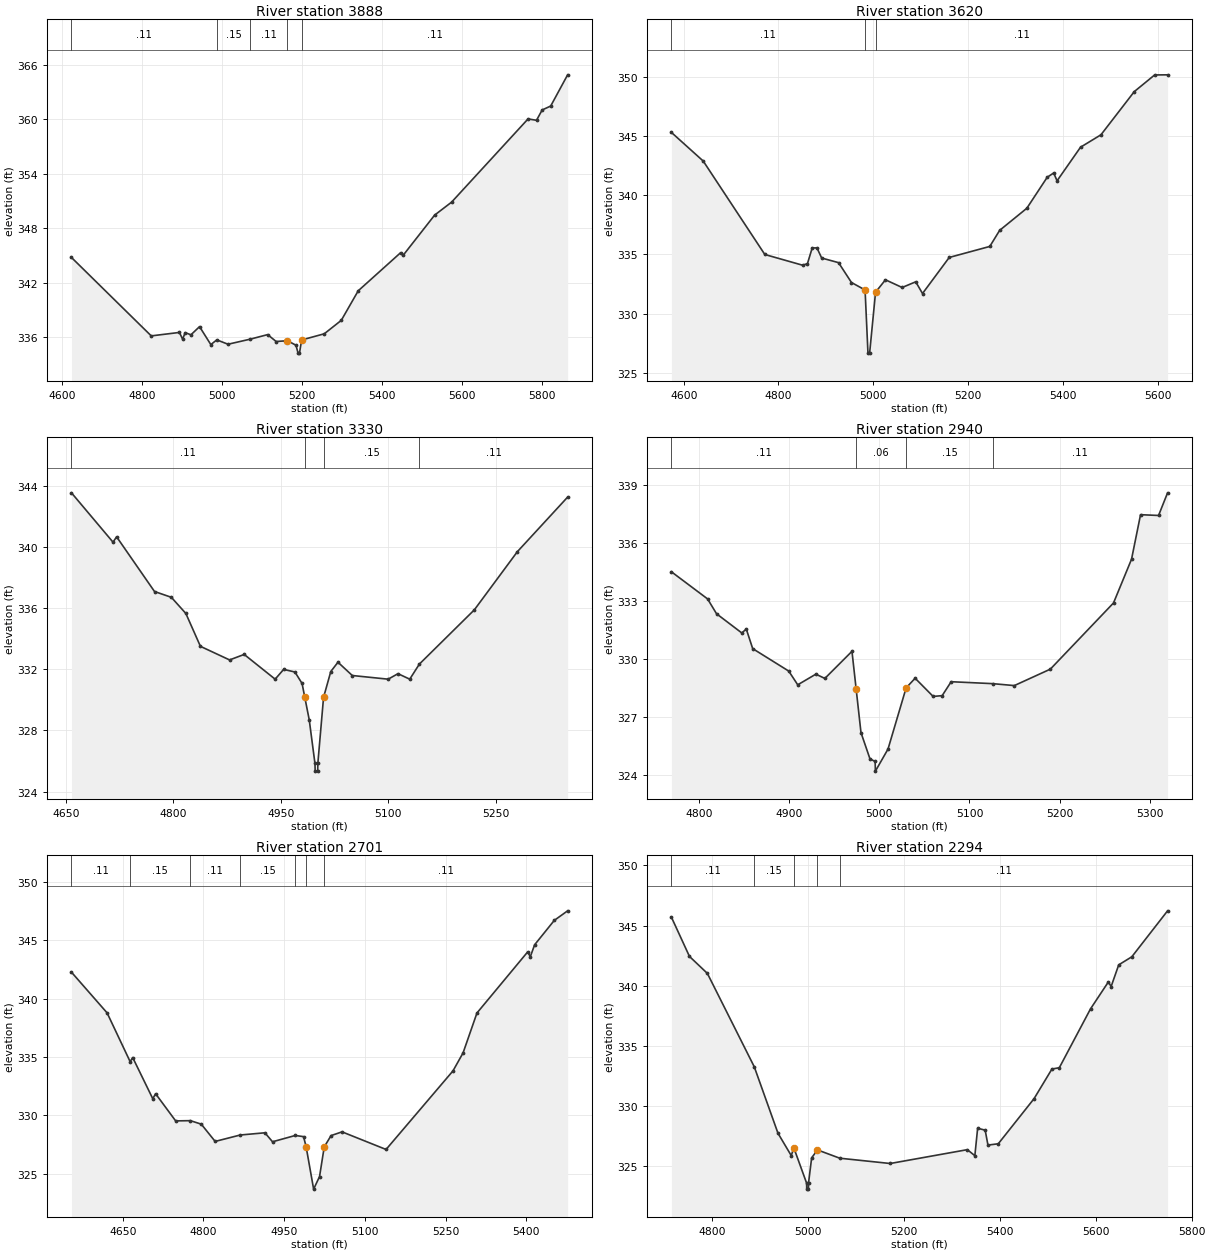
Type RM Length L Ch R = 1 ,3888    ,268,268,268
BEGIN DESCRIPTION:
CCLC 071 8.0
END DESCRIPTION:
XS GIS Cut Line= 3
      3686367.88     10178511.05        3686662.       10178276.
      3687267.82      10177661.1
#Sta/Elev= 30
  4623.5  344.78  4822.8  336.14  4893.2  336.52  4901.2  335.78  4907.6   336.5
    4922  336.26  4943.5  337.16  4971.7  335.18  4986.6   335.7  5014.7  335.22
  5070.2  335.78  5113.7  336.28  5134.9  335.52  5163.2  335.61  5184.4  335.11
  5189.7  334.24  5193.2  334.24  5198.6  335.69  5255.1  336.37  5297.6  337.85
    5340  341.11    5446  345.31  5453.1  345.07  5530.9  349.45  5573.3  350.88
  5764.3  360.05  5785.5   359.9  5799.6  361.04  5820.9  361.47  5863.2  364.91
#Mann= 5 ,-1 , 0
  4623.5     .11       0  4986.6     .15       0  5070.2     .11       0
  5163.2     .09       0  5198.6     .11       0
Bank Sta=5163.2,5198.6
XS Rating Curve= 0 ,0
Exp/Cntr=0.3,0.1

Type RM Length L Ch R = 1 ,3620    ,290,290,290
BEGIN DESCRIPTION:
Mapping XS d0bce974
END DESCRIPTION:
XS GIS Cut Line= 3
      3686370.71     10178559.29      3686711.02     10178560.86
      3687160.71     10178015.59
#Sta/Elev= 30
  4574.1  345.32  4641.2   342.9  4771.2     335  4851.2  334.09  4861.2  334.23
  4871.2  335.55  4881.2  335.56  4891.2   334.7  4926.8  334.31  4954.1  332.63
  4982.8     332  4988.9  326.66  4992.4  326.66  5004.9  331.81  5025.8  332.86
    5061  332.21  5089.7  332.69    5104   331.7  5160.4  334.75    5246  335.68
  5266.8  337.04  5324.2  338.91  5367.2  341.53  5380.8  341.89    5388  341.23
  5437.5  344.07  5480.6  345.12  5550.9  348.77  5593.9  350.18  5621.2  350.19
#Mann= 3 , 0 , 0
  4574.1     .11       0  4982.8     .06       0  5004.9     .11       0
Bank Sta=4982.8,5004.9
XS Rating Curve= 0 ,0
Exp/Cntr=0.3,0.1

Type RM Length L Ch R = 1 ,3330    ,390,390,390
BEGIN DESCRIPTION:
CCLC 071 7.0
END DESCRIPTION:
XS GIS Cut Line= 3
      3686430.82      10178634.6      3686712.05     10178686.68
      3687117.83     10178661.07
#Sta/Elev= 30
  4657.7  343.56  4715.7  340.33  4720.7  340.68  4773.6   337.1  4797.1  336.72
  4817.4  335.66  4837.7  333.51  4878.4  332.62  4898.8  332.98    4942  331.36
  4953.9     332  4969.6  331.83  4979.6  331.08 4983.42330.1709  4989.6   328.7
  4997.6  325.84  4997.9  325.34  5001.4  325.34  5001.6  325.84  5009.6  330.17
  5019.7  331.86  5029.7  332.47  5049.7   331.6  5099.8  331.36  5113.5  331.72
  5129.9  331.36  5143.4  332.35  5220.1   335.9  5280.2  339.71  5350.3  343.28
#Mann= 4 ,-1 , 0
  4657.7     .11       0 4983.42     .09       0  5009.6     .15       0
  5143.4     .11       0
Bank Sta=4983.42,5009.6
XS Rating Curve= 0 ,0
Exp/Cntr=0.3,0.1

Type RM Length L Ch R = 1 ,2940    ,239,239,239
BEGIN DESCRIPTION:
CCLC 071 6.0
END DESCRIPTION:
XS GIS Cut Line= 3
      3686467.87     10179011.07      3686698.23     10178996.84
      3687017.81     10179011.07
#Sta/Elev= 30
  4769.2  334.52  4809.3  333.12  4819.3  332.35  4847.3  331.36  4852.3  331.56
  4859.4  330.55  4899.4  329.39  4909.4  328.68  4929.5  329.23  4939.5  329.01
  4969.6  330.41 4974.23328.4655  4979.6  326.21  4989.6  324.85  4995.3  324.72
  4995.6  324.22  5009.6  325.36  5029.7  328.52  5039.7  329.02  5059.7  328.08
  5069.7  328.12  5079.7  328.84  5125.8  328.74  5149.8  328.64  5189.8  329.49
  5259.9  332.91  5279.9  335.17  5289.9  337.47  5309.9  337.43  5319.9   338.6
#Mann= 4 ,-1 , 0
  4769.2     .11       0 4974.23     .06       0  5029.7     .15       0
  5125.8     .11       0
Bank Sta=4974.23,5029.7
XS Rating Curve= 0 ,0
Exp/Cntr=0.3,0.1

Type RM Length L Ch R = 1 ,2701    ,407,407,407
BEGIN DESCRIPTION:
CCLC 071 5.0
END DESCRIPTION:
XS GIS Cut Line= 3
      3686267.86     10179311.07      3686665.18     10179217.93
      3687167.86     10179111.07
#Sta/Elev= 30
  4554.7  342.28  4620.9  338.79  4663.7  334.61  4668.5  334.96  4705.8  331.43
    4711  331.86  4748.3  329.53  4775.7  329.55  4795.9  329.25  4821.7  327.77
  4868.3  328.32  4914.2  328.51  4928.3  327.74  4970.6  328.28    4986  328.18
 4990.75327.3138  5004.7  323.68  5015.7  324.76 5024.42327.3009  5037.1  328.27
  5057.5  328.59  5139.3  327.08  5263.7  333.82  5282.4  335.36  5308.2  338.78
  5402.3  344.01  5407.4  343.61  5415.4  344.63  5451.9  346.72  5476.7  347.54
#Mann= 7 ,-1 , 0
  4554.7     .11       0  4663.7     .15       0  4775.7     .11       0
  4868.3     .15       0  4970.6     .11       0 4990.75     .06       0
 5024.42     .11       0
Bank Sta=4990.75,5024.42
XS Rating Curve= 0 ,0
Exp/Cntr=0.3,0.1

Type RM Length L Ch R = 1 ,2294    ,315,315,315
BEGIN DESCRIPTION:
Mapping XS b61bff3f
END DESCRIPTION:
XS GIS Cut Line= 3
      3686201.64     10179358.55      3686623.51     10179457.51
      3687143.03     10179156.19
#Sta/Elev= 30
  4715.9   345.7  4753.5  342.44  4790.8  341.03  4888.5  333.27    4938  327.74
  4965.7  325.88  4970.8  326.55  4997.6   323.6  4997.9   323.1  5001.4   323.1
  5001.6   323.6  5008.1   325.7  5020.2  326.36  5066.7  325.67  5171.8  325.23
  5332.5  326.38  5348.2  325.88    5354  328.16  5369.7     328  5375.5  326.76
    5397  326.87  5471.6  330.62  5508.8  333.08  5524.2  333.19  5589.2  338.08
  5626.4  340.32  5632.2  339.94    5648  341.74  5675.3  342.41  5749.8  346.23
#Mann= 5 ,-1 , 0
  4715.9     .11       0  4888.5     .15       0  4970.8     .09       0
  5020.2     .15       0  5066.7     .11       0
Bank Sta=4970.8,5020.2
XS Rating Curve= 0 ,0
Exp/Cntr=0.3,0.1

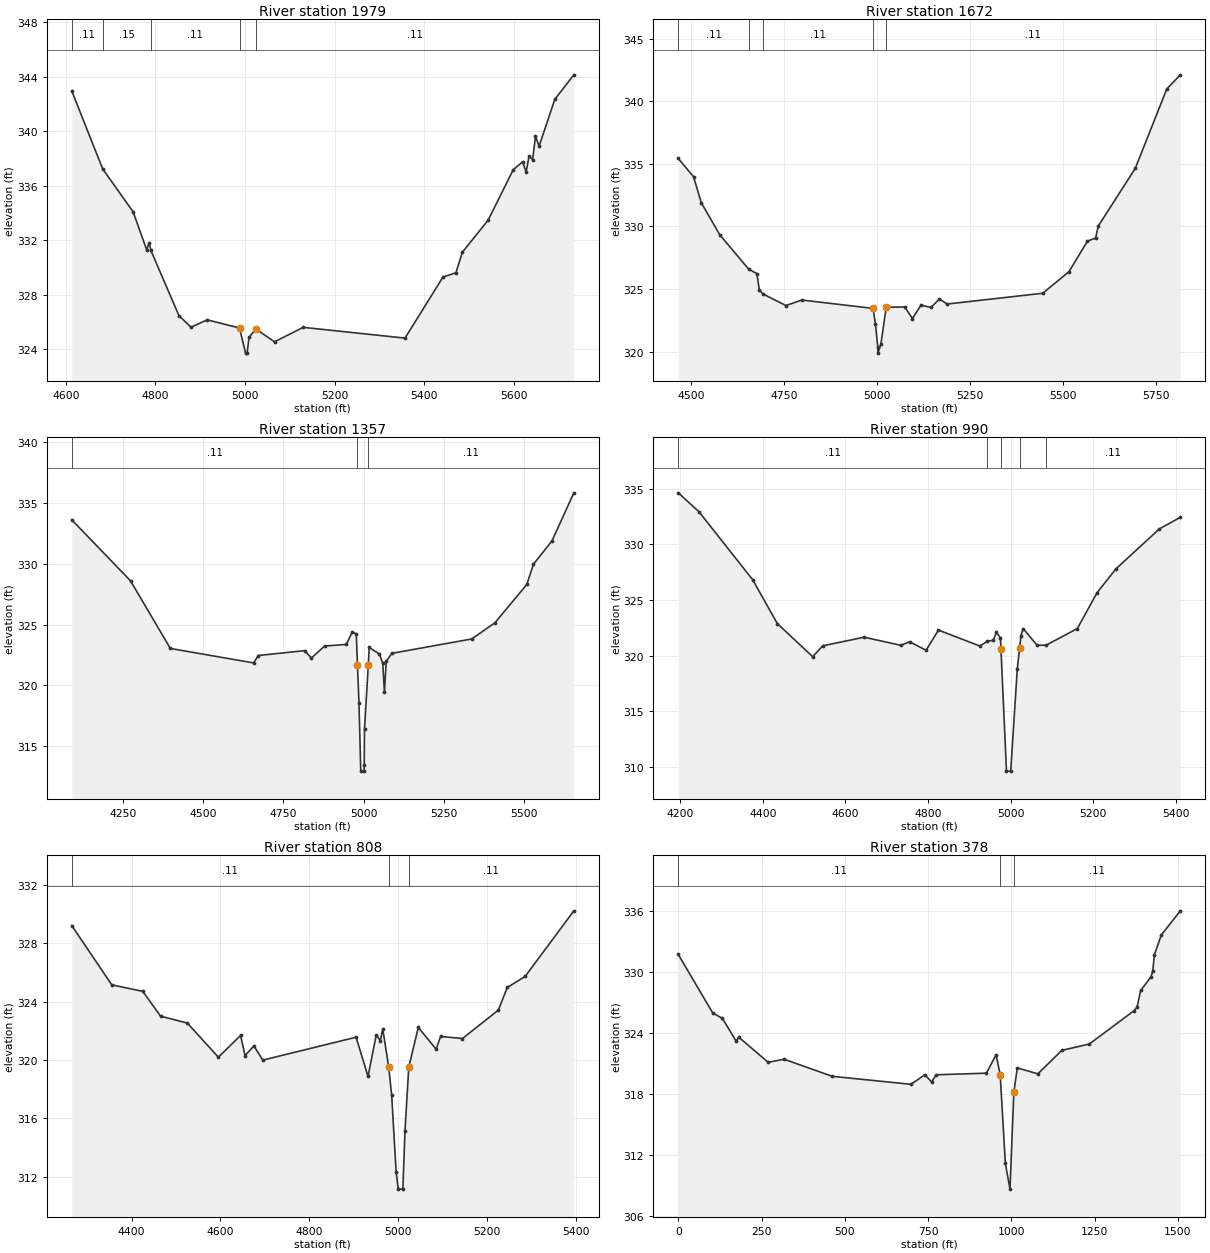
Type RM Length L Ch R = 1 ,1979    ,307,307,307
BEGIN DESCRIPTION:
CCLC 071 4.0
END DESCRIPTION:
XS GIS Cut Line= 3
      3686217.87     10179411.08      3686572.47     10179644.91
      3687117.81      10179211.1
#Sta/Elev= 30
    4613  342.95  4682.1  337.23    4750  334.09  4780.1  331.32  4786.1  331.83
  4789.7  331.26  4852.4  326.48  4879.4  325.63  4915.6  326.17  4987.8  325.57
  5001.2  323.73  5004.7  323.73  5008.9  324.88    5024   325.5  5065.9  324.56
    5130  325.62  5357.4  324.83  5442.3  329.31  5471.2  329.62  5485.6  331.13
    5543  333.47  5599.3  337.18  5620.1  337.75  5628.1  337.01  5634.5  338.17
  5642.6  337.91  5648.9  339.62    5657   338.9  5692.2  342.34  5734.6  344.13
#Mann= 5 ,-1 , 0
    4613     .11       0  4682.1     .15       0  4789.7     .11       0
  4987.8     .06       0    5024     .11       0
Bank Sta=4987.8,5024
XS Rating Curve= 0 ,0
Exp/Cntr=0.3,0.1

Type RM Length L Ch R = 1 ,1672    ,315,315,315
BEGIN DESCRIPTION:
CCLC 071 3.0
END DESCRIPTION:
XS GIS Cut Line= 3
      3686113.12     10179598.16      3686503.72     10179926.26
      3687167.81      10179411.1
#Sta/Elev= 30
  4465.7  335.42  4506.8  333.97  4527.6   331.9  4577.1  329.34  4655.4  326.58
  4677.2  326.23  4683.7  324.96  4693.1  324.61  4755.3  323.68  4798.2  324.12
  4989.9  323.45  4996.2   322.2  5002.4  320.38  5002.6  319.88  5010.7  320.58
  5025.2  323.54    5075  323.57  5095.8  322.64  5118.5  323.71  5145.6  323.53
  5168.2   324.2    5189   323.8  5446.1  324.66  5516.7  326.38  5566.5  328.82
  5588.5  329.07  5595.5  330.02  5695.1  334.63  5780.1  340.98  5816.3   342.1
#Mann= 5 ,-1 , 0
  4465.7     .11       0  4655.4     .15       0  4693.1     .11       0
  4989.9     .06       0  5025.2     .11       0
Bank Sta=4989.9,5025.2
XS Rating Curve= 0 ,0
Exp/Cntr=0.3,0.1

Type RM Length L Ch R = 1 ,1357    ,367,367,367
BEGIN DESCRIPTION:
Mapping XS c249fafb
END DESCRIPTION:
XS GIS Cut Line= 3
      3686441.21     10180905.45      3686769.34     10179967.93
      3687123.19     10179520.41
#Sta/Elev= 30
  4091.1  333.62  4274.1   328.6  4398.2  323.04  4657.3  321.85  4672.2  322.46
  4816.2  322.86  4837.4  322.25  4878.8  323.24  4946.1  323.37  4964.5  324.39
  4977.2  324.24 4981.05321.6721  4985.7  318.57  4991.2  312.95  5001.5  312.95
    5002  313.45  5002.9  316.42  5014.7321.6719  5017.5  323.12  5049.3  322.58
  5059.7  321.82    5065  319.45  5070.5  321.98  5088.4  322.64  5336.8  323.82
    5409  325.15  5508.3   328.3  5529.2  329.97  5586.9  331.89  5654.9  335.84
#Mann= 3 , 0 , 0
  4091.1     .11       0 4981.05     .07       0  5014.7     .11       0
Bank Sta=4981.05,5014.7
XS Rating Curve= 0 ,0
Exp/Cntr=0.3,0.1

Type RM Length L Ch R = 1 ,990     ,182,182,182
BEGIN DESCRIPTION:
CCLC 071 2.0
END DESCRIPTION:
XS GIS Cut Line= 3
      3687067.85     10180861.05      3687104.88      10180056.7
      3687217.84     10179661.12
#Sta/Elev= 30
  4194.8  334.63  4244.8  332.94    4375  326.83    4435  322.88  4520.6  319.91
  4545.1  320.89  4645.3  321.66  4734.4  320.93  4755.4  321.25  4795.4  320.49
  4825.4   322.3  4925.6  320.87  4943.9  321.29  4958.3  321.39  4965.6  322.09
  4975.6  321.61 4976.76320.6451  4990.2  309.63  5000.5  309.63  5016.3  318.79
 5021.96320.6893  5025.3  321.81  5030.5  322.44  5064.3  320.94  5086.3  320.94
  5161.9  322.44  5209.9  325.67  5255.4   327.8  5360.7  331.39  5411.4  332.43
#Mann= 5 ,-1 , 0
  4194.8     .11       0  4943.9     .15       0 4976.76     .09       0
 5021.96     .15       0  5086.3     .11       0
Bank Sta=4976.76,5021.96
XS Rating Curve= 0 ,0
Exp/Cntr=0.3,0.1

Type RM Length L Ch R = 1 ,808     ,430,430,430
BEGIN DESCRIPTION:
Mapping XS 2e19f1c6
END DESCRIPTION:
XS GIS Cut Line= 3
      3687300.45     10180801.04       3687282.4     10180115.33
      3687305.86      10179671.4
#Sta/Elev= 30
  4265.5  329.21  4355.5  325.15  4425.5   324.7  4465.5     323  4525.6  322.53
  4595.6  320.19  4645.6  321.68  4655.6   320.3  4675.6  320.96  4695.6  319.99
  4905.7  321.56  4932.5  318.87  4951.1  321.71  4960.4  321.32  4965.7  322.14
 4979.19319.5041  4985.8  317.58  4995.8  312.35  5000.6  311.15    5011  311.15
  5015.8  315.16 5024.39319.5239  5045.8  322.23  5085.9  320.74  5095.9  321.61
  5145.2  321.47  5226.1  323.42  5246.1  324.97  5286.2  325.72    5396  330.22
#Mann= 3 , 0 , 0
  4265.5     .11       0 4979.19     .06       0 5024.39     .11       0
Bank Sta=4979.19,5024.39
XS Rating Curve= 0 ,0
Exp/Cntr=0.3,0.1

Type RM Length L Ch R = 1 ,378     ,0,0,0
BEGIN DESCRIPTION:
CCLC 071 1.0
END DESCRIPTION:
XS GIS Cut Line= 3
      3687449.09     10180820.05      3687664.72     10179939.09
       3687523.2      10179354.9
#Sta/Elev= 30
       0  331.76   103.5     326   132.8  325.45     174  323.21   181.6  323.61
     270  321.13   318.1  321.43   462.2  319.75     699  318.96   740.2   319.9
   760.8   319.2   774.6   319.9   925.5  320.06   954.3  321.88   966.7  319.91
   982.2  311.17   996.1  308.63  1007.8  318.22  1018.1  320.58  1079.7  319.99
  1151.9  322.31  1234.2  322.93  1367.9   326.2  1377.6  326.57  1388.5  328.21
  1419.4  329.55  1424.6   330.1  1429.7  331.72  1450.3  333.67  1507.5  336.06
#Mann= 3 ,-1 , 0
       0     .11       0   966.7    .065       0  1007.8     .11       0
Bank Sta=966.7,1007.8
XS Rating Curve= 0 ,0
Exp/Cntr=0.3,0.1

Chan Stop Cuts=-1
Use User Specified Reach Order=0
Composite Channel Slope=5