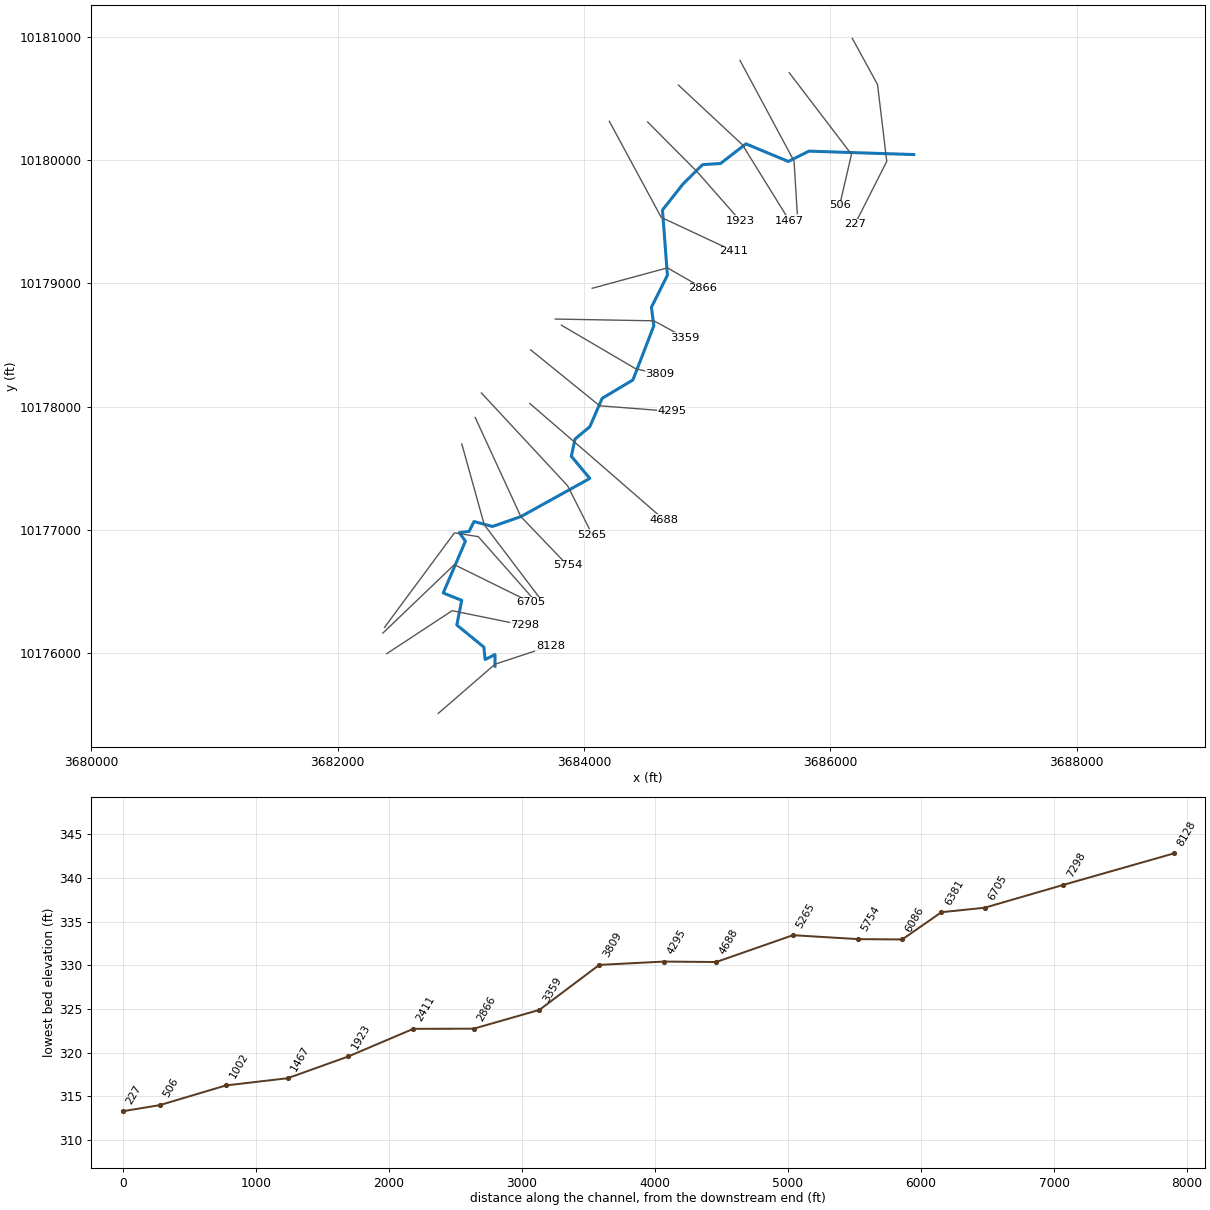
--- CCLC 072.prj (project) ---

Proj Title=CCLC 072 Base Level Engineering
Current Plan=p01
Default Exp/Contr=0.3,0.1
English Units
Geom File=g01
Flow File=f01
Flow File=f02
Plan File=p01
Y Axis Title=Elevation
X Axis Title(PF)=Main Channel Distance
X Axis Title(XS)=Station
BEGIN DESCRIPTION:
CCLC 072
END DESCRIPTION:
DSS Export Rating Curves= 0
DSS Export Rating Curve Sorted= 0
DSS Export Volume Flow Curves= 0
DXF OffsetX= 0
DXF OffsetY= 0
DXF ScaleX= 1
DXF ScaleY= 10

--- CCLC 072.p01 (plan) ---

Plan Title=Multiple Run
Short Identifier=Multiple
Geom File=g01
Flow File=f01
Subcritical Flow
K Sum by GR= 0
Std Step Tol= 0.01
Critical Tol= 0.01
Num of Std Step Trials= 20
Max Error Tol= 0.3
Flow Tol Ratio= 0.001
Split Flow NTrial= 30
Split Flow Tol= 0.02
Split Flow Ratio= 0.02
Log Output Level= 0
Friction Slope Method= 1
Unsteady Friction Slope Method= 2
Unsteady Bridges Friction Slope Method= 1
Parabolic Critical Depth
Global Vel Dist=  1 , 1 , 1
Global Log Level= 0
CheckData=True
Encroach Param= -1, 0, 0, 0
BEGIN DESCRIPTION:
Multiple Run
END DESCRIPTION:

--- CCLC 072.f01 (steady flow) ---

Flow Title=Multiple
Program Version=4.10
Number of Profiles= 7
Profile Names=10-year,25-year,50-year,1pct_min,100-year,1pct_plu,500-year
River Rch & RM=CCLC 072,Reach-1         ,8128
     393     518     687     300     905    2733    1627
River Rch & RM=CCLC 072,Reach-1         ,6086
    1289    1816    2517    1144    3455   10434    6748
River Rch & RM=CCLC 072,Reach-1         ,1923
    1373    1930    2673    1213    3663   11062    7128
Boundary for River Rch & Prof#=CCLC 072,Reach-1         , 1
Up Type= 0
Dn Type= 3
Dn Slope=0.005
Boundary for River Rch & Prof#=CCLC 072,Reach-1         , 2
Up Type= 0
Dn Type= 3
Dn Slope=0.005
Boundary for River Rch & Prof#=CCLC 072,Reach-1         , 3
Up Type= 0
Dn Type= 3
Dn Slope=0.005
Boundary for River Rch & Prof#=CCLC 072,Reach-1         , 4
Up Type= 0
Dn Type= 3
Dn Slope=0.005
Boundary for River Rch & Prof#=CCLC 072,Reach-1         , 5
Up Type= 0
Dn Type= 3
Dn Slope=0.005
Boundary for River Rch & Prof#=CCLC 072,Reach-1         , 6
Up Type= 0
Dn Type= 3
Dn Slope=0.005
Boundary for River Rch & Prof#=CCLC 072,Reach-1         , 7
Up Type= 0
Dn Type= 3
Dn Slope=0.005
DSS Import GetInterval= 0
DSS Import GetPeak= 0
DSS Import FillOption= 0

--- CCLC 072.f02 (steady flow) ---

Flow Title=Orig_BLE_Flows
Program Version=4.10
Number of Profiles= 7
Profile Names=10-year,25-year,50-year,1pct_min,100-year,1pct_plu,500-year
River Rch & RM=CCLC 072,Reach-1         ,8128
     393     508     597     231     696    2103     946
River Rch & RM=CCLC 072,Reach-1         ,6086
    1289    1780    2189     880    2658    8027    3923
River Rch & RM=CCLC 072,Reach-1         ,1923
    1373    1892    2324     933    2818    8509    4144
Boundary for River Rch & Prof#=CCLC 072,Reach-1         , 1
Up Type= 0
Dn Type= 3
Dn Slope=0.005
Boundary for River Rch & Prof#=CCLC 072,Reach-1         , 2
Up Type= 0
Dn Type= 3
Dn Slope=0.005
Boundary for River Rch & Prof#=CCLC 072,Reach-1         , 3
Up Type= 0
Dn Type= 3
Dn Slope=0.005
Boundary for River Rch & Prof#=CCLC 072,Reach-1         , 4
Up Type= 0
Dn Type= 3
Dn Slope=0.005
Boundary for River Rch & Prof#=CCLC 072,Reach-1         , 5
Up Type= 0
Dn Type= 3
Dn Slope=0.005
Boundary for River Rch & Prof#=CCLC 072,Reach-1         , 6
Up Type= 0
Dn Type= 3
Dn Slope=0.005
Boundary for River Rch & Prof#=CCLC 072,Reach-1         , 7
Up Type= 0
Dn Type= 3
Dn Slope=0.005
DSS Import GetInterval= 0
DSS Import GetPeak= 0
DSS Import FillOption= 0

--- CCLC 072.g01 (geometry) ---

Geom Title=Existing Conditions
Program Version=4.10

River Reach=CCLC 072        ,Reach-1
Reach XY= 30
      3683278.23     10175891.84      3683278.23     10175986.84
      3683198.23     10175946.84      3683188.23     10176046.84
      3682968.23     10176226.84      3683008.23     10176426.84
      3682858.23     10176486.84      3683038.23     10176906.84
      3682988.23     10176976.84      3683068.23     10176986.84
      3683108.23     10177066.84      3683258.23     10177026.84
      3683488.23     10177106.84      3684048.23     10177416.84
      3683898.23     10177596.84      3683928.23     10177736.84
      3684048.23     10177836.84      3684148.23     10178066.84
      3684398.23     10178216.84      3684568.23     10178656.84
      3684548.23     10178806.84      3684678.23     10179066.84
      3684638.23     10179596.84      3684805.71     10179808.73
      3684963.69     10179965.19      3685109.52     10179974.31
      3685316.11     10180133.81      3685659.42     10179991.02
      3685828.03     10180074.57      3686678.23     10180046.84

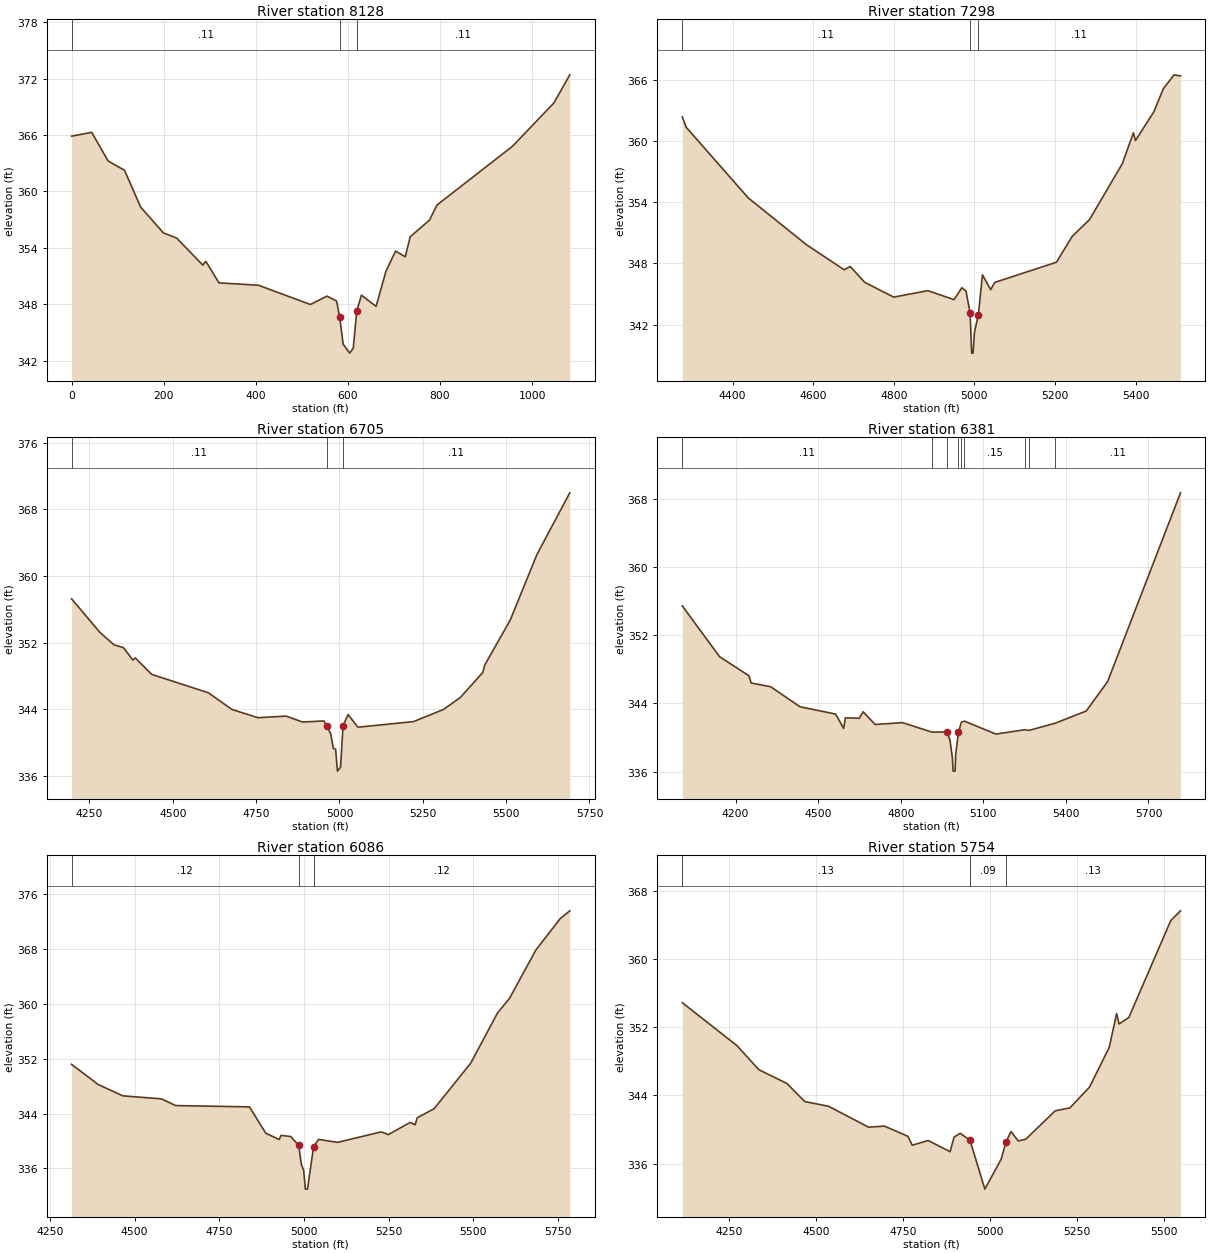
Type RM Length L Ch R = 1 ,8128    ,830,830,830
BEGIN DESCRIPTION:
CCLC 072 15.0
END DESCRIPTION:
XS GIS Cut Line= 3
      3682817.89      10175509.1      3683278.17     10175908.19
      3683727.68     10176056.47
#Sta/Elev= 30
       0  365.88    43.7  366.28    79.4  363.24     115  362.25   150.1  358.33
   199.5  355.59     228  355.05     285  352.17   291.6  352.57   320.1  350.28
   405.6  350.03   518.6  347.98   554.7  348.87   575.6  348.34   582.3   346.6
   589.8  343.75   604.1  342.81   611.7  343.34   619.4  347.34   629.5  348.97
   661.3  347.78   682.6   351.5   703.6  353.66   724.7  353.05   735.3  355.18
   777.4  356.96   793.6  358.56   957.6  364.81  1047.6  369.42  1081.9   372.4
#Mann= 3 , 0 , 0
       0     .11       0   582.3     .06       0   619.4     .11       0
Bank Sta=582.3,619.4
XS Rating Curve= 0 ,0
Exp/Cntr=0.3,0.1

Type RM Length L Ch R = 1 ,7298    ,593,593,593
BEGIN DESCRIPTION:
Mapping XS e7e51b77
END DESCRIPTION:
XS GIS Cut Line= 3
      3682399.58     10175993.99       3682930.8     10176342.93
      3683519.36     10176223.13
#Sta/Elev= 30
  4275.2  362.35  4285.1  361.33  4438.8  354.42  4583.4  349.83  4676.8  347.38
  4691.9   347.7  4727.8  346.15  4799.6   344.7  4884.7  345.33  4949.4  344.45
    4969  345.62  4979.2  345.29  4989.4  343.13  4993.2  339.21  4996.7  339.21
    5000  341.22  5009.8  342.97    5020  346.88  5040.4  345.43  5050.6  346.14
  5203.7  348.12  5242.7  350.65  5285.4  352.28    5367  357.77  5394.5   360.8
  5399.6  360.04    5445  362.84    5469  365.13  5495.6  366.48  5511.4  366.37
#Mann= 3 , 0 , 0
  4275.2     .11       0  4989.4     .06       0  5009.8     .11       0
Bank Sta=4989.4,5009.8
XS Rating Curve= 0 ,0
Exp/Cntr=0.3,0.1

Type RM Length L Ch R = 1 ,6705    ,324,324,324
BEGIN DESCRIPTION:
CCLC 072 14.0
END DESCRIPTION:
XS GIS Cut Line= 3
      3682367.83     10176161.05      3682948.23     10176716.84
      3683567.89     10176411.05
#Sta/Elev= 30
  4196.4  357.25  4281.2  353.24  4323.6  351.74    4352   351.4  4380.3  349.91
  4387.5  350.17  4436.9  348.19  4606.7  345.99  4677.4  343.99  4755.1     343
    4840  343.19  4889.4  342.48  4953.3  342.61 4962.97341.9598  4974.3  340.99
  4981.6  339.31  4988.5  339.23    4994  336.59  5003.5  337.09  5010.7  342.03
  5025.9  343.38  5055.3  341.86  5222.4  342.53  5311.8  343.98  5362.6  345.42
    5430  348.42  5435.6  349.29  5512.5  354.72  5592.7  362.59    5691  369.97
#Mann= 3 ,-1 , 0
  4196.4     .11       0 4962.97     .06       0  5010.7     .11       0
Bank Sta=4962.97,5010.7
XS Rating Curve= 0 ,0
Exp/Cntr=0.3,0.1

Type RM Length L Ch R = 1 ,6381    ,295,295,295
BEGIN DESCRIPTION:
Mapping XS a3c1adfe
END DESCRIPTION:
XS GIS Cut Line= 4
      3682381.65     10176208.03      3682949.14     10176974.91
      3683142.77     10176944.24      3683579.84     10176449.65
#Sta/Elev= 30
  4006.4  355.43  4141.9  349.48  4248.3  347.25  4256.7   346.4  4327.6  345.96
    4434  343.62  4563.5  342.76  4592.7  341.08    4599  342.32  4649.1  342.27
  4663.7  343.03  4706.8  341.54  4806.4  341.76  4914.3  340.64  4969.2  340.68
  4979.4  339.62  4987.5  337.68 4990.45  336.08 4997.65  336.08  4999.6  337.99
  5009.7  340.63  5020.6  341.82  5031.5  341.93  5145.6  340.42  5251.8  340.93
  5266.2  340.85  5362.2   341.7    5474  343.12  5551.8  346.57  5816.5  368.67
#Mann= 9 ,-1 , 0
  4006.4     .11       0  4914.3     .15       0  4969.2     .09       0
  5009.7     .15       0  5020.6     .11       0  5031.5     .15       0
  5251.8     .11       0  5266.2     .15       0  5362.2     .11       0
Bank Sta=4969.2,5009.7
XS Rating Curve= 0 ,0
Exp/Cntr=0.3,0.1

Type RM Length L Ch R = 1 ,6086    ,332,332,332
BEGIN DESCRIPTION:
CCLC 072 13.0
END DESCRIPTION:
XS GIS Cut Line= 3
      3683008.93     10177697.08      3683191.22     10177040.85
      3683667.86     10176411.06
#Sta/Elev= 30
  4313.9  351.18  4392.8  348.23  4465.4  346.58  4579.6  346.14  4621.1  345.16
  4839.1  344.97  4887.4  341.12  4926.8  340.21  4932.5  340.81  4961.1  340.64
  4984.4  339.35  4992.3  336.58  4999.3  335.69    5004  332.96  5010.4  332.96
  5028.4  339.14    5043  340.22  5099.2  339.79  5228.2  341.32    5249  340.92
  5313.5   342.7  5328.1  342.35  5334.3  343.37  5384.3  344.71  5492.4  351.36
  5571.5  358.69  5606.9  360.82  5684.5  367.86  5756.7  372.47  5784.8   373.6
#Mann= 3 , 0 , 0
  4313.9     .12       0  4984.4     .07       0  5028.4     .12       0
Bank Sta=4984.4,5028.4
XS Rating Curve= 0 ,0
Exp/Cntr=0.3,0.1

Type RM Length L Ch R = 1 ,5754    ,489,489,489
BEGIN DESCRIPTION:
CCLC 072 12.0
END DESCRIPTION:
XS GIS Cut Line= 3
      3683117.86     10177911.06      3683488.23     10177106.84
      3683867.85     10176711.08
#Sta/Elev= 30
  4114.6   354.9  4272.1  349.85  4334.8  347.03  4415.4  345.42  4466.9  343.29
  4535.7  342.73  4650.5  340.28  4696.4   340.4  4764.1   339.2  4776.3  338.16
  4822.3  338.71  4885.3   337.4  4896.6   339.1  4914.1  339.56  4942.6  338.75
  4985.3     333  5032.2  336.51  5046.3  338.55  5060.5  339.76  5081.6  338.66
  5102.9  338.86  5187.8   342.2    5230  342.54  5286.6  344.99  5343.2  349.64
  5364.6  353.63  5371.5   352.4  5399.8  353.17  5520.3  364.54  5548.4  365.69
#Mann= 3 , 0 , 0
  4114.6     .13       0  4942.6     .09       0  5046.3     .13       0
Bank Sta=4942.6,5046.3
XS Rating Curve= 0 ,0
Exp/Cntr=0.3,0.1

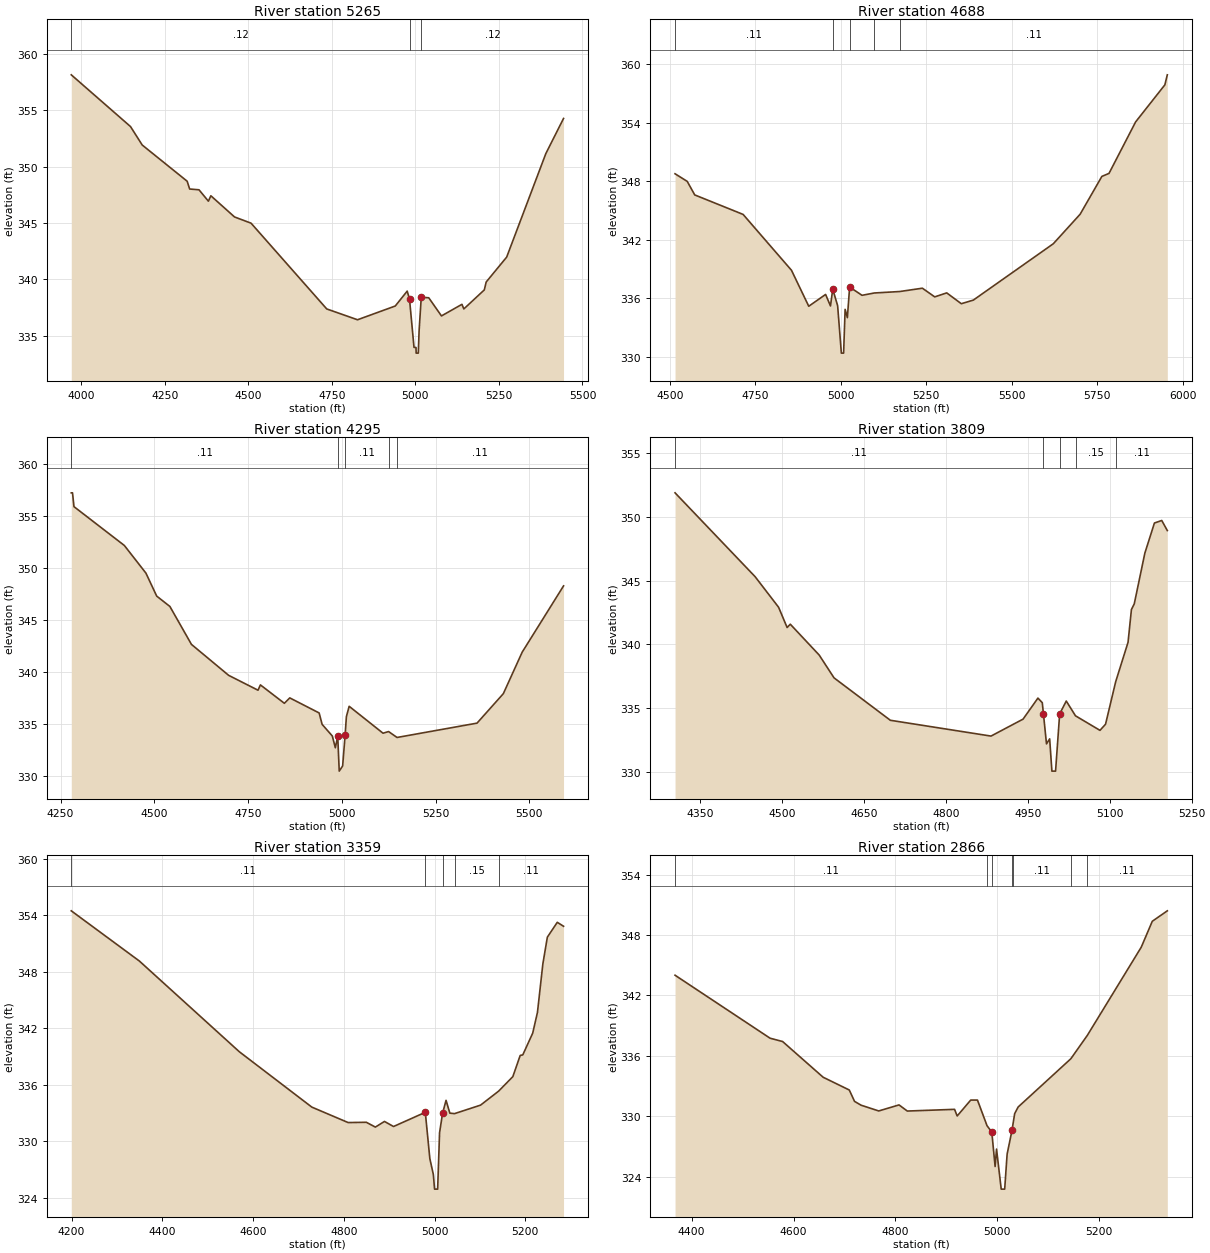
Type RM Length L Ch R = 1 ,5265    ,577,577,577
BEGIN DESCRIPTION:
CCLC 072 11.0
END DESCRIPTION:
XS GIS Cut Line= 3
      3683167.83      10178111.1      3683868.23     10177356.84
      3684067.87     10176961.04
#Sta/Elev= 30
  3970.7  358.14  4147.9  353.55    4183  351.91  4317.4   348.7  4324.8  348.01
  4352.8  347.94  4380.9  346.93  4388.3  347.41  4459.1  345.53  4508.5  344.98
  4734.9  337.37    4827  336.41  4939.9  337.63  4975.6  338.95  4982.5  338.25
    4996  333.96  5001.9  333.95  5002.4  333.45  5008.8  333.45  5011.2  335.44
  5017.7  338.41  5040.1  338.36  5078.1  336.75  5139.4  337.78    5145  337.37
  5206.3  339.06  5211.9  339.76  5273.2  341.97  5390.3  351.15  5443.3  354.27
#Mann= 3 , 0 , 0
  3970.7     .12       0  4982.5     .08       0  5017.7     .12       0
Bank Sta=4982.5,5017.7
XS Rating Curve= 0 ,0
Exp/Cntr=0.3,0.1

Type RM Length L Ch R = 1 ,4688    ,393,393,393
BEGIN DESCRIPTION:
CCLC 072 10.0
END DESCRIPTION:
XS GIS Cut Line= 3
      3683561.04      10178025.2      3684014.14      10177634.6
      3684649.57      10177082.5
#Sta/Elev= 30
  4515.2  348.78  4550.8     348  4572.8  346.61  4714.3  344.61  4855.8  338.88
  4906.3  335.19  4955.6   336.4  4969.9  335.22  4976.5  336.94  4990.8  335.25
  5001.7  330.38  5008.3  330.38  5012.7  334.87  5019.3  334.02  5025.9  337.16
  5062.1  336.31  5098.3  336.55  5172.5   336.7  5238.7  337.04  5274.8  336.15
  5309.9  336.56  5352.6  335.45  5387.8  335.82  5621.7   341.6  5700.2  344.63
  5763.8  348.51  5784.7  348.82  5862.5   354.1    5948   357.9  5955.2  358.93
#Mann= 5 ,-1 , 0
  4515.2     .11       0  4976.5     .06       0  5025.9     .11       0
  5098.3     .15       0  5172.5     .11       0
Bank Sta=4976.5,5025.9
XS Rating Curve= 0 ,0
Exp/Cntr=0.3,0.1

Type RM Length L Ch R = 1 ,4295    ,486,486,486
BEGIN DESCRIPTION:
CCLC 072 9.0
END DESCRIPTION:
XS GIS Cut Line= 3
      3683567.81      10178461.1      3684128.23     10178006.84
      3684717.86     10177961.07
#Sta/Elev= 30
  4278.6  357.22  4281.9  357.22  4285.8  355.89  4420.2  352.15  4477.7  349.49
  4506.4  347.28  4541.6  346.28  4599.1  342.63  4698.3  339.65  4776.6  338.22
    4783  338.73  4846.9  336.96  4861.3  337.48  4939.6  336.03  4947.6  334.93
  4974.8  333.81  4982.8  332.68  4989.2  333.78  4993.2  330.43  5002.3  330.93
 5008.83333.8618  5012.3  335.68  5019.7  336.67    5110  334.08  5124.8  334.24
  5147.4  333.67  5360.7  335.05  5430.9  337.89  5481.1  341.88  5591.4  348.26
#Mann= 5 ,-1 , 0
  4278.6     .11       0  4989.2     .06       0 5008.83     .11       0
  5124.8     .15       0  5147.4     .11       0
Bank Sta=4989.2,5008.83
XS Rating Curve= 0 ,0
Exp/Cntr=0.3,0.1

Type RM Length L Ch R = 1 ,3809    ,450,450,450
BEGIN DESCRIPTION:
CCLC 072 8.0
END DESCRIPTION:
XS GIS Cut Line= 3
      3683817.84     10178661.08      3684419.04     10178308.55
      3684617.81     10178261.08
#Sta/Elev= 30
    4304  351.89  4450.6  345.31  4493.6  342.91  4509.2  341.32    4515  341.58
  4567.9  339.16  4595.1  337.37  4698.2  334.04  4882.5   332.8  4941.2  334.13
  4968.4  335.78  4976.4  335.42 4978.49334.5432  4984.1  332.19  4989.9  332.58
    4994  330.05  5000.7  330.05  5008.2  334.54  5020.3  335.55  5037.2  334.39
    5082  333.25  5092.2  333.73  5110.8  337.07  5133.4  340.16  5139.6  342.73
  5144.8  343.18  5164.2  347.16  5181.7  349.52  5195.1  349.72  5205.3  348.93
#Mann= 5 ,-1 , 0
    4304     .11       0 4978.49     .06       0  5008.2     .11       0
  5037.2     .15       0  5110.8     .11       0
Bank Sta=4978.49,5008.2
XS Rating Curve= 0 ,0
Exp/Cntr=0.3,0.1

Type RM Length L Ch R = 1 ,3359    ,493,493,493
BEGIN DESCRIPTION:
CCLC 072 7.0
END DESCRIPTION:
XS GIS Cut Line= 3
      3683767.86     10178711.07      3684568.23     10178696.84
      3684817.89     10178561.05
#Sta/Elev= 30
  4199.5  354.46  4349.5  349.13  4569.6   339.5  4729.6  333.61  4809.6  331.97
  4849.6     332  4869.6  331.49  4889.6  332.09  4909.6  331.55  4979.6  333.06
  4989.6  328.14  4997.3  326.46    5000   324.9  5006.8   324.9    5011  330.88
 5017.55332.9363  5025.3  334.33  5033.7  332.97    5044  332.92  5101.3  333.82
  5141.2  335.31  5172.5  336.85  5188.7   339.1  5194.4  339.16  5216.2  341.46
  5226.7  343.67  5238.6  348.81  5248.5  351.66  5270.4  353.24  5284.2  352.82
#Mann= 5 ,-1 , 0
  4199.5     .11       0  4979.6     .06       0 5017.55     .11       0
    5044     .15       0  5141.2     .11       0
Bank Sta=4979.6,5017.55
XS Rating Curve= 0 ,0
Exp/Cntr=0.3,0.1

Type RM Length L Ch R = 1 ,2866    ,455,455,455
BEGIN DESCRIPTION:
CCLC 072 6.0
END DESCRIPTION:
XS GIS Cut Line= 3
      3684067.84     10178961.07      3684678.23     10179126.84
      3684967.84     10178961.08
#Sta/Elev= 30
  4367.5  344.01    4554  337.75  4578.6  337.42  4658.2  333.87  4709.5   332.6
  4719.8  331.47  4732.7  331.09  4767.3  330.52  4807.1  331.12  4823.4  330.51
  4916.1  330.68  4921.3  330.02  4947.8   331.6  4961.1   331.6  4979.8  329.06
  4989.2  328.42  4995.7     325  4998.5  326.73  5007.7  322.75  5014.5  322.75
  5019.3  326.23 5028.83328.5841  5030.3  329.05  5034.1  330.25  5040.9  330.91
  5144.4  335.71  5176.7  338.03  5282.6   346.8  5304.2  349.37  5333.7  350.41
#Mann= 7 ,-1 , 0
  4367.5     .11       0  4979.8     .15       0  4989.2     .09       0
 5028.83     .15       0  5030.3     .11       0  5144.4     .15       0
  5176.7     .11       0
Bank Sta=4989.2,5028.83
XS Rating Curve= 0 ,0
Exp/Cntr=0.3,0.1

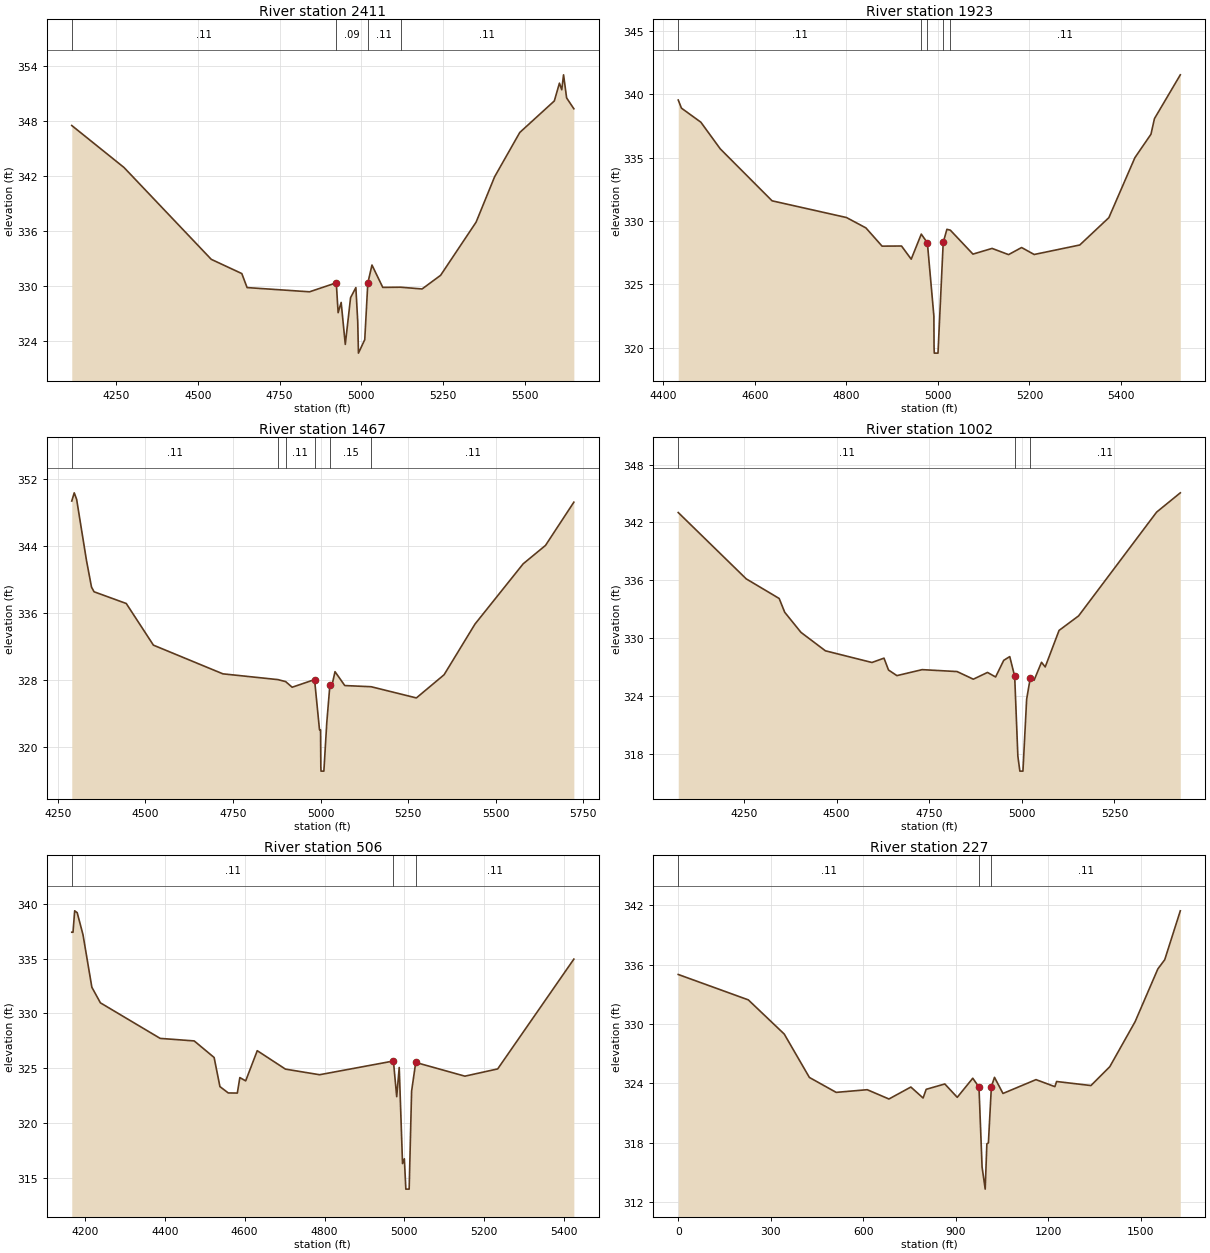
Type RM Length L Ch R = 1 ,2411    ,488,488,488
BEGIN DESCRIPTION:
CCLC 072 5.0
END DESCRIPTION:
XS GIS Cut Line= 3
      3684206.84      10180316.9      3684628.23     10179536.84
      3685217.83     10179261.08
#Sta/Elev= 30
  4113.4  347.56  4273.4  342.98  4540.6  332.96  4634.1  331.41  4650.3  329.88
  4841.6  329.42  4923.4   330.4  4929.1  327.14  4938.4  328.26    4951  323.68
  4967.2  328.78  4983.4  329.88  4989.1  326.18  4991.3  322.73  5010.6   324.2
 5019.96330.3575  5032.7  332.34  5065.8   329.9  5120.2  329.92  5186.2  329.73
  5242.9  331.22  5351.6  337.02  5408.3  341.97  5485.3   346.8  5591.1  350.24
  5606.8  352.18  5613.9  351.46  5619.4  353.09  5628.8  350.57  5650.9  349.39
#Mann= 4 ,-1 , 0
  4113.4     .11       0  4923.4     .09       0 5019.96     .11       0
  5120.2     .11       0
Bank Sta=4923.4,5019.96
XS Rating Curve= 0 ,0
Exp/Cntr=0.3,0.1

Type RM Length L Ch R = 1 ,1923    ,456,456,456
BEGIN DESCRIPTION:
CCLC 072 4.0
END DESCRIPTION:
XS GIS Cut Line= 3
      3684517.89     10180311.04      3684918.12     10179908.99
      3685267.87     10179511.05
#Sta/Elev= 30
  4432.7  339.56  4439.7  338.92  4482.1  337.81  4524.6   335.7  4637.7   331.6
  4800.3  330.28  4842.8  329.46  4878.1  328.02  4920.6  328.03  4941.8  326.99
  4963.8  328.97  4977.1  328.28  4991.3  322.51  4991.7  320.07  4992.2  319.57
  5000.3  319.57 5011.72328.3103  5019.8  329.35  5027.3  329.28  5076.7  327.39
  5118.5  327.84  5154.5  327.35    5183  327.91  5210.5  327.36  5310.1  328.11
  5373.7  330.27  5430.6  335.01  5465.7  336.86  5473.3  338.09  5529.8  341.55
#Mann= 5 ,-1 , 0
  4432.7     .11       0  4963.8     .15       0  4977.1     .09       0
 5011.72     .15       0  5027.3     .11       0
Bank Sta=4977.1,5011.72
XS Rating Curve= 0 ,0
Exp/Cntr=0.3,0.1

Type RM Length L Ch R = 1 ,1467    ,465,465,465
BEGIN DESCRIPTION:
CCLC 072 3.0
END DESCRIPTION:
XS GIS Cut Line= 3
      3684767.88     10180611.05      3685287.25     10180126.21
      3685667.87     10179511.04
#Sta/Elev= 30
  4289.5  349.37  4296.5  350.35  4303.4  349.57  4331.7  342.22  4345.9  339.08
  4353.2  338.52  4445.1  337.12  4522.7  332.14  4721.1  328.71  4878.4  328.02
  4900.4  327.78  4918.9  327.11  4982.9  328.02    4997  322.02    5000  322.02
  5000.8  317.58  5001.3  317.08  5009.5  317.08  5017.8  322.88  5026.7  327.37
  5032.5  327.31  5041.3  328.97  5069.2  327.31  5144.5  327.17  5273.7  325.83
  5352.8   328.6  5441.1  334.66  5578.6  341.86  5642.4  344.06  5723.4  349.23
#Mann= 6 ,-1 , 0
  4289.5     .11       0  4878.4     .15       0  4900.4     .11       0
  4982.9     .06       0  5026.7     .15       0  5144.5     .11       0
Bank Sta=4982.9,5026.7
XS Rating Curve= 0 ,0
Exp/Cntr=0.3,0.1

Type RM Length L Ch R = 1 ,1002    ,496,496,496
BEGIN DESCRIPTION:
CCLC 072 2.0
END DESCRIPTION:
XS GIS Cut Line= 3
      3685267.86     10180811.05      3685706.51     10179994.06
      3685732.87     10179567.17
#Sta/Elev= 30
  4072.7  343.03  4256.2  336.16  4345.1  334.13  4360.1   332.7  4403.9  330.62
  4469.9  328.71  4595.5   327.5    4628  327.95  4640.2  326.72  4662.9  326.14
    4731  326.76  4825.3  326.56  4869.1  325.77  4907.3  326.47  4929.2     326
  4951.1  327.72  4967.4  328.11  4980.7  326.07  4989.3   317.8  4994.7  316.25
    5003  316.25    5013   323.7    5023  325.94    5033  325.66  5053.1  327.52
  5063.1  327.04  5100.5  330.82  5153.3  332.33  5363.7  343.07  5427.7  345.07
#Mann= 3 , 0 , 0
  4072.7     .11       0  4980.7     .06       0    5023     .11       0
Bank Sta=4980.7,5023
XS Rating Curve= 0 ,0
Exp/Cntr=0.3,0.1

Type RM Length L Ch R = 1 ,506     ,279,279,279
BEGIN DESCRIPTION:
CCLC 072 1.0
END DESCRIPTION:
XS GIS Cut Line= 3
      3685667.85     10180711.07      3686172.86     10180048.74
      3686076.81     10179635.35
#Sta/Elev= 30
  4167.1   337.4  4170.2   337.4  4174.4  339.35  4180.7  339.18  4195.2  337.18
  4217.4  332.39  4238.8  330.97  4388.5  327.73  4473.7   327.5  4523.6  325.99
  4538.1  323.34    4559  322.76  4581.7  322.75    4588  324.16  4602.6  323.86
  4631.6  326.61  4702.3  324.93  4787.6  324.42  4972.6  325.67  4980.8  322.42
  4987.1  325.08  4995.4  316.33    5000  316.76  5003.7     314    5012     314
  5018.1  322.92  5028.4  325.54  5151.6  324.29  5233.7  324.95  5424.4  334.95
#Mann= 3 , 0 , 0
  4167.1     .11       0  4972.6     .06       0  5028.4     .11       0
Bank Sta=4972.6,5028.4
XS Rating Curve= 0 ,0
Exp/Cntr=0.3,0.1

Type RM Length L Ch R = 1 ,227     ,0,0,0
XS GIS Cut Line= 4
      3686179.45     10180990.67      3686384.31     10180615.67
      3686459.32     10179991.45      3686200.28     10179480.25
#Sta/Elev= 30
       0  335.02   227.4  332.45     344  328.99   425.6   324.6   512.5  323.09
   613.2  323.36   683.7  322.42   754.8  323.63   794.5  322.52   804.6   323.4
     865  323.94   905.3  322.59   955.7  324.52   975.8  323.63   985.9  315.54
     996   313.3  1001.4  317.88  1006.4  317.98  1016.1  323.68  1026.2  324.61
  1053.7  322.98  1160.9  324.38  1222.1  323.67  1227.7  324.19  1339.1  323.78
  1400.3  325.69  1482.4  330.24  1556.2  335.58  1578.5  336.51  1629.1  341.46
#Mann= 3 , 0 , 0
       0     .11       0   975.8     .06       0  1016.1     .11       0
Bank Sta=975.8,1016.1
XS Rating Curve= 0 ,0
Exp/Cntr=0.3,0.1

Chan Stop Cuts=-1
Use User Specified Reach Order=0
Composite Channel Slope=5