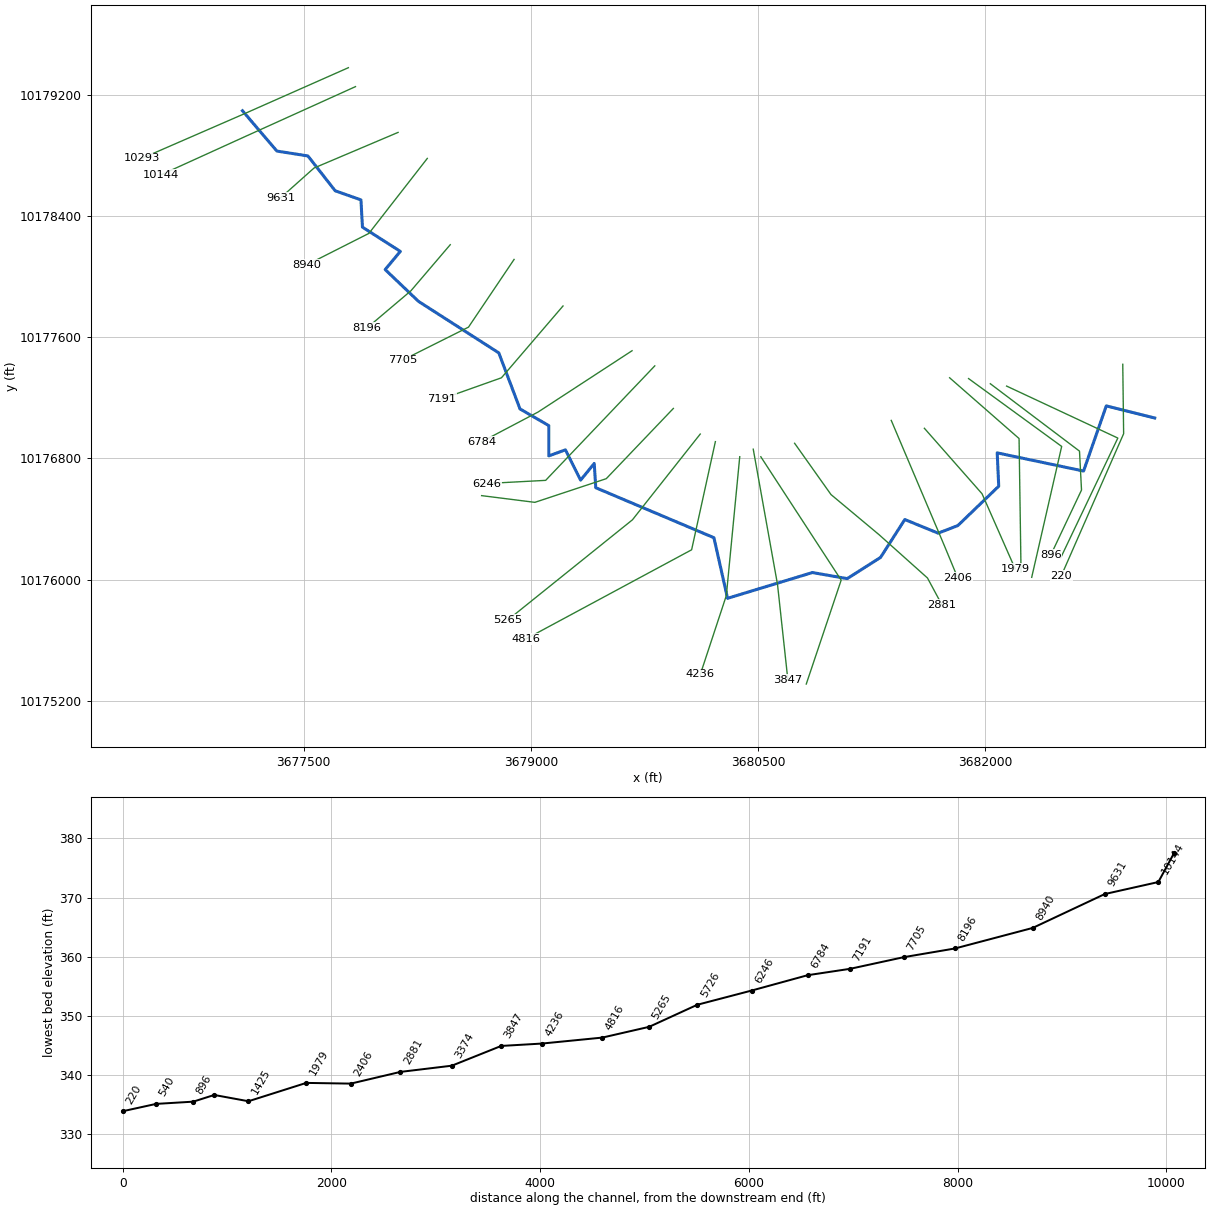
--- CCLC 073.prj (project) ---

Proj Title=CCLC 073 Base Level Engineering
Current Plan=p01
Default Exp/Contr=0.3,0.1
English Units
Geom File=g01
Flow File=f01
Flow File=f02
Plan File=p01
Y Axis Title=Elevation
X Axis Title(PF)=Main Channel Distance
X Axis Title(XS)=Station
BEGIN DESCRIPTION:
CCLC 073
END DESCRIPTION:
DSS Export Rating Curves= 0
DSS Export Rating Curve Sorted= 0
DSS Export Volume Flow Curves= 0
DXF OffsetX= 0
DXF OffsetY= 0
DXF ScaleX= 1
DXF ScaleY= 10

--- CCLC 073.p01 (plan) ---

Plan Title=Multiple Run
Short Identifier=Multiple
Geom File=g01
Flow File=f01
Subcritical Flow
K Sum by GR= 0
Std Step Tol= 0.01
Critical Tol= 0.01
Num of Std Step Trials= 20
Max Error Tol= 0.3
Flow Tol Ratio= 0.001
Split Flow NTrial= 30
Split Flow Tol= 0.02
Split Flow Ratio= 0.02
Log Output Level= 0
Friction Slope Method= 1
Unsteady Friction Slope Method= 2
Unsteady Bridges Friction Slope Method= 1
Parabolic Critical Depth
Global Vel Dist=  1 , 1 , 1
Global Log Level= 0
CheckData=True
Encroach Param= -1, 0, 0, 0
BEGIN DESCRIPTION:
Multiple Run
END DESCRIPTION:

--- CCLC 073.f01 (steady flow) ---

Flow Title=Multiple
Program Version=4.10
Number of Profiles= 7
Profile Names=10-year,25-year,50-year,1pct_min,100-year,1pct_plu,500-year
River Rch & RM=CCLC 073,Reach-1         ,10293
     729    1000    1362     610    1842    5563    3488
River Rch & RM=CCLC 073,Reach-1         ,5265
    1005    1396    1919     866    2614    7894    5022
Boundary for River Rch & Prof#=CCLC 073,Reach-1         , 1
Up Type= 0
Dn Type= 3
Dn Slope=0.005
Boundary for River Rch & Prof#=CCLC 073,Reach-1         , 2
Up Type= 0
Dn Type= 3
Dn Slope=0.005
Boundary for River Rch & Prof#=CCLC 073,Reach-1         , 3
Up Type= 0
Dn Type= 3
Dn Slope=0.005
Boundary for River Rch & Prof#=CCLC 073,Reach-1         , 4
Up Type= 0
Dn Type= 3
Dn Slope=0.005
Boundary for River Rch & Prof#=CCLC 073,Reach-1         , 5
Up Type= 0
Dn Type= 3
Dn Slope=0.005
Boundary for River Rch & Prof#=CCLC 073,Reach-1         , 6
Up Type= 0
Dn Type= 3
Dn Slope=0.005
Boundary for River Rch & Prof#=CCLC 073,Reach-1         , 7
Up Type= 0
Dn Type= 3
Dn Slope=0.005
DSS Import GetInterval= 0
DSS Import GetPeak= 0
DSS Import FillOption= 0

--- CCLC 073.f02 (steady flow) ---

Flow Title=Orig_BLE_Flows
Program Version=4.10
Number of Profiles= 7
Profile Names=10-year,25-year,50-year,1pct_min,100-year,1pct_plu,500-year
River Rch & RM=CCLC 073,Reach-1         ,10293
     729     980    1184     469    1417    4279    2028
River Rch & RM=CCLC 073,Reach-1         ,5265
    1005    1369    1669     666    2011    6072    2920
Boundary for River Rch & Prof#=CCLC 073,Reach-1         , 1
Up Type= 0
Dn Type= 3
Dn Slope=0.005
Boundary for River Rch & Prof#=CCLC 073,Reach-1         , 2
Up Type= 0
Dn Type= 3
Dn Slope=0.005
Boundary for River Rch & Prof#=CCLC 073,Reach-1         , 3
Up Type= 0
Dn Type= 3
Dn Slope=0.005
Boundary for River Rch & Prof#=CCLC 073,Reach-1         , 4
Up Type= 0
Dn Type= 3
Dn Slope=0.005
Boundary for River Rch & Prof#=CCLC 073,Reach-1         , 5
Up Type= 0
Dn Type= 3
Dn Slope=0.005
Boundary for River Rch & Prof#=CCLC 073,Reach-1         , 6
Up Type= 0
Dn Type= 3
Dn Slope=0.005
Boundary for River Rch & Prof#=CCLC 073,Reach-1         , 7
Up Type= 0
Dn Type= 3
Dn Slope=0.005
DSS Import GetInterval= 0
DSS Import GetPeak= 0
DSS Import FillOption= 0

--- CCLC 073.g01 (geometry) ---

Geom Title=Existing Conditions
Program Version=4.10

River Reach=CCLC 073        ,Reach-1
Reach XY= 30
      3677096.22      10179095.2      3677323.37     10178828.98
      3677528.23     10178796.84      3677708.23     10178566.84
      3677878.23     10178506.84      3677888.23     10178326.84
      3678138.23     10178166.84      3678038.23     10178046.84
      3678258.23     10177836.84      3678788.23     10177496.84
      3678928.23     10177126.84      3679118.23     10177016.84
      3679118.23     10176816.84      3679228.23     10176856.84
      3679328.23     10176656.84      3679418.23     10176766.84
      3679428.23     10176606.84      3680208.23     10176276.84
      3680298.23     10175876.84      3680858.23     10176046.84
      3681088.23     10176006.84      3681308.23     10176146.84
      3681468.23     10176396.84      3681688.23     10176306.84
      3681818.23     10176356.84      3682088.23     10176616.84
      3682078.23     10176836.84      3682648.23     10176716.84
      3682798.23     10177146.84      3683118.23     10177066.84

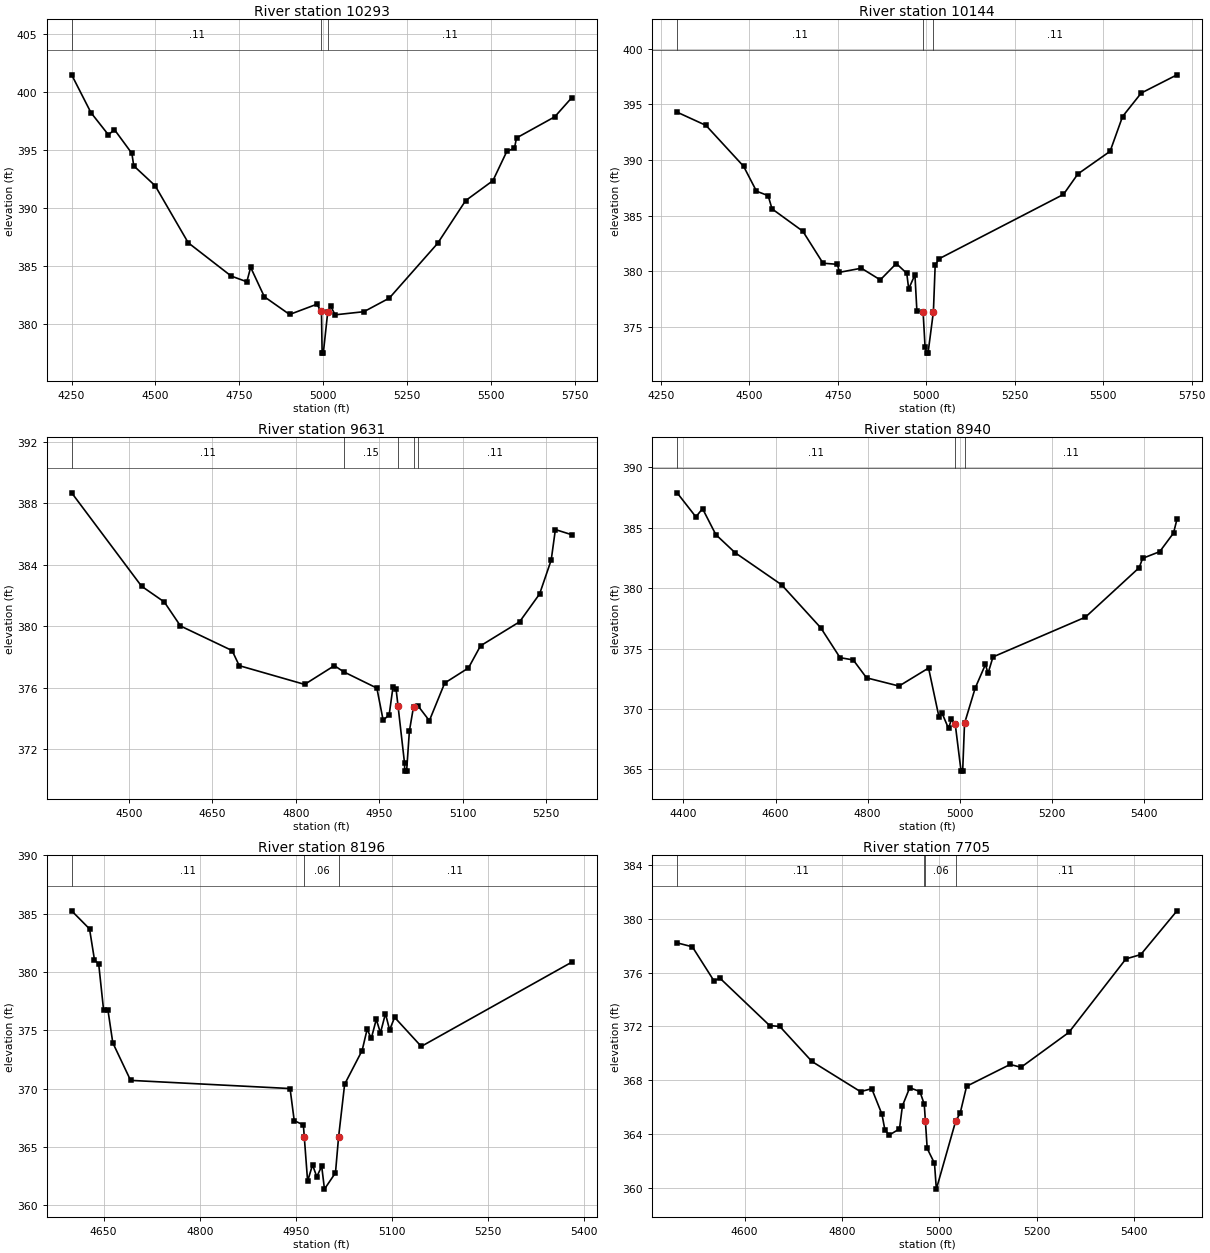
Type RM Length L Ch R = 1 ,10293   ,149,149,149
BEGIN DESCRIPTION:
CCLC 073 20.0
END DESCRIPTION:
XS GIS Cut Line= 3
      3677795.37     10179379.38      3677114.95     10179078.11
      3676431.84     10178780.88
#Sta/Elev= 30
  4250.4  401.44  4307.9  398.18  4359.9  396.27  4377.8  396.72  4429.8  394.67
  4435.3   393.6  4499.2  391.88  4597.6  386.97  4725.6   384.1  4772.2  383.61
  4783.6  384.85  4824.3  382.32  4899.6  380.79  4980.4  381.67  4994.5  381.05
  4996.5  377.46    5000  377.46  5013.2     381  5021.7  381.53    5035  380.76
  5120.9  381.03  5196.6   382.2  5340.3  386.91  5423.9   390.6  5505.2  392.32
  5546.6  394.84  5569.4  395.12  5575.5     396  5689.3  397.82  5739.5  399.45
#Mann= 3 , 0 , 0
  4250.4     .11       0  4994.5     .06       0  5013.2     .11       0
Bank Sta=4994.5,5013.2
XS Rating Curve= 0 ,0
Exp/Cntr=0.3,0.1

Type RM Length L Ch R = 1 ,10144   ,513,513,513
BEGIN DESCRIPTION:
Mapping XS b92c9dd1
END DESCRIPTION:
XS GIS Cut Line= 3
      3677842.22     10179254.37      3677114.95     10178925.33
       3676555.8     10178671.05
#Sta/Elev= 30
  4296.2   394.3  4377.8  393.11  4484.1  389.43  4520.5  387.19  4553.4  386.79
  4564.4   385.6  4651.4  383.59  4708.5  380.71  4749.3  380.61  4754.8  379.89
  4816.9  380.26  4870.3  379.21  4915.6  380.68  4945.1   379.8  4950.6   378.4
  4968.2  379.67  4973.7  376.44  4991.3  376.31  4996.8  373.19  5001.7  372.62
  5005.2  372.62 5020.43376.3554  5025.4  380.53  5036.4  381.11  5387.9   386.9
  5428.6  388.74  5519.7  390.78  5554.9  393.91  5607.6  396.02  5708.7  397.66
#Mann= 3 , 0 , 0
  4296.2     .11       0  4991.3     .06       0 5020.43     .11       0
Bank Sta=4991.3,5020.43
XS Rating Curve= 0 ,0
Exp/Cntr=0.3,0.1

Type RM Length L Ch R = 1 ,9631    ,691,691,691
BEGIN DESCRIPTION:
CCLC 073 19.0
END DESCRIPTION:
XS GIS Cut Line= 3
      3678123.47     10178952.29      3677568.23     10178716.84
      3677347.45     10178519.99
#Sta/Elev= 30
  4396.9  388.69  4522.5  382.62  4563.5  381.59  4592.6  380.03  4685.4  378.43
  4698.2  377.45  4815.8  376.23  4869.3  377.45    4886  377.05  4945.7  375.99
    4957   373.9  4967.8  374.25  4974.8  376.08  4980.2  375.94 4983.78374.8276
  4995.5  371.09  4995.7  370.59  4999.2  370.59  5004.2   373.2  5011.7  374.79
  5019.6  374.84  5040.1  373.87  5067.7  376.32  5110.4   377.3  5132.1  378.74
  5202.3   380.3  5238.3  382.11  5259.2  384.32  5266.7   386.3  5295.8  385.97
#Mann= 5 ,-1 , 0
  4396.9     .11       0    4886     .15       0 4983.78     .09       0
  5011.7     .15       0  5019.6     .11       0
Bank Sta=4983.78,5011.7
XS Rating Curve= 0 ,0
Exp/Cntr=0.3,0.1

Type RM Length L Ch R = 1 ,8940    ,744,744,744
BEGIN DESCRIPTION:
CCLC 073 18.0
END DESCRIPTION:
XS GIS Cut Line= 3
      3678316.21     10178780.42       3677930.8     10178285.64
      3677521.11     10178078.19
#Sta/Elev= 30
  4386.1  387.89  4426.9   385.9  4441.4  386.58  4470.3  384.43    4512  382.94
  4613.2  380.28  4698.3  376.72  4740.2  374.25  4768.9  374.06  4797.8  372.58
  4868.4   371.9  4932.6  373.39  4955.2  369.34  4961.6  369.68    4976  368.39
  4982.4  369.17  4990.5  368.76  5003.2  364.86  5006.7  364.86 5010.76368.8139
  5033.9  371.73  5056.2  373.69  5061.8  372.95  5072.6  374.31  5273.4   377.6
  5390.4   381.7  5397.7  382.47  5434.9  383.02  5464.9  384.56  5472.5  385.71
#Mann= 3 , 0 , 0
  4386.1     .11       0  4990.5     .06       0 5010.76     .11       0
Bank Sta=4990.5,5010.76
XS Rating Curve= 0 ,0
Exp/Cntr=0.3,0.1

Type RM Length L Ch R = 1 ,8196    ,491,491,491
BEGIN DESCRIPTION:
CCLC 073 16.0
END DESCRIPTION:
XS GIS Cut Line= 3
      3678467.82     10178211.04      3678208.23     10177906.84
      3677917.87     10177661.09
#Sta/Elev= 30
  4600.1  385.24    4628  383.69  4635.7  381.04  4642.3  380.68    4650  376.71
  4656.6  376.78  4664.3  373.93  4692.1  370.71    4941  370.01  4947.5  367.26
  4961.8  366.89 4963.21365.8602  4968.4  362.07  4976.1  363.47  4982.7  362.45
  4990.4  363.35  4994.7  361.39  5011.9  362.79 5016.69365.8335  5026.2  370.38
  5053.5  373.27  5061.3  375.09  5067.8  374.31  5075.6  375.94  5082.1  374.78
  5089.9  376.43  5096.4  375.03  5104.2  376.11  5145.8  373.62  5380.4  380.83
#Mann= 3 , 0 , 0
  4600.1     .11       0 4963.21     .06       0 5016.69     .11       0
Bank Sta=4963.21,5016.69
XS Rating Curve= 0 ,0
Exp/Cntr=0.3,0.1

Type RM Length L Ch R = 1 ,7705    ,514,514,514
BEGIN DESCRIPTION:
CCLC 073 15.0
END DESCRIPTION:
XS GIS Cut Line= 3
      3678889.15     10178113.78      3678588.23     10177666.84
       3678151.2     10177447.92
#Sta/Elev= 30
  4461.2  378.21  4492.5  377.92  4536.8   375.4  4549.5  375.58  4651.4  372.07
  4672.4     372  4738.4   369.4  4838.2  367.16  4861.3  367.38  4882.3  365.48
  4888.4  364.31  4897.3  363.94  4918.3  364.39  4924.4  366.11  4939.3  367.45
  4960.3  367.17  4969.3  366.22 4971.58364.9734  4975.3  362.94  4990.3  361.84
  4994.1  359.92    5034  364.99    5043  365.55  5056.3  367.56  5145.8  369.18
  5168.2  368.97  5266.5  371.56  5383.8  377.02  5414.3  377.34  5488.8  380.59
#Mann= 4 ,-1 , 0
  4461.2     .11       0  4969.3     .09       0 4971.58     .06       0
    5034     .11       0
Bank Sta=4971.58,5034
XS Rating Curve= 0 ,0
Exp/Cntr=0.3,0.1

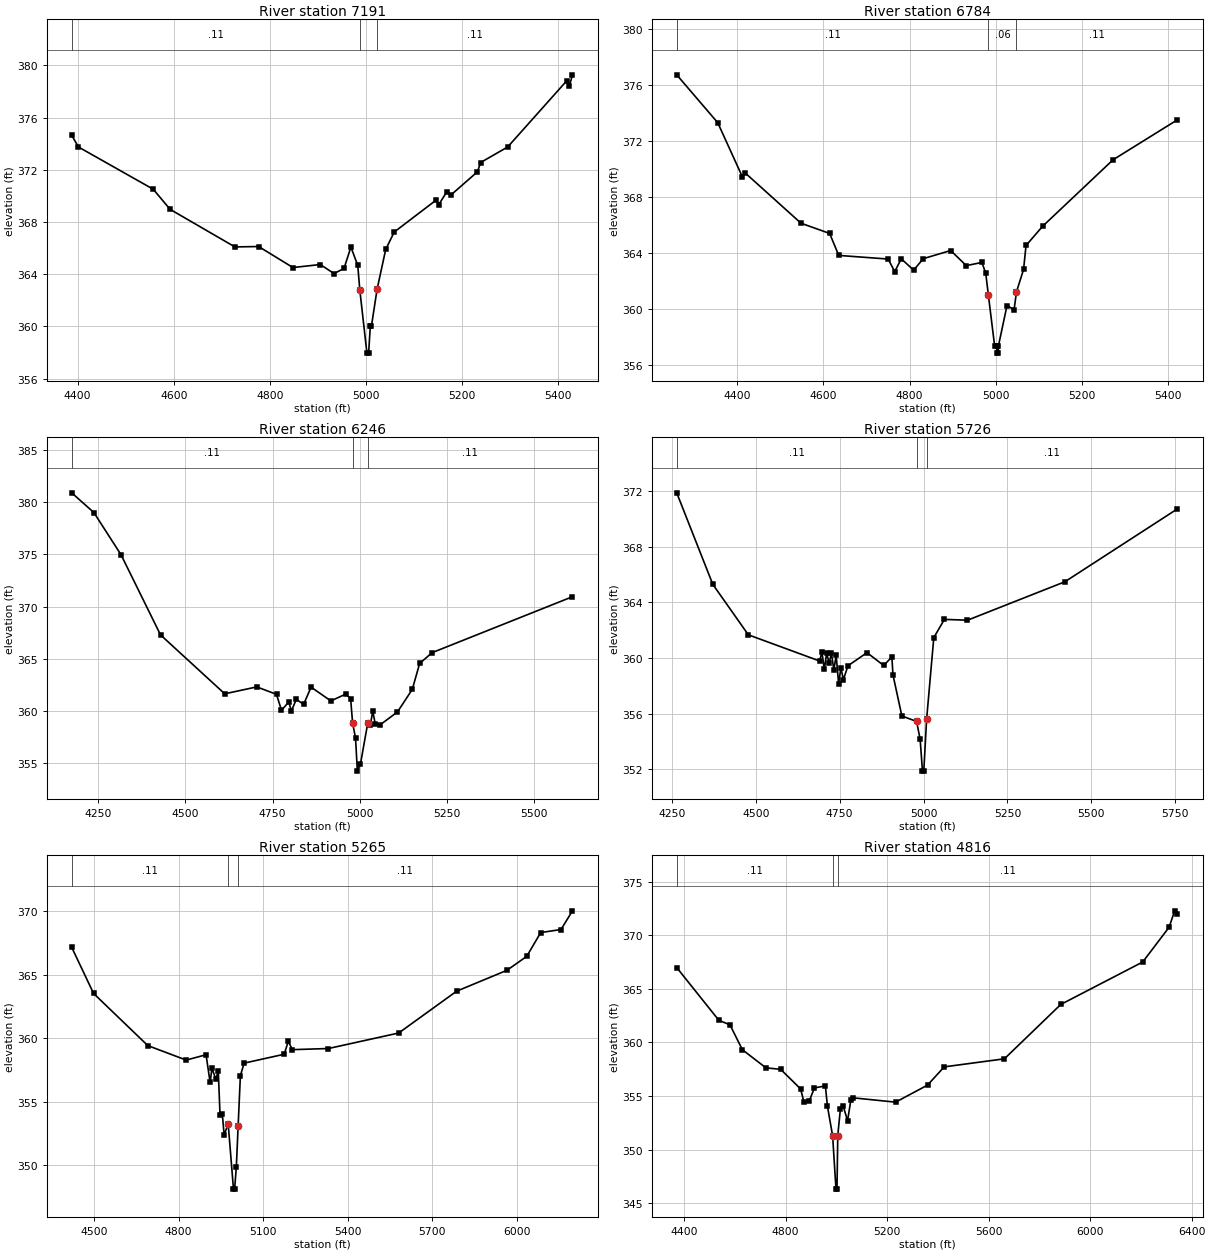
Type RM Length L Ch R = 1 ,7191    ,407,407,407
BEGIN DESCRIPTION:
CCLC 073 14.0
END DESCRIPTION:
XS GIS Cut Line= 3
      3679212.08     10177806.51       3678805.8     10177332.51
      3678411.44     10177192.41
#Sta/Elev= 30
  4387.6  374.65  4401.6  373.75  4557.4  370.51  4592.5  368.97  4727.5  366.09
  4776.9  366.12  4848.3  364.51  4905.3  364.74  4933.9  364.05  4954.7  364.44
    4969  366.08  4983.3  364.67 4987.46362.8232  5002.4  357.95  5005.9  357.95
  5009.5  360.05  5011.9  360.05  5023.6362.8556  5041.5   365.9  5059.2  367.23
  5146.5  369.68  5151.8  369.32  5168.9  370.33  5177.3  370.07  5232.6  371.85
  5239.1  372.56  5295.5  373.75  5418.9  378.84  5424.2  378.45  5430.4  379.28
#Mann= 3 ,-1 , 0
  4387.6     .11       0 4987.46     .06       0  5023.6     .11       0
Bank Sta=4987.46,5023.6
XS Rating Curve= 0 ,0
Exp/Cntr=0.3,0.1

Type RM Length L Ch R = 1 ,6784    ,538,538,538
BEGIN DESCRIPTION:
CCLC 073 13.0
END DESCRIPTION:
XS GIS Cut Line= 3
      3679667.84     10177511.06      3679048.23     10177106.84
      3678675.63     10176910.65
#Sta/Elev= 30
  4260.2  376.75  4355.3  373.33  4412.6  369.45  4418.6  369.75  4548.3  366.15
  4614.7  365.42  4635.8  363.85  4750.4  363.59  4765.6  362.69  4780.7  363.61
  4809.4   362.8    4832  363.62  4895.3   364.2  4931.5  363.12  4967.7  363.35
  4976.6  362.57  4982.8  360.99  4997.2  357.38  5001.9  357.37  5002.1  356.87
  5005.6  356.87  5005.9  357.37  5025.9  360.27  5042.3  359.97  5047.9  361.25
  5064.3  362.85    5070  364.56  5108.4  365.93  5271.7  370.68  5421.1  373.54
#Mann= 3 ,-1 , 0
  4260.2     .11       0  4982.8     .06       0  5047.9     .11       0
Bank Sta=4982.8,5047.9
XS Rating Curve= 0 ,0
Exp/Cntr=0.3,0.1

Type RM Length L Ch R = 1 ,6246    ,520,520,520
BEGIN DESCRIPTION:
CCLC 073 12.0
END DESCRIPTION:
XS GIS Cut Line= 3
      3679817.84     10177411.06      3679097.47     10176655.43
      3678706.81     10176634.59
#Sta/Elev= 30
  4174.5  380.87  4238.2  378.98  4315.9  374.95  4429.1  367.29  4613.1  361.66
  4704.9  362.32  4761.5  361.61  4775.7  360.08  4796.8  360.89    4804  360.01
  4818.2  361.13  4839.2  360.65  4860.6   362.3  4917.2  360.98  4959.7  361.63
  4973.9  361.21 4979.49358.8847    4988  357.43  4993.2  354.27  5002.2  354.97
  5023.2   358.9  5030.5   358.7  5037.4  360.01  5044.6  358.75  5058.7   358.7
  5108.2  359.93  5150.6  362.08  5171.7  364.56  5207.2  365.59  5609.7  370.94
#Mann= 3 ,-1 , 0
  4174.5     .11       0 4979.49     .06       0  5023.2     .11       0
Bank Sta=4979.49,5023.2
XS Rating Curve= 0 ,0
Exp/Cntr=0.3,0.1

Type RM Length L Ch R = 1 ,5726    ,461,461,461
BEGIN DESCRIPTION:
Mapping XS c2267fda
END DESCRIPTION:
XS GIS Cut Line= 4
      3679940.46      10177130.1      3679497.76     10176666.56
      3679026.41     10176510.31      3678674.84     10176554.59
#Sta/Elev= 30
  4264.7  371.86  4372.1  365.29  4478.1  361.66  4690.4  359.78  4697.3  360.42
  4704.5  359.17  4711.4  360.36  4718.7  359.61  4725.6  360.34  4732.8  359.15
  4739.7  360.18    4747  358.16  4753.9   359.3  4761.1  358.44    4775  359.44
  4831.6  360.38  4881.3  359.46  4905.7  360.07    4909  358.78  4935.5  355.83
  4979.3  355.44  4989.9  354.16  4996.9  351.87  5000.8  351.87 5009.13355.5803
  5030.6  361.46  5062.2  362.77  5130.9  362.71    5421  365.47  5756.6  370.71
#Mann= 3 ,-1 , 0
  4264.7     .11       0  4979.3     .06       0 5009.13     .11       0
Bank Sta=4979.3,5009.13
XS Rating Curve= 0 ,0
Exp/Cntr=0.3,0.1

Type RM Length L Ch R = 1 ,5265    ,449,449,449
BEGIN DESCRIPTION:
CCLC 073 10.0
END DESCRIPTION:
XS GIS Cut Line= 3
      3680117.85     10176961.07      3679670.39     10176395.01
      3678847.44     10175733.53
#Sta/Elev= 30
  4420.6  367.16  4498.3  363.53  4690.7  359.43    4827  358.29  4897.5  358.71
  4911.9  356.53  4918.3  357.63  4932.7  356.78  4940.8  357.47  4947.1  353.94
  4955.2  354.06  4961.6  352.39    4976  353.28  4994.8  348.14  4998.8  348.14
  5004.9  349.86  5011.3  353.09  5019.3  357.06  5032.5  358.05  5174.9  358.75
  5189.3  359.77  5203.7  359.11  5331.7   359.2  5581.3  360.42  5786.9  363.71
  5965.3  365.35  6035.7  366.45  6085.3  368.32  6157.3  368.56    6198  370.03
#Mann= 3 ,-1 , 0
  4420.6     .11       0    4976     .06       0  5011.3     .11       0
Bank Sta=4976,5011.3
XS Rating Curve= 0 ,0
Exp/Cntr=0.3,0.1

Type RM Length L Ch R = 1 ,4816    ,580,580,580
BEGIN DESCRIPTION:
CCLC 073 9.0
END DESCRIPTION:
XS GIS Cut Line= 3
      3680217.86      10176911.1      3680061.01      10176197.1
      3678967.24     10175608.54
#Sta/Elev= 30
  4371.1  366.98  4537.2  362.06  4580.9  361.64  4629.8  359.32  4722.5  357.63
  4780.7  357.49    4859  355.67  4872.8  354.42  4893.3  354.54  4913.8  355.76
  4956.8  355.94    4965  354.04  4985.4  351.29  4998.6  346.32  5002.6  346.32
 5005.66351.3192  5016.1  353.82  5026.4  354.11  5044.3   352.7  5057.1  354.61
  5067.3  354.83  5233.6  354.43  5359.4  356.02  5425.1  357.72  5662.2  358.47
  5884.4  363.54  6207.3   367.5  6311.2  370.74  6333.1  372.27  6344.2  372.01
#Mann= 3 ,-1 , 0
  4371.1     .11       0  4985.4     .06       0 5005.66     .11       0
Bank Sta=4985.4,5005.66
XS Rating Curve= 0 ,0
Exp/Cntr=0.3,0.1

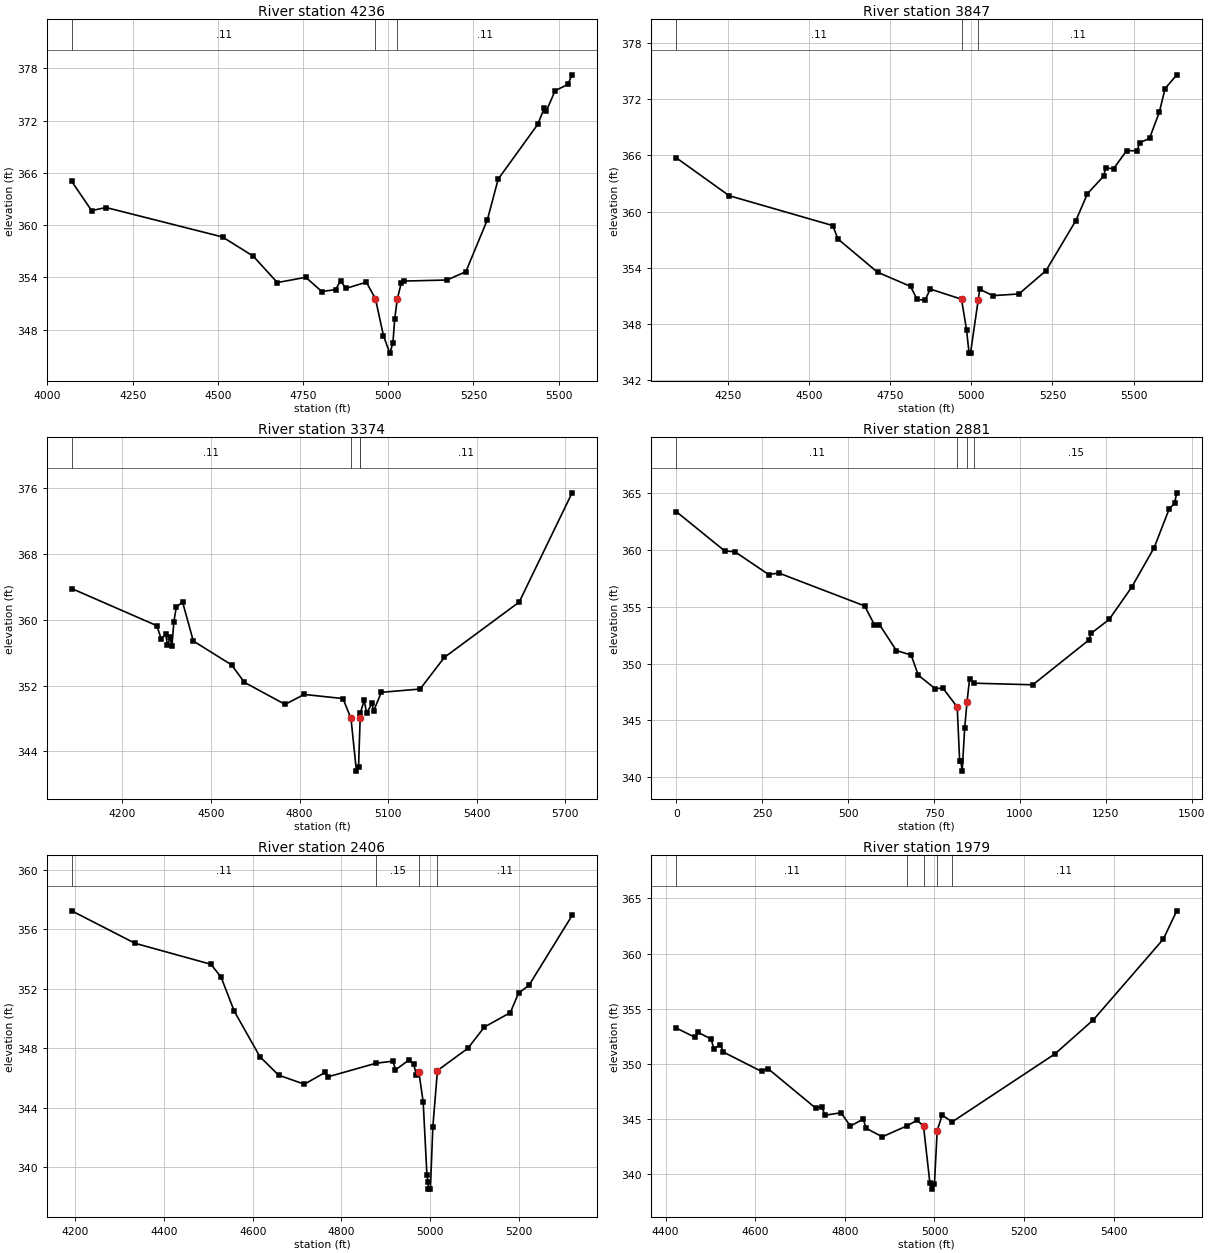
Type RM Length L Ch R = 1 ,4236    ,389,389,389
BEGIN DESCRIPTION:
CCLC 073 8.0
END DESCRIPTION:
XS GIS Cut Line= 3
      3680378.72     10176811.64      3680290.18     10175895.01
       3680118.6     10175375.08
#Sta/Elev= 30
  4071.1  365.02  4129.5  361.67  4172.1  362.02  4513.7  358.64  4604.1  356.43
  4674.5  353.41    4758  354.01  4805.1  352.38  4845.3   352.6  4860.2  353.61
  4875.4  352.73  4935.7  353.45  4962.5  351.54  4985.9  347.32  5004.5  345.31
  5013.7  346.46  5018.9  349.21 5026.38351.4794  5038.3  353.39  5045.4  353.58
  5172.4   353.7  5227.8  354.66    5291  360.63  5322.6  365.28  5438.4  371.55
  5458.2  373.45  5463.4  373.06  5489.9  375.44  5526.9  376.14  5539.5  377.25
#Mann= 3 ,-1 , 0
  4071.1     .11       0  4962.5     .06       0 5026.38     .11       0
Bank Sta=4962.5,5026.38
XS Rating Curve= 0 ,0
Exp/Cntr=0.3,0.1

Type RM Length L Ch R = 1 ,3847    ,473,473,473
BEGIN DESCRIPTION:
CCLC 073 7.0
END DESCRIPTION:
XS GIS Cut Line= 3
      3680467.85     10176861.08      3680628.23     10175966.84
      3680696.43     10175337.73
#Sta/Elev= 30
  4091.5  365.74  4254.1   361.7  4573.5  358.51  4589.3  357.08  4711.2  353.54
  4812.8  352.03  4833.2  350.64  4857.4  350.56  4873.8  351.74  4969.9  350.66
  4985.5  347.38  4993.1  344.91  4997.6  344.91 5021.43350.5992  5025.9  351.73
  5066.2  351.04  5146.6  351.22  5230.3  353.71    5322  359.04  5357.9  361.92
  5408.1   363.8  5413.6  364.66  5438.3  364.58  5478.6  366.51  5510.3  366.48
  5518.8  367.35    5549  367.82  5579.1   370.6  5596.9  373.12  5632.8  374.59
#Mann= 3 , 0 , 0
  4091.5     .11       0  4969.9     .06       0 5021.43     .11       0
Bank Sta=4969.9,5021.43
XS Rating Curve= 0 ,0
Exp/Cntr=0.3,0.1

Type RM Length L Ch R = 1 ,3374    ,493,493,493
BEGIN DESCRIPTION:
CCLC 073 6.0
END DESCRIPTION:
XS GIS Cut Line= 3
      3680517.87     10176811.04      3681048.23     10175996.84
      3680817.86     10175311.11
#Sta/Elev= 30
  4028.3  363.81  4316.5  359.29  4331.6  357.68  4346.7  358.26  4352.7   356.9
  4361.8  357.85  4367.8  356.78  4374.4  359.78  4382.9  361.59    4404  362.15
  4440.3  357.42    4570  354.51  4613.1  352.39  4751.1   349.7  4815.9  350.91
  4947.2  350.41  4974.4  347.99  4992.8  341.57    5000  342.07 5005.57348.0872
  5006.1  348.66  5019.4  350.21  5027.2  348.62  5045.7  349.82  5050.9  348.88
  5077.2  351.17  5208.6  351.57  5290.9  355.43  5544.1  362.16  5723.4  375.47
#Mann= 4 ,-1 , 0
  4028.3     .11       0  4974.4     .06       0 5005.57     .09       0
  5006.1     .11       0
Bank Sta=4974.4,5005.57
XS Rating Curve= 0 ,0
Exp/Cntr=0.3,0.1

Type RM Length L Ch R = 1 ,2881    ,475,475,475
BEGIN DESCRIPTION:
CCLC 073 5.0
END DESCRIPTION:
XS GIS Cut Line= 5
      3680740.86      10176900.2      3680980.96      10176561.8
      3681298.23     10176296.84      3681617.85     10176011.07
      3681713.65     10175833.13
#Sta/Elev= 30
       0  363.39   140.8  359.93   170.4  359.86   268.7  357.85   298.3  357.98
   548.2  355.08   576.8  353.41   591.1  353.44   640.6  351.15   683.5  350.75
   704.3  348.98   753.8  347.78   775.7  347.85   817.6  346.17   824.8  341.37
   828.3  341.37     832  340.52   839.5  344.36   846.2  346.63   853.7  348.68
   867.9  348.27  1037.6  348.13  1200.6  352.07  1207.3  352.66  1259.9  353.89
  1325.2  356.72  1390.9  360.22  1434.7  363.64  1450.1  364.12  1456.6  365.05
#Mann= 4 ,-1 , 0
       0     .11       0   817.6     .06       0   846.2     .11       0
   867.9     .15       0
Bank Sta=817.6,846.2
XS Rating Curve= 0 ,0
Exp/Cntr=0.3,0.1

Type RM Length L Ch R = 1 ,2406    ,427,427,427
BEGIN DESCRIPTION:
CCLC 073 4.0
END DESCRIPTION:
XS GIS Cut Line= 3
      3681378.71     10177051.28      3681727.68     10176228.35
      3681817.85     10176011.08
#Sta/Elev= 30
  4191.4  357.24  4334.2  355.06  4505.3  353.65  4528.3   352.8  4558.1   350.5
  4616.3  347.43  4658.2   346.2  4716.4  345.59  4763.7  346.39  4769.1  346.08
  4878.2     347  4916.6  347.14    4922  346.55    4952  347.21  4962.8  346.95
  4969.3  346.23  4974.8   346.4  4984.5  344.39    4993  339.46  4995.6  339.04
  4996.1  338.54  5000.8  338.54  5006.3  342.73  5016.7  346.51  5085.3     348
  5122.5  349.43  5181.1   350.4  5199.6  351.71  5223.1  352.23  5320.5  356.93
#Mann= 4 ,-1 , 0
  4191.4     .11       0  4878.2     .15       0  4974.8     .06       0
  5016.7     .11       0
Bank Sta=4974.8,5016.7
XS Rating Curve= 0 ,0
Exp/Cntr=0.3,0.1

Type RM Length L Ch R = 1 ,1979    ,554,554,554
BEGIN DESCRIPTION:
CCLC 073 3.0
END DESCRIPTION:
XS GIS Cut Line= 3
      3681597.47     10176999.18      3681978.23     10176566.84
      3682196.42     10176072.12
#Sta/Elev= 30
  4423.9  353.25  4465.2  352.42  4472.7  352.86  4501.2  352.26  4507.8  351.39
  4522.1  351.75  4528.7  351.08  4614.1  349.32  4628.3  349.58  4734.6  346.01
  4748.8  346.11  4755.5  345.35  4791.5  345.58  4812.4  344.37  4840.8     345
  4847.8  344.17  4883.5   343.4  4938.6  344.39  4961.3   344.9  4975.6  344.36
  4989.8  339.21  4993.5  338.66    5000  339.16  5006.1  343.97  5017.2  345.37
  5039.4  344.75  5268.6   350.9  5354.5  353.99  5510.8  361.31  5540.7  363.87
#Mann= 5 ,-1 , 0
  4423.9     .11       0  4938.6     .15       0  4975.6     .09       0
  5006.1     .15       0  5039.4     .11       0
Bank Sta=4975.6,5006.1
XS Rating Curve= 0 ,0
Exp/Cntr=0.3,0.1

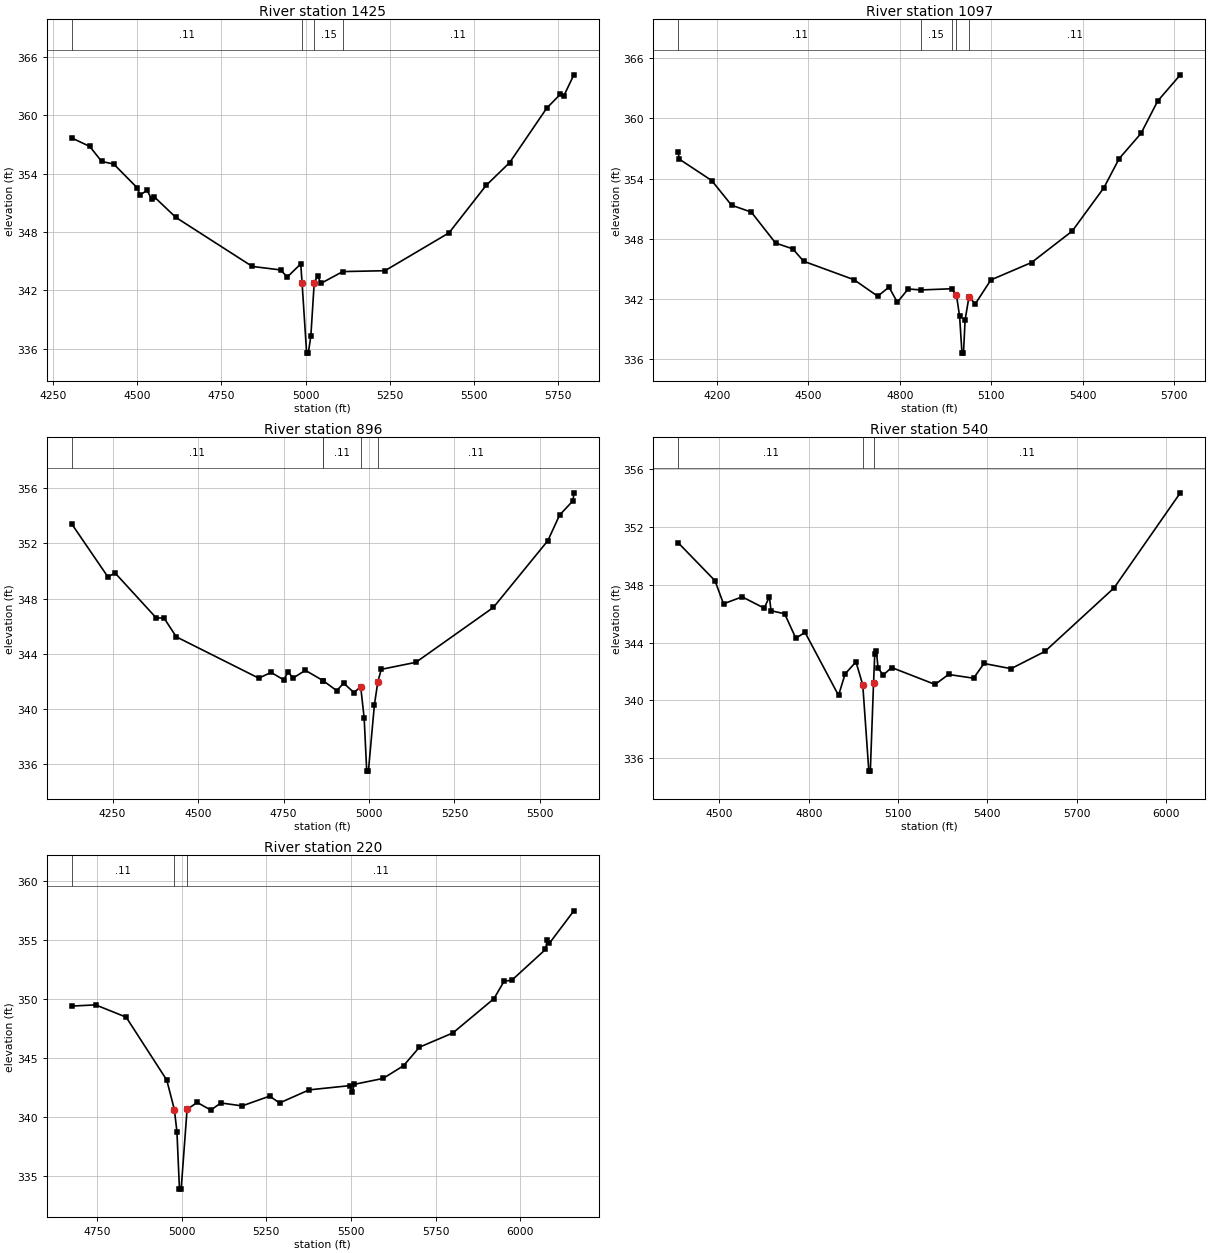
Type RM Length L Ch R = 1 ,1425    ,328,328,328
BEGIN DESCRIPTION:
CCLC 073 2.0
END DESCRIPTION:
XS GIS Cut Line= 3
       3681764.1     10177332.54      3682222.47     10176931.47
      3682235.56     10176050.63
#Sta/Elev= 30
  4306.3  357.67  4359.7   356.8  4394.9  355.26  4430.9  354.99  4501.2  352.52
  4508.7  351.79  4529.6  352.29  4543.9  351.37  4550.5  351.64  4615.1  349.51
  4841.9  344.47  4925.8  344.11  4945.9  343.38  4985.8  344.73 4989.82342.7521
  5003.3  335.56  5008.2  335.56  5015.8  337.31  5025.8  342.79  5035.8  343.49
  5045.8  342.73  5110.5  343.94  5235.8  344.03  5425.8  347.92  5535.8  352.79
  5605.8  355.14  5715.9  360.74  5755.9  362.15  5765.9  361.95  5796.3  364.16
#Mann= 4 ,-1 , 0
  4306.3     .11       0 4989.82     .06       0  5025.8     .15       0
  5110.5     .11       0
Bank Sta=4989.82,5025.8
XS Rating Curve= 0 ,0
Exp/Cntr=0.3,0.1

Type RM Length L Ch R = 1 ,1097    ,201,201,201
BEGIN DESCRIPTION:
Mapping XS 895e6843
END DESCRIPTION:
XS GIS Cut Line= 3
      3681889.16     10177327.28      3682503.72     10176879.39
      3682305.94     10176015.39
#Sta/Elev= 30
  4072.8   356.6  4076.1  355.94  4182.7   353.8  4247.6  351.35  4312.5  350.66
  4392.1  347.58  4448.5     347    4484  345.77  4649.3  343.93    4727  342.29
  4764.1  343.19  4791.5  341.69    4827  343.01  4868.4  342.91  4970.1  343.03
  4985.4  342.38  4995.7  340.28  5003.5  336.62  5008.4  336.62  5013.7  339.92
  5026.4  342.22    5047  341.52  5098.3  343.91  5231.6  345.64    5365  348.77
  5468.6  353.07  5518.9  355.98  5590.7   358.5  5645.4  361.72  5719.6  364.33
#Mann= 5 ,-1 , 0
  4072.8     .11       0  4868.4     .15       0  4970.1     .11       0
  4985.4     .06       0  5026.4     .11       0
Bank Sta=4985.4,5026.4
XS Rating Curve= 0 ,0
Exp/Cntr=0.3,0.1

Type RM Length L Ch R = 1 ,896     ,356,356,356
BEGIN DESCRIPTION:
Mapping XS 09649fc9
END DESCRIPTION:
XS GIS Cut Line= 4
      3682032.78     10177293.14      3682621.31     10176848.38
      3682634.73     10176591.49      3682432.16     10176163.43
#Sta/Elev= 30
  4130.6  353.41  4236.4  349.57  4257.2  349.86    4378  346.59  4400.2   346.6
  4436.2  345.23  4677.6  342.23  4713.5  342.65  4750.4  342.11  4763.7  342.69
  4777.5  342.23  4813.8   342.8  4865.7  342.05  4865.8  342.05  4905.6  341.32
  4925.7  341.87  4955.7  341.19  4975.7   341.6  4985.8  339.34  4993.3  335.49
  4998.2  335.49  5015.8  340.31  5025.8  341.96  5035.8  342.87  5137.1  343.38
  5363.8  347.36    5523   352.2  5557.5  354.06  5596.8   355.1  5599.1  355.67
#Mann= 5 ,-1 , 0
  4130.6     .11       0  4865.7     .15       0  4865.8     .11       0
  4975.7     .06       0  5025.8     .11       0
Bank Sta=4975.7,5025.8
XS Rating Curve= 0 ,0
Exp/Cntr=0.3,0.1

Type RM Length L Ch R = 1 ,540     ,320,320,320
BEGIN DESCRIPTION:
Mapping XS 8bc29795
END DESCRIPTION:
XS GIS Cut Line= 3
      3682140.15      10177277.8      3682874.37     10176934.65
      3682497.47     10176144.49
#Sta/Elev= 30
  4361.9  350.91  4485.2  348.29  4513.9  346.69  4576.6  347.17  4650.6  346.39
    4668  347.18  4673.5  346.21  4719.2     346  4756.7  344.31  4787.7  344.71
  4900.2  340.35  4922.3  341.84  4958.7  342.67  4981.5  341.08  5001.9  335.11
  5006.9  335.11 5017.69341.1849  5021.7  343.19  5027.2  343.42  5032.8  342.25
  5050.1  341.76  5078.4  342.28  5224.3  341.11  5269.6   341.8  5353.6  341.54
  5388.6  342.56  5479.4   342.2  5592.9  343.39  5825.4  347.79  6047.8  354.37
#Mann= 3 , 0 , 0
  4361.9     .11       0  4981.5     .06       0 5017.69     .11       0
Bank Sta=4981.5,5017.69
XS Rating Curve= 0 ,0
Exp/Cntr=0.3,0.1

Type RM Length L Ch R = 1 ,220     ,0,0,0
BEGIN DESCRIPTION:
CCLC 073 1.0
END DESCRIPTION:
XS GIS Cut Line= 3
      3682906.96     10177421.62      3682912.71     10176963.41
      3682500.97     10176025.01
#Sta/Elev= 30
  4675.2   349.4  4745.8   349.5  4835.8  348.46  4955.8  343.12 4978.25340.6199
  4985.8  338.74  4993.3  333.87  4998.3  333.87  5015.8  340.64  5045.8  341.22
  5085.8  340.58  5115.8  341.18  5178.5  340.93  5259.6  341.76  5288.9  341.18
  5376.2  342.29  5496.4  342.65  5504.1  342.13  5509.6  342.76  5594.7  343.26
  5655.2  344.34    5702  345.91  5800.9  347.12  5922.3  350.03    5952   351.5
  5975.3   351.6  6074.3   354.2  6079.7  355.01  6086.1  354.73  6158.2  357.48
#Mann= 3 , 0 , 0
  4675.2     .11       0 4978.25     .06       0  5015.8     .11       0
Bank Sta=4978.25,5015.8
XS Rating Curve= 0 ,0
Exp/Cntr=0.3,0.1

Chan Stop Cuts=-1
Use User Specified Reach Order=0
Composite Channel Slope=5