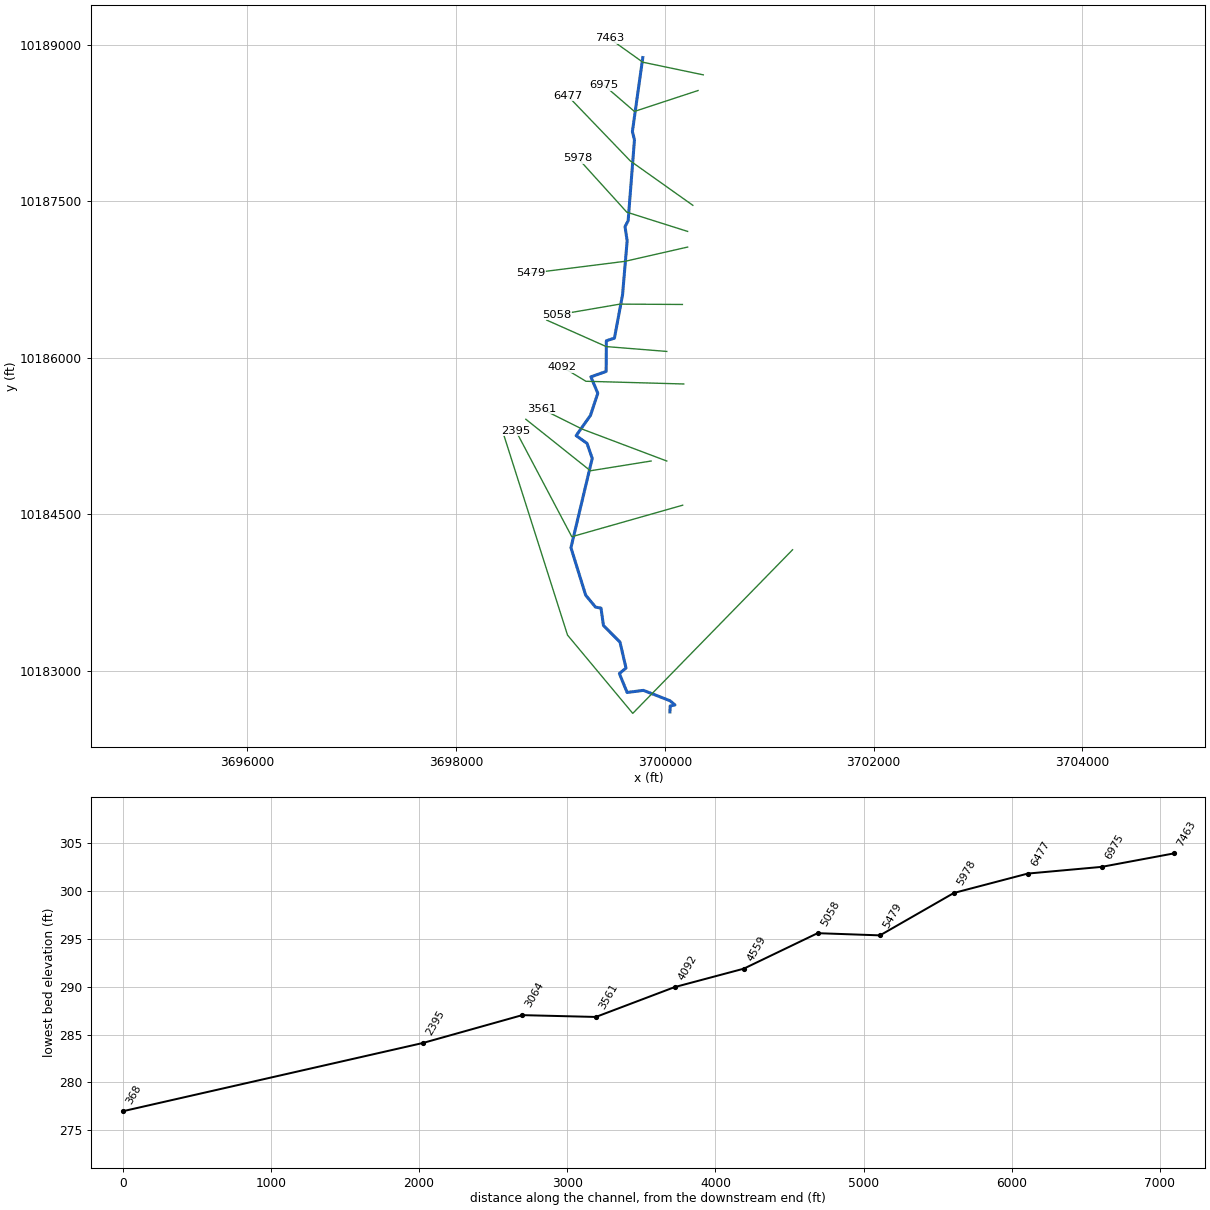
--- CCLC 074.prj (project) ---

Proj Title=CCLC 074 Base Level Engineering
Current Plan=p01
Default Exp/Contr=0.3,0.1
English Units
Geom File=g01
Flow File=f01
Flow File=f02
Plan File=p01
Y Axis Title=Elevation
X Axis Title(PF)=Main Channel Distance
X Axis Title(XS)=Station
BEGIN DESCRIPTION:
CCLC 074
END DESCRIPTION:
DSS Export Rating Curves= 0
DSS Export Rating Curve Sorted= 0
DSS Export Volume Flow Curves= 0
DXF OffsetX= 0
DXF OffsetY= 0
DXF ScaleX= 1
DXF ScaleY= 10

--- CCLC 074.p01 (plan) ---

Plan Title=Multiple Run
Short Identifier=Multiple
Geom File=g01
Flow File=f01
Subcritical Flow
K Sum by GR= 0
Std Step Tol= 0.01
Critical Tol= 0.01
Num of Std Step Trials= 20
Max Error Tol= 0.3
Flow Tol Ratio= 0.001
Split Flow NTrial= 30
Split Flow Tol= 0.02
Split Flow Ratio= 0.02
Log Output Level= 0
Friction Slope Method= 1
Unsteady Friction Slope Method= 2
Unsteady Bridges Friction Slope Method= 1
Parabolic Critical Depth
Global Vel Dist=  1 , 1 , 1
Global Log Level= 0
CheckData=True
Encroach Param= -1, 0, 0, 0
BEGIN DESCRIPTION:
Multiple Run
END DESCRIPTION:

--- CCLC 074.f01 (steady flow) ---

Flow Title=Multiple
Program Version=4.10
Number of Profiles= 7
Profile Names=10-year,25-year,50-year,1pct_min,100-year,1pct_plu,500-year
River Rch & RM=CCLC 074,Reach-1         ,7463
     903    1263    1743     791    2389    7215    4646
River Rch & RM=CCLC 074,Reach-1         ,4092
     839    1157    1581     710    2144    6475    4078
Boundary for River Rch & Prof#=CCLC 074,Reach-1         , 1
Up Type= 0
Dn Type= 3
Dn Slope=0.005
Boundary for River Rch & Prof#=CCLC 074,Reach-1         , 2
Up Type= 0
Dn Type= 3
Dn Slope=0.005
Boundary for River Rch & Prof#=CCLC 074,Reach-1         , 3
Up Type= 0
Dn Type= 3
Dn Slope=0.005
Boundary for River Rch & Prof#=CCLC 074,Reach-1         , 4
Up Type= 0
Dn Type= 3
Dn Slope=0.005
Boundary for River Rch & Prof#=CCLC 074,Reach-1         , 5
Up Type= 0
Dn Type= 3
Dn Slope=0.005
Boundary for River Rch & Prof#=CCLC 074,Reach-1         , 6
Up Type= 0
Dn Type= 3
Dn Slope=0.005
Boundary for River Rch & Prof#=CCLC 074,Reach-1         , 7
Up Type= 0
Dn Type= 3
Dn Slope=0.005
DSS Import GetInterval= 0
DSS Import GetPeak= 0
DSS Import FillOption= 0

--- CCLC 074.f02 (steady flow) ---

Flow Title=Orig_BLE_Flows
Program Version=4.10
Number of Profiles= 7
Profile Names=10-year,25-year,50-year,1pct_min,100-year,1pct_plu,500-year
River Rch & RM=CCLC 074,Reach-1         ,7463
     903    1238    1516     609    1838    5550    2701
River Rch & RM=CCLC 074,Reach-1         ,4092
     839    1134    1375     546    1649    4979    2371
Boundary for River Rch & Prof#=CCLC 074,Reach-1         , 1
Up Type= 0
Dn Type= 3
Dn Slope=0.005
Boundary for River Rch & Prof#=CCLC 074,Reach-1         , 2
Up Type= 0
Dn Type= 3
Dn Slope=0.005
Boundary for River Rch & Prof#=CCLC 074,Reach-1         , 3
Up Type= 0
Dn Type= 3
Dn Slope=0.005
Boundary for River Rch & Prof#=CCLC 074,Reach-1         , 4
Up Type= 0
Dn Type= 3
Dn Slope=0.005
Boundary for River Rch & Prof#=CCLC 074,Reach-1         , 5
Up Type= 0
Dn Type= 3
Dn Slope=0.005
Boundary for River Rch & Prof#=CCLC 074,Reach-1         , 6
Up Type= 0
Dn Type= 3
Dn Slope=0.005
Boundary for River Rch & Prof#=CCLC 074,Reach-1         , 7
Up Type= 0
Dn Type= 3
Dn Slope=0.005
DSS Import GetInterval= 0
DSS Import GetPeak= 0
DSS Import FillOption= 0

--- CCLC 074.g01 (geometry) ---

Geom Title=Existing Conditions
Program Version=4.10

River Reach=CCLC 074        ,Reach-1
Reach XY= 30
      3699788.23     10188876.84      3699688.71     10188168.76
      3699708.31     10188087.14      3699647.82     10187313.04
      3699618.09     10187256.44       3699638.4     10187121.69
      3699594.39     10186604.35      3699516.54     10186188.18
      3699439.21     10186163.57      3699437.01     10185869.12
      3699290.86     10185817.64      3699357.21     10185660.26
      3699286.95     10185448.39      3699149.68     10185254.31
      3699254.14       10185180.      3699303.74     10185036.33
      3699099.81     10184180.69      3699240.87     10183725.94
      3699334.82     10183611.52      3699387.88     10183601.44
      3699411.32     10183435.23      3699569.94     10183275.44
      3699627.28     10183027.45      3699563.74     10182974.76
      3699638.13     10182793.42      3699794.67     10182813.56
      3700048.95     10182714.12      3700096.49     10182673.77
      3700050.77      10182663.9      3700048.23     10182606.84

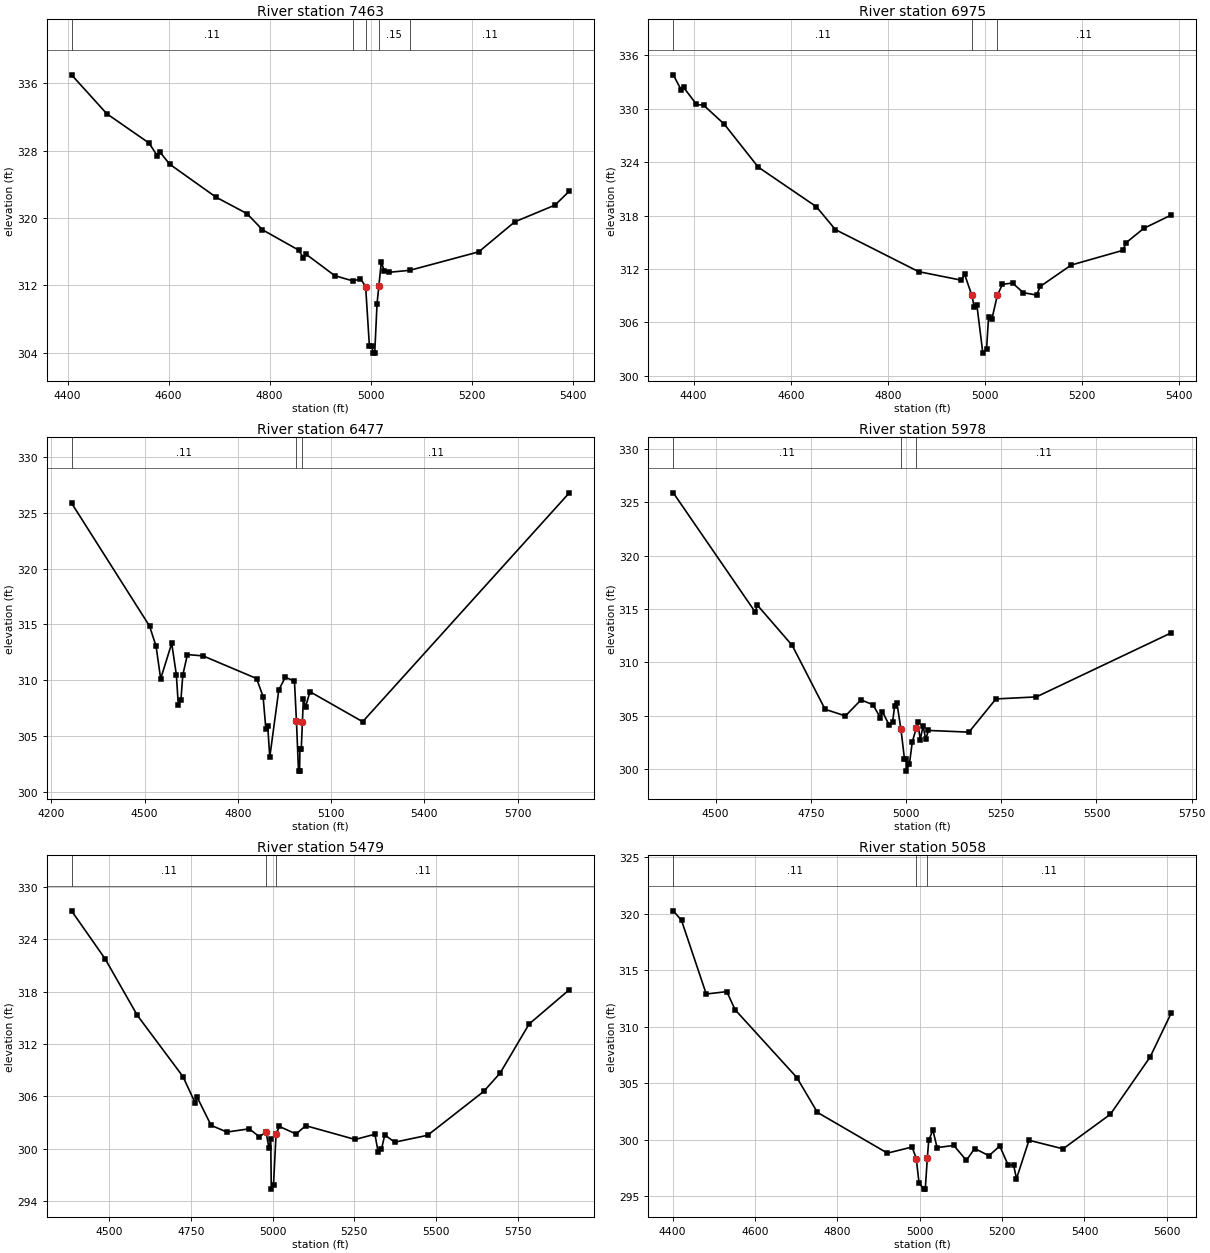
Type RM Length L Ch R = 1 ,7463    ,488,488,488
BEGIN DESCRIPTION:
CCLC 074 11.0
END DESCRIPTION:
XS GIS Cut Line= 3
      3700367.88     10188711.06      3699788.26     10188832.44
      3699467.86     10189061.06
#Sta/Elev= 30
  4407.8  336.99  4477.6  332.37  4561.1   328.9  4577.5   327.4  4582.6  327.84
    4602  326.39  4693.9  322.47  4755.2  320.52  4785.9   318.6  4857.4  316.19
  4866.9  315.28    4872  315.71  4928.9  313.16  4965.4  312.52    4980   312.8
  4990.2  311.86  4997.7  304.78  5003.1  304.78  5004.7  303.96  5008.2  303.96
  5012.8  309.82 5016.29311.8683  5021.2  314.75  5027.3  313.71  5035.9  313.55
  5077.9  313.79  5214.2  315.98  5285.5  319.54  5365.3  321.53  5393.6  323.19
#Mann= 5 ,-1 , 0
  4407.8     .11       0  4965.4     .15       0  4990.2     .09       0
 5016.29     .15       0  5077.9     .11       0
Bank Sta=4990.2,5016.29
XS Rating Curve= 0 ,0
Exp/Cntr=0.3,0.1

Type RM Length L Ch R = 1 ,6975    ,498,498,498
BEGIN DESCRIPTION:
CCLC 074 10.0
END DESCRIPTION:
XS GIS Cut Line= 3
      3700317.83     10188561.06      3699708.05     10188360.57
      3699417.82      10188611.1
#Sta/Elev= 30
  4358.1   333.8    4374  332.15  4379.2   332.4  4405.8  330.49  4421.2  330.36
  4463.3  328.25    4533  323.44  4652.8  318.99    4692  316.42  4863.4   311.7
  4951.6  310.74  4958.1  311.41  4972.8309.0769  4978.1  307.71  4983.4  307.96
  4995.7  302.55  5003.4  303.05  5007.6  306.65  5014.2  306.33 5025.58309.0464
  5036.2  310.28    5057  310.42  5078.9  309.34  5106.4  309.07    5114  310.04
  5177.7  312.44  5284.1  314.09  5290.9  314.95  5326.9  316.55  5383.4  318.05
#Mann= 3 , 0 , 0
  4358.1     .11       0  4972.8     .06       0 5025.58     .11       0
Bank Sta=4972.8,5025.58
XS Rating Curve= 0 ,0
Exp/Cntr=0.3,0.1

Type RM Length L Ch R = 1 ,6477    ,499,499,499
BEGIN DESCRIPTION:
CCLC 074 9.0
END DESCRIPTION:
XS GIS Cut Line= 3
      3700267.88     10187461.05      3699668.45     10187886.56
      3699067.88     10188511.04
#Sta/Elev= 30
  4264.9  325.88  4515.9  314.85  4536.8  313.05  4551.6  310.13  4587.2  313.31
    4602   310.5  4608.3  307.82  4616.8  308.25  4622.9  310.48  4637.7   312.3
  4688.1  312.18  4860.3  310.15  4881.2  308.52  4889.9  305.67    4896   305.9
  4902.6   303.1  4931.7  309.13  4952.6  310.27  4982.1  309.91  4988.5   306.3
  4995.1  301.85  4998.6  301.85  4999.6  303.83    5004  303.83 5007.65306.2909
  5010.6  308.28  5017.8  307.63    5032  308.97  5201.5  306.28  5866.4   326.8
#Mann= 3 , 0 , 0
  4264.9     .11       0  4988.5     .06       0 5007.65     .11       0
Bank Sta=4988.5,5007.65
XS Rating Curve= 0 ,0
Exp/Cntr=0.3,0.1

Type RM Length L Ch R = 1 ,5978    ,499,499,499
BEGIN DESCRIPTION:
CCLC 074 8.0
END DESCRIPTION:
XS GIS Cut Line= 3
      3700217.88     10187211.06      3699635.13     10187395.36
      3699167.86     10187911.06
#Sta/Elev= 30
  4388.8  325.88  4604.1  314.71  4609.4  315.37  4701.1  311.59  4787.4  305.61
  4840.8  304.99  4881.8  306.49  4913.2  306.04  4932.5  304.82  4937.7  305.39
  4955.2  304.18  4964.8  304.43  4970.1  305.95  4976.2  306.16  4986.7  303.72
  4995.9  300.94    5000  300.94  5000.4  299.82  5008.9  300.51  5016.4  302.55
 5026.78303.8387  5030.6  304.45  5037.3  302.75  5044.8  304.08  5051.5   302.8
  5058.9  303.63  5165.1  303.47    5236  306.58  5342.1  306.77  5695.9  312.76
#Mann= 3 , 0 , 0
  4388.8     .11       0  4986.7     .06       0 5026.78     .11       0
Bank Sta=4986.7,5026.78
XS Rating Curve= 0 ,0
Exp/Cntr=0.3,0.1

Type RM Length L Ch R = 1 ,5479    ,421,421,421
BEGIN DESCRIPTION:
CCLC 074 7.0
END DESCRIPTION:
XS GIS Cut Line= 3
       3700217.9     10187061.08      3699618.25     10186924.53
      3698717.87     10186811.07
#Sta/Elev= 30
    4385  327.27  4487.6  321.77  4586.4  315.28  4725.7  308.28  4763.6  305.22
  4768.8  305.94  4811.8  302.69    4860  301.92  4928.6  302.29  4959.4  301.38
  4979.9  301.92    4989  300.06  4994.2  301.16  4995.9  295.38  5002.7  295.88
  5010.5  301.68  5020.6  302.56  5071.8   301.7  5101.2  302.65  5252.4  301.07
  5312.8  301.67  5322.9  299.61    5333  299.98  5343.1  301.59  5373.3  300.76
  5474.1  301.55  5645.5  306.57  5695.9  308.68  5784.5   314.3  5907.5  318.23
#Mann= 3 , 0 , 0
    4385     .11       0  4979.9     .06       0  5010.5     .11       0
Bank Sta=4979.9,5010.5
XS Rating Curve= 0 ,0
Exp/Cntr=0.3,0.1

Type RM Length L Ch R = 1 ,5058    ,499,499,499
BEGIN DESCRIPTION:
CCLC 074 6.0
END DESCRIPTION:
XS GIS Cut Line= 3
      3700167.81     10186511.07      3699569.32     10186514.41
      3698967.83     10186411.07
#Sta/Elev= 30
  4401.5  320.27  4421.5  319.42  4481.5   312.9  4531.5  313.11  4551.5  311.51
  4701.5   305.5  4751.5  302.41  4921.5   298.8  4981.5  299.34  4991.5  298.32
  4998.2  296.18  5009.9  295.61  5013.4  295.61 5018.48298.3834  5021.8  299.93
  5031.9  300.84  5042.1  299.29  5082.7  299.48  5113.2  298.16  5133.4  299.21
  5168.1  298.57  5194.3  299.43  5214.6  297.75  5228.1  297.73  5234.9  296.53
  5265.3  299.94    5348  299.18  5462.9  302.24  5559.5  307.32  5610.3  311.18
#Mann= 3 , 0 , 0
  4401.5     .11       0  4991.5     .06       0 5018.48     .11       0
Bank Sta=4991.5,5018.48
XS Rating Curve= 0 ,0
Exp/Cntr=0.3,0.1

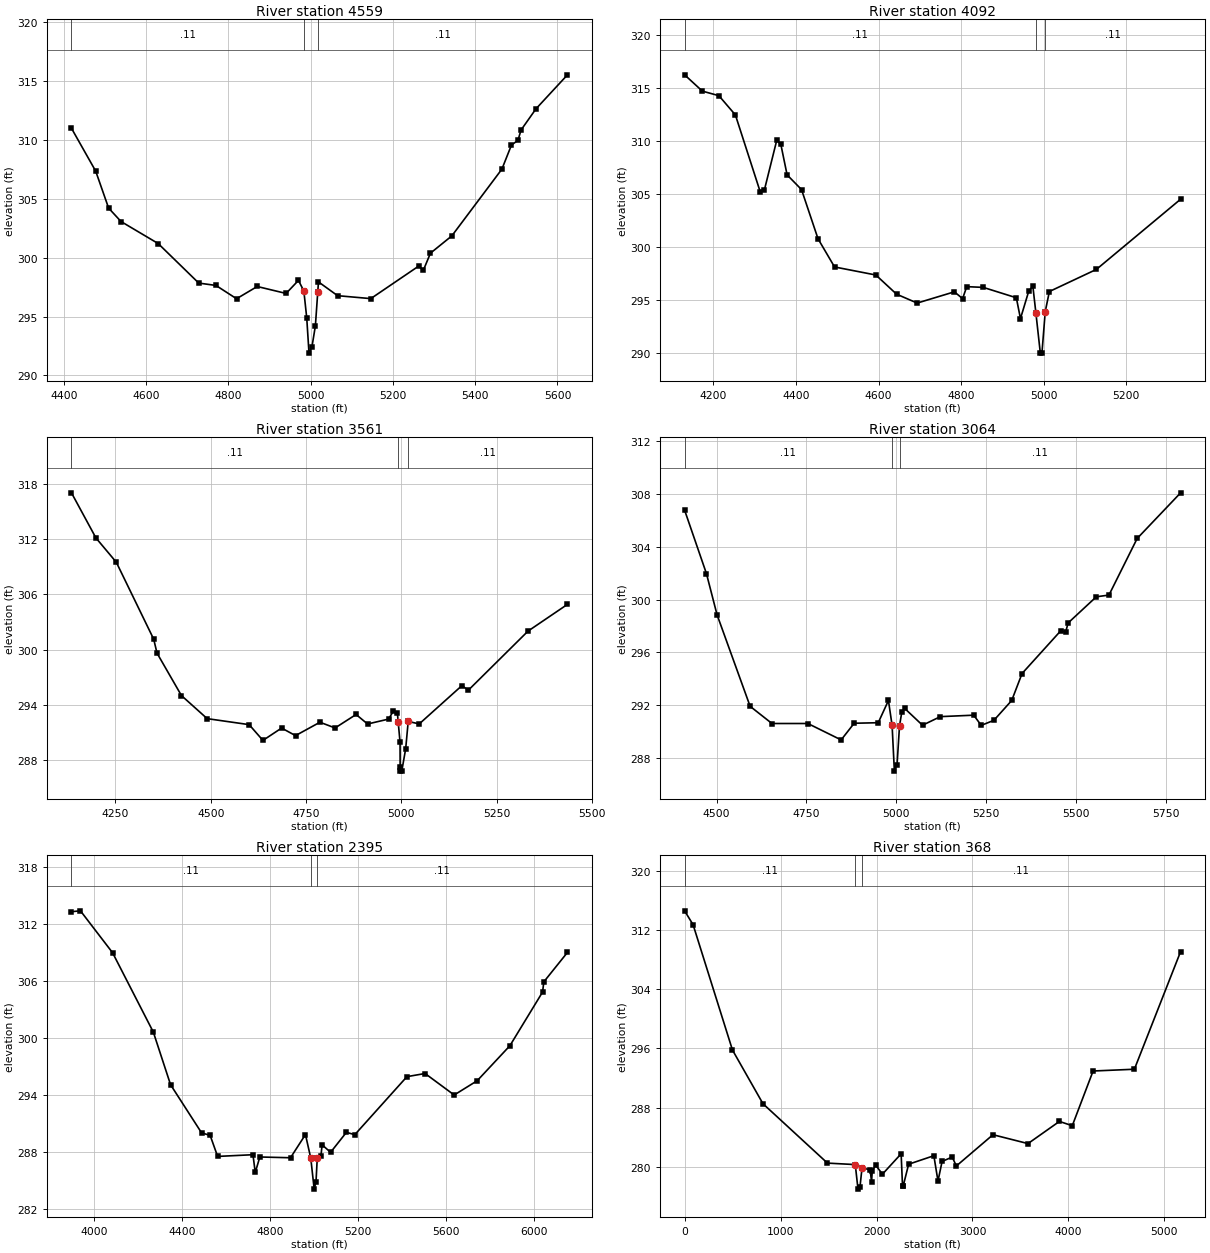
Type RM Length L Ch R = 1 ,4559    ,467,467,467
BEGIN DESCRIPTION:
CCLC 074 5.0
END DESCRIPTION:
XS GIS Cut Line= 3
      3700017.89     10186061.07      3699438.35     10186107.54
      3698867.85     10186361.07
#Sta/Elev= 30
  4418.6  310.99  4477.5  307.35  4508.9  304.21    4539  303.07  4629.3   301.2
    4728  297.84  4769.8  297.64  4819.9  296.51  4870.1  297.55  4940.3  296.96
  4970.4  298.07  4983.5  297.16  4990.5  294.88    4996  291.89    5003  292.39
  5011.5   294.2 5017.34297.1122    5019  297.94  5065.5  296.77  5146.2  296.52
  5262.5  299.28  5274.1  298.94  5291.2  300.38  5343.2  301.85  5464.9  307.52
  5488.2  309.57  5503.9  309.96  5511.4  310.84  5547.7  312.64  5624.3  315.53
#Mann= 3 , 0 , 0
  4418.6     .11       0  4983.5     .06       0 5017.34     .11       0
Bank Sta=4983.5,5017.34
XS Rating Curve= 0 ,0
Exp/Cntr=0.3,0.1

Type RM Length L Ch R = 1 ,4092    ,531,531,531
BEGIN DESCRIPTION:
CCLC 074 4.0
END DESCRIPTION:
XS GIS Cut Line= 3
      3700180.82     10185749.18       3699243.3     10185775.22
      3699017.85     10185911.07
#Sta/Elev= 30
  4130.3  316.25  4173.3  314.71  4213.3  314.28  4253.3  312.46  4313.3  305.21
  4323.3  305.34  4353.4  310.06  4363.4  309.67  4378.5   306.8  4413.4  305.41
  4453.4  300.76  4493.4   298.1  4593.4  297.34  4643.5  295.53  4693.5  294.69
  4783.5  295.75  4803.5  295.11  4813.5  296.24  4853.5  296.17  4933.6  295.19
  4943.6  293.22  4963.6  295.81  4973.6  296.29 4981.08293.7094  4991.7  289.96
  4995.6  289.96  5003.6  293.89  5013.6  295.78  5127.5  297.87  5331.4   304.5
#Mann= 3 , 0 , 0
  4130.3     .11       0 4981.08     .06       0  5003.6     .11       0
Bank Sta=4981.08,5003.6
XS Rating Curve= 0 ,0
Exp/Cntr=0.3,0.1

Type RM Length L Ch R = 1 ,3561    ,497,497,497
BEGIN DESCRIPTION:
CCLC 074 3.0
END DESCRIPTION:
XS GIS Cut Line= 3
      3700017.89     10185011.06      3699208.12     10185316.62
      3698817.88     10185511.06
#Sta/Elev= 30
  4134.5  317.01  4198.7  312.12  4252.1  309.49  4350.3  301.14    4359  299.63
  4423.1  295.03  4490.6  292.53  4600.7  291.88  4636.9  290.17  4685.9  291.51
  4722.4  290.69  4786.5  292.14  4826.2  291.52  4881.3  292.98  4911.5  291.95
  4966.5  292.48  4978.9  293.33  4989.6  293.18 4991.77292.1928  4996.7  289.95
  4996.9  287.34  4997.3  286.84  5001.2  286.84  5011.5  289.28 5018.08292.2237
  5047.1  291.96    5159  296.11  5175.8  295.61  5332.5  302.02    5436  304.92
#Mann= 3 , 0 , 0
  4134.5     .11       0 4991.77     .06       0 5018.08     .11       0
Bank Sta=4991.77,5018.08
XS Rating Curve= 0 ,0
Exp/Cntr=0.3,0.1

Type RM Length L Ch R = 1 ,3064    ,669,669,669
BEGIN DESCRIPTION:
CCLC 074 2.0
END DESCRIPTION:
XS GIS Cut Line= 3
      3699867.89     10185011.08      3699286.45     10184917.62
      3698667.85     10185411.07
#Sta/Elev= 30
  4411.1  306.76  4471.9  301.96  4501.4  298.85  4593.4  291.93  4654.2  290.63
  4754.1  290.63  4846.7  289.39  4882.9  290.65  4949.9  290.69  4978.3  292.37
  4988.5  290.48  4994.8  287.03  5002.3  287.53  5009.1  290.45  5015.5   291.5
  5023.5  291.77  5073.1   290.5  5122.8  291.15  5215.6  291.26  5236.5  290.49
  5271.7  290.87  5321.3  292.37  5350.1  294.41  5457.4  297.63  5471.5  297.55
  5478.2  298.23  5556.7  300.21  5591.9  300.34  5670.4  304.62  5791.3  308.07
#Mann= 3 , 0 , 0
  4411.1     .11       0  4988.5     .06       0  5009.1     .11       0
Bank Sta=4988.5,5009.1
XS Rating Curve= 0 ,0
Exp/Cntr=0.3,0.1

Type RM Length L Ch R = 1 ,2395    ,2027,2027,2027
BEGIN DESCRIPTION:
Mapping XS 2f15de67
END DESCRIPTION:
XS GIS Cut Line= 3
      3700170.39     10184587.72      3699107.89     10184285.64
      3698572.13     10185299.93
#Sta/Elev= 30
  3899.1   313.3  3939.9  313.39  4085.8  308.98  4270.8  300.63    4349   295.1
  4489.7  290.04  4528.7  289.77  4562.6  287.56    4723  287.74  4733.4  285.87
  4754.2   287.5  4893.5  287.42  4961.3  289.86 4985.44287.3818  5000.9  284.12
  5009.3  284.92    5015  287.44  5031.4   287.6    5037  288.78  5075.4  287.99
  5147.1  290.09  5185.5  289.85    5422  295.95  5504.4  296.28  5636.5  294.02
  5740.9  295.52  5889.3   299.2  6037.8  304.85  6043.4  305.92  6150.8  309.02
#Mann= 3 , 0 , 0
  3899.1     .11       0 4985.44     .06       0    5015     .11       0
Bank Sta=4985.44,5015
XS Rating Curve= 0 ,0
Exp/Cntr=0.3,0.1

Type RM Length L Ch R = 1 ,368     ,0,0,0
XS GIS Cut Line= 4
      3701223.32     10184160.77      3699692.07     10182593.06
      3699067.07     10183343.06      3698459.77     10185250.18
#Sta/Elev= 30
       0  314.62    88.5  312.74   498.7  295.79   816.9  288.52  1488.7  280.49
  1778.6  280.29  1806.9  276.97  1828.2  277.31  1849.3  279.89  1934.2  279.55
  1948.3  277.94  1955.5  279.41  1990.7  280.23  2061.5  278.99  2256.6  281.75
  2270.9  277.43  2278.7  277.43  2334.7  280.34  2597.6  281.49  2640.6  278.06
  2683.5  280.72    2789  281.31  2831.9   280.1  3213.7  284.33  3578.6  283.13
  3906.1  286.13  4040.2  285.55  4257.1  292.95  4687.4  293.19  5169.2  309.11
#Mann= 3 , 0 , 0
       0     .11       0  1778.6     .06       0  1849.3     .11       0
Bank Sta=1778.6,1849.3
XS Rating Curve= 0 ,0
Exp/Cntr=0.3,0.1

Chan Stop Cuts=-1
Use User Specified Reach Order=0
Composite Channel Slope=5