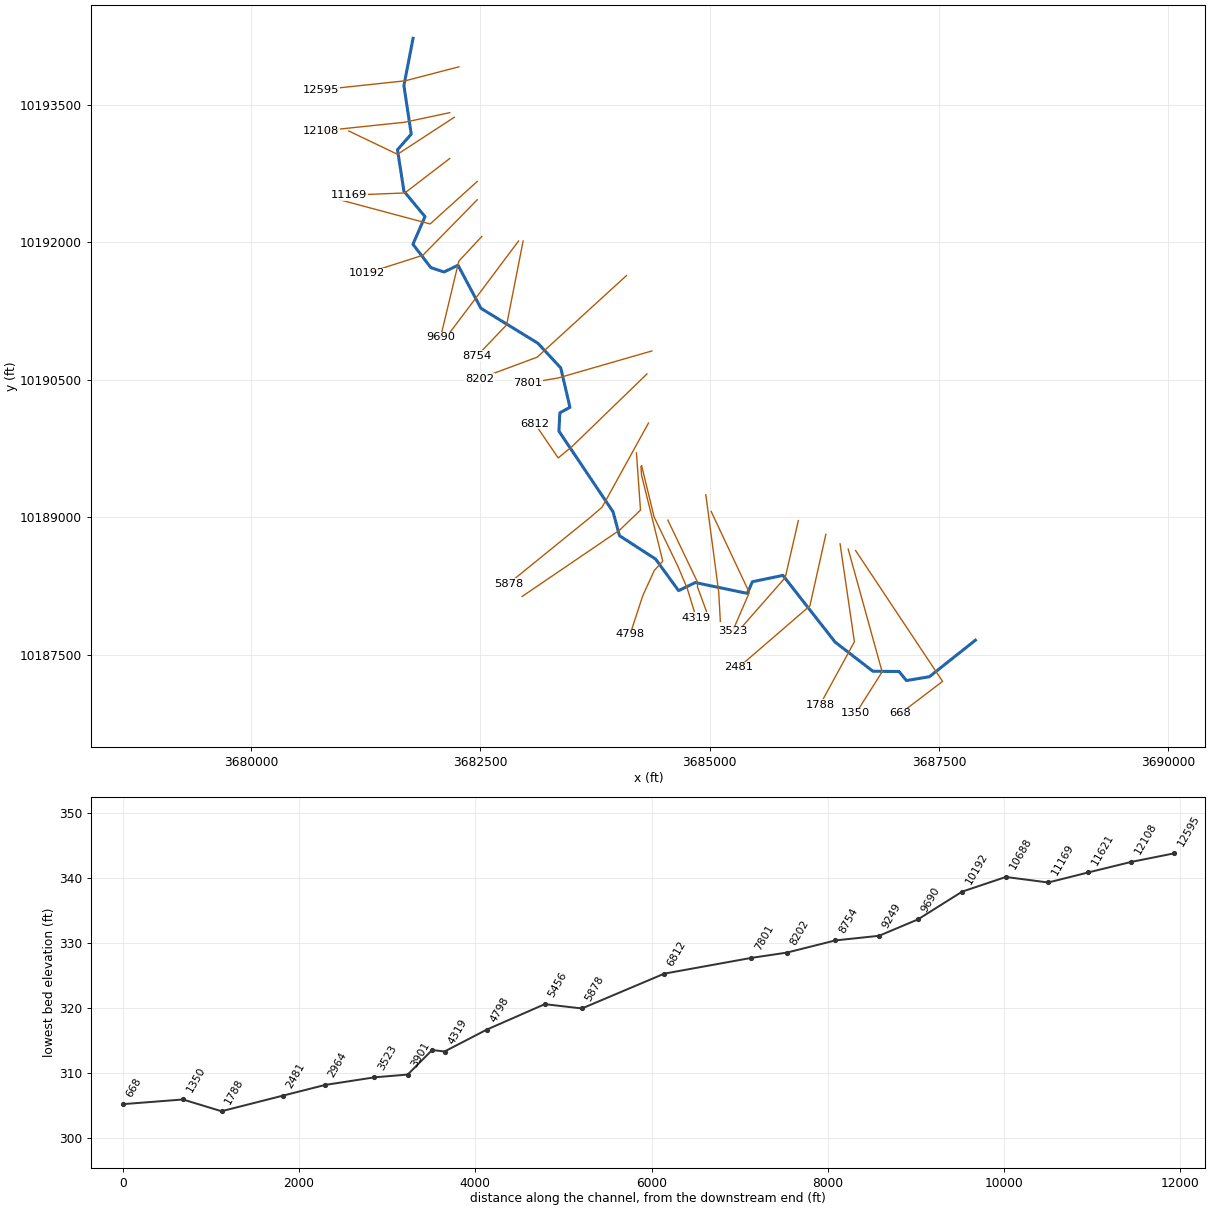
--- CCLC 075.prj (project) ---

Proj Title=CCLC 075 Base Level Engineering
Current Plan=p01
Default Exp/Contr=0.3,0.1
English Units
Geom File=g01
Flow File=f01
Flow File=f02
Plan File=p01
Y Axis Title=Elevation
X Axis Title(PF)=Main Channel Distance
X Axis Title(XS)=Station
BEGIN DESCRIPTION:
CCLC 075
END DESCRIPTION:
DSS Export Rating Curves= 0
DSS Export Rating Curve Sorted= 0
DSS Export Volume Flow Curves= 0
DXF OffsetX= 0
DXF OffsetY= 0
DXF ScaleX= 1
DXF ScaleY= 10

--- CCLC 075.p01 (plan) ---

Plan Title=Multiple Run
Short Identifier=Multiple
Geom File=g01
Flow File=f01
Subcritical Flow
K Sum by GR= 0
Std Step Tol= 0.01
Critical Tol= 0.01
Num of Std Step Trials= 20
Max Error Tol= 0.3
Flow Tol Ratio= 0.001
Split Flow NTrial= 30
Split Flow Tol= 0.02
Split Flow Ratio= 0.02
Log Output Level= 0
Friction Slope Method= 1
Unsteady Friction Slope Method= 2
Unsteady Bridges Friction Slope Method= 1
Parabolic Critical Depth
Global Vel Dist=  1 , 1 , 1
Global Log Level= 0
CheckData=True
Encroach Param= -1, 0, 0, 0
BEGIN DESCRIPTION:
Multiple Run
END DESCRIPTION:

--- CCLC 075.f01 (steady flow) ---

Flow Title=Multiple
Program Version=4.10
Number of Profiles= 7
Profile Names=10-year,25-year,50-year,1pct_min,100-year,1pct_plu,500-year
River Rch & RM=CCLC 075,Reach-1         ,12595
     663     905    1229     549    1658    5007    3122
River Rch & RM=CCLC 075,Reach-1         ,9249
     733    1000    1357     605    1828    5520    3433
River Rch & RM=CCLC 075,Reach-1         ,5878
    1435    2037    2838    1297    3917   11829    7730
River Rch & RM=CCLC 075,Reach-1         ,4319
    1435    2037    2838    1297    3917   11829    7730
Boundary for River Rch & Prof#=CCLC 075,Reach-1         , 1
Up Type= 0
Dn Type= 3
Dn Slope=0.005
Boundary for River Rch & Prof#=CCLC 075,Reach-1         , 2
Up Type= 0
Dn Type= 3
Dn Slope=0.005
Boundary for River Rch & Prof#=CCLC 075,Reach-1         , 3
Up Type= 0
Dn Type= 3
Dn Slope=0.005
Boundary for River Rch & Prof#=CCLC 075,Reach-1         , 4
Up Type= 0
Dn Type= 3
Dn Slope=0.005
Boundary for River Rch & Prof#=CCLC 075,Reach-1         , 5
Up Type= 0
Dn Type= 3
Dn Slope=0.005
Boundary for River Rch & Prof#=CCLC 075,Reach-1         , 6
Up Type= 0
Dn Type= 3
Dn Slope=0.005
Boundary for River Rch & Prof#=CCLC 075,Reach-1         , 7
Up Type= 0
Dn Type= 3
Dn Slope=0.005
DSS Import GetInterval= 0
DSS Import GetPeak= 0
DSS Import FillOption= 0

--- CCLC 075.f02 (steady flow) ---

Flow Title=Orig_BLE_Flows
Program Version=4.10
Number of Profiles= 7
Profile Names=10-year,25-year,50-year,1pct_min,100-year,1pct_plu,500-year
River Rch & RM=CCLC 075,Reach-1         ,12595
     663     887    1069     422    1275    3852    1815
River Rch & RM=CCLC 075,Reach-1         ,9249
     733     980    1180     466    1406    4247    1996
River Rch & RM=CCLC 075,Reach-1         ,5878
    1435    1997    2468     998    3013    9100    4494
River Rch & RM=CCLC 075,Reach-1         ,4319
    1435    1997    2468     998    3013    9100    4494
Boundary for River Rch & Prof#=CCLC 075,Reach-1         , 1
Up Type= 0
Dn Type= 3
Dn Slope=0.005
Boundary for River Rch & Prof#=CCLC 075,Reach-1         , 2
Up Type= 0
Dn Type= 3
Dn Slope=0.005
Boundary for River Rch & Prof#=CCLC 075,Reach-1         , 3
Up Type= 0
Dn Type= 3
Dn Slope=0.005
Boundary for River Rch & Prof#=CCLC 075,Reach-1         , 4
Up Type= 0
Dn Type= 3
Dn Slope=0.005
Boundary for River Rch & Prof#=CCLC 075,Reach-1         , 5
Up Type= 0
Dn Type= 3
Dn Slope=0.005
Boundary for River Rch & Prof#=CCLC 075,Reach-1         , 6
Up Type= 0
Dn Type= 3
Dn Slope=0.005
Boundary for River Rch & Prof#=CCLC 075,Reach-1         , 7
Up Type= 0
Dn Type= 3
Dn Slope=0.005
DSS Import GetInterval= 0
DSS Import GetPeak= 0
DSS Import FillOption= 0

--- CCLC 075.g01 (geometry) ---

Geom Title=Existing Conditions
Program Version=4.10

River Reach=CCLC 075        ,Reach-1
Reach XY= 30
      3681768.23     10194221.84      3681668.23     10193706.84
      3681748.23     10193176.84      3681598.23     10193006.84
      3681668.61     10192554.45      3681898.23     10192276.84
      3681766.98      10191975.6      3681962.24      10191720.6
      3682106.01     10191673.55      3682258.23     10191746.84
      3682508.23     10191276.84      3683128.23     10190896.84
      3683378.23     10190626.84      3683478.23     10190196.84
      3683368.23     10190136.84      3683358.23     10189936.84
      3683948.23     10189056.84      3684018.23     10188796.84
      3684412.16     10188541.42      3684662.39     10188197.51
      3684844.04      10188285.4      3685412.37     10188167.23
      3685467.17     10188294.41      3685799.83     10188363.75
      3686367.85     10187636.93      3686780.72     10187318.23
      3687065.86     10187315.47      3687146.25     10187216.83
      3687395.84     10187258.14      3687898.23     10187656.84

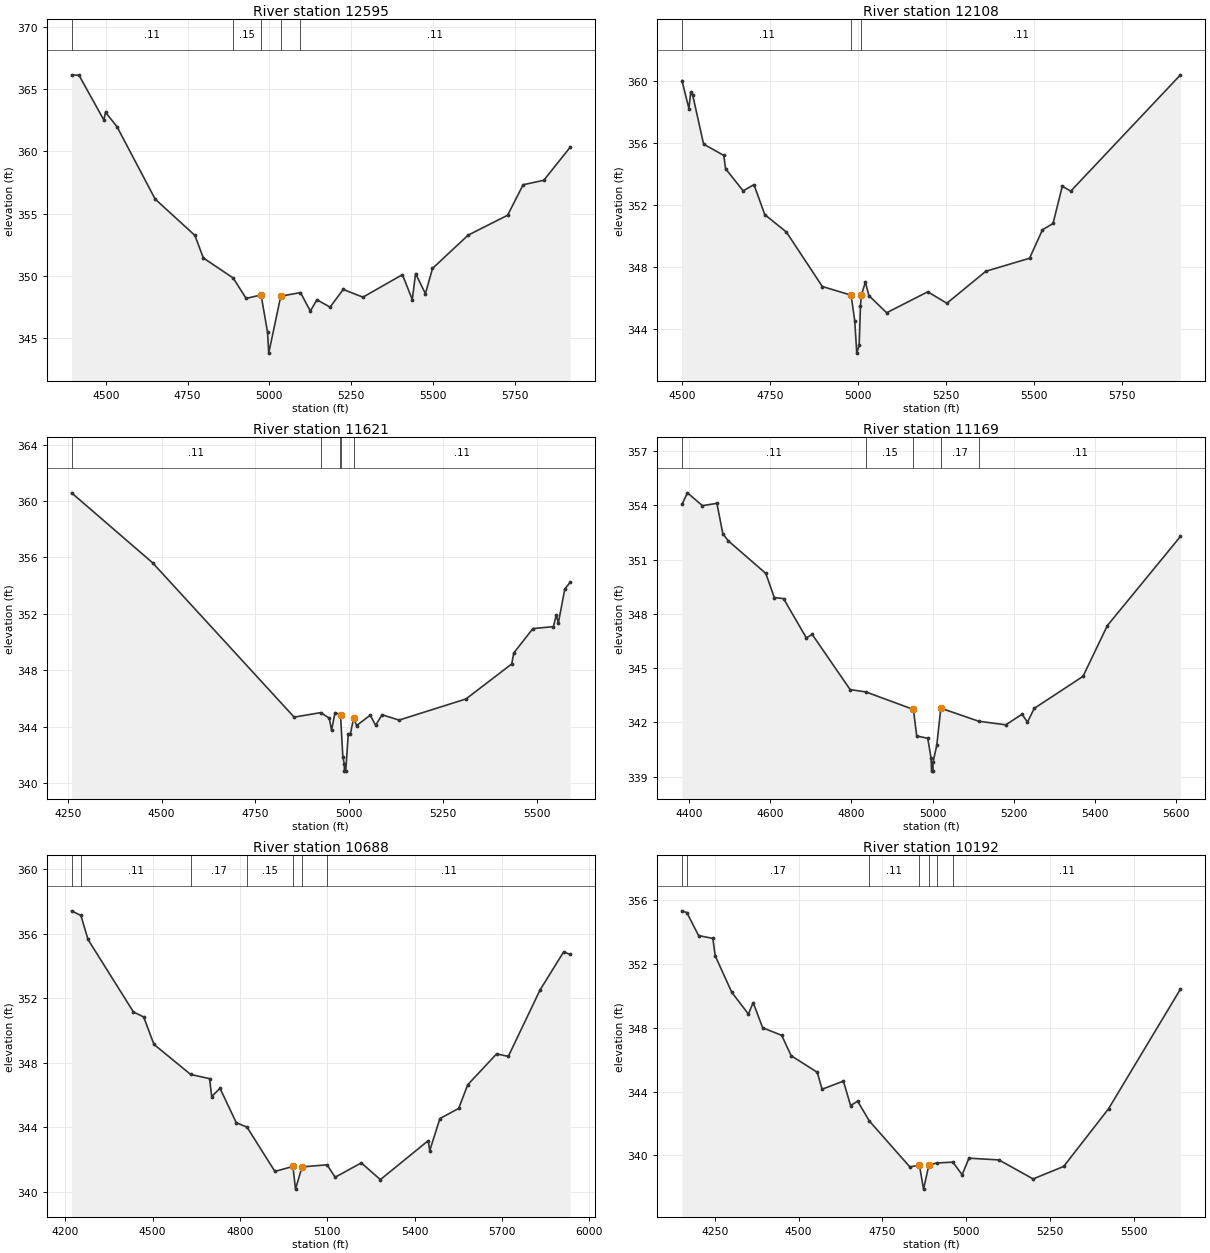
Type RM Length L Ch R = 1 ,12595   ,487,487,487
BEGIN DESCRIPTION:
CCLC 075 21.0
END DESCRIPTION:
XS GIS Cut Line= 3
      3682267.82     10193911.06      3681682.55      10193758.6
      3680767.84     10193661.07
#Sta/Elev= 30
  4395.2  366.16    4418  366.12  4493.8  362.53    4499  363.15  4534.3  361.98
  4650.7  356.17  4772.2  353.25  4798.2  351.43  4889.5  349.82    4929  348.18
  4974.7  348.46  4994.5  345.47  4998.1  343.78  5034.9  348.36  5095.3  348.65
  5125.4  347.16  5145.5  348.07  5185.7  347.48    5226   348.9  5286.3  348.28
    5407  350.09  5437.2  348.09  5447.2  350.18  5477.4  348.56    5499  350.59
  5608.1  353.27  5728.8  354.87  5776.2  357.32  5839.4  357.68  5919.9  360.33
#Mann= 5 ,-1 , 0
  4395.2     .11       0  4889.5     .15       0  4974.7     .09       0
  5034.9     .15       0  5095.3     .11       0
Bank Sta=4974.7,5034.9
XS Rating Curve= 0 ,0
Exp/Cntr=0.3,0.1

Type RM Length L Ch R = 1 ,12108   ,487,487,487
BEGIN DESCRIPTION:
CCLC 075 20.0
END DESCRIPTION:
XS GIS Cut Line= 3
      3682167.86     10193411.07      3681678.23     10193306.84
      3680767.85     10193211.07
#Sta/Elev= 30
  4499.4  360.01  4519.1  358.21  4524.2  359.27  4530.1  359.05  4560.8  355.92
  4618.2  355.19  4623.3  354.33  4673.2  352.91  4703.9  353.31  4734.6  351.38
  4795.9  350.26  4898.1  346.75  4979.9  346.19  4990.2  344.53  4995.9  342.46
  5002.7  342.96  5006.4   345.5 5009.04346.2128  5020.5  347.03  5030.5  346.16
  5080.8  345.06  5197.5  346.41  5251.8  345.67  5362.4  347.73  5486.7  348.57
  5523.3   350.4  5553.4  350.81  5579.7  353.21  5603.7  352.89  5915.4  360.38
#Mann= 3 , 0 , 0
  4499.4     .11       0  4979.9     .06       0 5009.04     .11       0
Bank Sta=4979.9,5009.04
XS Rating Curve= 0 ,0
Exp/Cntr=0.3,0.1

Type RM Length L Ch R = 1 ,11621   ,452,452,452
BEGIN DESCRIPTION:
CCLC 075 19.0
END DESCRIPTION:
XS GIS Cut Line= 3
      3682217.84     10193361.06      3681598.23     10192956.84
      3681067.82     10193211.09
#Sta/Elev= 30
  4260.2  360.58  4475.9  355.62  4853.1  344.67  4923.7  344.99  4946.6   344.6
  4952.7  343.74  4961.7  344.95    4975   344.9  4976.6  344.84  4982.8  341.86
  4986.8  341.34    4987  340.84  4990.5  340.84  4997.2  343.48    5003  343.48
  5011.5  344.62  5019.2  344.07  5055.9  344.81  5070.1  344.09  5087.2  344.84
  5132.5  344.46  5310.9  345.96  5432.6  348.44  5438.1  349.22    5489  350.95
  5543.8  351.09  5551.4  351.92  5556.9  351.35  5574.1  353.76  5588.2  354.23
#Mann= 5 ,-1 , 0
  4260.2     .11       0  4923.7     .15       0    4975     .11       0
  4976.6     .06       0  5011.5     .11       0
Bank Sta=4976.6,5011.5
XS Rating Curve= 0 ,0
Exp/Cntr=0.3,0.1

Type RM Length L Ch R = 1 ,11169   ,481,481,481
BEGIN DESCRIPTION:
CCLC 075 18.0
END DESCRIPTION:
XS GIS Cut Line= 3
      3682167.82     10192911.05       3681678.2     10192535.28
      3681067.88     10192511.07
#Sta/Elev= 30
  4382.8  354.05  4396.3  354.69  4433.2  353.98  4468.9  354.11  4483.4  352.43
  4496.2  352.05  4589.4  350.23  4610.2   348.9    4633  348.84  4689.1  346.67
  4703.6  346.86    4797  343.81  4835.8  343.68  4952.9  342.71  4961.1  341.24
  4988.2  341.12  4996.4  340.02  4997.6   339.3  5001.1   339.3  5001.3   339.8
  5010.4  340.72  5020.4  342.78  5113.7  342.06  5180.5  341.86  5220.5  342.45
  5233.9  342.01  5250.5  342.77  5370.6  344.54  5430.7  347.35  5610.8  352.28
#Mann= 5 ,-1 , 0
  4382.8     .11       0  4835.8     .15       0  4952.9     .09       0
  5020.4     .17       0  5113.7     .11       0
Bank Sta=4952.9,5020.4
XS Rating Curve= 0 ,0
Exp/Cntr=0.3,0.1

Type RM Length L Ch R = 1 ,10688   ,496,496,496
BEGIN DESCRIPTION:
CCLC 075 17.0
END DESCRIPTION:
XS GIS Cut Line= 3
      3682467.84     10192661.06      3681954.24      10192197.1
      3680967.88     10192461.06
#Sta/Elev= 30
  4221.5  357.43  4253.6  357.14  4277.9  355.65  4434.1  351.15  4469.2  350.84
  4504.5  349.14  4630.7  347.27  4695.6  347.01  4703.1   345.9  4731.5  346.41
  4787.6  344.27  4824.3     344  4920.2  341.25  4982.1  341.56    4991  340.15
  5013.4  341.53  5099.3  341.66  5127.3  340.89  5217.2  341.78  5282.6  340.74
  5447.1  343.16  5452.3  342.54  5487.2  344.53  5551.7  345.16  5582.8  346.63
  5682.2  348.55  5722.3  348.39  5831.2  352.51  5912.1  354.87  5934.7  354.73
#Mann= 7 ,-1 , 0
  4221.5     .17       0  4253.6     .11       0  4630.7     .17       0
  4824.3     .15       0  4982.1     .09       0  5013.4     .15       0
  5099.3     .11       0
Bank Sta=4982.1,5013.4
XS Rating Curve= 0 ,0
Exp/Cntr=0.3,0.1

Type RM Length L Ch R = 1 ,10192   ,502,502,502
BEGIN DESCRIPTION:
CCLC 075 16.0
END DESCRIPTION:
XS GIS Cut Line= 3
      3682467.87     10192461.09      3681875.11     10191855.65
      3681267.83     10191661.06
#Sta/Elev= 30
  4152.7  355.33  4167.2  355.22  4202.2  353.78  4244.7   353.6  4251.7  352.51
  4301.2  350.22  4350.7  348.86  4364.8  349.58  4393.1     348  4449.7  347.53
    4478  346.25  4555.8  345.21    4570  344.15  4633.6  344.66  4654.9  343.13
    4676   343.4  4710.9  342.16  4831.6  339.28  4859.9   339.4  4872.3  337.89
  4888.2   339.4  4911.1  339.53  4959.8  339.58  4987.2  338.79  5007.6  339.83
  5096.9  339.72  5198.6  338.53  5289.7  339.31  5423.5  342.93  5637.7  350.43
#Mann= 7 ,-1 , 0
  4152.7     .11       0  4167.2     .17       0  4710.9     .11       0
  4859.9     .06       0  4888.2     .11       0  4911.1     .15       0
  4959.8     .11       0
Bank Sta=4859.9,4888.2
XS Rating Curve= 0 ,0
Exp/Cntr=0.3,0.1

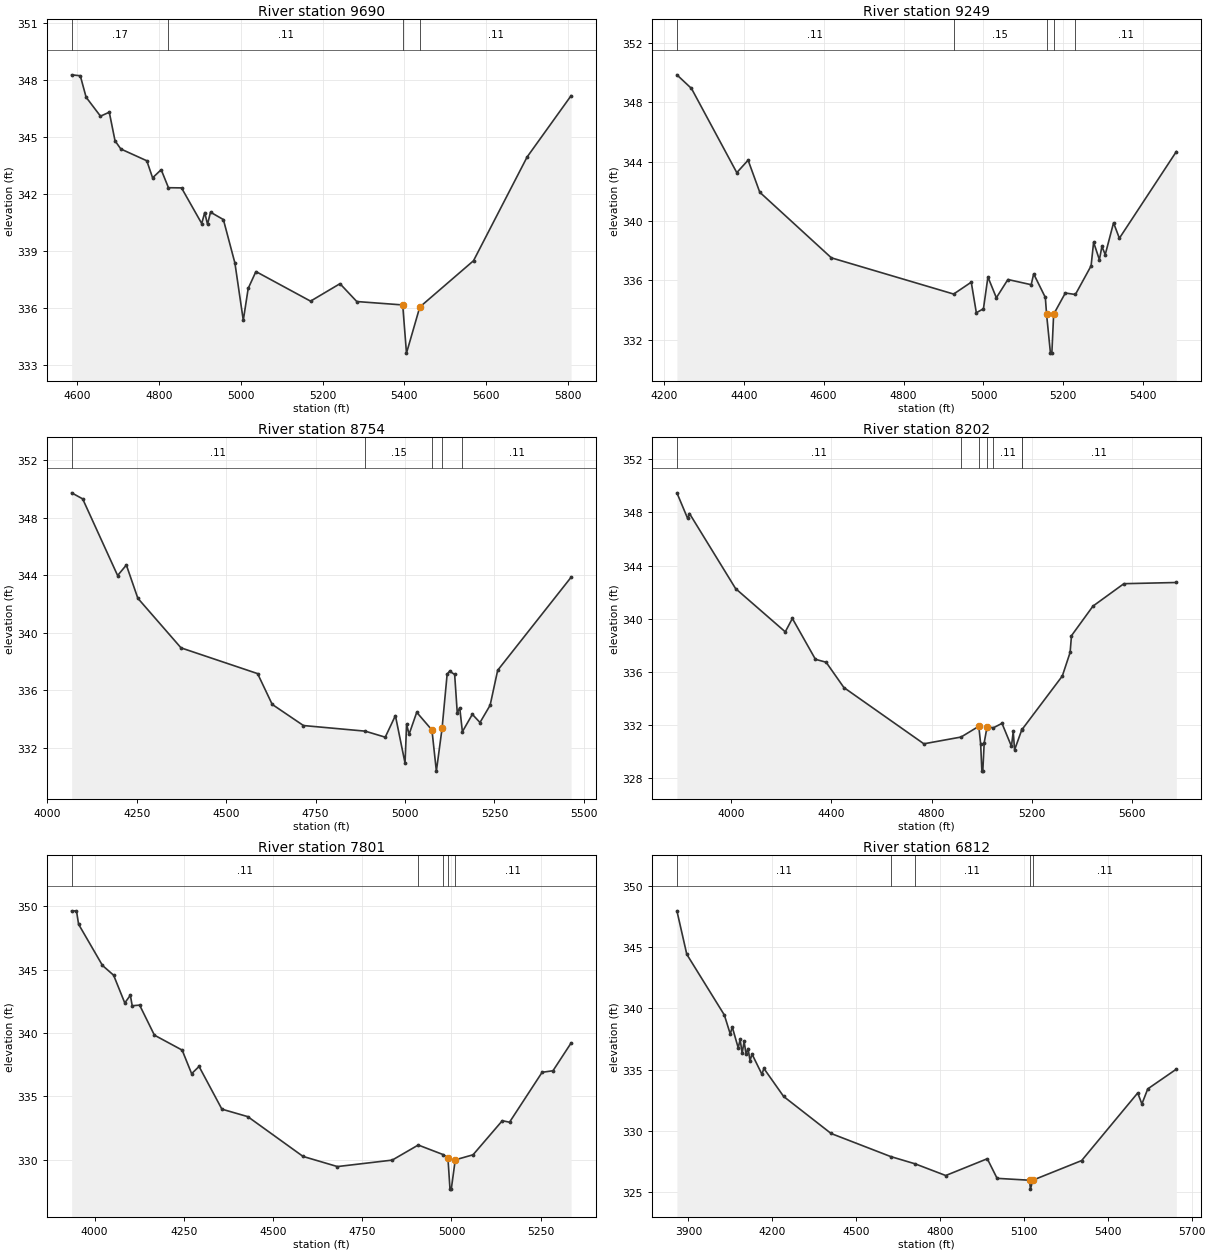
Type RM Length L Ch R = 1 ,9690    ,441,441,441
BEGIN DESCRIPTION:
CCLC 075 15.0
END DESCRIPTION:
XS GIS Cut Line= 3
      3682517.83     10192061.05      3682266.74     10191790.85
      3682067.86      10190961.1
#Sta/Elev= 30
  4585.9  348.28  4607.1  348.23  4621.3   347.1  4656.5   346.1    4678  346.31
  4692.1   344.8  4706.3  344.37  4769.8  343.75    4784  342.85    4805  343.28
  4822.8  342.33  4854.8  342.32  4904.2  340.44  4911.5  341.02  4918.4   340.4
  4925.7  341.04  4957.2  340.65  4985.4  338.36  5005.9  335.34  5017.9  337.02
  5036.8  337.91  5170.5  336.35  5242.5  337.27  5283.6  336.33    5396  336.15
  5405.2  333.61  5437.8  336.04  5569.2  338.48  5700.4  343.95    5808  347.18
#Mann= 4 ,-1 , 0
  4585.9     .17       0  4822.8     .11       0    5396     .06       0
  5437.8     .11       0
Bank Sta=5396,5437.8
XS Rating Curve= 0 ,0
Exp/Cntr=0.3,0.1

Type RM Length L Ch R = 1 ,9249    ,495,495,495
BEGIN DESCRIPTION:
CCLC 075 14.0
END DESCRIPTION:
XS GIS Cut Line= 3
      3682917.88     10192011.11      3682458.23     10191396.84
      3682167.88     10191011.11
#Sta/Elev= 30
  4232.8  349.84  4269.3  348.92  4382.7  343.25    4411  344.09  4440.2  341.93
  4619.4  337.51  4925.4  335.07  4969.5  335.87  4982.2  333.81    5000  334.08
  5011.2  336.22  5032.3  334.82  5061.2  336.05  5119.5   335.7  5125.7  336.43
  5154.9  334.84 5158.02333.6977  5167.7  331.09  5171.2  331.09  5175.7  333.71
  5204.9  335.14  5230.1  335.04  5269.4  336.97  5275.7  338.56  5290.2  337.38
  5296.5  338.28  5304.8  337.73  5325.6  339.87  5340.2  338.83  5482.8  344.67
#Mann= 5 ,-1 , 0
  4232.8     .11       0  4925.4     .15       0 5158.02     .09       0
  5175.7     .15       0  5230.1     .11       0
Bank Sta=5158.02,5175.7
XS Rating Curve= 0 ,0
Exp/Cntr=0.3,0.1

Type RM Length L Ch R = 1 ,8754    ,552,552,552
BEGIN DESCRIPTION:
CCLC 075 13.0
END DESCRIPTION:
XS GIS Cut Line= 3
      3682967.85     10192011.07      3682788.23     10191096.84
      3682467.85     10190761.07
#Sta/Elev= 30
  4068.3  349.73  4099.1  349.31  4196.8  343.98  4221.2  344.71  4253.3   342.4
    4374  338.95    4588  337.16  4628.8  335.02  4716.1  333.55  4888.6  333.16
  4944.7  332.74  4973.1  334.24    5000  330.94  5004.4  333.64  5011.3  332.94
  5032.7  334.47  5075.2  333.24  5087.6  330.38  5103.5  333.35  5117.7  337.12
  5124.6  337.33  5138.7   337.1    5146  334.42  5152.9  334.79  5160.3  333.12
  5188.1  334.33  5209.5  333.76  5237.8  334.96  5258.9  337.39  5464.1  343.86
#Mann= 5 ,-1 , 0
  4068.3     .11       0  4888.6     .15       0  5075.2     .09       0
  5103.5     .15       0  5160.3     .11       0
Bank Sta=5075.2,5103.5
XS Rating Curve= 0 ,0
Exp/Cntr=0.3,0.1

Type RM Length L Ch R = 1 ,8202    ,401,401,401
BEGIN DESCRIPTION:
CCLC 075 12.0
END DESCRIPTION:
XS GIS Cut Line= 3
      3684094.87      10191634.6      3683120.91     10190743.97
      3682491.78       10190510.
#Sta/Elev= 30
    3785  349.48  3827.8  347.55  3835.2  347.92    4019  342.26    4217     339
  4245.3  340.01  4337.2  336.93  4379.8  336.71  4450.7   334.8  4769.5  330.56
  4917.8  331.07  4988.4  331.88  4995.8  330.56  5000.8   328.5  5004.4   328.5
    5010  330.64 5021.36331.8328  5046.9  331.77  5080.9   332.1  5118.7  330.37
  5125.7  331.49  5131.1   330.1  5159.5   331.6  5161.7  331.66  5321.4  335.67
  5352.5  337.45  5357.9  338.71  5443.6  340.94  5566.8  342.63    5776  342.72
#Mann= 7 ,-1 , 0
    3785     .11       0  4917.8     .15       0  4988.4     .09       0
 5021.36     .15       0  5046.9     .11       0  5159.5     .15       0
  5161.7     .11       0
Bank Sta=4988.4,5021.36
XS Rating Curve= 0 ,0
Exp/Cntr=0.3,0.1

Type RM Length L Ch R = 1 ,7801    ,989,989,989
BEGIN DESCRIPTION:
CCLC 075 11.0
END DESCRIPTION:
XS GIS Cut Line= 3
      3684370.88     10190811.67      3683348.23     10190516.84
      3683017.81     10190461.06
#Sta/Elev= 30
  3935.7  349.65  3949.3  349.64  3955.2  348.59  4022.1  345.34  4053.3  344.57
  4084.6  342.38  4100.2  342.99  4105.4  342.16  4126.2  342.21  4167.6  339.84
  4245.3  338.66  4271.9   336.8  4292.7  337.37  4356.7     334  4429.2  333.41
  4584.1  330.27  4680.4  329.47  4833.9  329.98  4906.8  331.17  4976.2  330.42
    4990  330.16  4995.8  327.69  4999.4  327.69  5010.5     330  5060.4   330.4
  5142.4  333.09  5162.6  332.97  5253.9  336.91  5284.3  337.03  5335.1  339.22
#Mann= 5 ,-1 , 0
  3935.7     .11       0  4906.8     .15       0  4976.2     .11       0
    4990     .06       0  5010.5     .11       0
Bank Sta=4990,5010.5
XS Rating Curve= 0 ,0
Exp/Cntr=0.3,0.1

Type RM Length L Ch R = 1 ,6812    ,934,934,934
BEGIN DESCRIPTION:
CCLC 075 10.0
END DESCRIPTION:
XS GIS Cut Line= 4
      3684317.85     10190561.07      3683498.23     10189766.84
      3683350.07     10189645.01      3683094.88       10190020.
#Sta/Elev= 30
  3858.7  347.97  3894.1  344.42  4028.4  339.47  4049.7  337.91  4056.6   338.5
    4078  336.79  4084.9  337.47  4092.1  336.35  4099.1  337.32  4106.3  336.26
  4113.2  336.73  4120.4  335.74  4127.4  336.28  4162.9  334.63  4169.8  335.11
  4240.6  332.82  4410.3   329.8  4623.2  327.92  4711.4  327.32  4820.4  326.37
    4969  327.74  5004.1  326.14 5120.05325.9866  5123.5  325.26  5131.8  325.99
  5306.6  327.59  5507.2  333.11  5522.1  332.21  5543.1  333.44  5645.4  335.05
#Mann= 5 ,-1 , 0
  3858.7     .11       0  4623.2     .15       0  4711.4     .11       0
 5120.05     .06       0  5131.8     .11       0
Bank Sta=5120.05,5131.8
XS Rating Curve= 0 ,0
Exp/Cntr=0.3,0.1

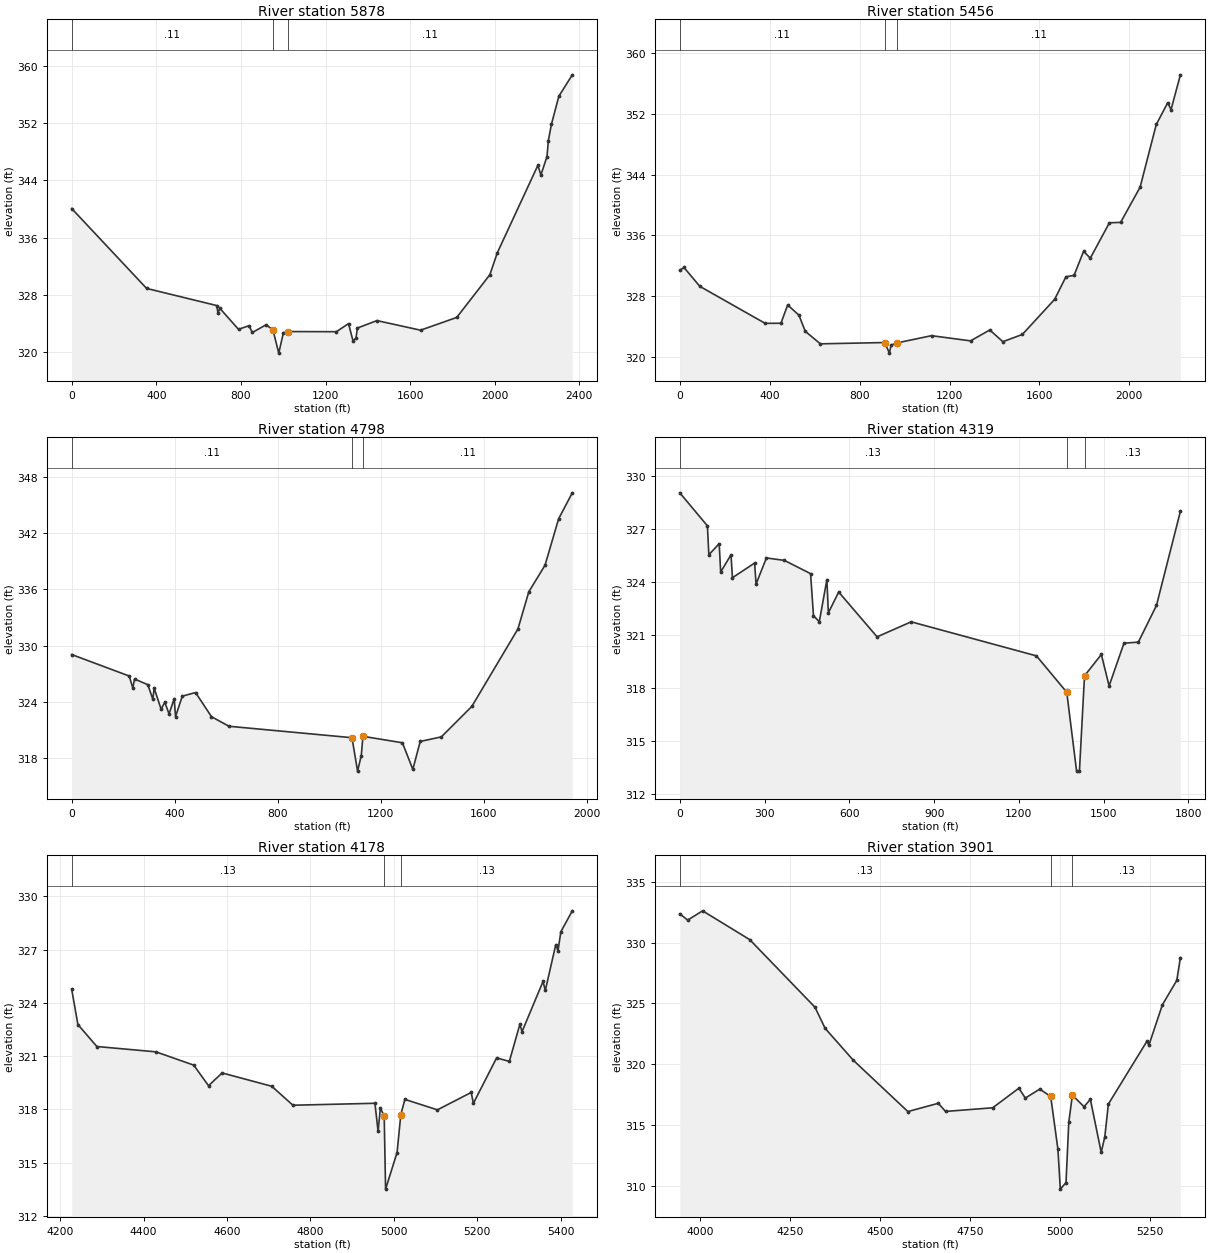
Type RM Length L Ch R = 1 ,5878    ,422,422,422
XS GIS Cut Line= 4
      3684334.45     10190025.22      3683829.24     10189108.55
      3683709.45     10189004.39      3682807.59     10188272.67
#Sta/Elev= 30
       0  340.08   354.2  328.93   685.6  326.54   691.3  325.57   701.2  326.13
   788.7  323.22   838.3  323.73   854.1  322.78   919.4  323.86   951.5  323.14
     979   319.9  1000.8  322.73  1022.6  322.91  1251.4  322.89  1308.9  324.02
  1329.8  321.64  1344.1  321.97  1350.6   323.4  1443.3  324.44  1649.4   323.1
  1820.4  324.88  1977.1  330.84  2012.3   333.9  2204.1  346.11  2218.4  344.77
  2247.2  347.33  2253.6  349.54    2268  351.81  2303.2  355.75  2366.8  358.74
#Mann= 3 , 0 , 0
       0     .11       0   951.5     .06       0  1022.6     .11       0
Bank Sta=951.5,1022.6
XS Rating Curve= 0 ,0
Exp/Cntr=0.3,0.1

Type RM Length L Ch R = 1 ,5456    ,658,658,658
XS GIS Cut Line= 4
      3684203.42     10189699.75      3684247.35     10189075.86
      3684018.23     10188856.26      3682956.89     10188133.78
#Sta/Elev= 30
       0  331.43    18.7   331.8    88.9  329.33   379.6  324.47   449.8  324.48
   479.9  326.88     530  325.54   558.2  323.42   625.3  321.78   911.4  321.95
   932.5  320.56   939.6  321.61   967.5  321.91  1119.8  322.85  1293.3  322.17
  1378.8   323.6    1437  322.06  1523.7  323.01  1667.4  327.62  1717.5  330.58
  1753.8  330.77  1796.1  333.92    1826  333.03    1911  337.67  1960.8  337.72
  2047.5  342.34  2119.4  350.57  2170.2  353.42  2185.2  352.53  2226.7  357.09
#Mann= 3 , 0 , 0
       0     .11       0   911.4     .06       0   967.5     .11       0
Bank Sta=911.4,967.5
XS Rating Curve= 0 ,0
Exp/Cntr=0.3,0.1

Type RM Length L Ch R = 1 ,4798    ,479,479,479
XS GIS Cut Line= 6
      3684252.03     10189550.45      3684258.98      10189456.7
      3684490.25     10188519.02      3684397.81     10188417.46
      3684272.86      10188144.2      3684133.98     10187720.59
#Sta/Elev= 30
       0  329.06   223.4  326.77   237.2  325.49     244  326.45   295.5  325.85
     315   324.3   320.1  325.48     347  323.25   361.6  323.98   377.9  322.73
   397.9  324.36   403.1  322.45   429.4  324.63   480.9  325.01   542.7  322.44
   610.5  321.42  1088.2   320.2  1109.8  316.64    1124  318.27  1130.8  320.35
  1283.9  319.66  1324.4  316.83    1353   319.8  1435.1  320.29  1553.5  323.54
  1732.4  331.79  1774.5  335.74  1837.6  338.58  1890.3  343.52  1943.4  346.29
#Mann= 3 , 0 , 0
       0     .11       0  1088.2     .06       0  1130.8     .11       0
Bank Sta=1088.2,1130.8
XS Rating Curve= 0 ,0
Exp/Cntr=0.3,0.1

Type RM Length L Ch R = 1 ,4319    ,141,141,141
BEGIN DESCRIPTION:
Mapping XS 6939b281
END DESCRIPTION:
XS GIS Cut Line= 5
      3684259.76     10189560.79       3684395.7     10189000.97
      3684657.37     10188457.51      3684756.32     10188223.14
      3684855.28     10187900.22
#Sta/Elev= 30
       0  329.04    97.7  327.17   102.8  325.53   139.4  326.16   144.6  324.55
   181.2  325.53   186.3  324.23   264.7  325.06   269.9  323.87   306.5  325.35
   370.2  325.21   462.8  324.46   473.1  322.07   493.7  321.74   520.5  324.12
   525.7  322.24   562.3  323.42   698.1  320.88   818.8  321.73  1262.2   319.8
  1369.3  317.74  1403.9   313.3  1414.2  313.27  1432.1  318.67  1491.7  319.88
  1519.2   318.1  1571.8  320.52  1622.7  320.58  1686.8  322.66  1771.4  327.99
#Mann= 3 ,-1 , 0
       0     .13       0  1369.3     .09       0  1432.1     .13       0
Bank Sta=1369.3,1432.1
XS Rating Curve= 0 ,0
Exp/Cntr=0.3,0.1

Type RM Length L Ch R = 1 ,4178    ,277,277,277
BEGIN DESCRIPTION:
Mapping XS fb1a174d
END DESCRIPTION:
XS GIS Cut Line= 4
      3684545.21     10188967.01      3684871.68     10188284.04
      3684868.21      10188238.9      3685005.18     10187865.38
#Sta/Elev= 30
  4227.6  324.76  4242.5  322.78  4287.9  321.54  4429.5  321.24  4520.2  320.49
  4555.6  319.33  4588.2  320.05  4707.1   319.3    4758  318.23  4954.6  318.34
  4962.1  316.76  4967.7  318.08  4976.8   317.6  4980.1   313.5  5007.6  315.56
 5016.57317.6858  5026.3  318.56  5104.4  317.97  5185.3  318.95  5190.6  318.34
  5246.3   320.9  5276.8   320.7    5302  322.79  5307.3  322.38  5357.6  325.21
    5363   324.7  5388.1  327.28  5393.4  326.93  5400.3  328.01  5427.7  329.19
#Mann= 3 , 0 , 0
  4227.6     .13       0  4976.8     .09       0 5016.57     .13       0
Bank Sta=4976.8,5016.57
XS Rating Curve= 0 ,0
Exp/Cntr=0.3,0.1

Type RM Length L Ch R = 1 ,3901    ,378,378,378
BEGIN DESCRIPTION:
CCLC 075 5.0
END DESCRIPTION:
XS GIS Cut Line= 3
      3684959.44     10189244.01      3685100.07     10188181.47
      3685117.85     10187861.07
#Sta/Elev= 30
  3943.2  332.36  3965.2  331.85  4006.7  332.61  4137.8  330.24  4319.4  324.68
  4347.4  322.95  4425.9  320.32  4577.8   316.1  4662.4  316.78  4682.5  316.11
  4813.7  316.41  4886.5  318.02  4904.5  317.21  4944.8  317.95  4975.1  317.34
  4995.2     313  5001.9  309.72  5017.7  310.26  5025.4  315.21  5035.4  317.45
  5067.8   316.5  5085.5   317.1  5115.6  312.74  5125.6  314.02  5135.6  316.72
  5243.2   321.9  5248.2  321.55  5285.8  324.88  5325.9  326.89  5335.9  328.76
#Mann= 3 , 0 , 0
  3943.2     .13       0  4975.1     .09       0  5035.4     .13       0
Bank Sta=4975.1,5035.4
XS Rating Curve= 0 ,0
Exp/Cntr=0.3,0.1

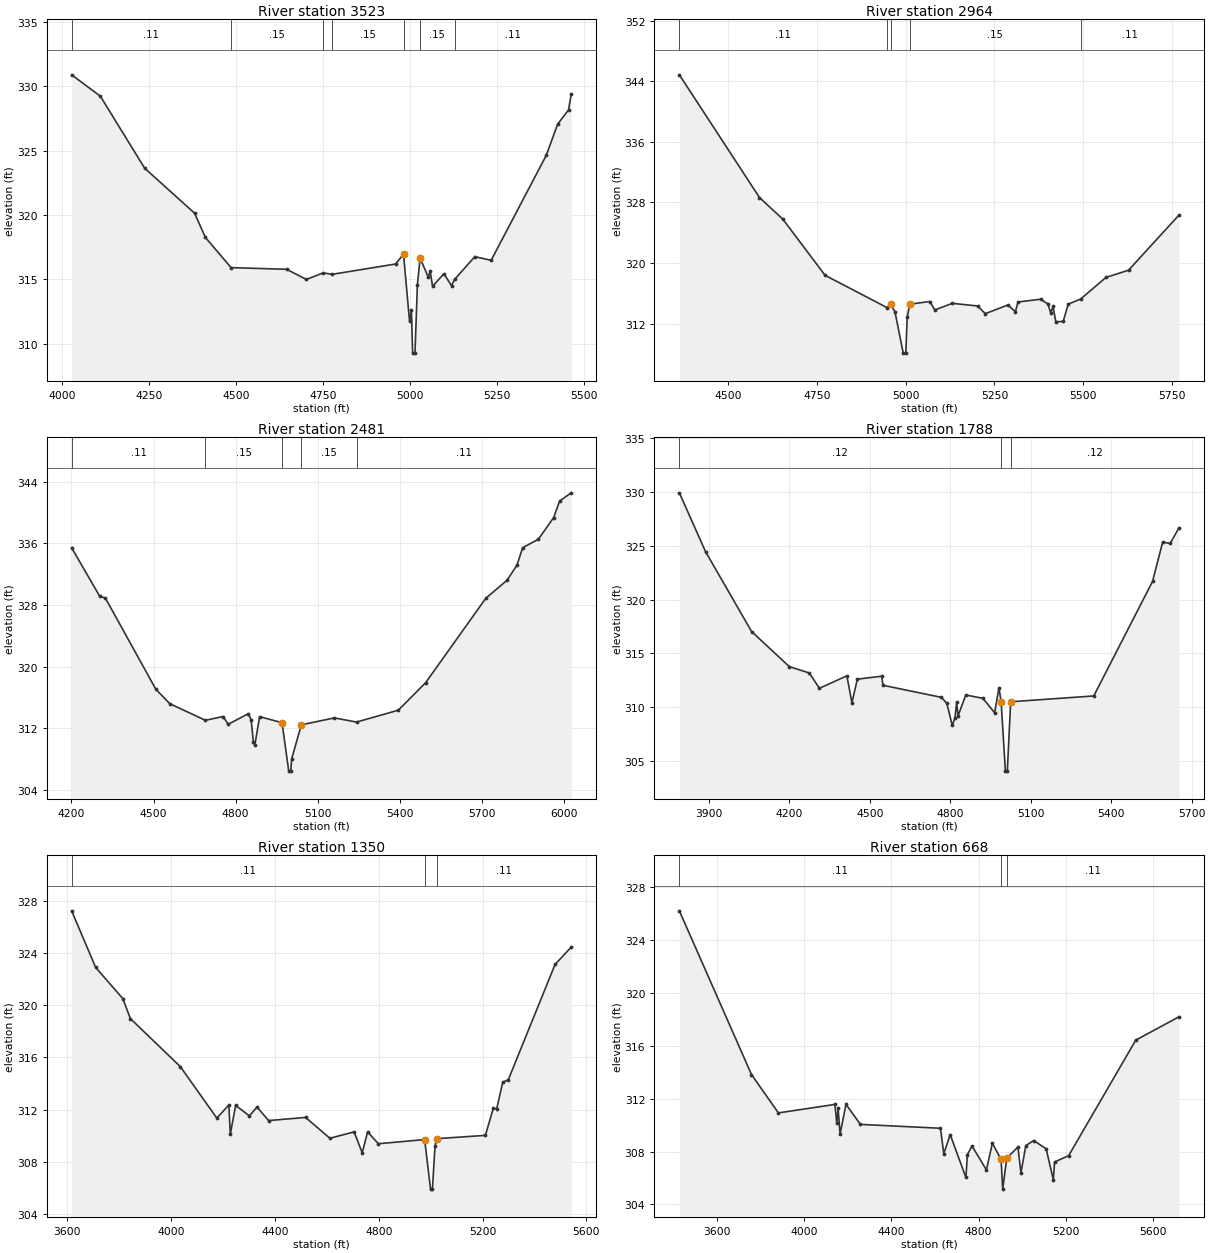
Type RM Length L Ch R = 1 ,3523    ,559,559,559
BEGIN DESCRIPTION:
CCLC 075 4.0
END DESCRIPTION:
XS GIS Cut Line= 3
      3685017.87     10189061.03      3685433.41     10188176.26
      3685251.46     10187755.18
#Sta/Elev= 30
  4026.5  330.87  4109.1  329.21  4236.4  323.63    4380  320.14  4411.1  318.26
  4484.9  315.92  4644.7  315.79  4701.4     315  4749.4  315.51  4775.4   315.4
  4957.8   316.2  4980.6  316.97  4997.9  311.77  5003.3  312.63  5006.8  309.29
  5013.6  309.29  5020.5  314.59  5028.3  316.66  5051.8  315.18  5057.2  315.66
  5064.1  314.47  5096.8  315.45  5118.6  314.52  5127.2     315  5185.6  316.77
  5232.6  316.49  5390.9  324.62  5423.6  327.04    5455  328.15  5462.7  329.36
#Mann= 7 ,-1 , 0
  4026.5     .11       0  4484.9     .15       0  4749.4     .11       0
  4775.4     .15       0  4980.6     .09       0  5028.3     .15       0
  5127.2     .11       0
Bank Sta=4980.6,5028.3
XS Rating Curve= 0 ,0
Exp/Cntr=0.3,0.1

Type RM Length L Ch R = 1 ,2964    ,483,483,483
BEGIN DESCRIPTION:
CCLC 075 3.0
END DESCRIPTION:
XS GIS Cut Line= 3
      3685967.85     10188961.08      3685825.44     10188339.79
      3685317.84     10187761.05
#Sta/Elev= 30
  4362.6  344.84  4588.3  328.65  4654.3  325.78    4773  318.39  4947.4  314.13
  4957.6  314.54  4969.9  313.58  4993.2  308.12  5000.4  308.12  5004.4  312.84
  5011.6  314.58    5068  314.93  5082.3  313.82  5131.6  314.69  5202.8  314.34
  5224.4  313.33  5288.2  314.47  5309.1  313.58  5316.6  314.87  5380.2  315.23
  5401.1   314.6  5408.7   313.4  5415.3  314.29  5422.9  312.26  5443.8   312.3
    5458  314.58  5492.7  315.25  5564.3  318.11  5627.9  319.06  5769.8  326.33
#Mann= 5 ,-1 , 0
  4362.6     .11       0  4947.4     .15       0  4957.6     .09       0
  5011.6     .15       0  5492.7     .11       0
Bank Sta=4957.6,5011.6
XS Rating Curve= 0 ,0
Exp/Cntr=0.3,0.1

Type RM Length L Ch R = 1 ,2481    ,693,693,693
BEGIN DESCRIPTION:
CCLC 075 2.0
END DESCRIPTION:
XS GIS Cut Line= 3
      3686267.86      10188811.1      3686094.05     10188031.24
      3685317.84     10187361.06
#Sta/Elev= 30
    4201  335.41  4303.5  329.13    4324  328.91  4508.4  317.08  4559.6   315.2
  4689.5  313.05  4754.3  313.54  4772.7  312.53  4846.5  313.91  4856.7  313.09
  4864.7  310.26  4869.9   309.8  4887.5  313.52  4969.4  312.74  4993.9  306.46
  5001.1  306.46  5004.7  308.07  5039.9  312.46  5160.5  313.36  5241.6  312.82
  5394.2  314.36    5494  317.93  5713.4  328.86  5791.3  331.21  5827.3  333.16
  5848.3  335.43  5905.3  336.51  5961.3  339.32  5983.2  341.48  6025.5  342.54
#Mann= 5 ,-1 , 0
    4201     .11       0  4689.5     .15       0  4969.4     .09       0
  5039.9     .15       0  5241.6     .11       0
Bank Sta=4969.4,5039.9
XS Rating Curve= 0 ,0
Exp/Cntr=0.3,0.1

Type RM Length L Ch R = 1 ,1788    ,438,438,438
BEGIN DESCRIPTION:
Mapping XS 636d2634
END DESCRIPTION:
XS GIS Cut Line= 3
      3686422.99     10188707.54      3686579.24      10187639.8
      3686204.26     10186952.34
#Sta/Elev= 30
  3790.5  329.91    3888  324.45  4059.8  317.03  4200.1  313.78    4275  313.18
  4312.5  311.76  4414.9  312.92  4433.8  310.42    4454  312.61  4544.6  312.88
  4549.6  312.04  4767.3  310.92  4787.5  310.36  4807.7  308.32  4817.8  308.99
  4824.2  310.48  4829.2  309.19  4858.2  311.14  4922.1  310.83  4965.7  309.49
  4981.9  311.82 4990.11310.4622  5005.8  304.07    5013  304.07  5025.5  310.51
  5335.2  311.05  5554.3  321.68  5592.2  325.34    5620  325.21  5652.7  326.65
#Mann= 3 , 0 , 0
  3790.5     .12       0 4990.11     .07       0  5025.5     .12       0
Bank Sta=4990.11,5025.5
XS Rating Curve= 0 ,0
Exp/Cntr=0.3,0.1

Type RM Length L Ch R = 1 ,1350    ,682,682,682
BEGIN DESCRIPTION:
Mapping XS 15314b97
END DESCRIPTION:
XS GIS Cut Line= 3
      3686511.54     10188650.19      3686881.32     10187311.68
      3686594.88     10186858.58
#Sta/Elev= 30
  3616.7  327.27  3709.2  322.92  3813.7  320.53  3842.9  318.99  4035.3   315.3
    4176  311.34  4222.6  312.35  4227.9   310.1  4248.6  312.31  4301.6  311.51
  4330.8  312.19  4375.5  311.15    4518  311.39  4611.7  309.79  4705.1  310.28
  4736.2  308.67    4757  310.28  4798.5  309.37  4976.8  309.69  4999.4  305.88
  5006.7  305.88  5016.6  309.16  5022.5  309.76  5210.7  310.01  5241.3  312.09
  5254.5  312.06  5277.7   314.1  5298.9  314.28  5479.3  323.15  5541.4  324.48
#Mann= 3 , 0 , 0
  3616.7     .11       0  4976.8     .07       0  5022.5     .11       0
Bank Sta=4976.8,5022.5
XS Rating Curve= 0 ,0
Exp/Cntr=0.3,0.1

Type RM Length L Ch R = 1 ,668     ,0,0,0
BEGIN DESCRIPTION:
CCLC 075 1.0
END DESCRIPTION:
XS GIS Cut Line= 3
      3686592.25     10188634.61      3687540.18     10187207.51
      3687082.31     10186858.91
#Sta/Elev= 30
  3429.5  326.19  3759.9  313.82  3883.2  310.92    4142  311.56  4150.8  310.12
  4156.8  311.27  4165.8  309.32  4192.9  311.57    4259  310.05  4625.8  309.76
  4640.9  307.84  4670.3  309.28  4742.3  306.04  4749.1  307.77  4770.2  308.42
  4836.3  306.61  4863.4  308.63 4903.41307.4102  4910.8  305.16  4929.5   307.5
  4980.6  308.34  4994.4  306.38  5016.7  308.45  5052.8  308.83  5109.9  308.21
  5142.7  305.87  5148.5  307.21    5213  307.69  5520.6  316.42  5718.2  318.18
#Mann= 3 , 0 , 0
  3429.5     .11       0 4903.41     .06       0  4929.5     .11       0
Bank Sta=4903.41,4929.5
XS Rating Curve= 0 ,0
Exp/Cntr=0.3,0.1

Chan Stop Cuts=-1
Use User Specified Reach Order=0
Composite Channel Slope=5