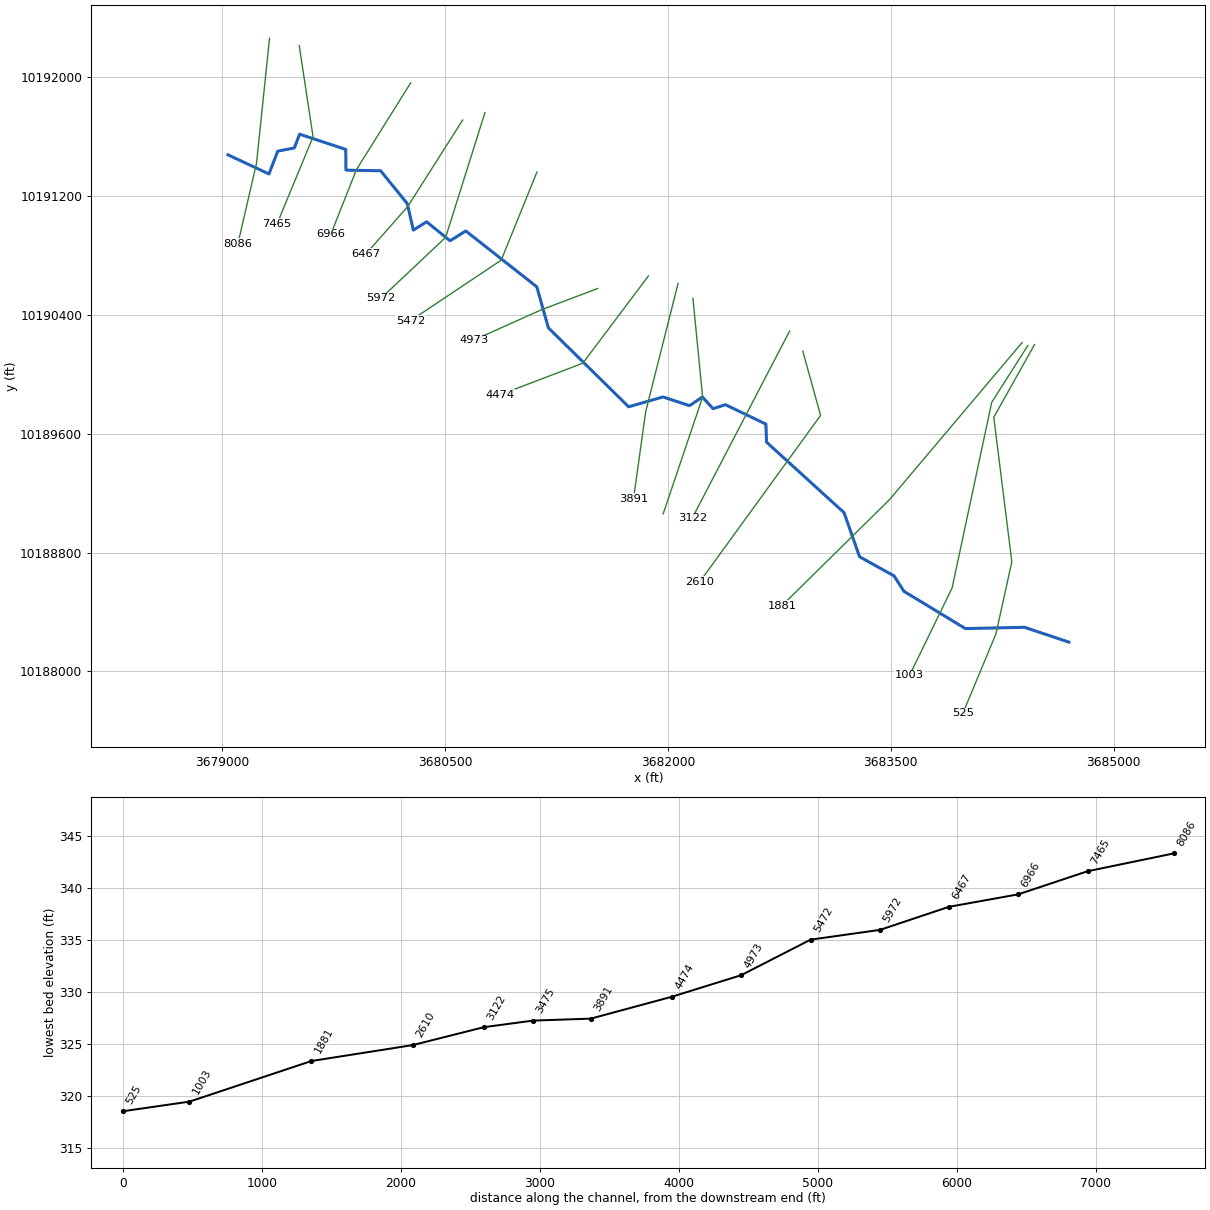
--- CCLC 076.prj (project) ---

Proj Title=CCLC 076 Base Level Engineering
Current Plan=p01
Default Exp/Contr=0.3,0.1
English Units
Geom File=g01
Flow File=f01
Flow File=f02
Plan File=p01
Y Axis Title=Elevation
X Axis Title(PF)=Main Channel Distance
X Axis Title(XS)=Station
BEGIN DESCRIPTION:
CCLC 076
END DESCRIPTION:
DSS Export Rating Curves= 0
DSS Export Rating Curve Sorted= 0
DSS Export Volume Flow Curves= 0
DXF OffsetX= 0
DXF OffsetY= 0
DXF ScaleX= 1
DXF ScaleY= 10

--- CCLC 076.p01 (plan) ---

Plan Title=Multiple Run
Short Identifier=Multiple
Geom File=g01
Flow File=f01
Subcritical Flow
K Sum by GR= 0
Std Step Tol= 0.01
Critical Tol= 0.01
Num of Std Step Trials= 20
Max Error Tol= 0.3
Flow Tol Ratio= 0.001
Split Flow NTrial= 30
Split Flow Tol= 0.02
Split Flow Ratio= 0.02
Log Output Level= 0
Friction Slope Method= 1
Unsteady Friction Slope Method= 2
Unsteady Bridges Friction Slope Method= 1
Parabolic Critical Depth
Global Vel Dist=  1 , 1 , 1
Global Log Level= 0
CheckData=True
Encroach Param= -1, 0, 0, 0
BEGIN DESCRIPTION:
Multiple Run
END DESCRIPTION:

--- CCLC 076.f01 (steady flow) ---

Flow Title=Multiple
Program Version=4.10
Number of Profiles= 7
Profile Names=10-year,25-year,50-year,1pct_min,100-year,1pct_plu,500-year
River Rch & RM=CCLC 076,Reach-1         ,8086
     714     977    1329     595    1797    5427    3394
River Rch & RM=CCLC 076,Reach-1         ,3891
     792    1090    1488     667    2015    6085    3827
River Rch & RM=CCLC 076,Reach-1         ,1881
    1435    2037    2838    1297    3917   11829    7730
Boundary for River Rch & Prof#=CCLC 076,Reach-1         , 1
Up Type= 0
Dn Type= 3
Dn Slope=0.005
Boundary for River Rch & Prof#=CCLC 076,Reach-1         , 2
Up Type= 0
Dn Type= 3
Dn Slope=0.005
Boundary for River Rch & Prof#=CCLC 076,Reach-1         , 3
Up Type= 0
Dn Type= 3
Dn Slope=0.005
Boundary for River Rch & Prof#=CCLC 076,Reach-1         , 4
Up Type= 0
Dn Type= 3
Dn Slope=0.005
Boundary for River Rch & Prof#=CCLC 076,Reach-1         , 5
Up Type= 0
Dn Type= 3
Dn Slope=0.005
Boundary for River Rch & Prof#=CCLC 076,Reach-1         , 6
Up Type= 0
Dn Type= 3
Dn Slope=0.005
Boundary for River Rch & Prof#=CCLC 076,Reach-1         , 7
Up Type= 0
Dn Type= 3
Dn Slope=0.005
DSS Import GetInterval= 0
DSS Import GetPeak= 0
DSS Import FillOption= 0

--- CCLC 076.f02 (steady flow) ---

Flow Title=Orig_BLE_Flows
Program Version=4.10
Number of Profiles= 7
Profile Names=10-year,25-year,50-year,1pct_min,100-year,1pct_plu,500-year
River Rch & RM=CCLC 076,Reach-1         ,8086
     714     958    1156     458    1382    4174    1973
River Rch & RM=CCLC 076,Reach-1         ,3891
     792    1069    1294     513    1550    4681    2225
River Rch & RM=CCLC 076,Reach-1         ,1881
    1435    1997    2468     998    3013    9100    4494
Boundary for River Rch & Prof#=CCLC 076,Reach-1         , 1
Up Type= 0
Dn Type= 3
Dn Slope=0.005
Boundary for River Rch & Prof#=CCLC 076,Reach-1         , 2
Up Type= 0
Dn Type= 3
Dn Slope=0.005
Boundary for River Rch & Prof#=CCLC 076,Reach-1         , 3
Up Type= 0
Dn Type= 3
Dn Slope=0.005
Boundary for River Rch & Prof#=CCLC 076,Reach-1         , 4
Up Type= 0
Dn Type= 3
Dn Slope=0.005
Boundary for River Rch & Prof#=CCLC 076,Reach-1         , 5
Up Type= 0
Dn Type= 3
Dn Slope=0.005
Boundary for River Rch & Prof#=CCLC 076,Reach-1         , 6
Up Type= 0
Dn Type= 3
Dn Slope=0.005
Boundary for River Rch & Prof#=CCLC 076,Reach-1         , 7
Up Type= 0
Dn Type= 3
Dn Slope=0.005
DSS Import GetInterval= 0
DSS Import GetPeak= 0
DSS Import FillOption= 0

--- CCLC 076.g01 (geometry) ---

Geom Title=Existing Conditions
Program Version=4.10

River Reach=CCLC 076        ,Reach-1
Reach XY= 30
      3679038.23     10191476.84      3679314.04     10191348.19
      3679373.09     10191501.74      3679484.54     10191523.16
      3679520.48     10191615.76      3679830.81     10191513.39
       3679832.3     10191373.78      3680065.77     10191369.61
      3680245.03      10191148.4      3680285.76     10190970.34
       3680375.5     10191025.84      3680533.27     10190898.18
      3680638.95     10190964.34      3681116.83     10190588.52
      3681194.87     10190312.28      3681735.02     10189780.88
      3681966.98     10189846.98      3682145.04     10189788.32
      3682231.15     10189846.69      3682303.38      10189768.3
      3682386.64     10189795.01      3682659.07     10189664.21
      3682663.36     10189542.77      3683185.16     10189068.18
       3683289.3     10188771.61      3683522.13     10188642.16
      3683587.42     10188539.47      3684001.68     10188287.88
      3684400.17     10188296.54      3684698.23     10188196.84

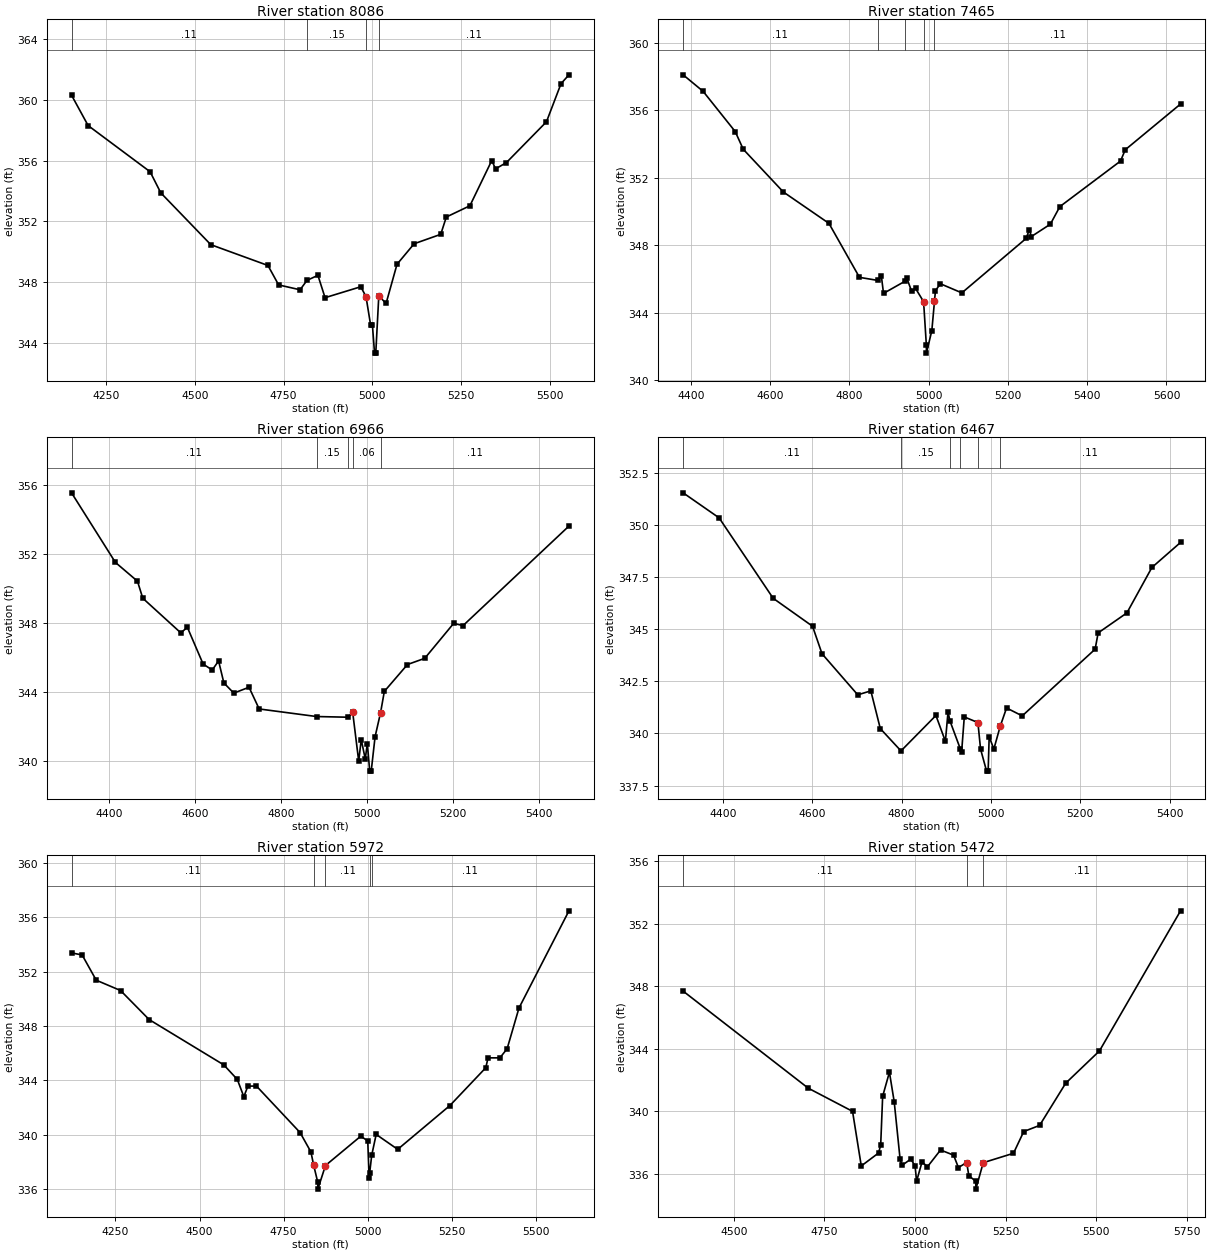
Type RM Length L Ch R = 1 ,8086    ,621,621,621
BEGIN DESCRIPTION:
CCLC 076 11.0
END DESCRIPTION:
XS GIS Cut Line= 3
      3679317.85     10192261.07      3679230.28     10191421.05
      3679105.27     10190879.35
#Sta/Elev= 30
    4153   360.3  4199.7   358.3  4374.2  355.26  4404.3  353.87  4545.1  350.46
    4706  349.09  4736.1  347.81  4796.5  347.49  4815.9  348.11  4846.7  348.44
  4866.8  346.97  4967.4  347.69 4982.16347.0332    4995  345.18  5000.1  345.18
  5006.1  343.32  5009.6  343.32  5018.1  347.09  5038.6  346.59  5069.4  349.17
  5117.6  350.52  5192.5  351.14  5208.2  352.28  5274.6  353.02  5336.2     356
  5346.8  355.45  5377.3  355.86  5490.2  358.55  5531.2  361.06  5553.5  361.64
#Mann= 4 ,-1 , 0
    4153     .11       0  4815.9     .15       0 4982.16     .07       0
  5018.1     .11       0
Bank Sta=4982.16,5018.1
XS Rating Curve= 0 ,0
Exp/Cntr=0.3,0.1

Type RM Length L Ch R = 1 ,7465    ,499,499,499
BEGIN DESCRIPTION:
CCLC 076 10.0
END DESCRIPTION:
XS GIS Cut Line= 3
      3679517.86     10192211.03      3679610.81     10191598.44
      3679367.87     10191011.11
#Sta/Elev= 30
  4380.4   358.1  4430.9  357.12  4511.8  354.74  4532.1  353.69  4633.2  351.16
  4748.3   349.3  4825.4   346.1  4871.2  345.92  4880.7  346.16  4886.1  345.15
  4939.5  345.86  4944.3  346.09  4956.9  345.28    4967  345.44  4987.2  344.66
  4994.1  342.11  4994.4  341.61    5008  342.95 5014.71344.6902  5017.1  345.31
  5029.6  345.72  5083.7  345.18  5246.1  348.41  5253.9  348.93  5259.3  348.52
  5307.1  349.25    5331  350.29  5484.1  352.99  5496.1  353.66  5635.6  356.37
#Mann= 5 ,-1 , 0
  4380.4     .11       0  4871.2     .15       0  4939.5     .11       0
  4987.2     .06       0 5014.71     .11       0
Bank Sta=4987.2,5014.71
XS Rating Curve= 0 ,0
Exp/Cntr=0.3,0.1

Type RM Length L Ch R = 1 ,6966    ,499,499,499
BEGIN DESCRIPTION:
CCLC 076 9.0
END DESCRIPTION:
XS GIS Cut Line= 3
      3680267.85     10191961.07      3679903.01     10191377.77
      3679730.27     10190941.85
#Sta/Elev= 30
    4312  355.55    4414  351.51  4465.3  350.42  4477.7  349.43  4566.1  347.42
  4581.4  347.74    4618  345.61  4639.2  345.26    4654  345.79  4666.3  344.51
  4689.4  343.92  4724.8  344.26  4748.4     343  4881.8  342.56  4955.2  342.52
 4965.94342.7971  4979.9  339.97  4985.8  341.22  4995.1   340.1    5000  340.99
  5005.5  339.39    5009  339.39    5018  341.39  5030.8  342.79  5039.5  344.02
  5093.3  345.58  5133.5  345.94  5200.8  347.97  5222.6  347.84  5468.9  353.62
#Mann= 5 ,-1 , 0
    4312     .11       0  4881.8     .15       0  4955.2     .11       0
 4965.94     .06       0  5030.8     .11       0
Bank Sta=4965.94,5030.8
XS Rating Curve= 0 ,0
Exp/Cntr=0.3,0.1

Type RM Length L Ch R = 1 ,6467    ,495,495,495
BEGIN DESCRIPTION:
CCLC 076 8.0
END DESCRIPTION:
XS GIS Cut Line= 3
      3680617.87      10191711.1      3680248.52     10191129.34
      3679967.82     10190811.03
#Sta/Elev= 30
  4310.9  351.54  4391.4  350.34  4512.5  346.48  4600.6  345.14  4621.8  343.82
  4701.8  341.85  4731.1  342.04  4752.3  340.23  4798.6  339.16  4876.8  340.86
    4898  339.62  4903.9  341.03  4908.2   340.6  4931.2  339.27  4934.4  339.13
  4940.3  340.79  4970.8  340.52  4976.7  339.25  4990.2  338.19  4993.7  338.19
    4996  339.84  5006.5  339.25  5020.7  340.34  5034.9  341.22    5070  340.84
  5233.2  344.04  5239.9  344.82  5304.3  345.78  5360.3  347.96  5424.4  349.16
#Mann= 6 ,-1 , 0
  4310.9     .11       0  4798.6     .15       0  4908.2     .11       0
  4931.2     .15       0  4970.8     .09       0  5020.7     .11       0
Bank Sta=4970.8,5020.7
XS Rating Curve= 0 ,0
Exp/Cntr=0.3,0.1

Type RM Length L Ch R = 1 ,5972    ,500,500,500
BEGIN DESCRIPTION:
CCLC 076 7.0
END DESCRIPTION:
XS GIS Cut Line= 3
      3680767.87     10191761.12      3680503.24     10190921.22
      3680067.89      10190511.1
#Sta/Elev= 30
  4119.4  353.38  4150.9  353.23  4192.8  351.37  4265.1  350.61  4350.1  348.47
  4572.1  345.13  4612.2  344.06  4631.6  342.79  4643.7  343.57  4669.2  343.57
  4798.7  340.15    4831  338.72 4839.38337.7227  4851.4  336.48  4851.6  335.98
  4874.3  337.72  4979.2  339.88    5000  339.53    5004   336.8  5005.7  337.18
  5011.8  338.48    5025  340.01    5089  338.91  5244.3  342.14  5350.8  344.92
  5357.6  345.65  5392.8  345.65  5414.3  346.32  5449.5  349.32  5598.1  356.48
#Mann= 5 ,-1 , 0
  4119.4     .11       0 4839.38     .06       0  4874.3     .11       0
  5005.7     .15       0  5011.8     .11       0
Bank Sta=4839.38,4874.3
XS Rating Curve= 0 ,0
Exp/Cntr=0.3,0.1

Type RM Length L Ch R = 1 ,5472    ,499,499,499
BEGIN DESCRIPTION:
CCLC 076 6.0
END DESCRIPTION:
XS GIS Cut Line= 3
      3681117.84     10191361.04      3680877.41     10190767.81
      3680267.86     10190361.07
#Sta/Elev= 30
  4359.9  347.69  4705.2  341.49  4827.5  340.01  4851.6  336.52  4899.4  337.35
  4905.2  337.87  4910.6  340.97  4929.3  342.51  4942.5  340.62  4958.8  336.94
  4964.2  336.56  4988.3  336.96    5000  336.53  5004.3  335.55  5019.3  336.78
  5034.3  336.47  5070.4  337.54  5106.4  337.21  5119.7  336.42  5142.5  336.74
  5148.5   335.9  5167.5  335.54  5167.8  335.04 5188.19336.7295  5271.7  337.33
    5300  338.72  5343.8  339.11  5415.9  341.81    5509  343.87  5732.8  352.82
#Mann= 3 , 0 , 0
  4359.9     .11       0  5142.5     .06       0 5188.19     .11       0
Bank Sta=5142.5,5188.19
XS Rating Curve= 0 ,0
Exp/Cntr=0.3,0.1

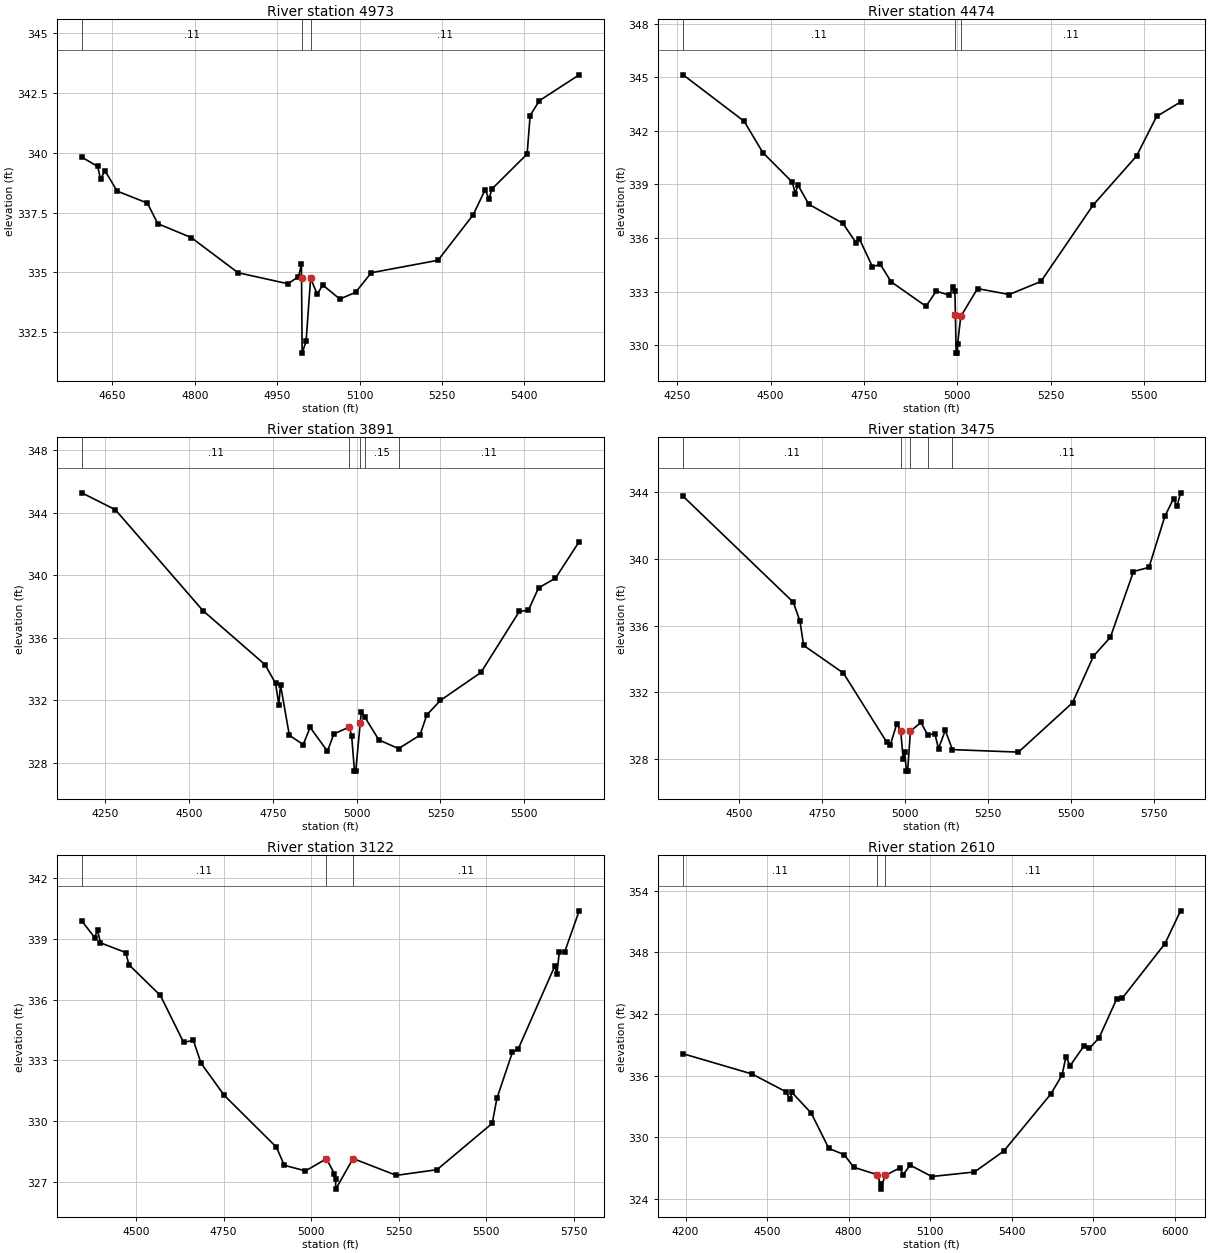
Type RM Length L Ch R = 1 ,4973    ,499,499,499
BEGIN DESCRIPTION:
CCLC 076 5.0
END DESCRIPTION:
XS GIS Cut Line= 3
      3681527.17     10190577.31      3681147.78     10190433.87
      3680691.74     10190229.35
#Sta/Elev= 30
  4594.4  339.82  4623.3  339.43  4628.6  338.89  4636.4  339.26  4658.8   338.4
  4713.8   337.9  4732.7  337.04  4793.6  336.46  4878.8  334.99  4969.4  334.53
  4988.8  334.82  4994.2  335.34  4994.4 334.757  4995.5  331.63  5002.7  332.13
  5010.9  334.75  5023.2  334.09  5032.8  334.48  5064.1  333.89  5092.7  334.17
  5121.4  334.99  5242.8  335.51  5306.8  337.41  5328.7  338.46  5335.5  338.07
    5341  338.49    5405  339.95  5410.5  341.56  5427.3  342.18  5499.8  343.26
#Mann= 3 , 0 , 0
  4594.4     .11       0  4994.4     .06       0  5010.9     .11       0
Bank Sta=4994.4,5010.9
XS Rating Curve= 0 ,0
Exp/Cntr=0.3,0.1

Type RM Length L Ch R = 1 ,4474    ,583,583,583
BEGIN DESCRIPTION:
CCLC 076 4.0
END DESCRIPTION:
XS GIS Cut Line= 3
      3681867.86     10190661.09      3681426.63     10190074.26
      3680867.82     10189861.06
#Sta/Elev= 30
  4265.8  345.13  4429.3  342.53  4479.3  340.78  4558.4  339.12  4566.1  338.48
    4573  338.98  4602.2  337.89  4693.8  336.82  4729.2  335.73  4737.5  335.97
  4772.9  334.39  4793.8  334.53  4822.9  333.55  4916.4  332.18  4943.7  333.03
  4979.1   332.8  4987.4  333.25  4993.7  333.05 4995.18 331.667  4997.1  329.56
  5000.6  329.56  5000.9  330.06  5009.4  331.61  5054.3  333.17  5139.2  332.84
  5224.1  333.57  5363.8  337.84  5480.3  340.59  5533.9   342.8  5598.1  343.61
#Mann= 3 , 0 , 0
  4265.8     .11       0 4995.18     .06       0  5009.4     .11       0
Bank Sta=4995.18,5009.4
XS Rating Curve= 0 ,0
Exp/Cntr=0.3,0.1

Type RM Length L Ch R = 1 ,3891    ,416,416,416
BEGIN DESCRIPTION:
CCLC 076 3.0
END DESCRIPTION:
XS GIS Cut Line= 3
      3682067.84     10190611.02      3681850.07     10189749.18
      3681767.85     10189161.03
#Sta/Elev= 30
  4180.8  345.26  4280.8  344.18  4541.8  337.73    4727  334.27  4758.4  333.08
  4768.1  331.72  4773.2  332.97  4799.6  329.75  4840.9  329.16  4861.5  330.26
  4913.1  328.73  4932.2  329.84  4978.4  330.28  4985.3  329.71  4993.7  327.46
  4997.4  327.46 5010.86330.5352  5014.3  331.26  5024.1  330.93  5066.2  329.46
    5125   328.9    5189  329.76  5209.2  331.05  5249.6  331.98  5370.7  333.77
  5484.9  337.67  5512.1  337.75  5542.4  339.18  5592.9   339.8  5663.6  342.14
#Mann= 5 ,-1 , 0
  4180.8     .11       0  4978.4     .06       0 5010.86     .11       0
  5024.1     .15       0    5125     .11       0
Bank Sta=4978.4,5010.86
XS Rating Curve= 0 ,0
Exp/Cntr=0.3,0.1

Type RM Length L Ch R = 1 ,3475    ,353,353,353
BEGIN DESCRIPTION:
CCLC 076 2.0
END DESCRIPTION:
XS GIS Cut Line= 3
      3682167.85     10190511.07      3682233.05     10189846.36
      3681967.84     10189061.03
#Sta/Elev= 30
  4332.1  343.75  4663.7   337.4  4683.8  336.25  4694.7  334.81  4814.4  333.15
    4945     329  4955.1  328.81  4975.2  330.12 4986.88 329.675  4994.1  328.02
    4999   328.4  5003.9  327.27  5007.6  327.27  5016.1  329.67  5047.8  330.19
  5067.9  329.44  5089.6  329.51  5100.6  328.62    5121  329.72  5142.4  328.56
  5341.2  328.41  5503.8  331.37  5566.7  334.16  5617.8   335.3  5687.3  339.24
  5733.9  339.49  5781.7  342.55  5807.7  343.61  5818.4  343.15  5828.9  343.96
#Mann= 5 ,-1 , 0
  4332.1     .11       0 4986.88     .06       0  5016.1     .11       0
  5067.9     .15       0  5142.4     .11       0
Bank Sta=4986.88,5016.1
XS Rating Curve= 0 ,0
Exp/Cntr=0.3,0.1

Type RM Length L Ch R = 1 ,3122    ,512,512,512
BEGIN DESCRIPTION:
Mapping XS 32f7d7ab
END DESCRIPTION:
XS GIS Cut Line= 2
      3682818.83     10190290.85      3682162.73     10189030.73
#Sta/Elev= 30
  4345.2  339.89  4382.1  339.07  4390.1  339.44  4398.6  338.81  4470.5  338.33
  4480.2  337.72  4569.7  336.21    4636  333.89  4663.8  333.99  4685.9  332.86
  4752.2  331.27  4901.3  328.71  4923.4  327.82    4984  327.54    5044  328.14
  5066.5  327.41  5070.3  327.14  5070.5  326.64 5120.02328.1503  5243.6  327.32
  5359.7   327.6  5517.5  329.89  5530.9  331.13  5575.1   333.4  5591.6  333.56
  5696.4  337.67  5702.1  337.25  5709.1  338.36  5724.2  338.35  5765.9  340.39
#Mann= 3 , 0 , 0
  4345.2     .11       0    5044     .06       0 5120.02     .11       0
Bank Sta=5044,5120.02
XS Rating Curve= 0 ,0
Exp/Cntr=0.3,0.1

Type RM Length L Ch R = 1 ,2610    ,729,729,729
BEGIN DESCRIPTION:
Mapping XS f0f8c300
END DESCRIPTION:
XS GIS Cut Line= 3
      3682907.38     10190155.38      3683027.16     10189723.14
      3682215.62     10188604.67
#Sta/Elev= 30
  4190.9  338.12  4444.4  336.15  4568.9  334.42  4585.2  333.67  4590.4  334.37
  4662.2  332.34  4727.1  328.89  4783.5  328.28  4819.1  327.05  4904.9  326.33
  4917.4  325.42  4917.7  324.92  4934.3  326.26  4990.7  327.02  4999.2  326.28
  5026.3  327.26  5105.9  326.15  5262.8  326.59  5370.9  328.63  5543.5  334.18
  5585.2  336.04  5599.9  337.85  5614.6  336.94  5664.9  338.85  5685.7  338.65
  5721.3  339.66  5786.2  343.46  5807.1  343.55    5964  348.86  6021.3  352.06
#Mann= 3 , 0 , 0
  4190.9     .11       0  4904.9     .06       0  4934.3     .11       0
Bank Sta=4904.9,4934.3
XS Rating Curve= 0 ,0
Exp/Cntr=0.3,0.1

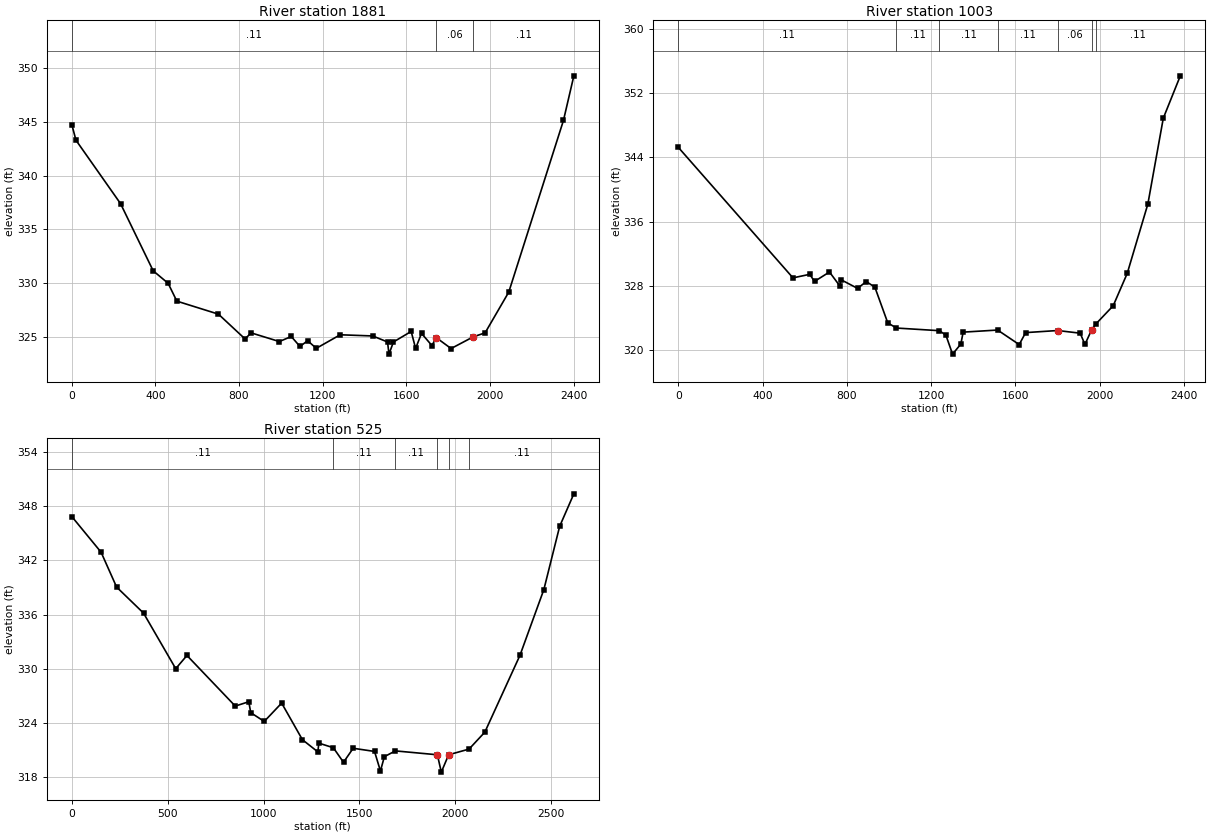
Type RM Length L Ch R = 1 ,1881    ,878,878,878
XS GIS Cut Line= 3
      3684383.98     10190213.64       3683490.7     10189155.43
      3682766.74     10188441.89
#Sta/Elev= 30
       0  344.75    20.1  343.29   233.3  337.39   389.4  331.14   460.8  329.98
   502.5  328.32   701.4  327.11   828.9   324.8   857.5  325.37   992.7  324.56
  1049.8  325.03  1091.5   324.1  1127.9  324.64  1169.5  323.93  1283.9  325.19
  1439.4  325.08  1510.2  324.52  1517.2  323.39  1538.4  324.52  1623.3   325.5
  1644.5  323.92  1672.7  325.32  1722.3  324.19  1743.5  324.92  1814.2  323.91
  1920.3     325  1976.9  325.37    2090  329.16  2351.6  345.13  2401.3  349.28
#Mann= 3 , 0 , 0
       0     .11       0  1743.5     .06       0  1920.3     .11       0
Bank Sta=1743.5,1920.3
XS Rating Curve= 0 ,0
Exp/Cntr=0.3,0.1

Type RM Length L Ch R = 1 ,1003    ,478,478,478
XS GIS Cut Line= 4
      3684422.17     10190192.81      3684179.11     10189810.87
      3683912.57     10188561.68      3683626.12     10187973.14
#Sta/Elev= 30
       0  345.26   544.5  328.99   623.9  329.43   646.8  328.55   717.8  329.72
   767.3  327.97   772.4  328.76   851.3  327.68   892.2  328.53   933.1  327.84
   994.4  323.39  1035.3  322.74  1239.8  322.41  1270.5  321.84  1301.9  319.49
  1341.2  320.74  1352.3  322.23  1515.9  322.49  1618.2  320.68  1648.8  322.17
  1800.5  322.43  1907.6   322.1  1930.2   320.7  1961.5 322.481  1980.8  323.21
  2064.4  325.52  2131.1  329.56  2228.9  338.19  2302.1  348.88  2382.9  354.16
#Mann= 7 ,-1 , 0
       0     .11       0  1035.3     .11       0  1239.8     .11       0
  1515.9     .11       0  1800.5     .06       0  1961.5     .11       0
  1980.8     .11       0
Bank Sta=1800.5,1961.5
XS Rating Curve= 0 ,0
Exp/Cntr=0.3,0.1

Type RM Length L Ch R = 1 ,525     ,0,0,0
XS GIS Cut Line= 5
      3684467.31     10190199.75        3684193.     10189710.17
      3684314.53     10188737.95      3684207.71     10188252.65
      3683984.67     10187717.12
#Sta/Elev= 30
       0  346.86   152.8  342.91   233.8  339.05   374.2  336.17     542  330.02
   600.6  331.48   852.5  325.88   923.1  326.36   933.2  325.15  1003.7  324.18
  1094.4  326.21  1202.6  322.16  1283.2  320.81  1288.2  321.78  1363.8  321.27
  1416.9  319.66  1467.3  321.21  1578.7  320.86  1609.5  318.69  1629.9  320.28
  1687.3  320.92  1906.4  320.49  1926.9  318.57  1965.1  320.49  2071.6  321.12
    2154     323  2337.1   331.5  2461.7  338.78    2544  345.77    2618  349.37
#Mann= 6 ,-1 , 0
       0     .11       0  1363.8     .11       0  1687.3     .11       0
  1906.4     .06       0  1965.1     .11       0  2071.6     .11       0
Bank Sta=1906.4,1965.1
XS Rating Curve= 0 ,0
Exp/Cntr=0.3,0.1

Chan Stop Cuts=-1
Use User Specified Reach Order=0
Composite Channel Slope=5