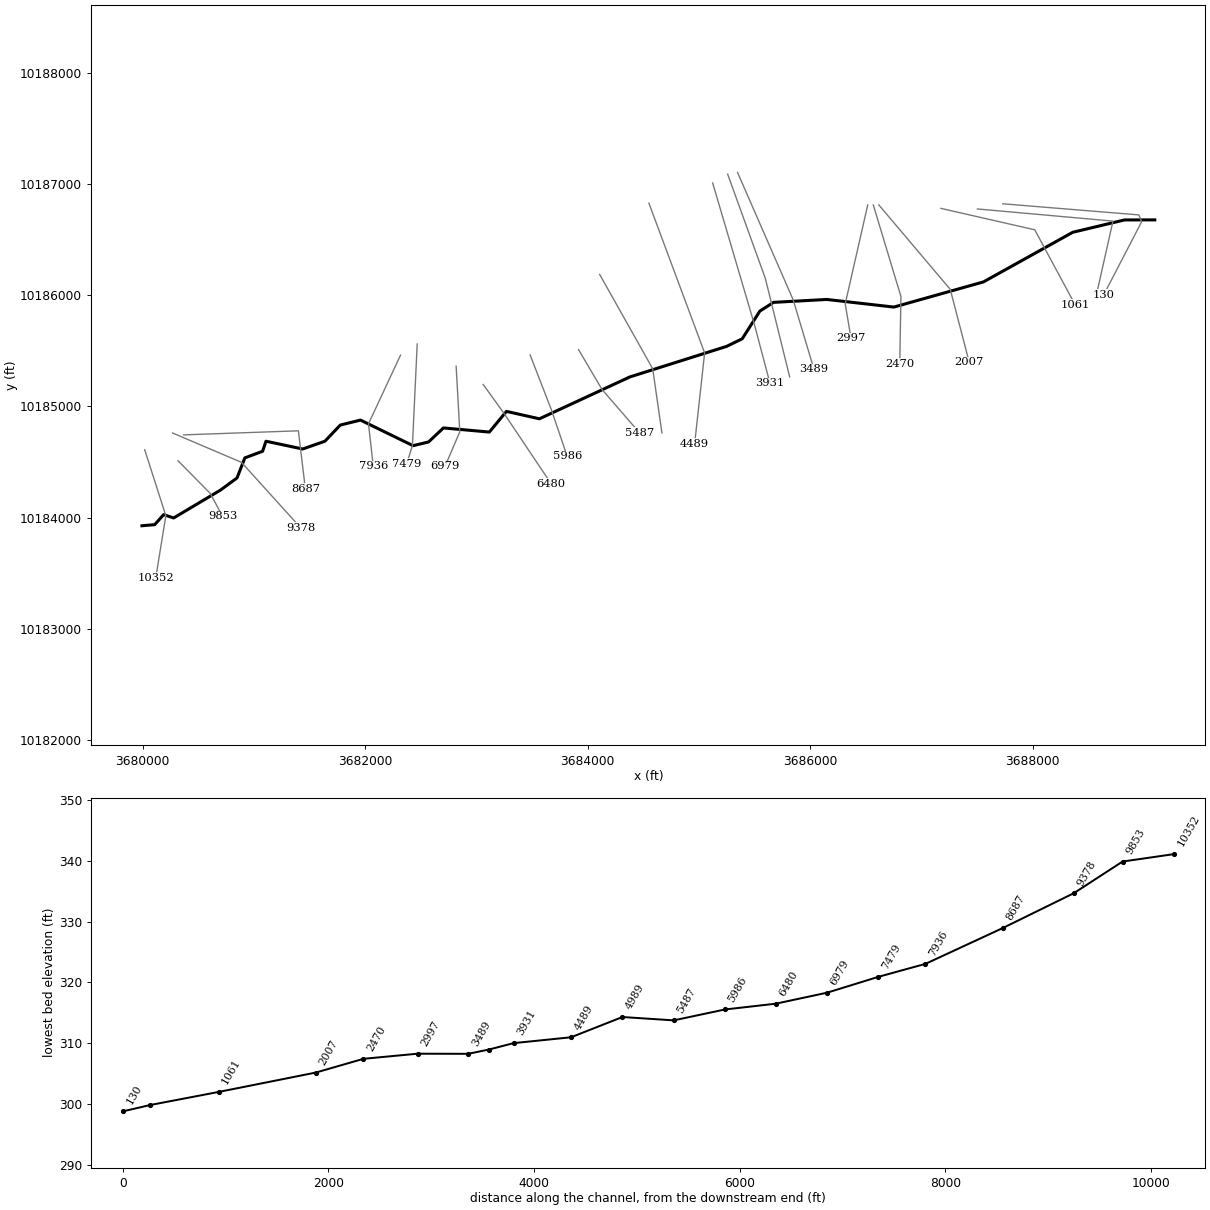
--- CCLC 078.prj (project) ---

Proj Title=CCLC 078 Base Level Engineering
Current Plan=p01
Default Exp/Contr=0.3,0.1
English Units
Geom File=g01
Flow File=f01
Flow File=f02
Plan File=p01
Y Axis Title=Elevation
X Axis Title(PF)=Main Channel Distance
X Axis Title(XS)=Station
BEGIN DESCRIPTION:
CCLC 078
END DESCRIPTION:
DSS Export Rating Curves= 0
DSS Export Rating Curve Sorted= 0
DSS Export Volume Flow Curves= 0
DXF OffsetX= 0
DXF OffsetY= 0
DXF ScaleX= 1
DXF ScaleY= 10

--- CCLC 078.p01 (plan) ---

Plan Title=Multiple Run
Short Identifier=Multiple
Geom File=g01
Flow File=f01
Subcritical Flow
K Sum by GR= 0
Std Step Tol= 0.01
Critical Tol= 0.01
Num of Std Step Trials= 20
Max Error Tol= 0.3
Flow Tol Ratio= 0.001
Split Flow NTrial= 30
Split Flow Tol= 0.02
Split Flow Ratio= 0.02
Log Output Level= 0
Friction Slope Method= 1
Unsteady Friction Slope Method= 2
Unsteady Bridges Friction Slope Method= 1
Parabolic Critical Depth
Global Vel Dist=  1 , 1 , 1
Global Log Level= 0
CheckData=True
Encroach Param= -1, 0, 0, 0
BEGIN DESCRIPTION:
Multiple Run
END DESCRIPTION:

--- CCLC 078.f01 (steady flow) ---

Flow Title=Multiple
Program Version=4.10
Number of Profiles= 7
Profile Names=10-year,25-year,50-year,1pct_min,100-year,1pct_plu,500-year
River Rch & RM=CCLC 078,Reach-1         ,10352
     700     966    1321     595    1797    5427    3437
River Rch & RM=CCLC 078,Reach-1         ,7479
    1423    2031    2841    1303    3936   11887    7835
Boundary for River Rch & Prof#=CCLC 078,Reach-1         , 1
Up Type= 0
Dn Type= 3
Dn Slope=0.005
Boundary for River Rch & Prof#=CCLC 078,Reach-1         , 2
Up Type= 0
Dn Type= 3
Dn Slope=0.005
Boundary for River Rch & Prof#=CCLC 078,Reach-1         , 3
Up Type= 0
Dn Type= 3
Dn Slope=0.005
Boundary for River Rch & Prof#=CCLC 078,Reach-1         , 4
Up Type= 0
Dn Type= 3
Dn Slope=0.005
Boundary for River Rch & Prof#=CCLC 078,Reach-1         , 5
Up Type= 0
Dn Type= 3
Dn Slope=0.005
Boundary for River Rch & Prof#=CCLC 078,Reach-1         , 6
Up Type= 0
Dn Type= 3
Dn Slope=0.005
Boundary for River Rch & Prof#=CCLC 078,Reach-1         , 7
Up Type= 0
Dn Type= 3
Dn Slope=0.005
DSS Import GetInterval= 0
DSS Import GetPeak= 0
DSS Import FillOption= 0

--- CCLC 078.f02 (steady flow) ---

Flow Title=Orig_BLE_Flows
Program Version=4.10
Number of Profiles= 7
Profile Names=10-year,25-year,50-year,1pct_min,100-year,1pct_plu,500-year
River Rch & RM=CCLC 078,Reach-1         ,10352
     700     947    1149     458    1382    4173    1998
River Rch & RM=CCLC 078,Reach-1         ,7479
    1423    1991    2470    1003    3028    9145    4555
Boundary for River Rch & Prof#=CCLC 078,Reach-1         , 1
Up Type= 0
Dn Type= 3
Dn Slope=0.005
Boundary for River Rch & Prof#=CCLC 078,Reach-1         , 2
Up Type= 0
Dn Type= 3
Dn Slope=0.005
Boundary for River Rch & Prof#=CCLC 078,Reach-1         , 3
Up Type= 0
Dn Type= 3
Dn Slope=0.005
Boundary for River Rch & Prof#=CCLC 078,Reach-1         , 4
Up Type= 0
Dn Type= 3
Dn Slope=0.005
Boundary for River Rch & Prof#=CCLC 078,Reach-1         , 5
Up Type= 0
Dn Type= 3
Dn Slope=0.005
Boundary for River Rch & Prof#=CCLC 078,Reach-1         , 6
Up Type= 0
Dn Type= 3
Dn Slope=0.005
Boundary for River Rch & Prof#=CCLC 078,Reach-1         , 7
Up Type= 0
Dn Type= 3
Dn Slope=0.005
DSS Import GetInterval= 0
DSS Import GetPeak= 0
DSS Import FillOption= 0

--- CCLC 078.g01 (geometry) ---

Geom Title=Existing Conditions
Program Version=4.10

River Reach=CCLC 078        ,Reach-1
Reach XY= 30
      3679993.23     10183926.84      3680108.23     10183936.84
      3680188.23     10184026.84      3680278.23     10183996.84
      3680698.23     10184246.84      3680848.23     10184356.84
      3680918.23     10184536.84      3681078.23     10184596.84
      3681108.23     10184686.84      3681438.23     10184616.84
      3681638.23     10184686.84      3681776.41     10184832.12
      3681958.23     10184876.84      3682430.38     10184646.78
      3682569.72     10184680.15      3682703.46      10184806.2
       3683116.4     10184769.19      3683269.85      10184955.1
      3683566.58     10184888.53      3684379.95     10185265.01
      3685248.96     10185539.53      3685389.43     10185607.75
      3685548.37     10185857.07      3685670.78     10185935.32
      3686149.62     10185961.54      3686752.92     10185892.96
      3687558.17     10186119.24      3688360.77     10186565.35
       3688826.2     10186676.54      3689098.23     10186676.84

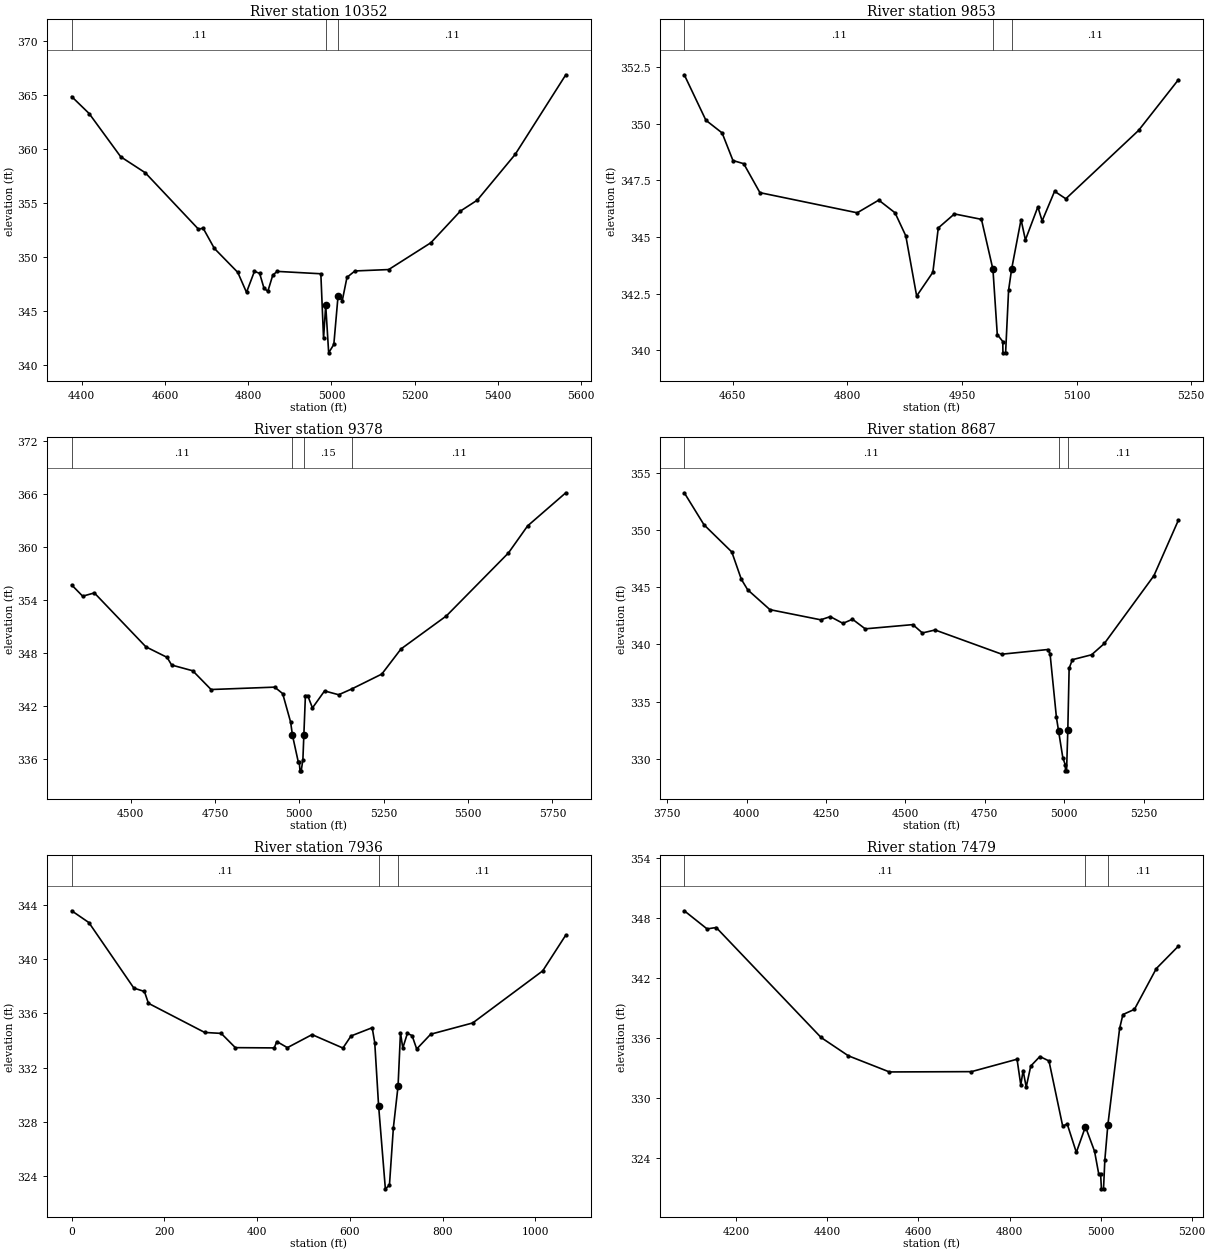
Type RM Length L Ch R = 1 ,10352   ,499,499,499
BEGIN DESCRIPTION:
CCLC 078 18.0
END DESCRIPTION:
XS GIS Cut Line= 3
      3680017.85     10184611.09      3680208.23     10184016.84
      3680117.85     10183461.05
#Sta/Elev= 30
    4376  364.82    4418  363.25  4493.8  359.25  4552.8  357.77  4680.5  352.55
  4691.8  352.64  4718.7  350.77    4775  348.55    4796   346.7  4815.1  348.65
  4827.6  348.45  4838.1  347.07  4847.3   346.8  4859.1  348.29  4869.6  348.64
  4974.6  348.42  4981.1  342.43  4986.3  345.51  4993.4   341.1  5005.8  341.88
    5016  346.39  5026.1  345.94  5037.4  348.09  5056.5  348.68  5137.6  348.81
  5238.9  351.29  5309.8  354.22  5350.3  355.23  5441.5  359.47  5563.1  366.84
#Mann= 3 , 0 , 0
    4376     .11       0  4986.3     .06       0    5016     .11       0
Bank Sta=4986.3,5016
XS Rating Curve= 0 ,0
Exp/Cntr=0.3,0.1

Type RM Length L Ch R = 1 ,9853    ,475,475,475
BEGIN DESCRIPTION:
CCLC 078 17.0
END DESCRIPTION:
XS GIS Cut Line= 3
      3680317.84     10184511.08      3680608.23     10184216.84
      3680717.87     10184011.03
#Sta/Elev= 30
  4586.6  352.17  4614.9  350.16  4636.1   349.6  4650.3  348.38  4664.4  348.24
  4685.6  346.96  4812.9  346.07  4841.1  346.63  4862.4  346.07  4876.5  345.05
  4890.7  342.39  4911.9  343.44    4919   345.4  4940.1  346.02  4975.5  345.78
 4990.53343.5688  4996.2  340.69  5003.4  340.38  5003.6  339.88  5007.1  339.88
    5011  342.65 5015.03343.5903  5027.3  345.77    5033  344.87  5049.3  346.33
  5054.9  345.71  5071.2  347.02  5085.9  346.69  5181.1  349.71  5233.2  351.95
#Mann= 3 , 0 , 0
  4586.6     .11       0 4990.53     .06       0 5015.03     .11       0
Bank Sta=4990.53,5015.03
XS Rating Curve= 0 ,0
Exp/Cntr=0.3,0.1

Type RM Length L Ch R = 1 ,9378    ,691,691,691
BEGIN DESCRIPTION:
CCLC 078 16.0
END DESCRIPTION:
XS GIS Cut Line= 3
      3680267.86     10184761.07      3680888.23     10184496.84
      3681417.85     10183911.07
#Sta/Elev= 30
  4325.7   355.7  4358.3  354.43  4392.9   354.8  4545.6   348.7  4608.3  347.51
  4621.9  346.64  4684.4  345.99  4738.7  343.87  4927.2  344.14  4950.8  343.41
  4974.4  340.18  4979.9  338.68  4997.1  335.67    5000  335.67  5002.2  334.67
  5005.7  334.67  5010.7  335.91 5013.59338.7149  5018.2  343.19  5024.9  343.19
  5039.1  341.79  5074.9  343.71  5116.8  343.28  5155.2  343.93  5244.6  345.62
  5301.4  348.46  5435.9   352.2  5619.7  359.32  5676.5  362.38  5789.7  366.13
#Mann= 4 ,-1 , 0
  4325.7     .11       0  4979.9     .06       0 5013.59     .15       0
  5155.2     .11       0
Bank Sta=4979.9,5013.59
XS Rating Curve= 0 ,0
Exp/Cntr=0.3,0.1

Type RM Length L Ch R = 1 ,8687    ,751,751,751
BEGIN DESCRIPTION:
CCLC 078 15.0
END DESCRIPTION:
XS GIS Cut Line= 3
      3680368.25     10184743.97      3681399.55     10184780.43
      3681462.05     10184259.61
#Sta/Elev= 30
  3803.3  353.28  3865.4  350.48    3953   348.1    3983  345.71    4003  344.79
  4073.1  343.05  4233.2  342.16  4263.2  342.44  4303.2  341.85  4333.2  342.21
  4373.3  341.37  4523.3  341.74  4553.4  341.01  4593.4  341.27  4803.5  339.15
  4948.6  339.56  4955.5   339.2  4975.6  333.62 4982.23 332.459  4995.7   330.1
  5003.8  329.44  5004.1  328.94  5007.6  328.94 5011.48332.5113 5015.66  337.92
  5025.9  338.67  5086.4   339.1  5126.7  340.09  5282.7  346.02  5359.8  350.88
#Mann= 3 , 0 , 0
  3803.3     .11       0 4982.23     .09       0 5011.48     .11       0
Bank Sta=4982.23,5011.48
XS Rating Curve= 0 ,0
Exp/Cntr=0.3,0.1

Type RM Length L Ch R = 1 ,7936    ,457,457,457
BEGIN DESCRIPTION:
CCLC 078 14.0
END DESCRIPTION:
XS GIS Cut Line= 3
      3682317.85     10185461.07      3682029.76     10184842.93
      3682073.16     10184460.18
#Sta/Elev= 30
       0  343.56    37.1  342.69   134.1  337.86   156.9  337.61   165.5  336.74
   286.9  334.59   322.5  334.52     353  333.47   436.9  333.45   442.4  333.92
   465.3  333.47   518.5  334.43   585.1  333.44   602.5  334.33   648.2  334.94
   653.7  333.84     662  329.19   676.6  323.06   685.4  323.33   693.9  327.57
     704  330.64   709.2  334.57   714.2  333.44   724.1  334.52   734.2  334.36
   744.2  333.37   774.4  334.46     865  335.29    1016  339.13  1065.8  341.77
#Mann= 3 ,-1 , 0
       0     .11       0     662     .06       0     704     .11       0
Bank Sta=662,704
XS Rating Curve= 0 ,0
Exp/Cntr=0.3,0.1

Type RM Length L Ch R = 1 ,7479    ,500,500,500
BEGIN DESCRIPTION:
CCLC 078 13.0
END DESCRIPTION:
XS GIS Cut Line= 3
      3682467.85      10185561.1      3682424.74     10184647.82
      3682373.89     10184484.77
#Sta/Elev= 30
  4085.7  348.69  4135.8  346.88  4155.8  347.02  4386.1  336.04  4446.1  334.21
  4536.2   332.6  4716.4  332.63  4816.5  333.87  4824.7   331.3  4829.8  332.74
  4836.6  331.09  4846.6  333.19  4866.6  334.14  4886.6   333.7  4916.7   327.2
  4926.7   327.4  4946.7  324.57  4966.7  327.13  4986.7  324.68  4995.9  322.41
    5000  322.41  5001.8  320.93  5006.4  320.93  5009.3  323.82 5015.83327.2841
  5041.8  336.96    5049  338.33  5074.3  338.85  5122.3  342.92  5170.8  345.16
#Mann= 3 , 0 , 0
  4085.7     .11       0  4966.7     .06       0 5015.83     .11       0
Bank Sta=4966.7,5015.83
XS Rating Curve= 0 ,0
Exp/Cntr=0.3,0.1

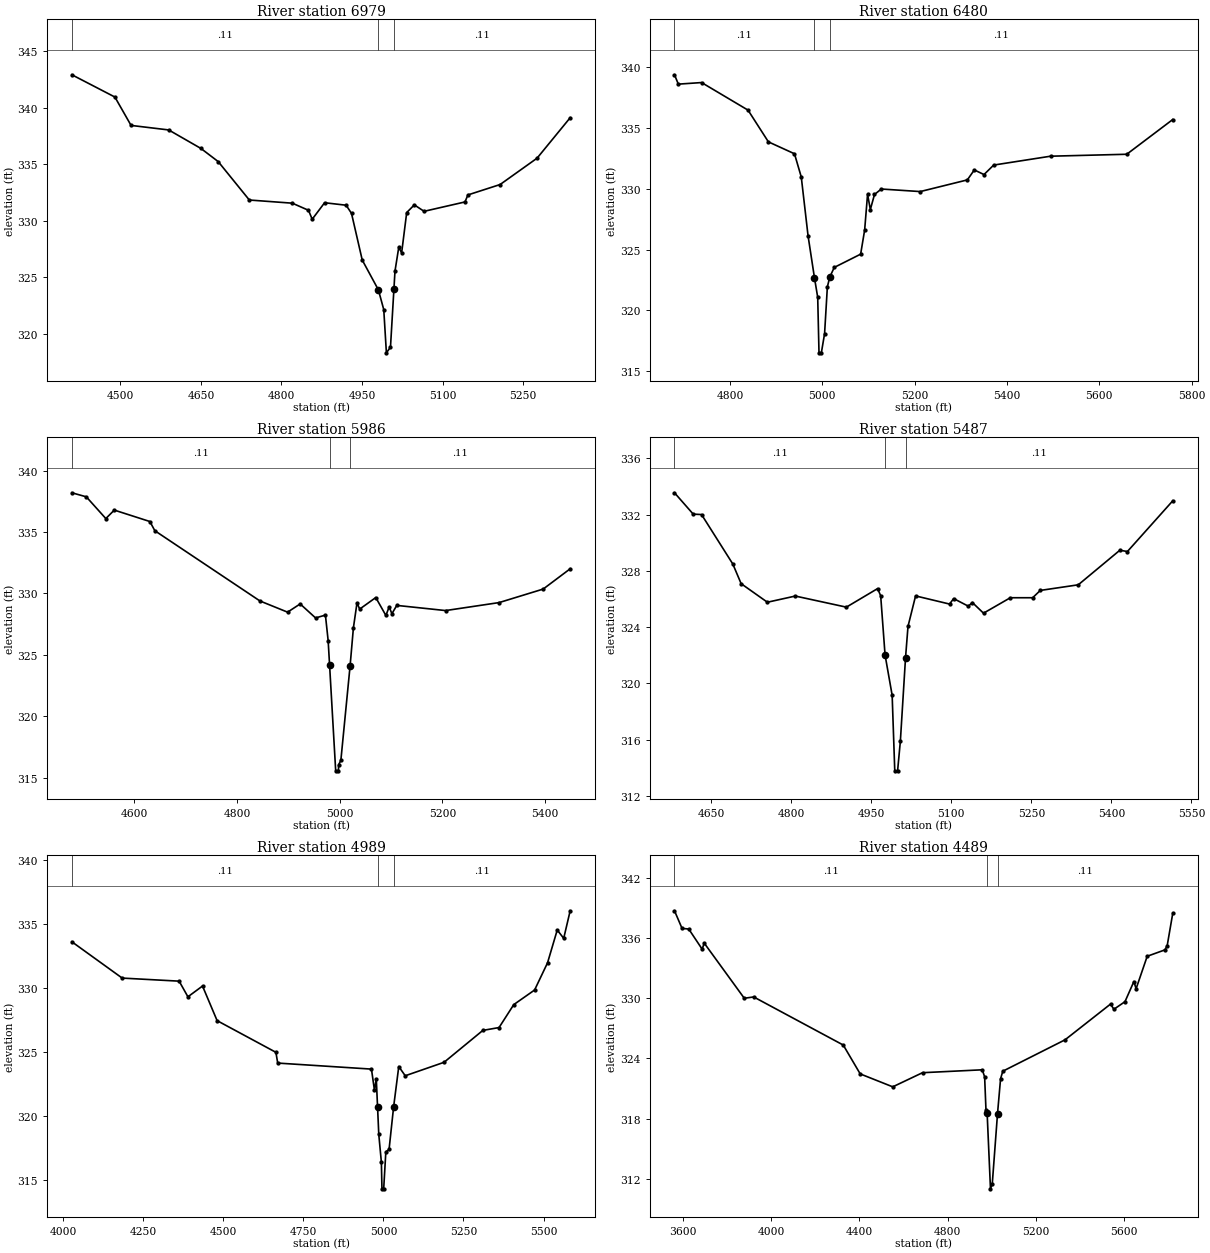
Type RM Length L Ch R = 1 ,6979    ,499,499,499
BEGIN DESCRIPTION:
CCLC 078 12.0
END DESCRIPTION:
XS GIS Cut Line= 3
      3682817.85     10185361.07      3682850.69     10184771.58
      3682717.86      10184461.1
#Sta/Elev= 30
  4409.6  342.92  4489.7  340.95  4519.8  338.44  4589.9  338.04    4650   336.4
  4682.1  335.24  4740.1  331.84  4820.2  331.56  4850.3  330.93  4857.2  330.14
  4880.3   331.6  4920.4  331.38  4930.4  330.66  4950.4  326.53  4980.5  323.89
  4990.5  322.14  4995.4  318.32    5003  318.82 5009.45323.9879  5011.4  325.55
  5018.4  327.65  5023.8  327.17  5033.2  330.73  5047.4  331.41  5065.6  330.84
  5141.8  331.67  5147.2  332.29  5207.2  333.21    5276  335.54  5337.7  339.12
#Mann= 3 , 0 , 0
  4409.6     .11       0  4980.5     .06       0 5009.45     .11       0
Bank Sta=4980.5,5009.45
XS Rating Curve= 0 ,0
Exp/Cntr=0.3,0.1

Type RM Length L Ch R = 1 ,6480    ,494,494,494
BEGIN DESCRIPTION:
CCLC 078 11.0
END DESCRIPTION:
XS GIS Cut Line= 3
      3683061.03     10185197.07      3683248.24      10184937.3
      3683670.41     10184306.43
#Sta/Elev= 30
  4679.8  339.39  4688.1  338.62  4738.5  338.75  4839.1  336.48  4883.2  333.87
  4939.7  332.89  4954.4  330.98  4969.1  326.14    4983  322.68    4990  321.08
  4992.8  316.51  4997.9  316.51  5004.9  318.09  5010.9  321.93 5016.08322.7432
  5025.9  323.54    5083  324.63  5091.7  326.62    5098  329.56    5104   328.3
    5113  329.54  5127.8  329.99  5212.1  329.78  5314.1  330.74  5329.2  331.56
  5350.2  331.18  5371.2  331.96  5494.3  332.69  5659.4  332.85  5759.1  335.71
#Mann= 3 , 0 , 0
  4679.8     .11       0    4983     .06       0 5016.08     .11       0
Bank Sta=4983,5016.08
XS Rating Curve= 0 ,0
Exp/Cntr=0.3,0.1

Type RM Length L Ch R = 1 ,5986    ,499,499,499
BEGIN DESCRIPTION:
CCLC 078 10.0
END DESCRIPTION:
XS GIS Cut Line= 3
      3683482.88     10185462.74      3683671.47     10184976.21
      3683816.21     10184551.29
#Sta/Elev= 30
  4478.2   338.2  4506.3  337.87  4544.3   336.1  4560.8  336.79  4630.1  335.86
  4639.8  335.11  4844.6  329.39  4898.4  328.48  4922.9  329.15  4952.9  328.01
  4972.1  328.24  4977.4  326.17 4980.23324.1551  4992.1  315.56  4997.4  315.56
  4997.9  316.06  5002.2  316.42 5020.23324.1352  5026.6   327.2  5033.6  329.23
  5038.9  328.73  5070.2  329.67  5089.9  328.21  5096.3  328.91  5101.6  328.35
  5111.1  329.03  5206.2  328.61  5310.5  329.26  5396.3  330.36  5448.9  332.01
#Mann= 3 , 0 , 0
  4478.2     .11       0 4980.23     .06       0 5020.23     .11       0
Bank Sta=4980.23,5020.23
XS Rating Curve= 0 ,0
Exp/Cntr=0.3,0.1

Type RM Length L Ch R = 1 ,5487    ,498,498,498
BEGIN DESCRIPTION:
CCLC 078 9.0
END DESCRIPTION:
XS GIS Cut Line= 3
      3683917.87     10185511.04      3684130.51     10185150.24
      3684467.83     10184761.09
#Sta/Elev= 30
  4581.2  333.56  4616.3  332.04  4631.9  332.01  4690.5  328.49  4706.1  327.09
  4755.3  325.77  4807.6  326.21  4903.3  325.42  4961.8  326.74  4967.6  326.23
  4975.8  322.02  4989.1  319.15    4994  313.77  4999.3  313.77  5004.5  315.89
 5014.15321.8083  5018.8  324.05    5033  326.22  5096.7  325.64  5104.3  326.03
  5131.8  325.49  5139.4  325.75  5160.3  324.99  5210.6  326.09  5252.4  326.09
  5266.7  326.61  5337.9  327.01  5415.8  329.47    5430  329.38    5515  332.99
#Mann= 3 , 0 , 0
  4581.2     .11       0  4975.8     .06       0 5014.15     .11       0
Bank Sta=4975.8,5014.15
XS Rating Curve= 0 ,0
Exp/Cntr=0.3,0.1

Type RM Length L Ch R = 1 ,4989    ,500,500,500
BEGIN DESCRIPTION:
CCLC 078 8.0
END DESCRIPTION:
XS GIS Cut Line= 3
      3684107.89     10186186.67      3684584.85     10185338.36
      3684667.85      10184761.1
#Sta/Elev= 30
  4026.8  333.59  4183.9  330.76  4361.8  330.52  4389.2   329.3  4434.8  330.14
  4480.4  327.44    4664  324.97  4669.7  324.13  4962.5  323.66  4971.9  322.01
  4977.6  322.91 4981.55320.7072  4985.4  318.56  4993.5  316.39  4995.3  314.32
  5000.7  314.32  5007.4   317.2  5017.5  317.39 5031.69320.7085  5047.8  323.86
    5068  323.14  5189.2  324.19  5310.5  326.68    5361   326.9    5407  328.69
  5472.1  329.83  5512.5  331.95  5542.8  334.51    5563  333.86  5583.2  336.01
#Mann= 3 ,-1 , 0
  4026.8     .11       0 4981.55     .06       0 5031.69     .11       0
Bank Sta=4981.55,5031.69
XS Rating Curve= 0 ,0
Exp/Cntr=0.3,0.1

Type RM Length L Ch R = 1 ,4489    ,558,558,558
BEGIN DESCRIPTION:
CCLC 078 7.0
END DESCRIPTION:
XS GIS Cut Line= 3
      3684550.61     10186827.27      3685051.65     10185480.98
      3684962.07     10184665.99
#Sta/Elev= 30
  3563.5  338.74  3597.7  336.98    3628  336.92  3688.7  334.91  3698.2  335.51
  3879.5  330.01  3922.2  330.14  4327.7  325.34  4404.5  322.46  4551.8  321.17
  4686.6  322.58  4957.2  322.87  4967.9  322.17    4974  318.86  4979.3  318.52
  4994.4  310.99  5002.5  311.49 5026.28318.4982  5040.1  321.98  5050.2  322.73
  5331.9  325.86  5538.1  329.43  5553.2  328.91  5603.5  329.67  5643.8  331.68
  5653.8  330.96  5704.1   334.2  5784.6  334.84  5794.7  335.27  5819.9   338.5
#Mann= 3 , 0 , 0
  3563.5     .11       0  4979.3     .06       0 5026.28     .11       0
Bank Sta=4979.3,5026.28
XS Rating Curve= 0 ,0
Exp/Cntr=0.3,0.1

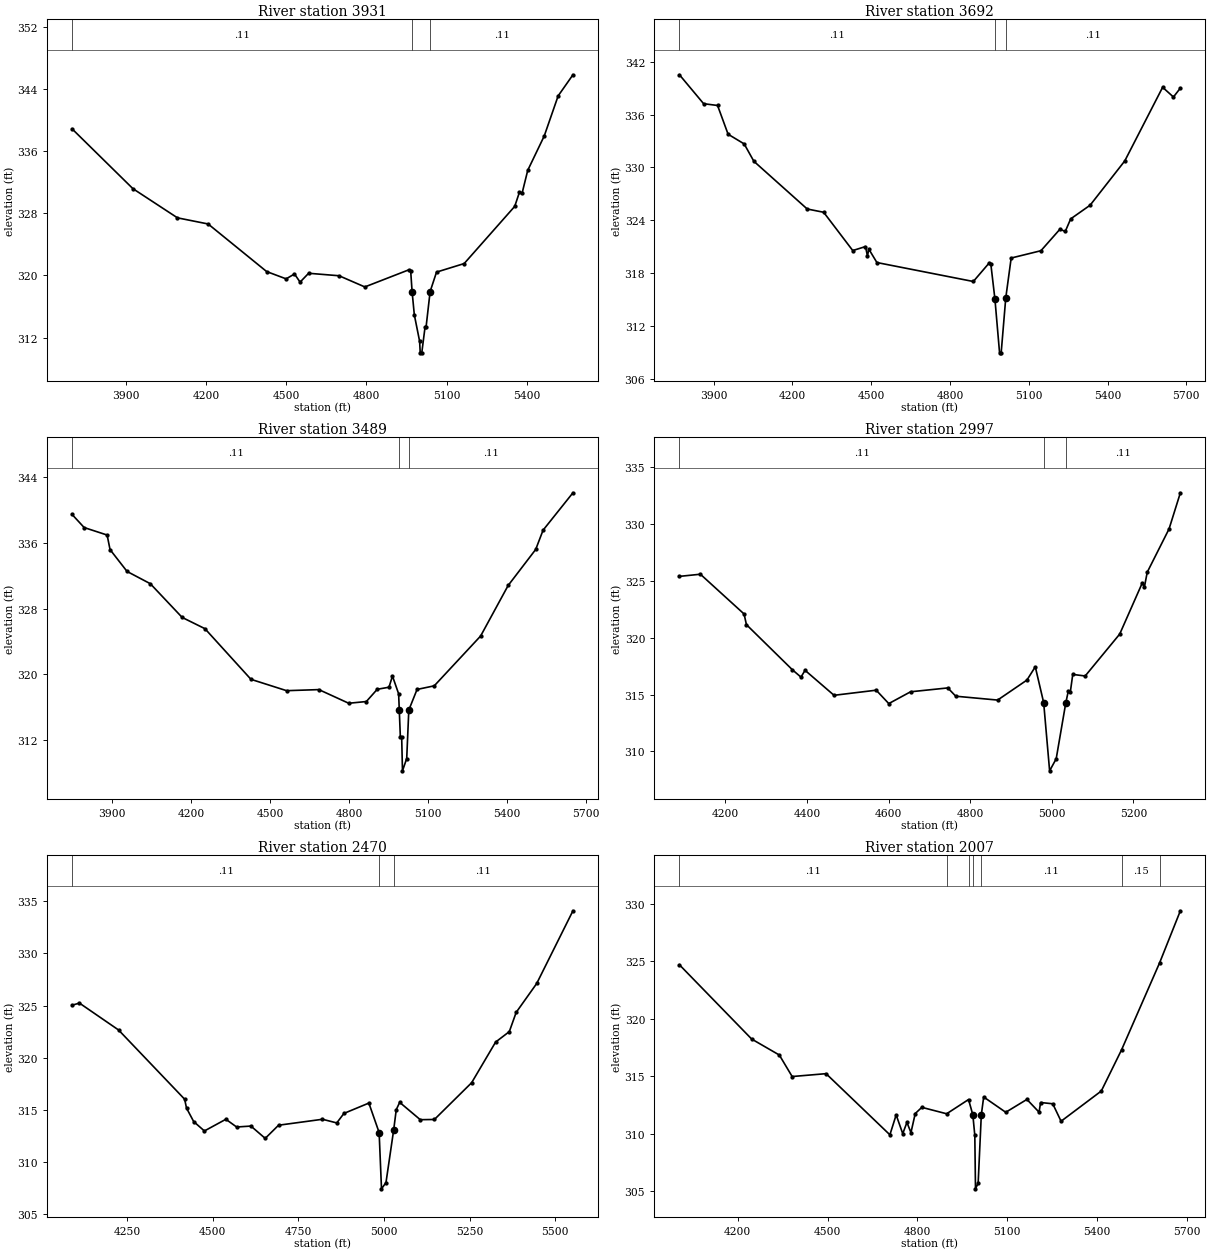
Type RM Length L Ch R = 1 ,3931    ,239,239,239
BEGIN DESCRIPTION:
CCLC 078 6.0
END DESCRIPTION:
XS GIS Cut Line= 3
      3685123.52     10187009.56      3685498.51     10185738.76
      3685639.13     10185207.53
#Sta/Elev= 30
  3698.5  338.89  3926.3  331.18  4093.1  327.42  4207.8  326.63  4426.8   320.5
  4499.7  319.56    4531  320.19  4551.9  319.14  4583.9  320.28  4697.8  319.96
  4794.2  318.52  4958.5  320.72  4965.9  320.52  4971.1   317.9  4979.4  314.93
  4999.2  311.52  5001.5  310.03  5007.3  310.03  5019.7  313.39  5023.5  313.39
  5038.5  317.92  5062.5  320.43  5165.9  321.53  5355.2   328.9  5372.8  330.73
  5383.1  330.65  5403.8  333.54  5465.5  337.96  5517.6  343.13    5573  345.85
#Mann= 3 , 0 , 0
  3698.5     .11       0  4971.1     .06       0  5038.5     .11       0
Bank Sta=4971.1,5038.5
XS Rating Curve= 0 ,0
Exp/Cntr=0.3,0.1

Type RM Length L Ch R = 1 ,3692    ,203,203,203
BEGIN DESCRIPTION:
Mapping XS 8cedb017
END DESCRIPTION:
XS GIS Cut Line= 3
      3685258.94     10187087.67      3685597.47     10186150.22
      3685816.07     10185265.43
#Sta/Elev= 30
  3769.4  340.51  3861.5  337.23  3914.6  337.03  3954.7  333.77    4016  332.67
  4052.9   330.7  4256.1  325.29  4318.7  324.92  4429.5  320.58  4478.1  321.03
  4485.5  319.96  4490.8  320.74  4521.5  319.22  4888.8  317.07  4950.4  319.21
  4955.6  319.03  4971.2  315.05  4988.8  308.98  4994.9  308.98  5012.4  315.21
    5033  319.73  5146.4  320.56  5218.5  322.99  5239.1  322.75  5259.7  324.17
  5333.7  325.72  5465.7  330.74  5609.9  339.09  5651.1  337.99  5677.5     339
#Mann= 3 , 0 , 0
  3769.4     .11       0  4971.2     .06       0  5012.4     .11       0
Bank Sta=4971.2,5012.4
XS Rating Curve= 0 ,0
Exp/Cntr=0.3,0.1

Type RM Length L Ch R = 1 ,3489    ,492,492,492
BEGIN DESCRIPTION:
CCLC 078 5.0
END DESCRIPTION:
XS GIS Cut Line= 3
      3685347.47     10187103.35      3685848.08     10185956.99
      3686034.44     10185334.28
#Sta/Elev= 30
  3749.1  339.46  3795.2  337.86  3882.3  336.95  3893.4  335.18    3958  332.52
  4046.2  331.03    4167  326.93  4253.5  325.56  4428.1   319.4  4563.3  318.02
  4685.8  318.15  4799.1  316.49    4866   316.7  4907.4  318.19  4951.9  318.44
  4965.1   319.8  4988.5  317.64 4990.95315.6761    4995  312.43    5000  312.43
  5003.1  308.27  5019.2  309.77  5027.1  315.66  5058.4  318.17  5123.7  318.61
  5299.7  324.67  5404.2  330.82  5508.7   335.2  5536.6  337.54    5650  342.09
#Mann= 3 , 0 , 0
  3749.1     .11       0 4990.95     .06       0  5027.1     .11       0
Bank Sta=4990.95,5027.1
XS Rating Curve= 0 ,0
Exp/Cntr=0.3,0.1

Type RM Length L Ch R = 1 ,2997    ,527,527,527
BEGIN DESCRIPTION:
CCLC 078 4.0
END DESCRIPTION:
XS GIS Cut Line= 3
      3686517.85     10186811.06      3686315.42     10185921.61
      3686367.85      10185611.1
#Sta/Elev= 30
  4087.8  325.41  4139.1   325.6  4246.1   322.1  4251.9  321.16  4364.7  317.18
  4385.5  316.54  4395.5  317.14  4466.5  314.94  4569.8  315.39  4600.6  314.21
    4654  315.25  4745.2  315.59  4764.7  314.86  4867.2  314.52    4939  316.28
  4959.5  317.45    4980   314.3  4994.6  308.29  5010.7  309.35 5034.01314.2314
  5040.3   315.3  5045.4  315.25  5051.3  316.78  5081.7  316.64  5166.3  320.33
  5221.7  324.84  5226.8  324.48  5233.8  325.78  5287.2  329.59  5314.9  332.77
#Mann= 3 , 0 , 0
  4087.8     .11       0    4980     .06       0 5034.01     .11       0
Bank Sta=4980,5034.01
XS Rating Curve= 0 ,0
Exp/Cntr=0.3,0.1

Type RM Length L Ch R = 1 ,2470    ,463,463,463
BEGIN DESCRIPTION:
CCLC 078 3.0
END DESCRIPTION:
XS GIS Cut Line= 3
      3686567.84     10186811.11      3686816.22     10185988.76
      3686805.82     10185385.29
#Sta/Elev= 30
  4089.2  325.03  4110.9  325.23    4225  322.66    4418  316.03  4423.5  315.18
  4444.4  313.89  4475.7  312.99  4538.4  314.11  4569.8  313.37  4611.5  313.46
  4653.3  312.28  4692.2  313.54  4820.5  314.11  4862.2  313.76  4883.1  314.67
  4955.9  315.66  4985.9  312.84  4992.8  307.45  5005.9  308.05 5028.26313.0665
  5035.9  315.03  5045.9  315.73    5106  314.07  5147.3  314.09    5256  317.61
    5326   321.5    5366   322.5    5386  324.34    5446  327.11  5551.8  334.07
#Mann= 3 , 0 , 0
  4089.2     .11       0  4985.9     .06       0 5028.26     .11       0
Bank Sta=4985.9,5028.26
XS Rating Curve= 0 ,0
Exp/Cntr=0.3,0.1

Type RM Length L Ch R = 1 ,2007    ,946,946,946
BEGIN DESCRIPTION:
CCLC 078 2.0
END DESCRIPTION:
XS GIS Cut Line= 3
      3686617.86     10186811.06      3687259.87     10186051.82
      3687430.66     10185395.58
#Sta/Elev= 30
  4005.7  324.68  4246.9  318.22  4339.2  316.83    4382  314.96  4495.2  315.21
  4708.3  309.89  4729.2  311.62  4751.2  309.99  4765.2  310.97  4778.6  310.08
  4792.9  311.74  4814.9  312.28  4897.8  311.72  4970.9  312.96  4985.2  311.63
  4991.8  309.84  4994.1  305.19    5003  305.69 5013.47311.6123  5021.4  313.18
  5095.1  311.85  5165.8  312.97  5206.3  311.86  5211.5   312.7    5252  312.59
  5279.8  311.07  5414.1   313.7  5481.9  317.29  5608.6  324.84  5678.1  329.38
#Mann= 7 ,-1 , 0
  4005.7     .11       0  4897.8     .15       0  4970.9     .11       0
  4985.2     .07       0 5013.47     .11       0  5481.9     .15       0
  5608.6     .11       0
Bank Sta=4985.2,5013.47
XS Rating Curve= 0 ,0
Exp/Cntr=0.3,0.1

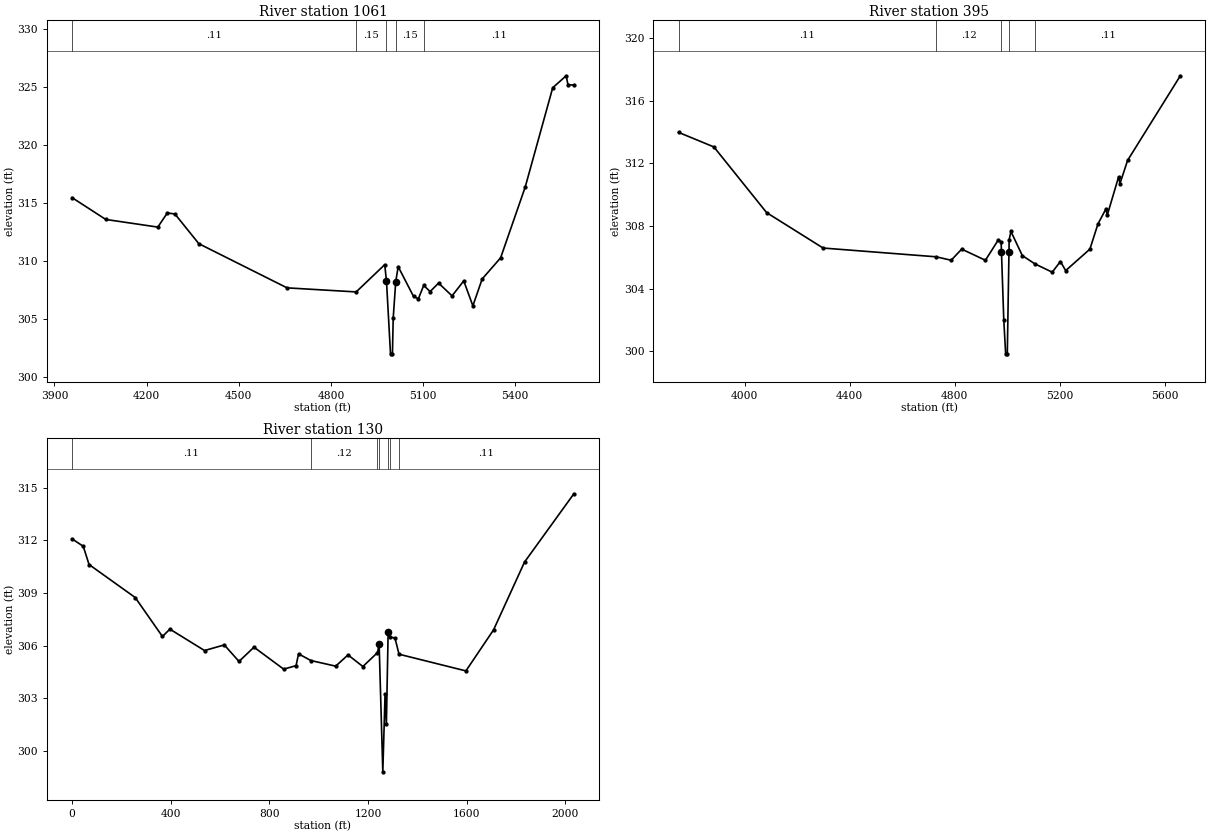
Type RM Length L Ch R = 1 ,1061    ,666,666,666
BEGIN DESCRIPTION:
Mapping XS 700a2677
END DESCRIPTION:
XS GIS Cut Line= 3
      3687175.64     10186780.42      3688019.34     10186587.72
      3688383.39     10185911.63
#Sta/Elev= 30
  3957.5  315.47  4067.2  313.59  4236.7  312.93  4267.5  314.15  4292.3  314.06
  4370.1   311.5  4657.3  307.69  4882.2  307.34  4975.2  309.69  4980.9  308.27
    4994     302  5000.3     302  5002.8  305.09 5011.02308.2293    5019  309.52
    5069  306.95  5084.7  306.75  5102.1   307.9  5122.9  307.37  5150.4   308.1
  5194.3     307  5232.4  308.29  5262.1  306.14  5292.4  308.46  5352.4  310.28
  5432.4  316.38    5522  324.95  5565.8  325.98  5571.5  325.22  5590.8  325.17
#Mann= 5 ,-1 , 0
  3957.5     .11       0  4882.2     .15       0  4980.9     .09       0
 5011.02     .15       0  5102.1     .11       0
Bank Sta=4980.9,5011.02
XS Rating Curve= 0 ,0
Exp/Cntr=0.3,0.1

Type RM Length L Ch R = 1 ,395     ,265,265,265
BEGIN DESCRIPTION:
CCLC 078 1.0
END DESCRIPTION:
XS GIS Cut Line= 3
       3687503.7     10186775.22      3688722.47     10186665.85
      3688571.67     10185995.05
#Sta/Elev= 30
  3748.5  313.98  3883.2  313.05    4084  308.86  4299.1   306.6  4730.1  306.04
  4786.8  305.82    4827  306.53  4917.3  305.82  4966.1  307.11  4977.2  306.99
 4978.49306.3539  4987.3  302.01  4994.4  299.85  5000.7  299.85 5007.03306.3389
  5007.8  307.13  5014.5  307.66  5057.8  306.12  5105.7  305.59  5171.8  305.06
    5203  305.74    5223  305.16  5315.3  306.53    5346  308.14  5376.2  309.09
  5381.3  308.69  5424.6  311.14  5429.8  310.71  5458.8  312.19  5659.7  317.59
#Mann= 5 ,-1 , 0
  3748.5     .11       0  4730.1     .12       0 4978.49     .06       0
 5007.03     .12       0  5105.7     .11       0
Bank Sta=4978.49,5007.03
XS Rating Curve= 0 ,0
Exp/Cntr=0.3,0.1

Type RM Length L Ch R = 1 ,130     ,0,0,0
BEGIN DESCRIPTION:
CCLC 078 1.0
END DESCRIPTION:
XS GIS Cut Line= 4
      3687732.67     10186821.55      3688955.41     10186721.63
      3688980.41      10186660.7      3688638.92      10186002.1
#Sta/Elev= 30
       0  312.08    45.3  311.66    68.8  310.62     256  308.74   366.4  306.52
   396.5  306.94     537  305.72   617.2  306.04   676.8   305.1   737.6  305.91
     858  304.66   908.2  304.86   918.2  305.53   968.4  305.15  1068.7  304.83
  1118.9  305.47  1179.1  304.81  1238.2   305.6    1245  306.08  1259.9  298.81
    1269  303.22  1274.4  301.55  1281.5  306.77  1289.8  306.47  1309.1  306.44
  1325.6  305.51  1596.8  304.56    1709   306.9  1834.5  310.76  2034.5  314.65
#Mann= 7 ,-1 , 0
       0     .11       0   968.4     .12       0  1238.2     .08       0
    1245     .06       0  1281.5     .08       0  1289.8     .12       0
  1325.6     .11       0
Bank Sta=1245,1281.5
XS Rating Curve= 0 ,0
Exp/Cntr=0.3,0.1

Chan Stop Cuts=-1
Use User Specified Reach Order=0
Composite Channel Slope=5