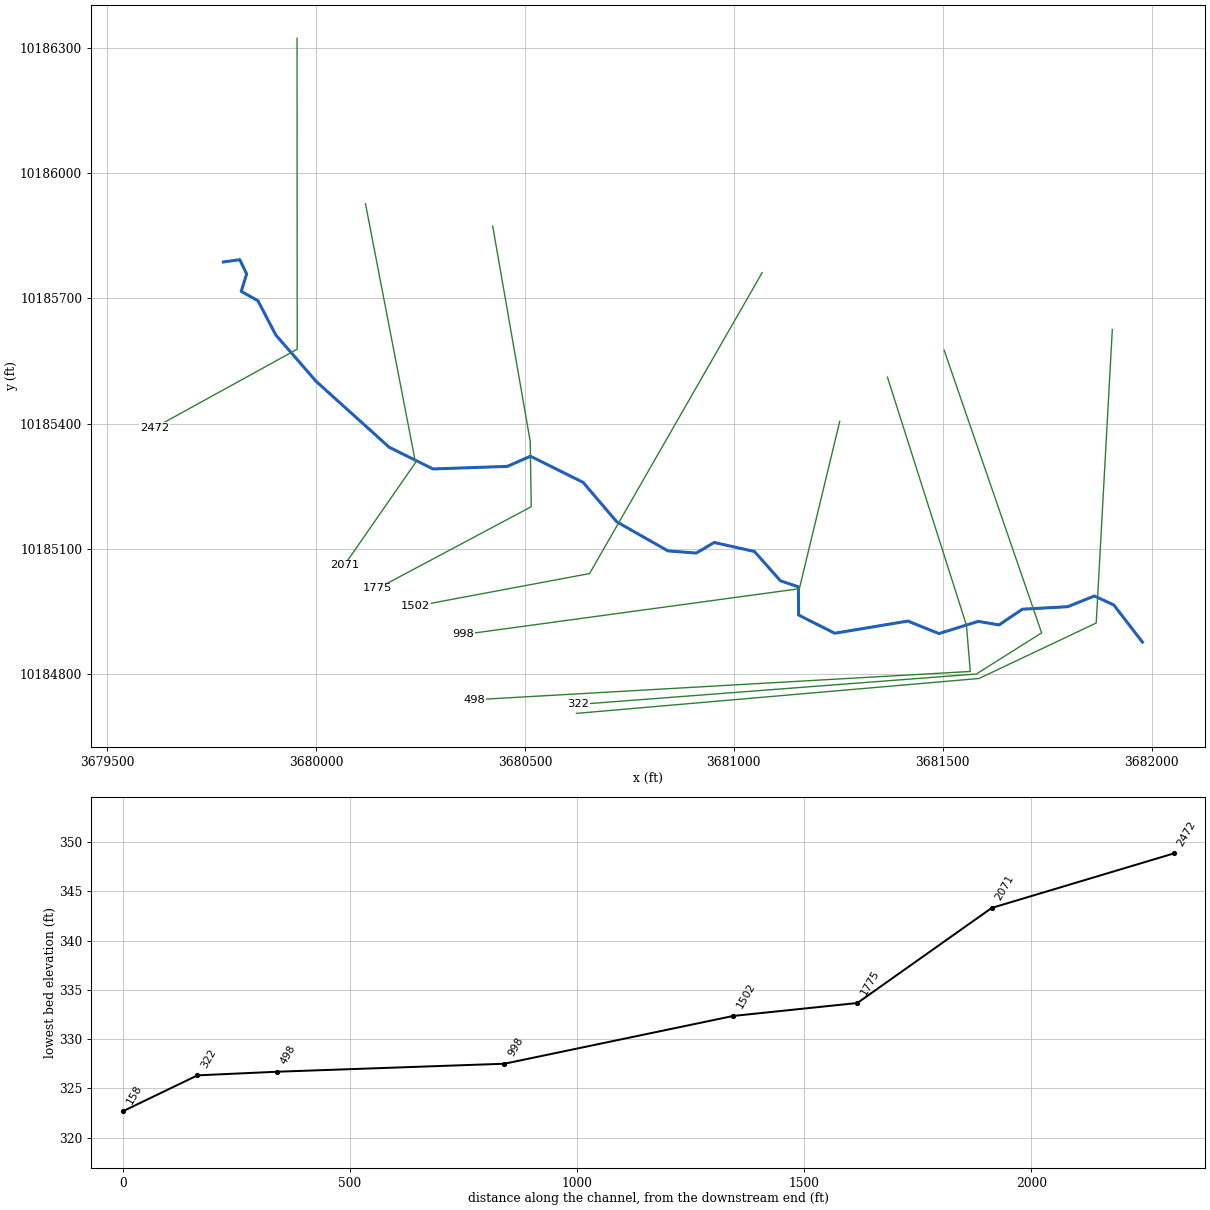
--- CCLC 079.prj (project) ---

Proj Title=CCLC 079 Base Level Engineering
Current Plan=p01
Default Exp/Contr=0.3,0.1
English Units
Geom File=g01
Flow File=f01
Flow File=f02
Plan File=p01
Y Axis Title=Elevation
X Axis Title(PF)=Main Channel Distance
X Axis Title(XS)=Station
BEGIN DESCRIPTION:
CCLC 079
END DESCRIPTION:
DSS Export Rating Curves= 0
DSS Export Rating Curve Sorted= 0
DSS Export Volume Flow Curves= 0
DXF OffsetX= 0
DXF OffsetY= 0
DXF ScaleX= 1
DXF ScaleY= 10

--- CCLC 079.p01 (plan) ---

Plan Title=Multiple Run
Short Identifier=Multiple
Geom File=g01
Flow File=f01
Subcritical Flow
K Sum by GR= 0
Std Step Tol= 0.01
Critical Tol= 0.01
Num of Std Step Trials= 20
Max Error Tol= 0.3
Flow Tol Ratio= 0.001
Split Flow NTrial= 30
Split Flow Tol= 0.02
Split Flow Ratio= 0.02
Log Output Level= 0
Friction Slope Method= 1
Unsteady Friction Slope Method= 2
Unsteady Bridges Friction Slope Method= 1
Parabolic Critical Depth
Global Vel Dist=  1 , 1 , 1
Global Log Level= 0
CheckData=True
Encroach Param= -1, 0, 0, 0
BEGIN DESCRIPTION:
Multiple Run
END DESCRIPTION:

--- CCLC 079.f01 (steady flow) ---

Flow Title=Multiple
Program Version=4.10
Number of Profiles= 7
Profile Names=10-year,25-year,50-year,1pct_min,100-year,1pct_plu,500-year
River Rch & RM=CCLC 079,Reach-1         ,2472
     593     804    1086     483    1459    4406    2721
Boundary for River Rch & Prof#=CCLC 079,Reach-1         , 1
Up Type= 0
Dn Type= 3
Dn Slope=0.005
Boundary for River Rch & Prof#=CCLC 079,Reach-1         , 2
Up Type= 0
Dn Type= 3
Dn Slope=0.005
Boundary for River Rch & Prof#=CCLC 079,Reach-1         , 3
Up Type= 0
Dn Type= 3
Dn Slope=0.005
Boundary for River Rch & Prof#=CCLC 079,Reach-1         , 4
Up Type= 0
Dn Type= 3
Dn Slope=0.005
Boundary for River Rch & Prof#=CCLC 079,Reach-1         , 5
Up Type= 0
Dn Type= 3
Dn Slope=0.005
Boundary for River Rch & Prof#=CCLC 079,Reach-1         , 6
Up Type= 0
Dn Type= 3
Dn Slope=0.005
Boundary for River Rch & Prof#=CCLC 079,Reach-1         , 7
Up Type= 0
Dn Type= 3
Dn Slope=0.005
DSS Import GetInterval= 0
DSS Import GetPeak= 0
DSS Import FillOption= 0

--- CCLC 079.f02 (steady flow) ---

Flow Title=Orig_BLE_Flows
Program Version=4.10
Number of Profiles= 7
Profile Names=10-year,25-year,50-year,1pct_min,100-year,1pct_plu,500-year
River Rch & RM=CCLC 079,Reach-1         ,2472
     593     788     944     372    1122    3389    1582
Boundary for River Rch & Prof#=CCLC 079,Reach-1         , 1
Up Type= 0
Dn Type= 3
Dn Slope=0.005
Boundary for River Rch & Prof#=CCLC 079,Reach-1         , 2
Up Type= 0
Dn Type= 3
Dn Slope=0.005
Boundary for River Rch & Prof#=CCLC 079,Reach-1         , 3
Up Type= 0
Dn Type= 3
Dn Slope=0.005
Boundary for River Rch & Prof#=CCLC 079,Reach-1         , 4
Up Type= 0
Dn Type= 3
Dn Slope=0.005
Boundary for River Rch & Prof#=CCLC 079,Reach-1         , 5
Up Type= 0
Dn Type= 3
Dn Slope=0.005
Boundary for River Rch & Prof#=CCLC 079,Reach-1         , 6
Up Type= 0
Dn Type= 3
Dn Slope=0.005
Boundary for River Rch & Prof#=CCLC 079,Reach-1         , 7
Up Type= 0
Dn Type= 3
Dn Slope=0.005
DSS Import GetInterval= 0
DSS Import GetPeak= 0
DSS Import FillOption= 0

--- CCLC 079.g01 (geometry) ---

Geom Title=Existing Conditions
Program Version=4.10

River Reach=CCLC 079        ,Reach-1
Reach XY= 30
      3679778.23     10185786.84      3679817.44     10185792.14
      3679833.79     10185758.14      3679820.77     10185716.44
      3679860.88     10185694.03      3679903.49     10185612.17
      3680000.29     10185500.92      3680174.85      10185343.4
      3680279.88     10185291.32      3680457.83      10185297.4
      3680513.39      10185321.7      3680639.26      10185259.2
      3680719.99     10185164.58      3680842.38     10185095.14
      3680910.09     10185089.93      3680953.18     10185115.27
      3681049.54     10185093.65      3681111.88     10185023.42
      3681154.72     10185009.04      3681155.12     10184941.61
      3681241.62     10184898.02      3681416.99     10184927.11
      3681491.02     10184897.11      3681585.41     10184926.42
      3681634.97      10184917.9      3681690.72     10184955.48
      3681799.36     10184961.55      3681863.19     10184987.17
      3681909.68     10184965.73      3681978.23     10184876.84

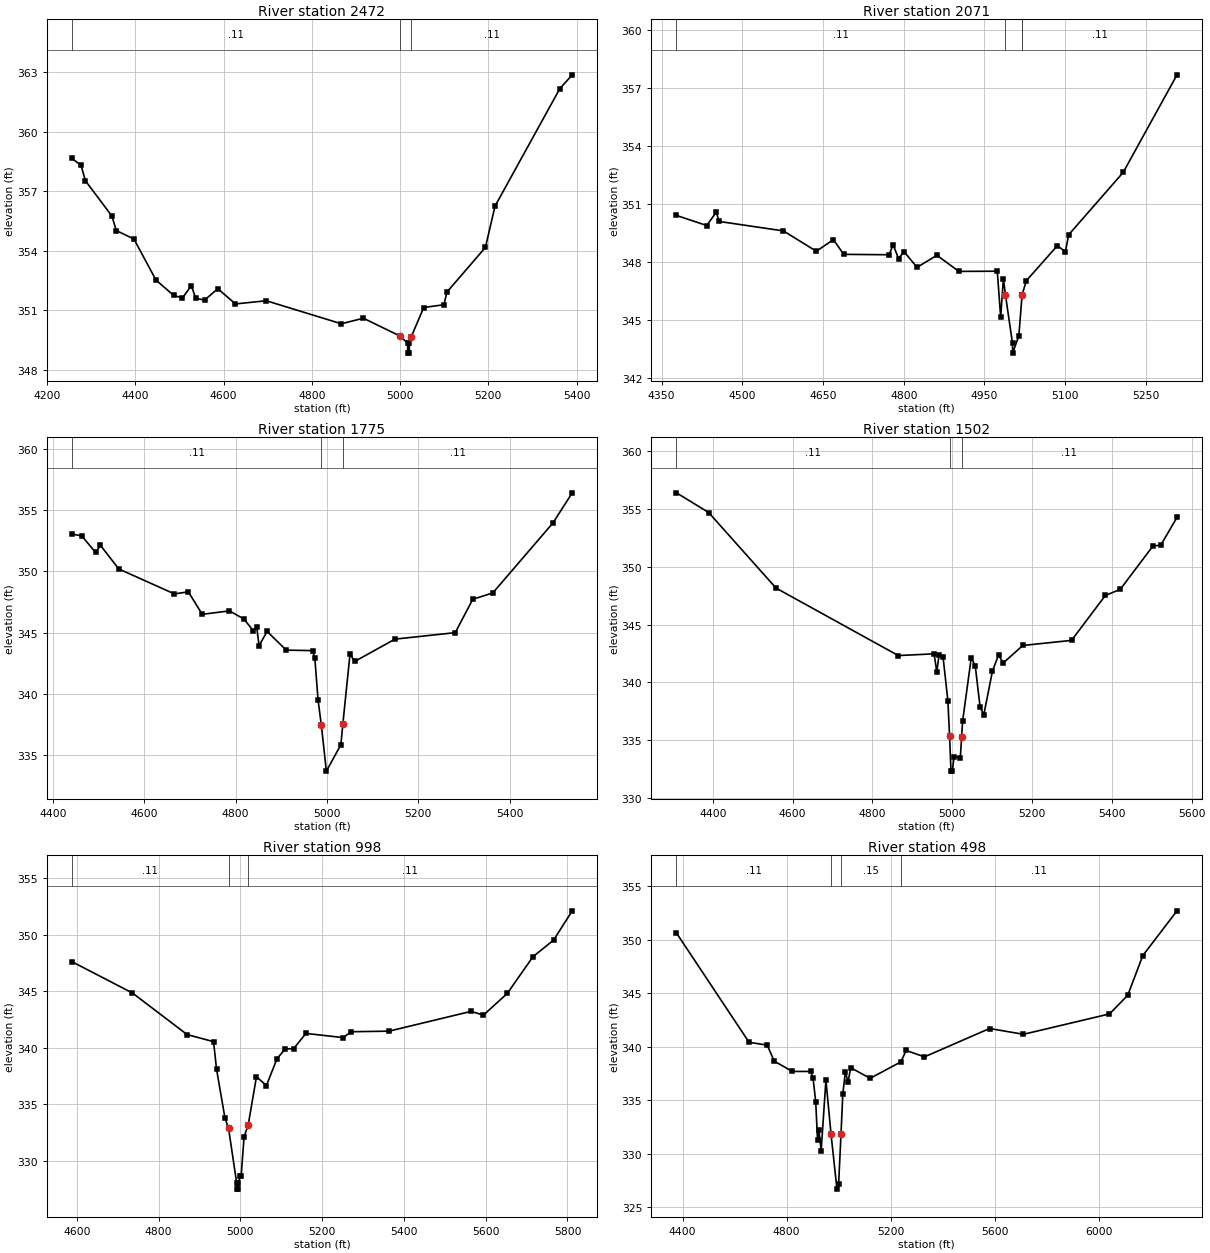
Type RM Length L Ch R = 1 ,2472    ,401,401,401
BEGIN DESCRIPTION:
CCLC 079 5.0
END DESCRIPTION:
XS GIS Cut Line= 3
      3679954.47     10186322.15       3679954.9     10185577.95
      3679613.07     10185389.79
#Sta/Elev= 30
  4255.8  358.66  4276.9  358.31  4286.9  357.53  4346.9  355.75  4356.9  355.02
  4396.9  354.59  4446.9  352.52  4486.9  351.75  4506.9  351.62  4526.9  352.24
  4536.9  351.61  4556.9  351.51  4586.9  352.09  4626.9  351.32  4696.9  351.48
  4866.9  350.32  4916.9   350.6    5000   349.7  5017.2  349.34  5017.4  348.84
  5020.9  348.84  5021.2  349.34  5024.9  349.64  5053.7  351.14  5099.4  351.28
  5106.3  351.92  5193.5  354.17  5215.2  356.25    5362  362.17  5390.2  362.87
#Mann= 3 ,-1 , 0
  4255.8     .11       0    5000     .06       0  5024.9     .11       0
Bank Sta=5000,5024.9
XS Rating Curve= 0 ,0
Exp/Cntr=0.3,0.1

Type RM Length L Ch R = 1 ,2071    ,296,296,296
BEGIN DESCRIPTION:
CCLC 079 4.0
END DESCRIPTION:
XS GIS Cut Line= 3
      3680118.31     10185926.21      3680238.09     10185306.47
      3680067.84     10185061.06
#Sta/Elev= 30
  4377.8  350.42    4434   349.9  4451.8  350.59  4456.9  350.11  4576.6  349.62
  4637.7  348.57  4669.3  349.17  4688.6  348.41  4772.9  348.39  4780.3  348.91
  4790.4  348.19  4800.6  348.55  4824.7  347.74  4861.7  348.36  4902.5  347.53
  4973.8  347.54  4980.1  345.17  4985.2  347.15 4989.05346.3109  5002.1  343.81
  5002.4  343.31  5013.9  344.21 5019.87346.3095  5019.9  346.32  5027.8  347.05
  5085.5  348.86  5100.3  348.54  5106.4  349.42  5207.7  352.64  5307.7  357.68
#Mann= 4 ,-1 , 0
  4377.8     .11       0 4989.05     .06       0 5019.87     .09       0
  5019.9     .11       0
Bank Sta=4989.05,5019.87
XS Rating Curve= 0 ,0
Exp/Cntr=0.3,0.1

Type RM Length L Ch R = 1 ,1775    ,273,273,273
BEGIN DESCRIPTION:
Mapping XS 3d0b2ecf
END DESCRIPTION:
XS GIS Cut Line= 4
      3680422.85     10185872.65      3680512.75     10185356.96
      3680515.11     10185200.83      3680147.61      10185005.3
#Sta/Elev= 30
  4441.3  353.06  4463.2  352.91  4493.7  351.55  4504.2  352.14  4544.4   350.2
  4666.2  348.16  4696.7  348.33  4727.1  346.49  4786.8  346.77  4818.5   346.1
  4838.8  345.15  4846.4  345.45  4851.5  343.93  4869.2  345.09    4911  343.56
  4968.7  343.52  4973.7  342.88  4980.7  339.49 4987.83337.4295  4998.9  333.66
  5030.7  335.82 5034.88337.4919  5050.7  343.24  5060.7  342.63  5149.2  344.46
  5281.1  344.99  5319.4  347.72  5363.3  348.24  5495.1  353.97  5537.2  356.43
#Mann= 3 , 0 , 0
  4441.3     .11       0 4987.83     .06       0 5034.88     .11       0
Bank Sta=4987.83,5034.88
XS Rating Curve= 0 ,0
Exp/Cntr=0.3,0.1

Type RM Length L Ch R = 1 ,1502    ,504,504,504
BEGIN DESCRIPTION:
CCLC 079 3.0
END DESCRIPTION:
XS GIS Cut Line= 3
      3681067.86     10185761.08      3680654.76     10185040.85
      3680238.11     10184962.72
#Sta/Elev= 30
  4309.1  356.36  4389.8  354.66  4558.7  348.14    4865  342.32  4954.7  342.47
  4961.4  340.91  4967.2   342.4  4977.2  342.17  4989.3  338.38 4993.39335.3641
    4997  332.35  5000.5  332.35  5004.5   333.6  5020.4  333.51 5023.65 335.306
  5026.1  336.66  5047.7  342.12  5057.7  341.45    5070  337.86  5079.3  337.23
  5100.9  340.99  5116.1  342.36  5128.2  341.69  5176.9  343.19    5299  343.63
  5383.9  347.51  5421.1  348.03  5502.5  351.75  5522.9  351.86  5563.3  354.24
#Mann= 3 , 0 , 0
  4309.1     .11       0 4993.39     .06       0 5023.65     .11       0
Bank Sta=4993.39,5023.65
XS Rating Curve= 0 ,0
Exp/Cntr=0.3,0.1

Type RM Length L Ch R = 1 ,998     ,500,500,500
BEGIN DESCRIPTION:
CCLC 079 2.0
END DESCRIPTION:
XS GIS Cut Line= 3
      3681253.71     10185405.39        3681157.     10185004.59
      3680352.73     10184895.02
#Sta/Elev= 30
  4587.7  347.64  4736.2  344.86  4869.9  341.18  4934.6  340.55  4941.9  338.12
  4962.5  333.79  4971.3  332.88  4991.3     328  4991.6   327.5  4995.1   327.5
  4995.3     328  4999.2  328.65  5002.1  328.65  5009.2  332.13  5019.3  333.17
  5039.5  337.44  5063.9  336.67    5090  339.06  5110.2  339.91  5130.3  339.93
  5160.6  341.28  5251.5  340.91  5271.6  341.43  5363.5  341.48  5564.3  343.23
  5594.6   342.9  5652.9  344.82  5715.7  348.07  5766.2  349.54  5811.7  352.13
#Mann= 3 , 0 , 0
  4587.7     .11       0  4971.3     .06       0  5019.3     .11       0
Bank Sta=4971.3,5019.3
XS Rating Curve= 0 ,0
Exp/Cntr=0.3,0.1

Type RM Length L Ch R = 1 ,498     ,176,176,176
BEGIN DESCRIPTION:
CCLC 079 1.0
END DESCRIPTION:
XS GIS Cut Line= 4
      3681367.85     10185511.07      3681556.97     10184917.15
      3681566.22     10184806.47      3680378.72     10184738.76
#Sta/Elev= 30
  4376.7  350.61  4655.8   340.4  4725.5  340.14  4752.5  338.64  4822.2  337.68
  4891.9  337.68  4901.4   337.1  4911.9  334.87  4918.8   331.3  4924.1  332.17
  4932.9  330.28  4951.1  336.88 4970.81331.8138  4993.6  326.69    5000  327.19
 5009.05331.7958  5016.1  335.61  5026.2  337.66  5036.2  336.66  5046.2  338.03
  5121.3  337.04  5238.9  338.57  5259.7  339.64  5329.8  339.04  5580.2  341.69
  5710.4  341.15  6040.9  343.05  6111.1  344.79  6169.1   348.5  6300.5  352.68
#Mann= 4 ,-1 , 0
  4376.7     .11       0 4970.81     .09       0 5009.05     .15       0
  5238.9     .11       0
Bank Sta=4970.81,5009.05
XS Rating Curve= 0 ,0
Exp/Cntr=0.3,0.1

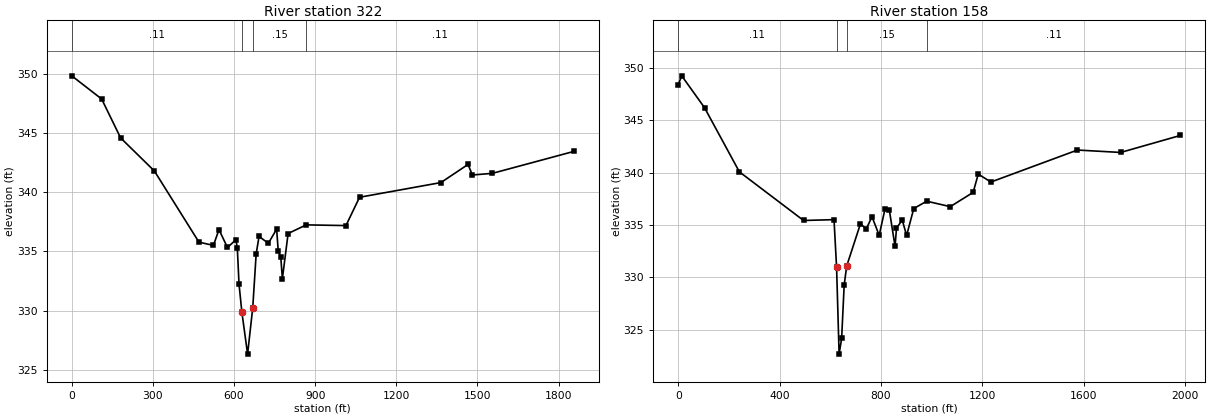
Type RM Length L Ch R = 1 ,322     ,164,164,164
BEGIN DESCRIPTION:
CCLC 079 0.5
END DESCRIPTION:
XS GIS Cut Line= 4
      3681503.58     10185575.64      3681737.01     10184898.89
      3681580.67     10184800.38      3680627.66     10184727.57
#Sta/Elev= 30
       0  349.81   110.6  347.85   180.6  344.57   305.4  341.78   470.3  335.77
   523.8   335.5   544.3  336.83   575.6  335.32   606.8  335.97   612.1  335.28
   618.4  332.23   628.9  329.87   650.1  326.32   669.2  330.25   681.8  334.78
   692.4  336.25   726.9  335.68   757.5  336.87   763.4  335.02   772.8   334.5
   778.7  332.69   799.9   336.5   866.9  337.23  1013.8  337.17    1064  339.56
  1364.8   340.8  1465.1  342.33  1481.2  341.44  1555.4  341.58  1856.4  343.43
#Mann= 4 ,-1 , 0
       0     .11       0   628.9     .09       0   669.2     .15       0
   866.9     .11       0
Bank Sta=628.9,669.2
XS Rating Curve= 0 ,0
Exp/Cntr=0.3,0.1

Type RM Length L Ch R = 1 ,158     ,0,0,0
BEGIN DESCRIPTION:
CCLC 079 0.1
END DESCRIPTION:
XS GIS Cut Line= 4
      3681906.19     10185624.89      3681867.65     10184922.45
       3681587.1     10184789.67      3680623.38     10184706.15
#Sta/Elev= 30
       0   348.4    13.8  349.23     104  346.18   241.3  340.07   494.6  335.43
   614.7  335.51   624.8  330.98   634.8  322.68   644.8  324.18   654.8  329.27
   664.8  331.09   719.1  335.12   741.9  334.62   764.6  335.79   792.9  334.01
   815.7  336.51   832.9  336.44   855.6  332.95   861.2   334.7   883.9  335.47
   901.2     334   929.4  336.57   980.5  337.27  1073.4  336.75  1163.7  338.11
  1183.8  339.85    1234   339.1  1575.2  342.15  1745.7  341.92  1981.2  343.54
#Mann= 4 ,-1 , 0
       0     .11       0   624.8     .09       0   664.8     .15       0
   980.5     .11       0
Bank Sta=624.8,664.8
XS Rating Curve= 0 ,0
Exp/Cntr=0.3,0.1

Chan Stop Cuts=-1
Use User Specified Reach Order=0
Composite Channel Slope=5