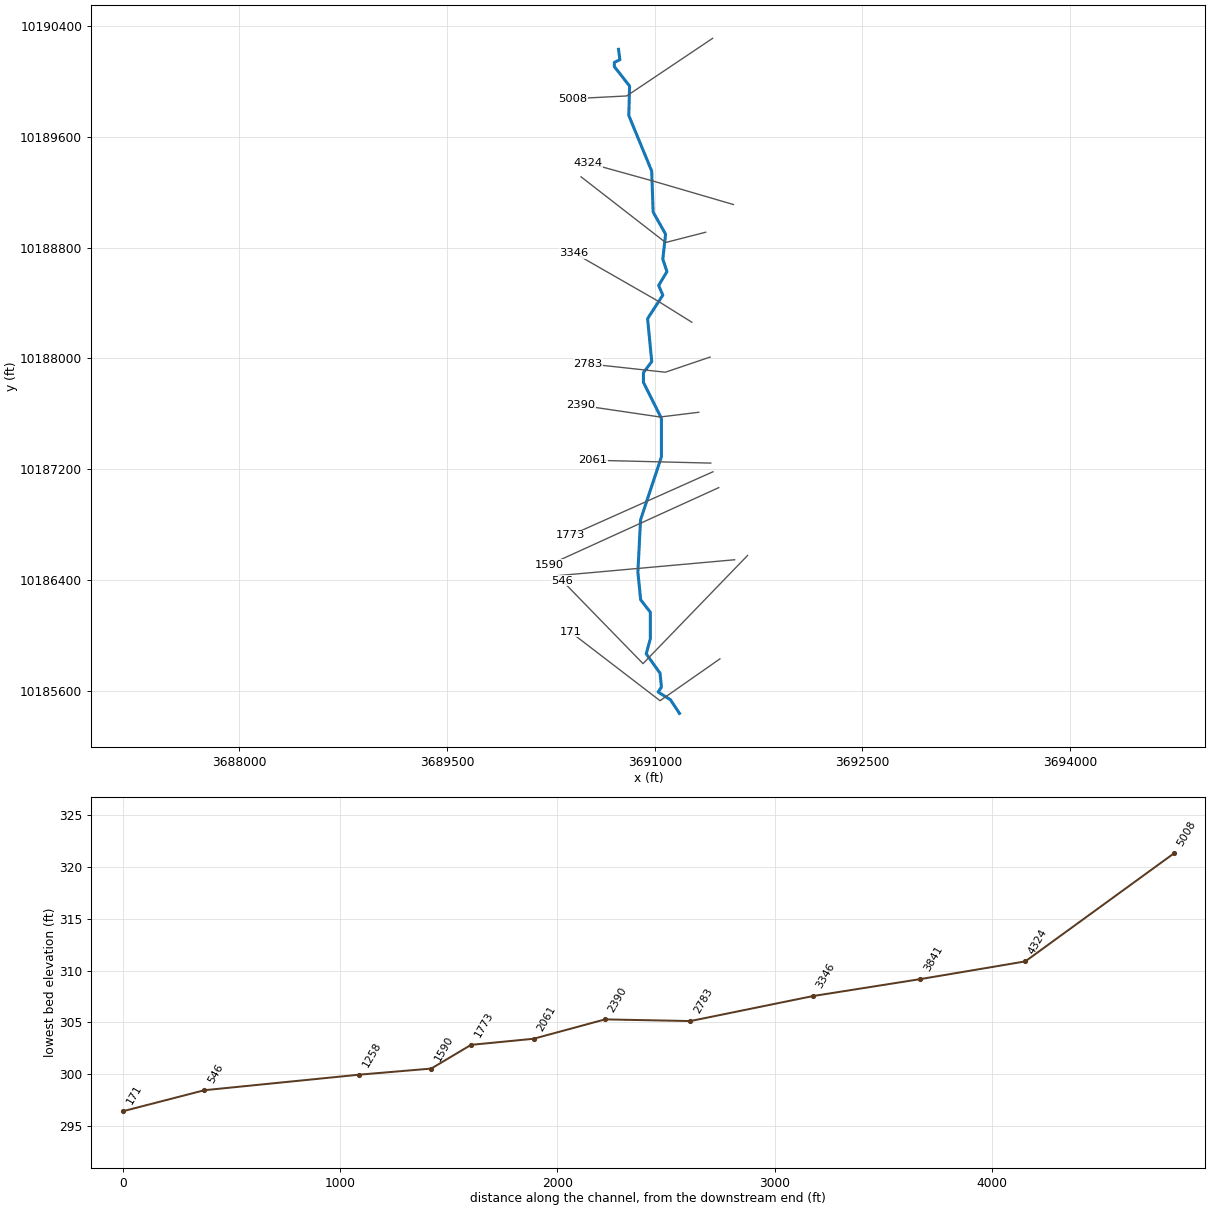
--- CCLC 080.prj (project) ---

Proj Title=CCLC 080 Base Level Engineering
Current Plan=p01
Default Exp/Contr=0.3,0.1
English Units
Geom File=g01
Flow File=f01
Flow File=f02
Plan File=p01
Y Axis Title=Elevation
X Axis Title(PF)=Main Channel Distance
X Axis Title(XS)=Station
BEGIN DESCRIPTION:
CCLC 080
END DESCRIPTION:
DSS Export Rating Curves= 0
DSS Export Rating Curve Sorted= 0
DSS Export Volume Flow Curves= 0
DXF OffsetX= 0
DXF OffsetY= 0
DXF ScaleX= 1
DXF ScaleY= 10

--- CCLC 080.p01 (plan) ---

Plan Title=Multiple Run
Short Identifier=Multiple
Geom File=g01
Flow File=f01
Subcritical Flow
K Sum by GR= 0
Std Step Tol= 0.01
Critical Tol= 0.01
Num of Std Step Trials= 20
Max Error Tol= 0.3
Flow Tol Ratio= 0.001
Split Flow NTrial= 30
Split Flow Tol= 0.02
Split Flow Ratio= 0.02
Log Output Level= 0
Friction Slope Method= 1
Unsteady Friction Slope Method= 2
Unsteady Bridges Friction Slope Method= 1
Parabolic Critical Depth
Global Vel Dist=  1 , 1 , 1
Global Log Level= 0
CheckData=True
Encroach Param= -1, 0, 0, 0
BEGIN DESCRIPTION:
Multiple Run
END DESCRIPTION:

--- CCLC 080.f01 (steady flow) ---

Flow Title=Multiple
Program Version=4.10
Number of Profiles= 7
Profile Names=10-year,25-year,50-year,1pct_min,100-year,1pct_plu,500-year
River Rch & RM=CCLC 080,Reach-1         ,5008
     661     903    1226     548    1654    4995    3113
Boundary for River Rch & Prof#=CCLC 080,Reach-1         , 1
Up Type= 0
Dn Type= 3
Dn Slope=0.005
Boundary for River Rch & Prof#=CCLC 080,Reach-1         , 2
Up Type= 0
Dn Type= 3
Dn Slope=0.005
Boundary for River Rch & Prof#=CCLC 080,Reach-1         , 3
Up Type= 0
Dn Type= 3
Dn Slope=0.005
Boundary for River Rch & Prof#=CCLC 080,Reach-1         , 4
Up Type= 0
Dn Type= 3
Dn Slope=0.005
Boundary for River Rch & Prof#=CCLC 080,Reach-1         , 5
Up Type= 0
Dn Type= 3
Dn Slope=0.005
Boundary for River Rch & Prof#=CCLC 080,Reach-1         , 6
Up Type= 0
Dn Type= 3
Dn Slope=0.005
Boundary for River Rch & Prof#=CCLC 080,Reach-1         , 7
Up Type= 0
Dn Type= 3
Dn Slope=0.005
DSS Import GetInterval= 0
DSS Import GetPeak= 0
DSS Import FillOption= 0

--- CCLC 080.f02 (steady flow) ---

Flow Title=Orig_BLE_Flows
Program Version=4.10
Number of Profiles= 7
Profile Names=10-year,25-year,50-year,1pct_min,100-year,1pct_plu,500-year
River Rch & RM=CCLC 080,Reach-1         ,5008
     661     885    1066     421    1272    3842    1810
Boundary for River Rch & Prof#=CCLC 080,Reach-1         , 1
Up Type= 0
Dn Type= 3
Dn Slope=0.005
Boundary for River Rch & Prof#=CCLC 080,Reach-1         , 2
Up Type= 0
Dn Type= 3
Dn Slope=0.005
Boundary for River Rch & Prof#=CCLC 080,Reach-1         , 3
Up Type= 0
Dn Type= 3
Dn Slope=0.005
Boundary for River Rch & Prof#=CCLC 080,Reach-1         , 4
Up Type= 0
Dn Type= 3
Dn Slope=0.005
Boundary for River Rch & Prof#=CCLC 080,Reach-1         , 5
Up Type= 0
Dn Type= 3
Dn Slope=0.005
Boundary for River Rch & Prof#=CCLC 080,Reach-1         , 6
Up Type= 0
Dn Type= 3
Dn Slope=0.005
Boundary for River Rch & Prof#=CCLC 080,Reach-1         , 7
Up Type= 0
Dn Type= 3
Dn Slope=0.005
DSS Import GetInterval= 0
DSS Import GetPeak= 0
DSS Import FillOption= 0

--- CCLC 080.g01 (geometry) ---

Geom Title=Existing Conditions
Program Version=4.10

River Reach=CCLC 080        ,Reach-1
Reach XY= 30
      3690738.23     10190231.84      3690748.23     10190156.84
      3690708.23     10190136.84      3690708.23     10190106.84
      3690818.23     10189966.84      3690812.68     10189753.33
      3690977.97     10189352.77      3690988.23     10189056.84
      3691078.23     10188896.84      3691058.23     10188716.84
      3691088.23     10188626.84      3691028.23     10188526.84
      3691058.23     10188456.84      3690948.23     10188286.84
      3690978.23     10187976.84      3690918.23     10187896.84
      3690918.23     10187826.84      3691048.23     10187566.84
      3691048.23     10187289.59      3690897.32     10186833.87
      3690878.23     10186456.84      3690898.23     10186256.84
      3690968.23     10186166.84      3690968.23     10185976.84
      3690938.23     10185866.84      3691038.23     10185726.84
      3691048.23     10185626.84      3691024.45     10185590.63
       3691113.1     10185535.39      3691178.23     10185436.84

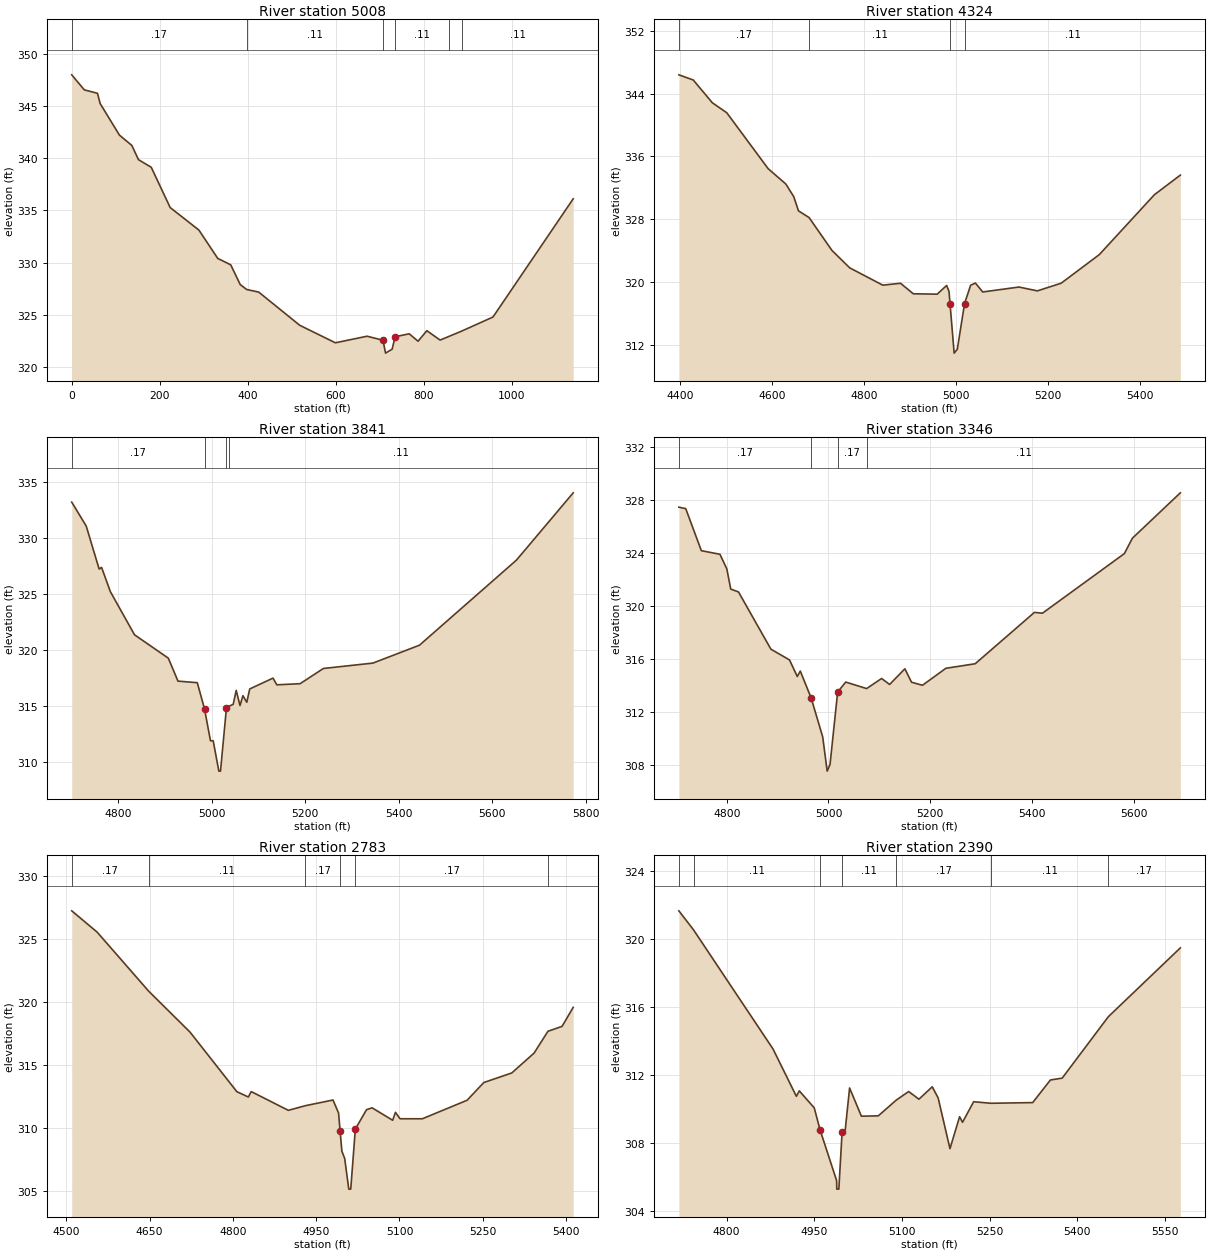
Type RM Length L Ch R = 1 ,5008    ,684,684,684
BEGIN DESCRIPTION:
CCLC 080 8.0
END DESCRIPTION:
XS GIS Cut Line= 3
      3691417.85     10190311.07      3690797.37     10189895.07
      3690405.94     10189874.88
#Sta/Elev= 30
       0     348    28.5  346.56    58.5  346.23    64.5  345.25   108.4  342.22
   136.6  341.23   151.6  339.87   180.6  339.14   223.6  335.28   288.9  333.12
   331.6  330.41   361.2  329.79   382.7   327.9   397.3  327.43   424.7  327.18
   517.8     324   598.8  322.32   670.8  322.95   706.8  322.57   712.8  321.33
   727.8  321.71   734.4   322.9   766.6  323.18   786.6  322.47   806.6  323.48
   836.7  322.58   856.7  322.93   886.7  323.46   956.8  324.79    1139  336.12
#Mann= 6 ,-1 , 0
       0     .17       0   397.3     .11       0   706.8     .07       0
   734.4     .11       0   856.7     .11       0   886.7     .11       0
Bank Sta=706.8,734.4
XS Rating Curve= 0 ,0
Exp/Cntr=0.3,0.1

Type RM Length L Ch R = 1 ,4324    ,483,483,483
BEGIN DESCRIPTION:
CCLC 080 7.0
END DESCRIPTION:
XS GIS Cut Line= 3
      3691567.88     10189111.06      3690988.83     10189280.38
      3690517.83     10189411.08
#Sta/Elev= 30
  4396.7   346.4    4428  345.74  4469.7  342.83  4500.9  341.57  4591.1  334.43
  4629.7  332.47  4646.8  330.87  4657.2  329.05  4680.3  328.19  4730.1     324
  4768.7  321.78  4840.8  319.57  4879.5  319.81  4907.2  318.47  4959.3  318.42
  4979.8  319.53    4985  318.77 4987.25 317.195  4996.2   310.9  5003.1   311.4
  5018.9  317.23  5032.1  319.56  5042.5  319.84  5058.4   318.7  5137.3  319.33
  5177.4  318.84  5229.3  319.82  5312.4  323.47  5432.2   331.1  5488.8  333.61
#Mann= 4 ,-1 , 0
  4396.7     .17       0  4680.3     .11       0 4987.25     .07       0
  5018.9     .11       0
Bank Sta=4987.25,5018.9
XS Rating Curve= 0 ,0
Exp/Cntr=0.3,0.1

Type RM Length L Ch R = 1 ,3841    ,495,495,495
BEGIN DESCRIPTION:
CCLC 080 6.0
END DESCRIPTION:
XS GIS Cut Line= 3
      3691367.87     10188911.08      3691078.23     10188836.84
      3690467.81      10189311.1
#Sta/Elev= 30
    4701  333.22    4732  331.08  4759.6  327.24  4764.8  327.39  4783.6  325.22
  4835.2  321.37  4907.5  319.28  4928.1  317.23  4969.4  317.09 4984.83314.7529
  4997.6   311.9  5003.4   311.9  5015.5  309.19    5019  309.19  5031.7  314.83
  5036.8  314.98  5046.2  315.16  5052.6   316.4  5060.7  315.05    5067  315.93
  5075.2  315.34  5081.5  316.53  5131.3   317.5  5139.4   316.9  5189.2     317
    5239  318.36  5344.9  318.84  5444.4  320.44  5651.7  328.04    5773  334.05
#Mann= 4 ,-1 , 0
    4701     .17       0 4984.83     .09       0  5031.7     .17       0
  5036.8     .11       0
Bank Sta=4984.83,5031.7
XS Rating Curve= 0 ,0
Exp/Cntr=0.3,0.1

Type RM Length L Ch R = 1 ,3346    ,563,563,563
BEGIN DESCRIPTION:
CCLC 080 5.0
END DESCRIPTION:
XS GIS Cut Line= 3
      3691267.82     10188261.09      3691018.23     10188416.84
      3690417.82     10188761.09
#Sta/Elev= 30
  4705.8  327.44  4719.3  327.33    4750  324.16  4786.6  323.89  4800.1  322.79
  4807.8  321.27  4823.1  321.05  4886.8  316.74  4923.4  315.93  4938.7  314.68
  4944.6  315.09  4965.9  313.07  4988.7  310.13  4997.5  307.55  5003.1  308.05
  5018.1  313.51    5034  314.26  5075.1  313.77  5104.5  314.53  5120.3  314.08
  5150.3  315.26  5163.4  314.25    5185  314.02    5231   315.3  5288.6  315.64
  5405.1  319.51  5420.9  319.45    5582  323.94  5597.8   325.1  5692.1  328.52
#Mann= 4 ,-1 , 0
  4705.8     .17       0  4965.9     .09       0  5018.1     .17       0
  5075.1     .11       0
Bank Sta=4965.9,5018.1
XS Rating Curve= 0 ,0
Exp/Cntr=0.3,0.1

Type RM Length L Ch R = 1 ,2783    ,393,393,393
BEGIN DESCRIPTION:
CCLC 080 4.0
END DESCRIPTION:
XS GIS Cut Line= 3
      3691399.53     10188009.59      3691076.64     10187900.22
      3690517.86     10187961.07
#Sta/Elev= 30
  4509.8  327.25  4555.5  325.56  4648.5  320.86  4722.7  317.62  4807.2  312.88
  4827.8  312.46    4833  312.89  4899.8   311.4  4930.7  311.77  4980.3  312.22
  4990.3  311.18 4993.02309.7877  4996.2  308.16  5001.3  307.58  5008.7  305.14
  5012.2  305.14  5020.5  309.91  5040.6  311.45  5050.7   311.6  5087.7  310.61
  5092.7  311.24    5101  310.73  5141.2  310.73  5221.7   312.2  5251.9  313.61
  5302.2  314.37  5342.4  315.95  5367.3  317.68  5392.7  318.07  5412.8  319.58
#Mann= 6 ,-1 , 0
  4509.8     .17       0  4648.5     .11       0  4930.7     .17       0
 4993.02     .09       0  5020.5     .17       0  5367.3     .11       0
Bank Sta=4993.02,5020.5
XS Rating Curve= 0 ,0
Exp/Cntr=0.3,0.1

Type RM Length L Ch R = 1 ,2390    ,329,329,329
BEGIN DESCRIPTION:
CCLC 080 3.0
END DESCRIPTION:
XS GIS Cut Line= 3
      3691317.84     10187611.07      3691038.23     10187576.84
      3690467.82     10187661.08
#Sta/Elev= 30
  4718.3  321.67  4743.4  320.55  4879.5  313.54  4919.4  310.76  4924.4  311.08
    4950  310.08  4960.1  308.77  4988.3   305.8  4988.6   305.3  4992.1   305.3
  4997.7  308.67  5002.7  308.67  5010.5  311.25  5030.7  309.59  5059.6  309.61
  5090.5  310.54  5111.6  311.04  5129.2  310.59    5152  311.32  5162.1  310.66
  5182.3  307.68  5198.8  309.56  5203.8  309.23  5222.8  310.44  5252.6  310.35
  5323.9  310.39  5354.2  311.72  5374.4  311.83  5453.3  315.44  5576.6  319.49
#Mann= 7 ,-1 , 0
  4718.3     .17       0  4743.4     .11       0  4960.1     .07       0
  4997.7     .11       0  5090.5     .17       0  5252.6     .11       0
  5453.3     .17       0
Bank Sta=4960.1,4997.7
XS Rating Curve= 0 ,0
Exp/Cntr=0.3,0.1

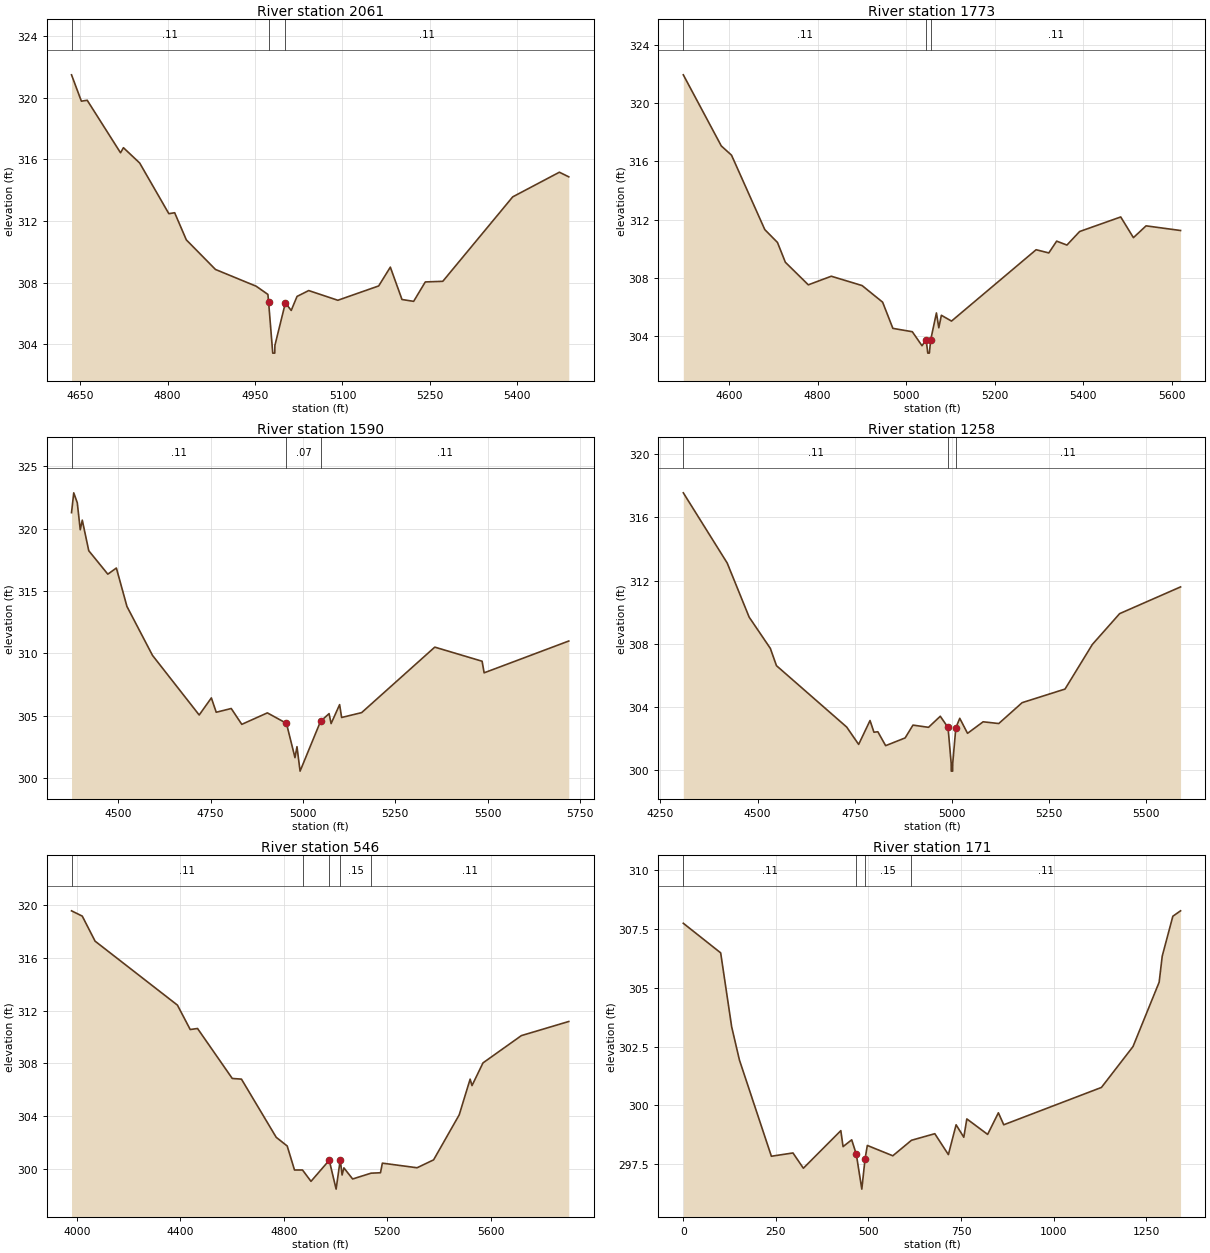
Type RM Length L Ch R = 1 ,2061    ,288,288,288
BEGIN DESCRIPTION:
CCLC 080 2.0
END DESCRIPTION:
XS GIS Cut Line= 2
      3691404.75     10187243.97      3690551.71     10187264.78
#Sta/Elev= 30
  4635.1  321.49    4652  319.78    4662  319.84  4719.2  316.43  4724.2  316.76
    4752  315.77  4802.1  312.48  4812.1  312.54  4832.1  310.78  4882.1  308.86
  4952.1  307.77  4972.1  307.24 4973.33306.7311  4980.4  303.43  4983.9  303.43
  4984.1  303.93  5002.1  306.69  5012.1   306.2  5022.1  307.11  5042.1  307.49
  5092.1  306.86  5162.2  307.79  5182.2  309.01  5202.2  306.91  5222.2  306.79
  5242.2  308.05  5272.2  308.09  5392.2  313.57  5472.3  315.17  5488.4  314.87
#Mann= 3 ,-1 , 0
  4635.1     .11       0 4973.33     .07       0  5002.1     .11       0
Bank Sta=4973.33,5002.1
XS Rating Curve= 0 ,0
Exp/Cntr=0.3,0.1

Type RM Length L Ch R = 1 ,1773    ,183,183,183
BEGIN DESCRIPTION:
Mapping XS 5d8e42c6
END DESCRIPTION:
XS GIS Cut Line= 2
      3691420.37     10187181.46      3690394.38     10186723.15
#Sta/Elev= 30
  4496.4  321.95  4582.2  317.07  4605.4  316.43  4680.6  311.32  4709.2  310.44
    4727  309.08  4778.9  307.53  4830.8  308.12  4900.4  307.48  4946.8  306.34
    4970  304.54  5013.9  304.31  5035.8  303.35  5045.2  303.75  5048.9  302.84
  5052.4  302.84 5055.53303.7591  5068.4   305.6  5073.8  304.58  5079.6  305.44
  5102.5  305.04  5293.7  309.94  5322.4  309.72  5340.1  310.53  5363.3  310.26
    5392  311.19  5484.9  312.19  5513.6  310.77  5542.2  311.58  5620.1  311.26
#Mann= 3 ,-1 , 0
  4496.4     .11       0  5045.2     .07       0 5055.53     .11       0
Bank Sta=5045.2,5055.53
XS Rating Curve= 0 ,0
Exp/Cntr=0.3,0.1

Type RM Length L Ch R = 1 ,1590    ,332,332,332
BEGIN DESCRIPTION:
Mapping XS 13247262
END DESCRIPTION:
XS GIS Cut Line= 2
      3691462.05     10187066.89      3690238.05     10186509.58
#Sta/Elev= 30
  4374.1  321.27  4380.1  322.86  4389.7  322.06  4397.7   319.9  4403.2  320.67
  4420.7  318.22  4472.3  316.34  4495.4  316.83    4524  313.75  4593.1  309.83
  4719.4  305.05  4752.3  306.42  4765.5  305.27  4806.1  305.57  4834.6   304.3
  4903.8  305.22  4955.4  304.38  4978.5  301.63  4983.9  302.51  4992.3  300.55
  5047.6  304.54  5070.7  305.16  5076.2  304.36  5099.2  305.88  5104.7  304.85
  5158.8  305.24  5356.6  310.49  5484.6  309.36  5490.1  308.43    5719  310.98
#Mann= 3 ,-1 , 0
  4374.1     .11       0  4955.4     .07       0  5047.6     .11       0
Bank Sta=4955.4,5047.6
XS Rating Curve= 0 ,0
Exp/Cntr=0.3,0.1

Type RM Length L Ch R = 1 ,1258    ,712,712,712
BEGIN DESCRIPTION:
Mapping XS f1ab69df
END DESCRIPTION:
XS GIS Cut Line= 2
      3691576.66     10186546.06      3690301.69     10186431.57
#Sta/Elev= 30
  4308.8  317.56  4421.8  313.12  4478.3   309.7  4532.9  307.72  4548.6  306.63
  4729.3  302.75  4760.2  301.65  4789.5  303.16  4799.6  302.42  4809.6  302.45
  4829.7  301.57  4879.9  302.06    4900  302.87  4940.1  302.73  4970.3  303.43
  4990.3  302.72  4998.4  300.46  4998.6  299.96  5002.1  299.96  5002.4  300.46
  5010.4   302.7  5020.5   303.3  5040.5  302.35  5080.7  303.08  5120.9  302.97
  5181.1  304.29  5291.5  305.15  5361.8  307.97  5432.1  309.92  5588.9  311.61
#Mann= 3 ,-1 , 0
  4308.8     .11       0  4990.3     .07       0  5010.4     .11       0
Bank Sta=4990.3,5010.4
XS Rating Curve= 0 ,0
Exp/Cntr=0.3,0.1

Type RM Length L Ch R = 1 ,546     ,375,375,375
BEGIN DESCRIPTION:
CCLC 080 1.0
END DESCRIPTION:
XS GIS Cut Line= 3
      3691670.37     10186577.28      3690915.18     10185796.05
      3690332.37     10186394.48
#Sta/Elev= 30
  3979.8  319.56  4021.3  319.16  4070.9  317.26  4389.2  312.41  4438.6  310.56
  4466.8  310.64  4601.1  306.85  4636.6   306.8  4770.9  302.39  4813.4  301.73
  4841.7  299.91  4872.6  299.91  4905.4  299.05  4975.9  300.65  5002.5  298.46
  5018.4  300.69  5025.6  299.53  5032.5  300.07  5066.4  299.23  5137.6  299.67
    5174   299.7  5181.2  300.43  5315.5  300.08  5379.3  300.68  5478.2  304.09
  5520.5   306.8  5527.7  306.31  5570.1  308.03  5718.6   310.1  5901.7  311.17
#Mann= 5 ,-1 , 0
  3979.8     .11       0  4872.6     .15       0  4975.9     .09       0
  5018.4     .15       0  5137.6     .11       0
Bank Sta=4975.9,5018.4
XS Rating Curve= 0 ,0
Exp/Cntr=0.3,0.1

Type RM Length L Ch R = 1 ,171     ,0,0,0
BEGIN DESCRIPTION:
CCLC 080 1.0
END DESCRIPTION:
XS GIS Cut Line= 3
      3691470.54     10185830.38      3691038.25     10185528.29
      3690389.81     10186025.69
#Sta/Elev= 30
       0  307.75   100.9  306.49   130.6  303.34   151.5  301.93   237.8  297.83
   296.1  297.97   324.2  297.32   425.3  298.92   431.4  298.24   454.7  298.53
   467.2  297.91     482  296.43   490.8  297.72   496.9  298.29   565.7  297.85
   616.1  298.51   679.1  298.79   715.8   297.9   736.6  299.17   757.4  298.64
   765.6  299.42   821.8  298.76   850.8  299.68   865.3  299.17  1129.1  300.76
  1214.3   302.5  1284.9  305.24  1293.2  306.35  1321.9  308.05  1342.7  308.28
#Mann= 4 ,-1 , 0
       0     .11       0   467.2     .09       0   490.8     .15       0
   616.1     .11       0
Bank Sta=467.2,490.8
XS Rating Curve= 0 ,0
Exp/Cntr=0.3,0.1

Chan Stop Cuts=-1
Use User Specified Reach Order=0
Composite Channel Slope=5