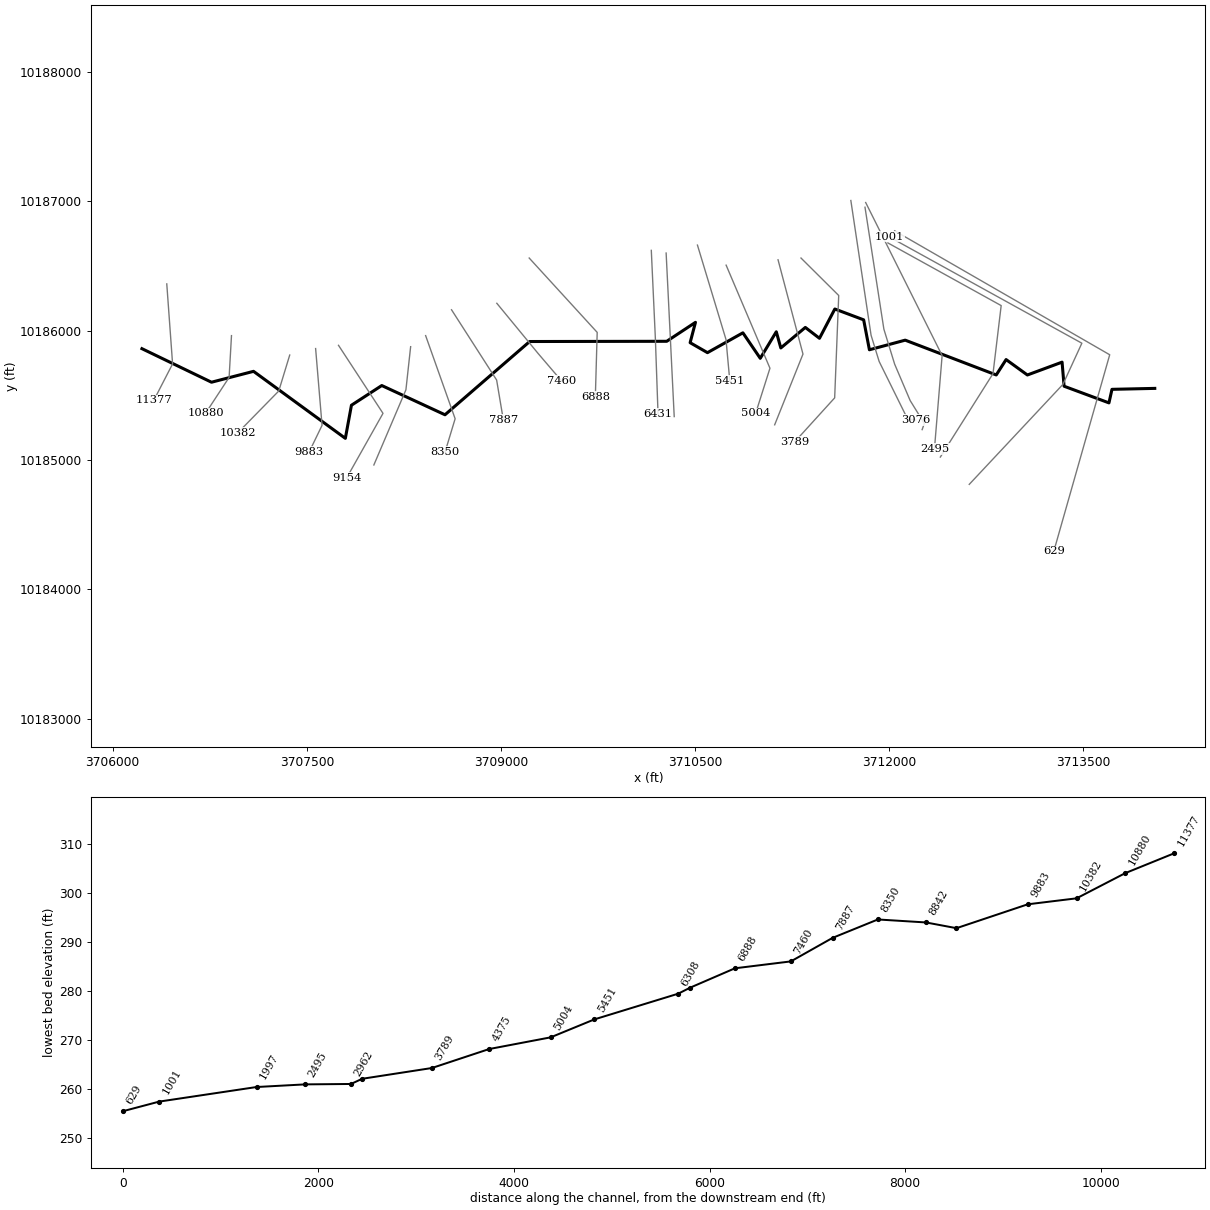
--- CCLC 084.prj (project) ---

Proj Title=CCLC 084 Base Level Engineering
Current Plan=p01
Default Exp/Contr=0.3,0.1
English Units
Geom File=g01
Flow File=f01
Flow File=f02
Plan File=p01
Y Axis Title=Elevation
X Axis Title(PF)=Main Channel Distance
X Axis Title(XS)=Station
BEGIN DESCRIPTION:
CCLC 084
END DESCRIPTION:
DSS Export Rating Curves= 0
DSS Export Rating Curve Sorted= 0
DSS Export Volume Flow Curves= 0
DXF OffsetX= 0
DXF OffsetY= 0
DXF ScaleX= 1
DXF ScaleY= 10

--- CCLC 084.p01 (plan) ---

Plan Title=Multiple Run
Short Identifier=Multiple
Geom File=g01
Flow File=f01
Subcritical Flow
K Sum by GR= 0
Std Step Tol= 0.01
Critical Tol= 0.01
Num of Std Step Trials= 20
Max Error Tol= 0.3
Flow Tol Ratio= 0.001
Split Flow NTrial= 30
Split Flow Tol= 0.02
Split Flow Ratio= 0.02
Log Output Level= 0
Friction Slope Method= 1
Unsteady Friction Slope Method= 2
Unsteady Bridges Friction Slope Method= 1
Parabolic Critical Depth
Global Vel Dist=  1 , 1 , 1
Global Log Level= 0
CheckData=True
Encroach Param= -1, 0, 0, 0
BEGIN DESCRIPTION:
Multiple Run
END DESCRIPTION:

--- CCLC 084.f01 (steady flow) ---

Flow Title=Multiple
Program Version=4.10
Number of Profiles= 7
Profile Names=10-year,25-year,50-year,1pct_min,100-year,1pct_plu,500-year
River Rch & RM=CCLC 084,Reach-1         ,11377
     848    1171    1603     721    2178    6577    4159
River Rch & RM=CCLC 084,Reach-1         ,6431
     939    1302    1787     805    2432    7345    4666
Boundary for River Rch & Prof#=CCLC 084,Reach-1         , 1
Up Type= 0
Dn Type= 3
Dn Slope=0.005
Boundary for River Rch & Prof#=CCLC 084,Reach-1         , 2
Up Type= 0
Dn Type= 3
Dn Slope=0.005
Boundary for River Rch & Prof#=CCLC 084,Reach-1         , 3
Up Type= 0
Dn Type= 3
Dn Slope=0.005
Boundary for River Rch & Prof#=CCLC 084,Reach-1         , 4
Up Type= 0
Dn Type= 3
Dn Slope=0.005
Boundary for River Rch & Prof#=CCLC 084,Reach-1         , 5
Up Type= 0
Dn Type= 3
Dn Slope=0.005
Boundary for River Rch & Prof#=CCLC 084,Reach-1         , 6
Up Type= 0
Dn Type= 3
Dn Slope=0.005
Boundary for River Rch & Prof#=CCLC 084,Reach-1         , 7
Up Type= 0
Dn Type= 3
Dn Slope=0.005
DSS Import GetInterval= 0
DSS Import GetPeak= 0
DSS Import FillOption= 0

--- CCLC 084.f02 (steady flow) ---

Flow Title=Orig_BLE_Flows
Program Version=4.10
Number of Profiles= 7
Profile Names=10-year,25-year,50-year,1pct_min,100-year,1pct_plu,500-year
River Rch & RM=CCLC 084,Reach-1         ,11377
     848    1148    1394     555    1675    5058    2418
River Rch & RM=CCLC 084,Reach-1         ,6431
     939    1276    1554     620    1871    5651    2713
Boundary for River Rch & Prof#=CCLC 084,Reach-1         , 1
Up Type= 0
Dn Type= 3
Dn Slope=0.005
Boundary for River Rch & Prof#=CCLC 084,Reach-1         , 2
Up Type= 0
Dn Type= 3
Dn Slope=0.005
Boundary for River Rch & Prof#=CCLC 084,Reach-1         , 3
Up Type= 0
Dn Type= 3
Dn Slope=0.005
Boundary for River Rch & Prof#=CCLC 084,Reach-1         , 4
Up Type= 0
Dn Type= 3
Dn Slope=0.005
Boundary for River Rch & Prof#=CCLC 084,Reach-1         , 5
Up Type= 0
Dn Type= 3
Dn Slope=0.005
Boundary for River Rch & Prof#=CCLC 084,Reach-1         , 6
Up Type= 0
Dn Type= 3
Dn Slope=0.005
Boundary for River Rch & Prof#=CCLC 084,Reach-1         , 7
Up Type= 0
Dn Type= 3
Dn Slope=0.005
DSS Import GetInterval= 0
DSS Import GetPeak= 0
DSS Import FillOption= 0

--- CCLC 084.g01 (geometry) ---

Geom Title=Existing Conditions
Program Version=4.10

River Reach=CCLC 084        ,Reach-1
Reach XY= 30
      3706225.94     10185860.22      3706763.43     10185600.83
       3707088.2     10185684.96      3707797.54     10185166.81
      3707844.62     10185422.93      3708078.97     10185575.19
      3708567.41     10185349.13      3709221.66     10185915.54
      3710280.72     10185917.28      3710502.58     10186063.81
      3710461.31     10185906.51      3710595.25     10185829.39
      3710868.97     10185982.75       3711003.2      10185785.6
      3711127.02     10185990.99      3711161.98     10185865.72
      3711351.35      10186024.5      3711460.62     10185940.37
      3711579.29     10186166.95      3711801.98      10186083.2
      3711846.49     10185851.69        3712123.     10185926.05
      3712826.38     10185656.97      3712902.51     10185775.93
      3713066.99     10185656.75      3713335.04     10185756.09
       3713350.6     10185569.85      3713697.19     10185441.07
      3713720.54     10185545.85       3714051.2     10185553.15

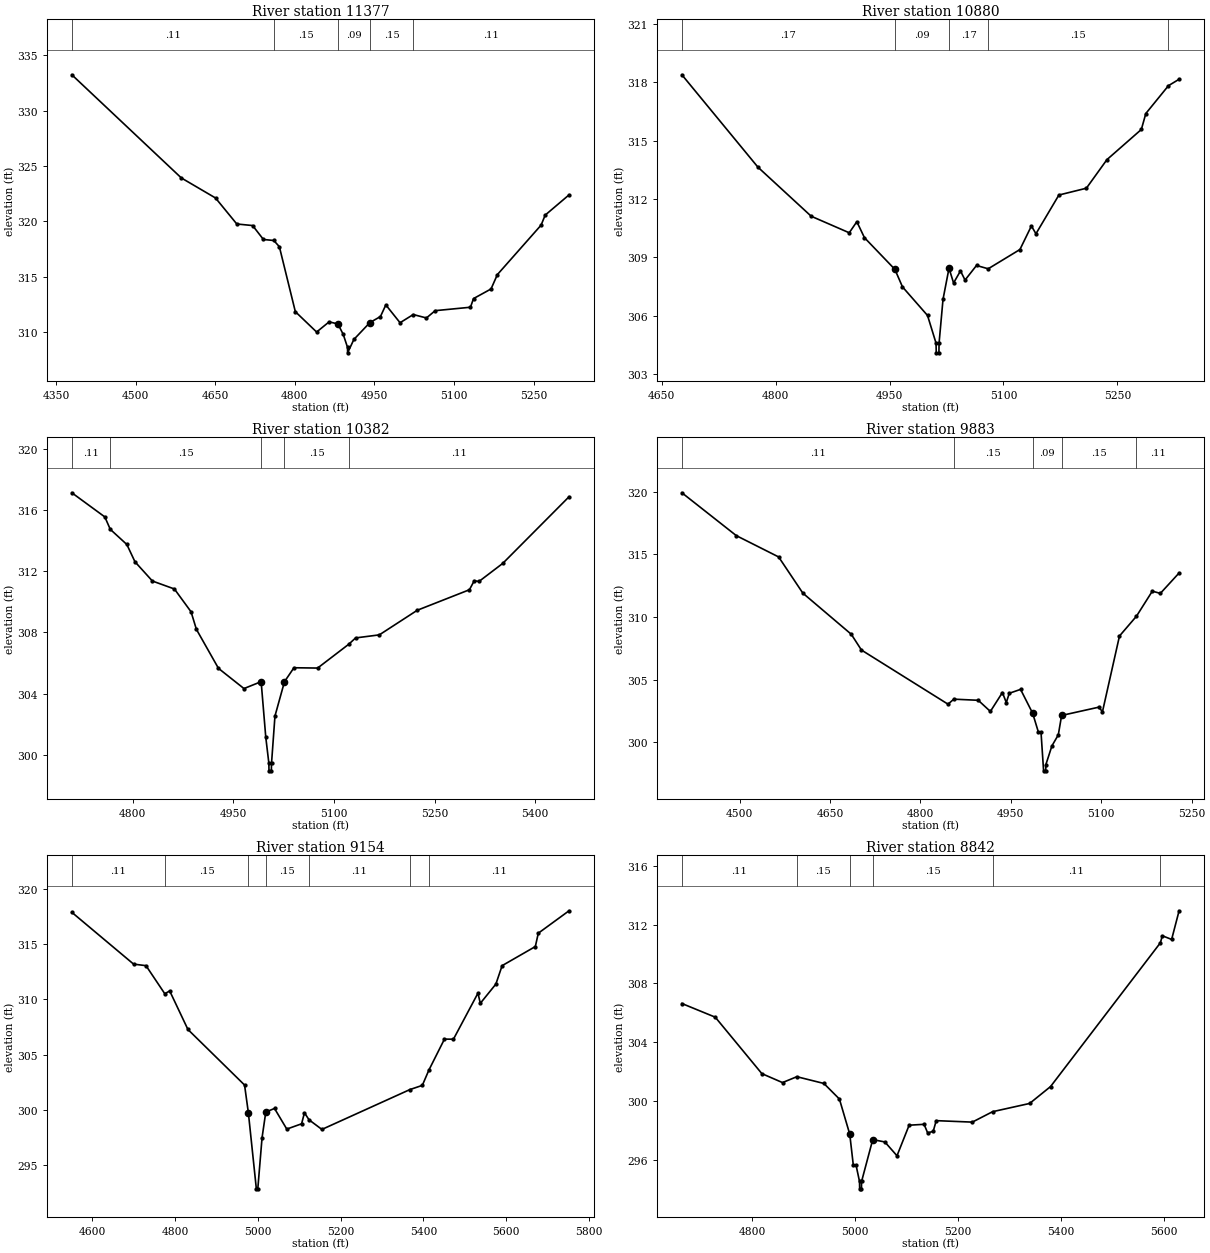
Type RM Length L Ch R = 1 ,11377   ,497,497,497
BEGIN DESCRIPTION:
CCLC 084 18.0
END DESCRIPTION:
XS GIS Cut Line= 3
      3706417.85     10186361.09      3706462.77     10185742.52
      3706317.84     10185461.04
#Sta/Elev= 30
  4379.8  333.25  4586.1  323.93  4650.5  322.12  4690.6  319.77  4720.4  319.63
  4740.8  318.37  4760.3  318.28  4770.8  317.72  4800.9  311.85    4841  310.01
  4864.6  310.93  4881.1  310.74  4891.2  309.79  4899.2  308.63  4899.4  308.13
  4911.2  309.34  4941.3  310.86  4961.3  311.41  4971.4  312.46  4998.2  310.85
  5023.1  311.59  5047.9  311.28  5064.4  311.94  5130.9  312.25  5136.6  313.03
  5169.6   313.9  5181.6   315.2    5264  319.67  5271.6  320.57  5316.6   322.4
#Mann= 5 ,-1 , 0
  4379.8     .11       0  4760.3     .15       0  4881.1     .09       0
  4941.3     .15       0  5023.1     .11       0
Bank Sta=4881.1,4941.3
XS Rating Curve= 0 ,0
Exp/Cntr=0.3,0.1

Type RM Length L Ch R = 1 ,10880   ,498,498,498
BEGIN DESCRIPTION:
CCLC 084 17.0
END DESCRIPTION:
XS GIS Cut Line= 3
      3706917.85     10185961.09      3706899.45     10185638.11
      3706717.83     10185361.04
#Sta/Elev= 30
  4676.5  318.39  4776.7  313.64  4846.8  311.12  4896.9  310.27  4906.9  310.84
  4916.9  310.02    4957  308.39    4967  307.49    5000  306.02  5011.2   304.6
  5011.5   304.1    5015   304.1  5015.2   304.6  5020.4  306.85  5028.3  308.45
  5034.3  307.69  5043.4  308.31  5049.4  307.84  5064.5  308.59  5079.9  308.42
  5121.7  309.41  5136.8  310.62  5142.8  310.22    5173  312.21  5209.2  312.56
  5236.3  314.03  5281.6  315.58  5287.5   316.4  5317.3  317.83  5331.3  318.16
#Mann= 5 ,-1 , 0
  4676.5     .17       0    4957     .09       0  5028.3     .17       0
  5079.9     .15       0  5317.3     .11       0
Bank Sta=4957,5028.3
XS Rating Curve= 0 ,0
Exp/Cntr=0.3,0.1

Type RM Length L Ch R = 1 ,10382   ,499,499,499
BEGIN DESCRIPTION:
CCLC 084 16.0
END DESCRIPTION:
XS GIS Cut Line= 3
      3707367.84     10185811.04      3707283.03     10185532.88
      3706967.88      10185211.1
#Sta/Elev= 30
  4709.2  317.13  4758.4  315.55  4766.5  314.74  4791.2  313.75  4803.3  312.62
  4829.3  311.36  4862.1  310.84  4886.9  309.35  4894.9   308.2  4927.8  305.65
  4965.8  304.33  4991.4  304.78  4998.3  301.15  5002.9  299.45  5003.1  298.95
  5006.6  298.95  5006.9  299.45    5012  302.53  5026.2  304.78  5040.3  305.69
  5075.6  305.67  5122.1  307.23  5132.2  307.64  5167.6  307.84  5224.2  309.45
  5301.9  310.79  5309.1  311.38  5316.1  311.33  5351.5  312.51  5450.4  316.87
#Mann= 5 ,-1 , 0
  4709.2     .11       0  4766.5     .15       0  4991.4     .09       0
  5026.2     .15       0  5122.1     .11       0
Bank Sta=4991.4,5026.2
XS Rating Curve= 0 ,0
Exp/Cntr=0.3,0.1

Type RM Length L Ch R = 1 ,9883    ,729,729,729
BEGIN DESCRIPTION:
CCLC 084 15.0
END DESCRIPTION:
XS GIS Cut Line= 3
      3707567.85     10185861.06      3707617.55     10185267.33
      3707517.85     10185061.06
#Sta/Elev= 30
  4404.2  319.92  4494.5   316.5  4564.7   314.8  4604.9  311.91  4685.2  308.63
  4702.1  307.37  4845.7  303.05  4855.4  303.45  4895.9  303.36    4916  302.47
    4936  303.98  4942.4  303.18  4947.4  303.92  4966.1  304.23  4986.2  302.32
  4995.6  300.83    5000  300.83  5004.3  297.73  5007.8  297.73  5008.1  298.23
  5018.1  299.72  5028.7   300.6  5034.2  302.15  5095.8  302.81    5102  302.45
  5130.2  308.49  5158.4  310.07  5184.7  312.07    5198  311.89  5229.1  313.52
#Mann= 5 ,-1 , 0
  4404.2     .11       0  4855.4     .15       0  4986.2     .09       0
  5034.2     .15       0  5158.4     .11       0
Bank Sta=4986.2,5034.2
XS Rating Curve= 0 ,0
Exp/Cntr=0.3,0.1

Type RM Length L Ch R = 1 ,9154    ,312,312,312
BEGIN DESCRIPTION:
Mapping XS 45e86836
END DESCRIPTION:
XS GIS Cut Line= 3
      3707744.68     10185886.09      3708088.44     10185360.03
      3707807.19     10184860.03
#Sta/Elev= 30
  4550.2  317.89  4699.5   313.2  4729.5  313.06  4774.9  310.52  4786.8  310.77
  4830.9  307.28  4967.8  302.25 4977.03299.7309  4996.3  292.85  4999.8  292.85
  5010.1  297.48  5019.1   299.8  5040.2  300.13  5069.9  298.26  5105.7  298.74
  5112.6  299.74  5123.7   299.1  5154.8  298.23  5367.6  301.84  5397.6  302.22
  5413.4   303.6  5451.1  306.41  5472.8   306.4  5532.1  310.57  5537.8  309.65
  5575.4  311.39  5590.5  313.06  5670.8  314.79    5678     316  5752.3  318.03
#Mann= 7 ,-1 , 0
  4550.2     .11       0  4774.9     .15       0 4977.03     .09       0
  5019.1     .15       0  5123.7     .11       0  5367.6     .15       0
  5413.4     .11       0
Bank Sta=4977.03,5019.1
XS Rating Curve= 0 ,0
Exp/Cntr=0.3,0.1

Type RM Length L Ch R = 1 ,8842    ,492,492,492
BEGIN DESCRIPTION:
CCLC 084 14.0
END DESCRIPTION:
XS GIS Cut Line= 3
      3708301.98     10185875.63      3708265.53     10185542.32
      3708017.86     10184961.08
#Sta/Elev= 30
  4663.2  306.63  4728.1   305.7  4818.7  301.86  4858.9  301.25  4886.8  301.65
  4939.4  301.19  4969.6  300.13  4989.7  297.74  4996.6  295.64  5001.9  295.64
  5008.7  294.52    5009  294.02  5012.5  294.02  5012.7  294.52  5034.4  297.37
    5058  297.21  5081.6  296.27  5105.2  298.35  5134.3  298.41  5141.2  297.83
    5152  297.93  5157.9  298.66  5228.1  298.56  5267.6  299.27  5339.6  299.83
  5380.3  300.98  5593.9  310.76  5597.7  311.24  5615.8  310.99  5630.3  312.94
#Mann= 6 ,-1 , 0
  4663.2     .11       0  4886.8     .15       0  4989.7     .09       0
  5034.4     .15       0  5267.6     .11       0  5593.9     .15       0
Bank Sta=4989.7,5034.4
XS Rating Curve= 0 ,0
Exp/Cntr=0.3,0.1

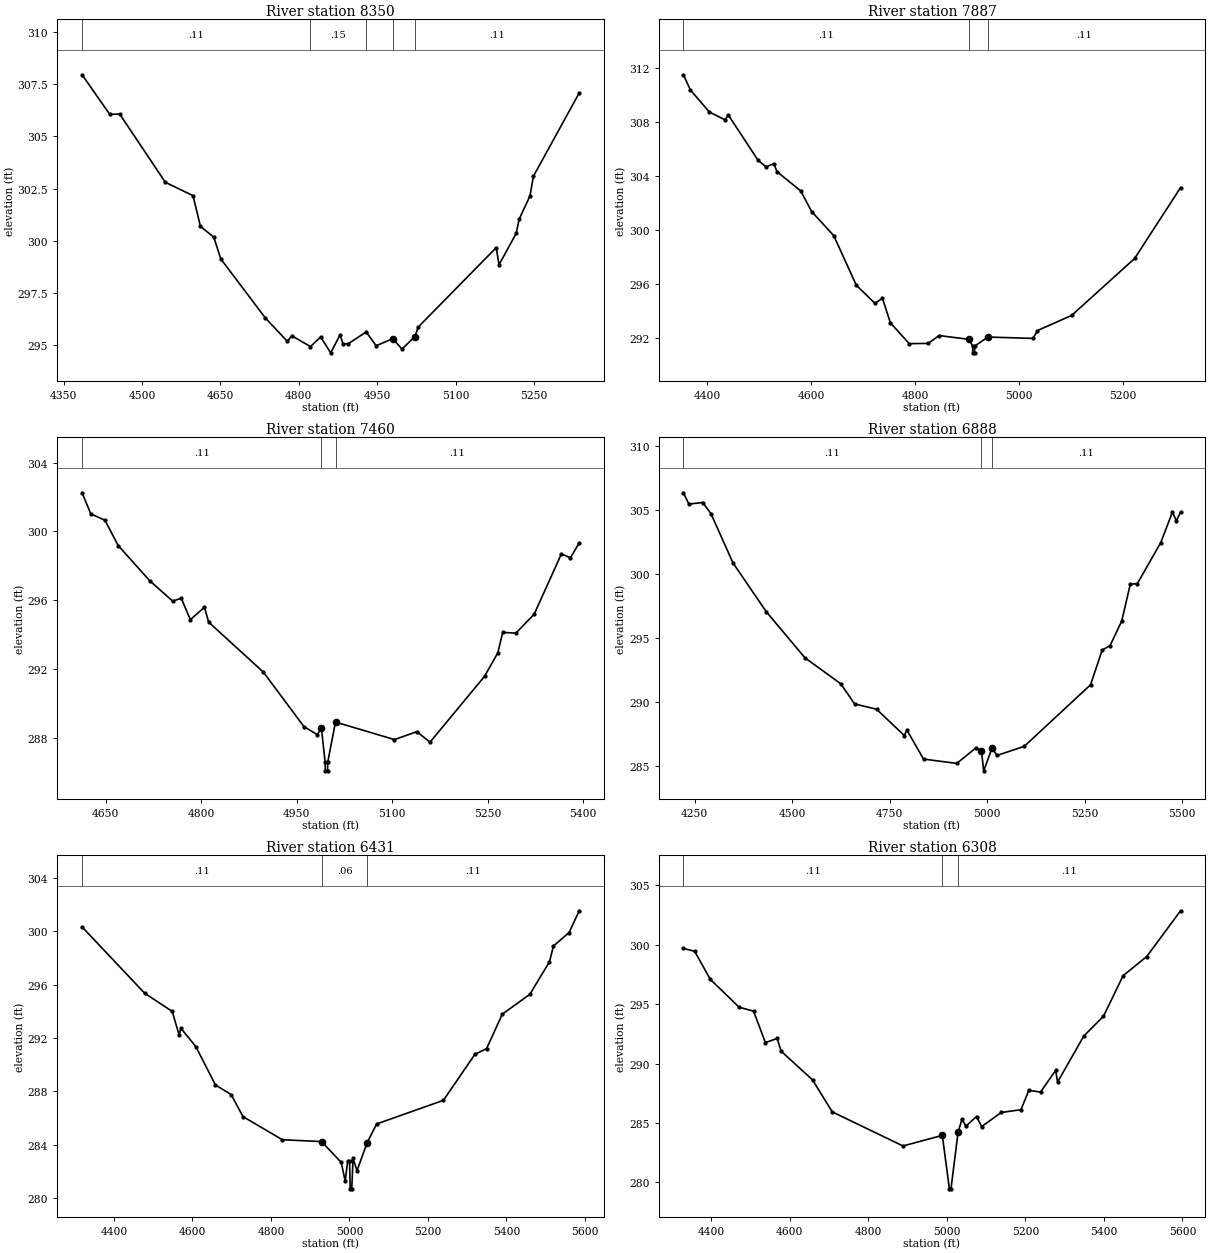
Type RM Length L Ch R = 1 ,8350    ,463,463,463
BEGIN DESCRIPTION:
CCLC 084 13.0
END DESCRIPTION:
XS GIS Cut Line= 3
      3708417.84     10185961.11      3708645.73     10185318.36
      3708567.85     10185061.05
#Sta/Elev= 30
  4385.4  307.95  4438.5  306.05  4457.3  306.07  4544.6   302.8  4597.6  302.16
  4611.7  300.69  4637.3  300.17  4650.7  299.13  4735.6  296.31    4778  295.18
  4786.4  295.45  4822.1  294.93  4841.7  295.39  4860.9  294.63    4879   295.5
  4884.3  295.06  4894.7  295.07  4928.8  295.63  4947.8  294.97  4979.6  295.31
  4997.2  294.81    5022  295.41  5028.1  295.86  5177.5  299.67  5182.8  298.85
  5215.7  300.35  5221.3  301.03  5242.1  302.15  5248.6  303.09  5336.2  307.08
#Mann= 5 ,-1 , 0
  4385.4     .11       0  4822.1     .15       0  4928.8     .11       0
  4979.6     .06       0    5022     .11       0
Bank Sta=4979.6,5022
XS Rating Curve= 0 ,0
Exp/Cntr=0.3,0.1

Type RM Length L Ch R = 1 ,7887    ,427,427,427
BEGIN DESCRIPTION:
CCLC 084 12.0
END DESCRIPTION:
XS GIS Cut Line= 3
      3708617.86     10186161.06      3708966.41     10185617.63
      3709017.84     10185311.12
#Sta/Elev= 30
  4354.4  311.47  4367.9  310.34  4404.3  308.71  4434.7  308.13  4440.6   308.5
  4498.1  305.13  4513.3  304.65  4528.5  304.88  4534.4  304.29    4580  302.87
  4601.2  301.33  4643.5  299.56    4687  295.88  4722.7  294.54  4737.3  294.91
  4752.5   293.1  4788.8  291.55  4825.2  291.57  4846.3  292.15  4903.8  291.87
  4910.8  291.37    4911  290.87  4914.5  290.87  4914.8  291.37  4940.1  292.04
  5026.9  291.94  5035.5  292.52  5101.2  293.64  5222.4  297.86  5310.8  303.11
#Mann= 3 , 0 , 0
  4354.4     .11       0  4903.8     .06       0  4940.1     .11       0
Bank Sta=4903.8,4940.1
XS Rating Curve= 0 ,0
Exp/Cntr=0.3,0.1

Type RM Length L Ch R = 1 ,7460    ,572,572,572
BEGIN DESCRIPTION:
CCLC 084 11.0
END DESCRIPTION:
XS GIS Cut Line= 3
      3708967.82     10186211.11      3709286.36     10185823.57
      3709467.85     10185611.08
#Sta/Elev= 30
    4613  302.25  4626.7  301.02  4648.9  300.65  4669.7  299.18  4719.2  297.13
  4755.4  295.94  4768.8  296.11  4783.1  294.86  4805.3  295.59  4811.8  294.72
  4897.8  291.81  4961.7  288.63  4982.6  288.17    4989  288.55  4994.9  286.56
  4995.2  286.06  4998.7  286.06  4998.9  286.56  5011.2   288.9  5103.8  287.88
  5138.9  288.34  5159.7  287.73  5245.3  291.56  5266.2  292.93  5273.9  294.12
  5294.7  294.08  5323.3  295.18  5366.1  298.69  5380.4  298.46  5394.1  299.34
#Mann= 3 , 0 , 0
    4613     .11       0    4989     .06       0  5011.2     .11       0
Bank Sta=4989,5011.2
XS Rating Curve= 0 ,0
Exp/Cntr=0.3,0.1

Type RM Length L Ch R = 1 ,6888    ,457,457,457
BEGIN DESCRIPTION:
CCLC 084 10.0
END DESCRIPTION:
XS GIS Cut Line= 3
      3709217.86     10186561.07       3709743.3     10185986.23
      3709729.07     10185490.23
#Sta/Elev= 30
  4221.2  306.37  4235.1  305.49  4270.8  305.61  4291.8  304.74  4348.5  300.88
  4433.7  297.08  4532.8  293.48  4624.8  291.45    4660  289.88  4716.7  289.46
  4787.6  287.41  4794.4  287.83    4837  285.57  4922.1  285.23  4971.4  286.44
  4985.6   286.2  4991.3  284.65  5012.8  286.44  5025.2  285.85  5095.2  286.56
  5265.3  291.37  5295.3  294.09  5315.3  294.43  5345.3  296.35  5367.3  299.23
  5385.3  299.27  5445.3  302.47  5475.4  304.86  5485.4  304.18  5496.2  304.86
#Mann= 3 , 0 , 0
  4221.2     .11       0  4985.6     .06       0  5012.8     .11       0
Bank Sta=4985.6,5012.8
XS Rating Curve= 0 ,0
Exp/Cntr=0.3,0.1

Type RM Length L Ch R = 1 ,6431    ,123,123,123
BEGIN DESCRIPTION:
CCLC 084 9.0
END DESCRIPTION:
XS GIS Cut Line= 3
      3710161.36     10186620.41      3710192.61     10185943.36
      3710213.42      10185355.4
#Sta/Elev= 30
  4319.1  300.32  4478.6  295.35  4548.7  293.99    4566  292.24    4571  292.72
  4608.7  291.36  4658.8  288.48  4698.8  287.76  4728.9  286.11    4829  284.38
  4929.1  284.24  4979.1  282.68  4989.2  281.27  4995.5  282.79  5000.3  282.79
  5001.9   280.7  5005.9   280.7  5009.2  282.98  5019.2  282.06 5045.27284.1698
  5069.2  285.56  5239.3  287.33  5319.4  290.77  5349.4  291.21  5389.4  293.79
  5459.4  295.27  5509.5  297.71  5519.5  298.89  5559.5   299.9  5585.2  301.53
#Mann= 3 , 0 , 0
  4319.1     .11       0  4929.1     .06       0 5045.27     .11       0
Bank Sta=4929.1,5045.27
XS Rating Curve= 0 ,0
Exp/Cntr=0.3,0.1

Type RM Length L Ch R = 1 ,6308    ,857,857,857
BEGIN DESCRIPTION:
Mapping XS 83889e93
END DESCRIPTION:
XS GIS Cut Line= 2
      3710275.94      10186599.6      3710338.39     10185335.04
#Sta/Elev= 30
  4329.1   299.7  4357.7  299.46  4397.7  297.09    4471  294.75  4507.8  294.42
  4537.9  291.77  4567.9  292.12  4577.9  291.05    4658  288.63  4708.1  285.94
  4888.3  283.07  4988.4  283.96  5006.5  279.46  5010.5  279.46  5028.5  284.21
  5038.5  285.33  5048.5  284.74  5075.5  285.55  5088.6   284.7  5138.6  285.89
  5188.7  286.12  5208.7  287.75  5238.7  287.61    5277  289.43    5282  288.45
  5348.9  292.33  5398.9  293.99    5449  297.41  5509.1  299.02  5595.2  302.87
#Mann= 3 , 0 , 0
  4329.1     .11       0  4988.4     .06       0  5028.5     .11       0
Bank Sta=4988.4,5028.5
XS Rating Curve= 0 ,0
Exp/Cntr=0.3,0.1

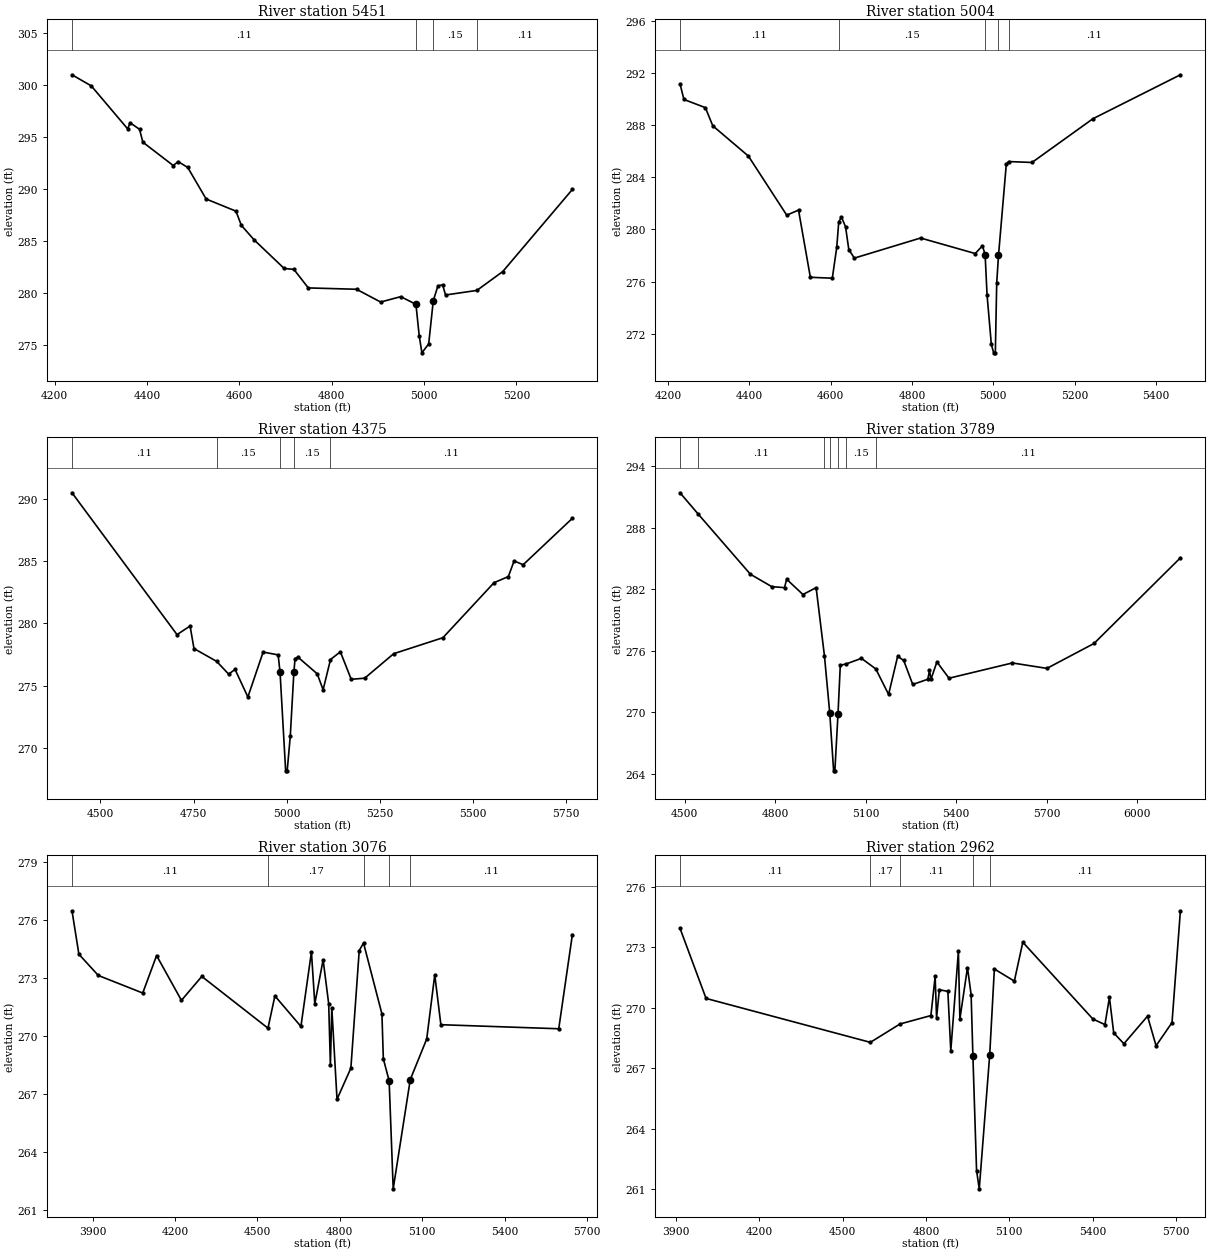
Type RM Length L Ch R = 1 ,5451    ,447,447,447
BEGIN DESCRIPTION:
CCLC 084 8.0
END DESCRIPTION:
XS GIS Cut Line= 3
      3710517.85     10186661.09      3710738.45      10185931.1
      3710767.85     10185611.04
#Sta/Elev= 30
  4237.4  300.98  4279.2  299.91    4358  295.77  4363.2  296.36  4383.7  295.73
  4390.9  294.49  4456.8  292.24  4467.3  292.62  4488.1  292.06    4528  289.02
  4592.6  287.85  4604.3  286.48  4632.1  285.08  4697.1  282.33    4718  282.25
  4749.3  280.46  4853.8  280.33    4906   279.1  4949.6  279.62  4982.5  278.88
  4989.6  275.84  4995.4  274.21  5010.1  275.07  5020.1  279.24  5030.2  280.66
  5040.2  280.76  5046.7  279.78  5114.5  280.22  5170.7  282.04  5321.4  289.94
#Mann= 4 ,-1 , 0
  4237.4     .11       0  4982.5     .09       0  5020.1     .15       0
  5114.5     .11       0
Bank Sta=4982.5,5020.1
XS Rating Curve= 0 ,0
Exp/Cntr=0.3,0.1

Type RM Length L Ch R = 1 ,5004    ,629,629,629
BEGIN DESCRIPTION:
CCLC 084 7.0
END DESCRIPTION:
XS GIS Cut Line= 3
      3710739.48     10186505.87      3711078.03     10185708.99
      3710967.84     10185361.03
#Sta/Elev= 30
  4229.5  291.16  4239.1  289.96  4291.9  289.33  4310.1  287.94  4397.7  285.62
    4492  281.09    4521  281.48  4550.1  276.33  4604.1  276.26    4615  278.62
  4619.9  280.56  4626.5  280.95  4636.7   280.2  4644.7  278.45  4658.4   277.8
  4821.2  279.34  4955.7  278.15  4973.5  278.75    4980278.0522  4984.8  274.95
  4995.3  271.18    5001  270.54  5005.1  270.54  5008.5  275.89 5012.88278.0027
  5032.1  285.01  5037.7   285.2  5095.3  285.13  5245.1  288.48  5460.3  291.85
#Mann= 5 ,-1 , 0
  4229.5     .11       0  4619.9     .15       0    4980     .09       0
 5012.88     .15       0  5037.7     .11       0
Bank Sta=4980,5012.88
XS Rating Curve= 0 ,0
Exp/Cntr=0.3,0.1

Type RM Length L Ch R = 1 ,4375    ,586,586,586
BEGIN DESCRIPTION:
Mapping XS 4888ccbb
END DESCRIPTION:
XS GIS Cut Line= 3
      3711140.52     10186547.53      3711333.23     10185818.36
      3711114.49     10185271.49
#Sta/Elev= 30
  4423.7  290.48  4705.6  279.09  4740.7  279.78  4751.1  277.97    4812  276.94
  4844.1  275.92  4861.5  276.29  4895.8  274.08  4936.8  277.69  4977.1  277.46
  4982.2  276.06  4997.2  268.15  5001.3  268.15  5009.6  270.92 5019.37276.1107
  5022.5  277.17  5030.3  277.28    5082  275.94  5097.8  274.66  5117.6  277.09
  5144.1  277.71  5173.2   275.5  5209.3  275.59  5287.4  277.56  5419.3  278.84
  5556.6  283.26    5595  283.75  5610.5  285.01  5634.7   284.7  5766.9  288.43
#Mann= 5 ,-1 , 0
  4423.7     .11       0    4812     .15       0  4982.2     .09       0
 5019.37     .15       0  5117.6     .11       0
Bank Sta=4982.2,5019.37
XS Rating Curve= 0 ,0
Exp/Cntr=0.3,0.1

Type RM Length L Ch R = 1 ,3789    ,713,713,713
BEGIN DESCRIPTION:
CCLC 084 6.0
END DESCRIPTION:
XS GIS Cut Line= 4
      3711317.88     10186561.04      3711609.28     10186271.49
      3711578.03     10185479.82       3711271.8     10185142.45
#Sta/Elev= 30
  4484.7  291.41  4544.4  289.35    4718  283.46  4788.7  282.25  4831.1  282.15
  4838.2  282.97  4892.2  281.48  4935.9  282.15  4963.5  275.49 4981.09269.8969
  4993.9  264.27    4998  264.27 5008.47269.8438    5016  274.58  5035.2   274.7
  5086.1  275.25  5133.6  274.22  5176.1  271.73  5206.2  275.45  5226.2  275.04
  5256.2   272.7  5306.2  273.21  5311.6  274.07  5316.6  273.21  5336.3   274.9
  5376.3  273.31  5586.4   274.8  5700.9  274.27    5857   276.7  6143.4  285.06
#Mann= 7 ,-1 , 0
  4484.7     .17       0  4544.4     .11       0  4963.5     .17       0
 4981.09     .09       0 5008.47     .17       0  5035.2     .15       0
  5133.6     .11       0
Bank Sta=4981.09,5008.47
XS Rating Curve= 0 ,0
Exp/Cntr=0.3,0.1

Type RM Length L Ch R = 1 ,3076    ,114,114,114
BEGIN DESCRIPTION:
Mapping XS 7c255c7b
END DESCRIPTION:
XS GIS Cut Line= 5
      3711703.02     10187005.88      3711859.28      10185964.2
      3711921.78     10185761.07      3712140.53     10185318.36
      3712203.11     10185308.62
#Sta/Elev= 30
  3824.3  276.47  3849.4  274.22  3920.2  273.12    4082  272.21  4132.5  274.15
    4223  271.83  4297.2  273.07  4538.3  270.39  4563.5  272.06  4658.3  270.48
  4696.6  274.33  4708.9  271.65  4739.2  273.93  4759.5  271.65  4765.7  268.46
  4770.8  271.45  4789.8  266.71  4840.3  268.32  4870.7  274.41  4886.4   274.8
  4953.4  271.13  4958.6   268.8  4979.7267.6677  4994.5  262.07  5056.7  267.73
  5116.6  269.83  5145.9  273.15  5168.2  270.57  5597.6  270.36  5647.3  275.24
#Mann= 5 ,-1 , 0
  3824.3     .11       0  4538.3     .17       0  4886.4     .11       0
  4979.7     .06       0  5056.7     .11       0
Bank Sta=4979.7,5056.7
XS Rating Curve= 0 ,0
Exp/Cntr=0.3,0.1

Type RM Length L Ch R = 1 ,2962    ,467,467,467
BEGIN DESCRIPTION:
Mapping XS dd1a8113
END DESCRIPTION:
XS GIS Cut Line= 6
       3711812.4     10186953.79      3711958.23     10186011.07
      3712041.57     10185740.24      3712161.36     10185458.99
      3712270.73      10185281.9      3712253.95     10185234.31
#Sta/Elev= 30
  3914.7  273.94  4008.5  270.46    4600  268.28  4706.5  269.19    4818  269.61
  4833.3  271.55  4838.4   269.5  4848.4  270.89  4879.1  270.81  4889.6  267.86
    4917  272.79  4922.3  269.43  4949.7  271.99  4962.8  270.65  4969.2267.6205
  4982.4  261.92  4992.1  261.01 5029.63267.6393  5046.5  271.92  5118.4  271.32
  5148.9  273.25  5401.1  269.44  5444.6  269.16  5460.8  270.51  5476.2  268.75
  5512.9  268.21    5598  269.58  5628.7  268.11  5686.1  269.26  5716.3  274.81
#Mann= 5 ,-1 , 0
  3914.7     .11       0    4600     .17       0  4706.5     .11       0
  4969.2     .06       0 5029.63     .11       0
Bank Sta=4969.2,5029.63
XS Rating Curve= 0 ,0
Exp/Cntr=0.3,0.1

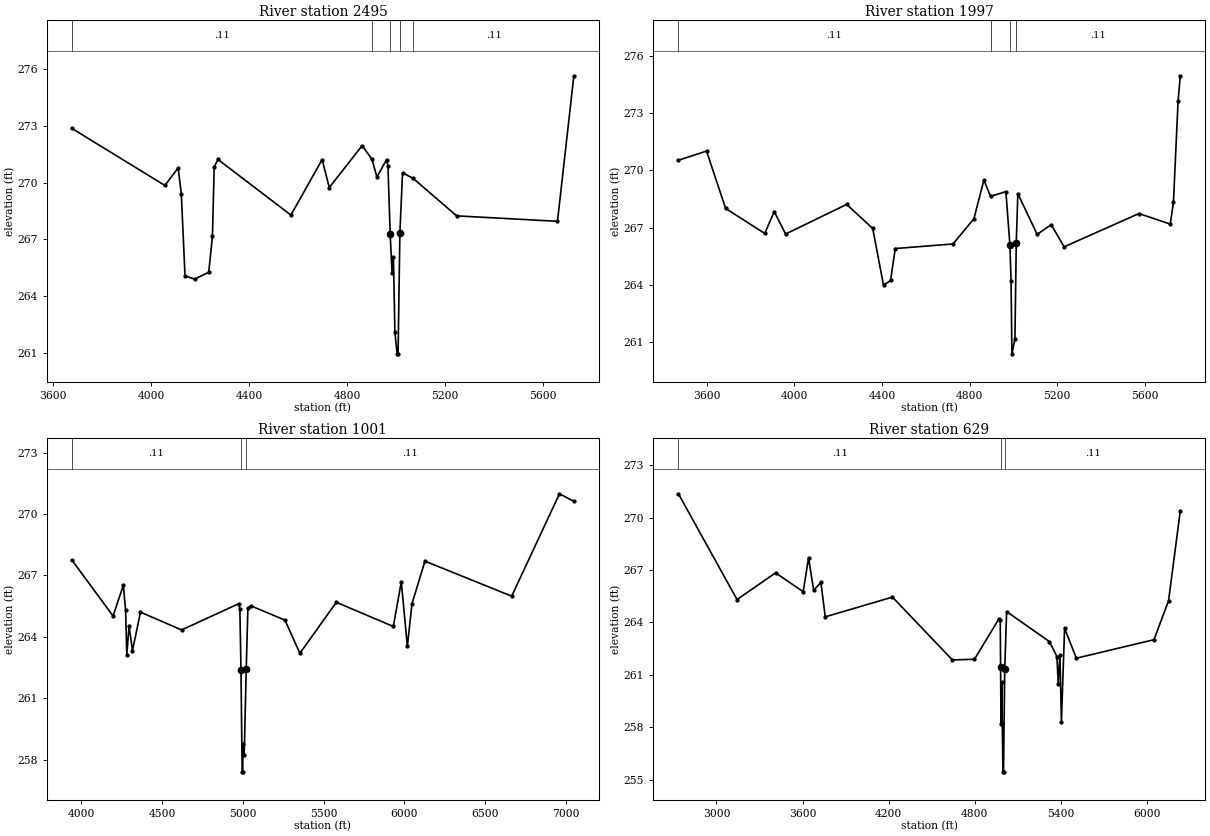
Type RM Length L Ch R = 1 ,2495    ,498,498,498
BEGIN DESCRIPTION:
CCLC 084 4.0
END DESCRIPTION:
XS GIS Cut Line= 3
      3711817.62     10186990.22      3712408.26     10185806.95
      3712348.97     10185084.48
#Sta/Elev= 30
  3677.5  272.87  4056.6  269.85  4110.7  270.78  4123.6  269.42  4138.7  265.06
  4177.9  264.89  4235.4  265.25  4250.6  267.15  4257.7  270.82  4272.9  271.23
  4570.7  268.28    4698  271.22  4727.2  269.74  4861.3  271.96  4901.1  271.24
  4921.7   270.3  4960.9  271.22  4966.5  270.86 4975.82267.2598  4983.3  265.19
  4988.8  266.07  4994.9  262.09  5003.8  260.93  5007.9  260.93 5015.23267.3206
    5026  270.52  5069.9  270.22  5246.7  268.24  5658.1  267.95  5724.9  275.66
#Mann= 5 ,-1 , 0
  3677.5     .11       0  4901.1     .15       0 4975.82     .09       0
 5015.23     .15       0  5069.9     .11       0
Bank Sta=4975.82,5015.23
XS Rating Curve= 0 ,0
Exp/Cntr=0.3,0.1

Type RM Length L Ch R = 1 ,1997    ,996,996,996
BEGIN DESCRIPTION:
CCLC 084 3.0
END DESCRIPTION:
XS GIS Cut Line= 4
      3711989.44     10186677.76      3712864.48     10186193.36
      3712801.38      10185667.2      3712394.43     10185022.14
#Sta/Elev= 30
  3469.9  270.52  3598.4     271  3685.4     268  3864.1  266.69  3907.6  267.83
  3959.6  266.66  4238.5  268.21  4357.6  266.95  4406.8  263.98  4438.9  264.23
  4460.6   265.9  4724.2  266.14  4819.8  267.46  4865.2  269.48  4895.9  268.63
  4965.9  268.88  4984.3  266.08  4989.4  264.21  4993.5  260.39  5007.2  261.17
 5013.17266.1798  5020.5  268.77  5108.7  266.64  5172.8  267.15  5231.9  265.99
  5573.6  267.73  5716.7  267.18  5731.3  268.31  5752.5  273.63  5762.7  274.94
#Mann= 4 ,-1 , 0
  3469.9     .11       0  4895.9     .15       0  4984.3     .09       0
 5013.17     .11       0
Bank Sta=4984.3,5013.17
XS Rating Curve= 0 ,0
Exp/Cntr=0.3,0.1

Type RM Length L Ch R = 1 ,1001    ,372,372,372
BEGIN DESCRIPTION:
CCLC 084 2.0
END DESCRIPTION:
XS GIS Cut Line= 4
      3712617.85     10184811.07       3713341.6     10185584.16
      3713487.85     10185902.45      3711999.87     10186724.63
#Sta/Elev= 30
    3941  267.75  4195.7  265.02  4259.3  266.52  4273.4   265.3  4280.7  263.13
  4294.9  264.55  4315.9  263.33  4365.6  265.21  4620.2  264.34  4973.9  265.62
  4981.2  265.36  4988.1   262.4  4995.4  257.41  4999.5  257.41    5000  258.78
  5008.1  258.23 5020.73262.4536    5031   265.4  5048.5  265.52  5260.7  264.82
  5353.1   263.2  5578.8  265.69    5932  264.51  5981.2  266.69    6019  263.54
  6047.2  265.61  6127.9   267.7  6665.1  265.99  6961.2  270.99  7050.3  270.62
#Mann= 3 , 0 , 0
    3941     .11       0  4988.1     .06       0 5020.73     .11       0
Bank Sta=4988.1,5020.73
XS Rating Curve= 0 ,0
Exp/Cntr=0.3,0.1

Type RM Length L Ch R = 1 ,629     ,0,0,0
BEGIN DESCRIPTION:
CCLC 084 1.0
END DESCRIPTION:
XS GIS Cut Line= 3
      3712041.54      10186771.5      3713703.03     10185813.15
      3713271.26     10184294.19
#Sta/Elev= 30
  2734.9  271.37  3143.3  265.31  3411.9  266.84  3604.3  265.76  3641.6   267.7
  3677.3  265.84  3727.8  266.29  3758.1  264.32  4226.2  265.45  4644.2  261.85
  4797.7  261.89    4967  264.19  4977.4  264.13  4979.8261.4314  4982.7  258.17
  4987.9  260.59  4996.1  255.44  5000.2  255.44  5008.6  261.31  5021.8  264.62
  5320.5   262.9  5372.5  262.04  5381.4  260.46  5393.3  262.15  5403.6   258.3
  5425.6  263.67  5507.6  261.95  6048.4  263.01  6150.1  265.24  6232.1  270.41
#Mann= 3 , 0 , 0
  2734.9     .11       0  4979.8     .06       0  5008.6     .11       0
Bank Sta=4979.8,5008.6
XS Rating Curve= 0 ,0
Exp/Cntr=0.3,0.1

Chan Stop Cuts=-1
Use User Specified Reach Order=0
Composite Channel Slope=5