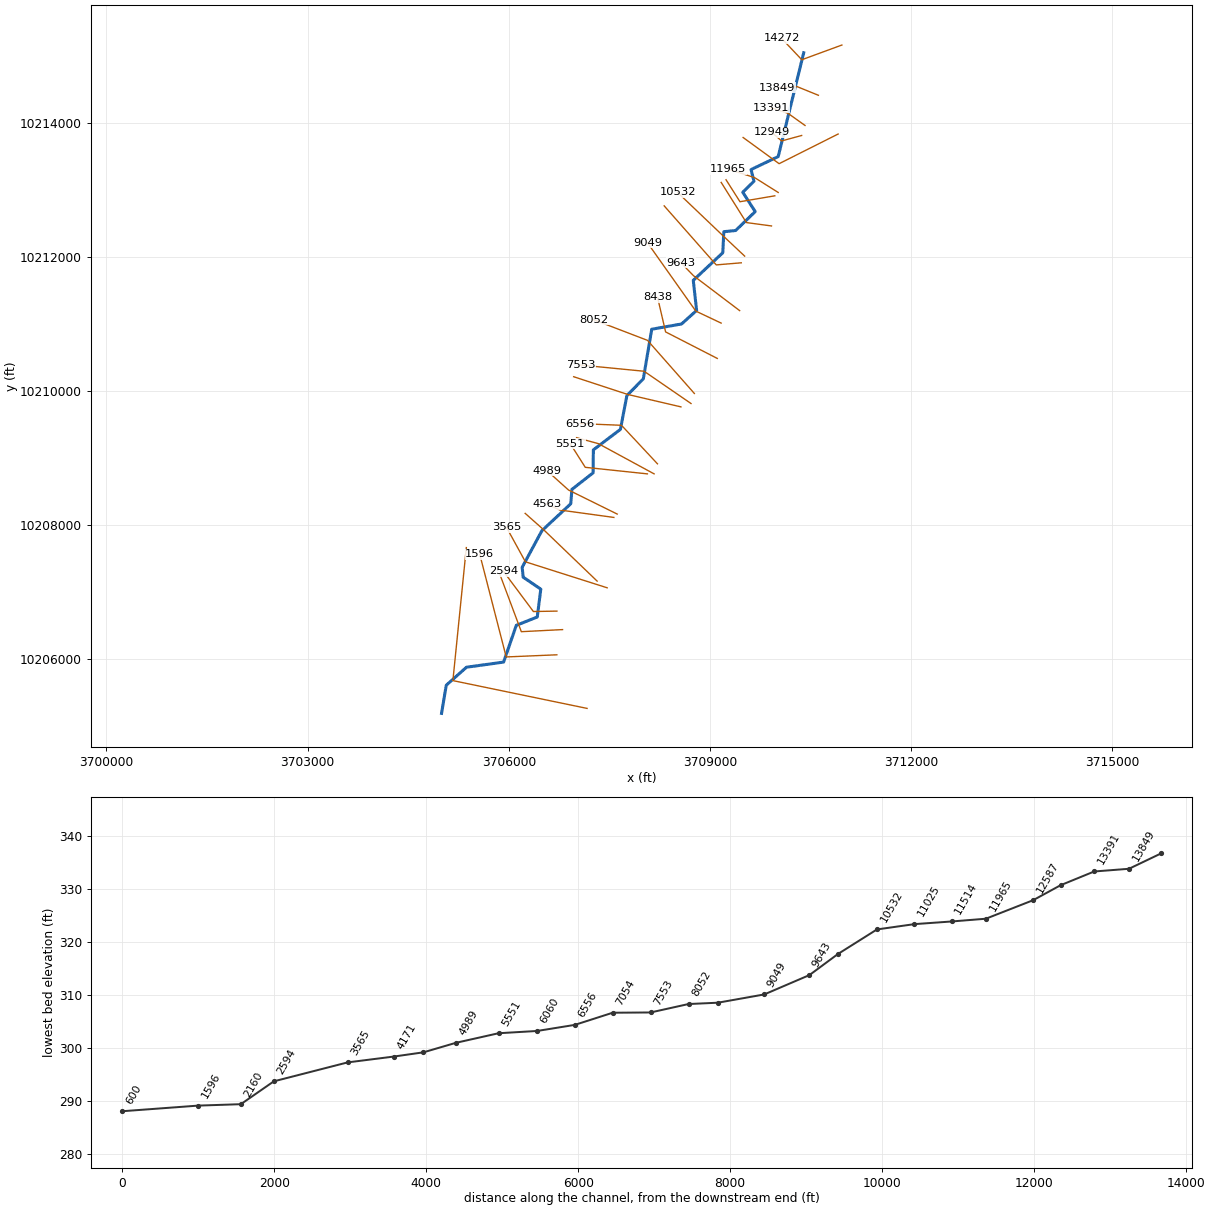
--- CCLC 086.prj (project) ---

Proj Title=CCLC 086 Base Level Engineering
Current Plan=p01
Default Exp/Contr=0.3,0.1
English Units
Geom File=g01
Flow File=f01
Flow File=f02
Plan File=p01
Y Axis Title=Elevation
X Axis Title(PF)=Main Channel Distance
X Axis Title(XS)=Station
BEGIN DESCRIPTION:
CCLC 086
END DESCRIPTION:
DSS Export Rating Curves= 0
DSS Export Rating Curve Sorted= 0
DSS Export Volume Flow Curves= 0
DXF OffsetX= 0
DXF OffsetY= 0
DXF ScaleX= 1
DXF ScaleY= 10

--- CCLC 086.p01 (plan) ---

Plan Title=Multiple Run
Short Identifier=Multiple
Geom File=g01
Flow File=f01
Subcritical Flow
K Sum by GR= 0
Std Step Tol= 0.01
Critical Tol= 0.01
Num of Std Step Trials= 20
Max Error Tol= 0.3
Flow Tol Ratio= 0.001
Split Flow NTrial= 30
Split Flow Tol= 0.02
Split Flow Ratio= 0.02
Log Output Level= 0
Friction Slope Method= 1
Unsteady Friction Slope Method= 2
Unsteady Bridges Friction Slope Method= 1
Parabolic Critical Depth
Global Vel Dist=  1 , 1 , 1
Global Log Level= 0
CheckData=True
Encroach Param= -1, 0, 0, 0
BEGIN DESCRIPTION:
Multiple Run
END DESCRIPTION:

--- CCLC 086.f01 (steady flow) ---

Flow Title=Multiple
Program Version=4.10
Number of Profiles= 7
Profile Names=10-year,25-year,50-year,1pct_min,100-year,1pct_plu,500-year
River Rch & RM=CCLC 086,Reach-1         ,14272
     773    1068    1463     659    1989    6007    3808
River Rch & RM=CCLC 086,Reach-1         ,11965
     851    1171    1601     719    2170    6553    4125
River Rch & RM=CCLC 086,Reach-1         ,8052
    1574    2238    3122    1428    4313   13025    8528
Boundary for River Rch & Prof#=CCLC 086,Reach-1         , 1
Up Type= 0
Dn Type= 3
Dn Slope=0.005
Boundary for River Rch & Prof#=CCLC 086,Reach-1         , 2
Up Type= 0
Dn Type= 3
Dn Slope=0.005
Boundary for River Rch & Prof#=CCLC 086,Reach-1         , 3
Up Type= 0
Dn Type= 3
Dn Slope=0.005
Boundary for River Rch & Prof#=CCLC 086,Reach-1         , 4
Up Type= 0
Dn Type= 3
Dn Slope=0.005
Boundary for River Rch & Prof#=CCLC 086,Reach-1         , 5
Up Type= 0
Dn Type= 3
Dn Slope=0.005
Boundary for River Rch & Prof#=CCLC 086,Reach-1         , 6
Up Type= 0
Dn Type= 3
Dn Slope=0.005
Boundary for River Rch & Prof#=CCLC 086,Reach-1         , 7
Up Type= 0
Dn Type= 3
Dn Slope=0.005
DSS Import GetInterval= 0
DSS Import GetPeak= 0
DSS Import FillOption= 0

--- CCLC 086.f02 (steady flow) ---

Flow Title=Orig_BLE_Flows
Program Version=4.10
Number of Profiles= 7
Profile Names=10-year,25-year,50-year,1pct_min,100-year,1pct_plu,500-year
River Rch & RM=CCLC 086,Reach-1         ,14272
     773    1047    1272     507    1530    4622    2214
River Rch & RM=CCLC 086,Reach-1         ,11965
     851    1148    1392     553    1669    5039    2398
River Rch & RM=CCLC 086,Reach-1         ,8052
    1574    2194    2715    1099    3318   10021    4958
Boundary for River Rch & Prof#=CCLC 086,Reach-1         , 1
Up Type= 0
Dn Type= 3
Dn Slope=0.005
Boundary for River Rch & Prof#=CCLC 086,Reach-1         , 2
Up Type= 0
Dn Type= 3
Dn Slope=0.005
Boundary for River Rch & Prof#=CCLC 086,Reach-1         , 3
Up Type= 0
Dn Type= 3
Dn Slope=0.005
Boundary for River Rch & Prof#=CCLC 086,Reach-1         , 4
Up Type= 0
Dn Type= 3
Dn Slope=0.005
Boundary for River Rch & Prof#=CCLC 086,Reach-1         , 5
Up Type= 0
Dn Type= 3
Dn Slope=0.005
Boundary for River Rch & Prof#=CCLC 086,Reach-1         , 6
Up Type= 0
Dn Type= 3
Dn Slope=0.005
Boundary for River Rch & Prof#=CCLC 086,Reach-1         , 7
Up Type= 0
Dn Type= 3
Dn Slope=0.005
DSS Import GetInterval= 0
DSS Import GetPeak= 0
DSS Import FillOption= 0

--- CCLC 086.g01 (geometry) ---

Geom Title=Existing Conditions
Program Version=4.10

River Reach=CCLC 086        ,Reach-1
Reach XY= 30
      3710398.48     10215045.72      3710018.23     10213496.84
      3709613.18     10213302.51      3709656.71     10213128.27
      3709489.53     10212964.37       3709675.3     10212675.32
      3709383.63     10212392.92      3709206.94     10212375.61
      3709192.21     10212061.35      3708751.87      10211649.2
      3708801.62     10211200.23      3708577.35     10210998.26
      3708132.46     10210919.98       3708006.8     10210179.33
      3707761.55     10209929.24      3707665.23     10209425.09
      3707261.81     10209119.03      3707258.23     10208776.84
      3706941.78     10208529.13      3706925.28     10208315.07
      3706493.99     10207912.35      3706200.52     10207366.84
      3706215.48     10207219.74      3706477.84      10207040.7
       3706425.3     10206625.34      3706112.97     10206500.76
      3705923.35     10205952.16      3705369.69     10205875.33
      3705068.46     10205607.29      3704998.23     10205186.84

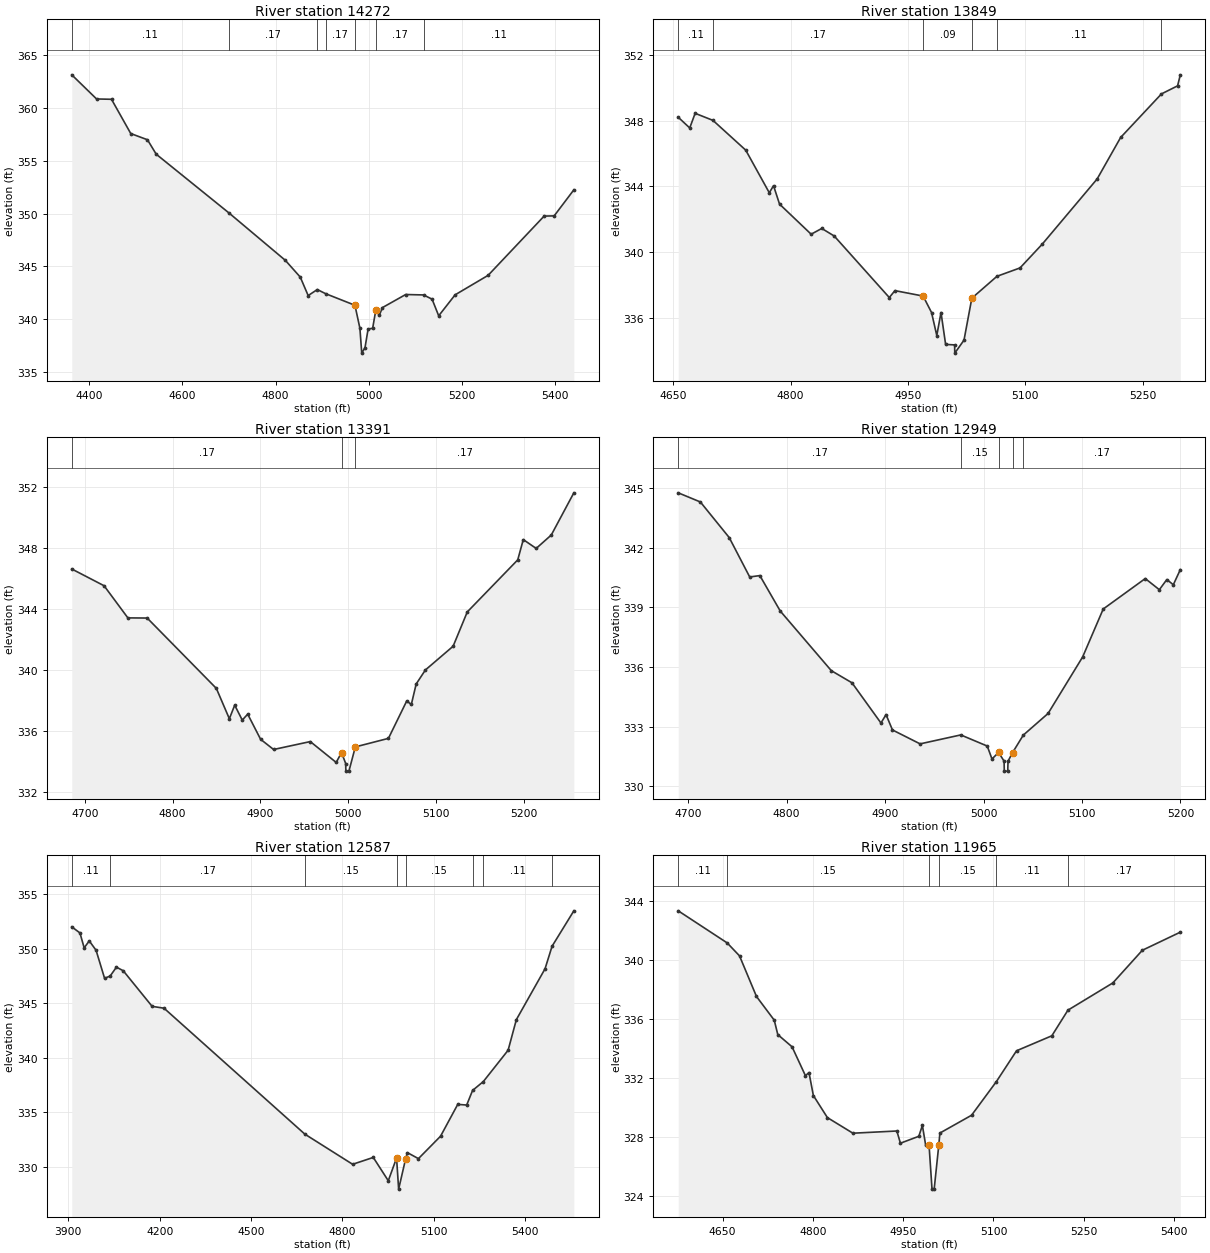
Type RM Length L Ch R = 1 ,14272   ,423,423,423
BEGIN DESCRIPTION:
CCLC 086 27.0
END DESCRIPTION:
XS GIS Cut Line= 3
      3710967.82     10215161.06      3710369.83     10214941.55
      3710067.88     10215261.04
#Sta/Elev= 30
    4363  363.16  4416.2  360.87  4448.2  360.84  4489.5  357.59  4525.3     357
  4544.1  355.63    4700  350.06    4821  345.56    4853  343.97  4869.9  342.22
  4889.5  342.79  4907.3   342.4  4970.2   341.3  4980.8  339.13  4984.8  336.76
  4991.8  337.28  4998.4  339.04  5008.2  339.12  5015.1  340.88  5022.4  340.35
  5029.2  341.08    5079  342.32  5117.3  342.28  5135.6  341.88  5149.8   340.3
    5185  342.29  5255.8  344.14  5375.9  349.76  5397.4  349.78  5439.6  352.25
#Mann= 7 ,-1 , 0
    4363     .11       0    4700     .17       0  4889.5     .11       0
  4907.3     .17       0  4970.2     .09       0  5015.1     .17       0
  5117.3     .11       0
Bank Sta=4970.2,5015.1
XS Rating Curve= 0 ,0
Exp/Cntr=0.3,0.1

Type RM Length L Ch R = 1 ,13849   ,458,458,458
BEGIN DESCRIPTION:
CCLC 086 26.0
END DESCRIPTION:
XS GIS Cut Line= 3
      3710617.81     10214411.09      3710299.52     10214540.51
      3710001.69     10214525.78
#Sta/Elev= 30
  4656.4   348.2  4671.1  347.55    4678  348.44  4700.8  348.01  4742.7   346.2
  4772.8  343.61  4778.2  344.04  4785.9  342.92  4826.3  341.09  4839.9  341.44
  4855.8  340.98  4926.2  337.24  4933.4  337.66  4969.4  337.33  4980.2  336.33
  4986.9  334.93  4992.3  336.33  4998.2  334.39  5009.7  334.36  5009.9  333.86
  5021.7  334.65  5031.7   337.2  5063.8  338.53  5093.3  339.04  5121.8  340.49
  5191.9  344.45  5221.9  346.97  5274.1  349.62  5294.7  350.11  5298.2  350.78
#Mann= 6 ,-1 , 0
  4656.4     .11       0  4700.8     .17       0  4969.4     .09       0
  5031.7     .17       0  5063.8     .11       0  5274.1     .17       0
Bank Sta=4969.4,5031.7
XS Rating Curve= 0 ,0
Exp/Cntr=0.3,0.1

Type RM Length L Ch R = 1 ,13391   ,442,442,442
BEGIN DESCRIPTION:
CCLC 086 25.0
END DESCRIPTION:
XS GIS Cut Line= 3
      3710417.84     10213961.08       3710161.5     10214143.81
      3709917.11     10214223.64
#Sta/Elev= 30
  4685.2  346.62    4722  345.52  4749.1  343.41  4771.1   343.4  4849.9  338.78
  4864.7  336.79  4870.8  337.68  4879.4   336.7  4885.6  337.09  4900.3  335.44
  4915.1  334.77  4956.9  335.29  4986.4  333.92  4992.5  334.57  4997.2  333.85
  4997.4  333.35  5000.9  333.35  5008.2  334.94  5045.9   335.5  5066.7  337.95
    5072  337.73  5077.5  339.07    5088  339.99  5119.6  341.55  5135.7   343.8
  5193.2  347.22  5199.5  348.55  5214.2  347.97  5231.4  348.85  5257.1  351.62
#Mann= 3 , 0 , 0
  4685.2     .17       0  4992.5     .09       0  5008.2     .17       0
Bank Sta=4992.5,5008.2
XS Rating Curve= 0 ,0
Exp/Cntr=0.3,0.1

Type RM Length L Ch R = 1 ,12949   ,362,362,362
BEGIN DESCRIPTION:
CCLC 086 24.0
END DESCRIPTION:
XS GIS Cut Line= 3
      3710367.86     10213811.07      3710068.62     10213729.75
      3709917.88     10213861.04
#Sta/Elev= 30
  4689.9  344.75  4712.4  344.29  4741.7   342.5  4762.5  340.52  4772.8  340.59
  4793.5  338.81  4845.4  335.81  4866.4   335.2  4895.8  333.18    4901   333.6
  4907.5  332.83  4935.6  332.13  4976.9  332.58  5003.8  332.02  5008.6  331.37
  5015.3   331.7  5020.9  331.26  5021.1  330.76  5024.6  330.76  5024.9  331.26
  5029.5  331.69  5040.4  332.57  5065.6  333.66  5100.7   336.5  5121.6  338.91
  5164.3  340.44  5178.6  339.88  5186.2  340.39  5192.8  340.13  5199.9  340.89
#Mann= 5 ,-1 , 0
  4689.9     .17       0  4976.9     .15       0  5015.3     .09       0
  5029.5     .15       0  5040.4     .17       0
Bank Sta=5015.3,5029.5
XS Rating Curve= 0 ,0
Exp/Cntr=0.3,0.1

Type RM Length L Ch R = 1 ,12587   ,622,622,622
BEGIN DESCRIPTION:
CCLC 086 23.0
END DESCRIPTION:
XS GIS Cut Line= 3
       3710911.9     10213833.01      3710031.69      10213390.3
      3709495.22     10213780.94
#Sta/Elev= 30
  3911.3  352.01  3938.2  351.45    3952  350.08  3968.7  350.72  3991.1  349.86
    4019  347.29  4037.3  347.49    4058  348.31  4080.3  347.98  4175.2  344.71
  4214.3  344.54  4676.7  332.98  4833.7  330.21  4901.5  330.84  4950.8   328.7
    4978  330.79  4984.8  327.93  5007.4  330.67  5013.6  331.28  5049.8  330.73
  5122.5  332.79  5178.9  335.71  5208.3  335.65  5227.6  336.99  5263.1  337.81
  5344.3  340.68  5371.4  343.49  5465.6  348.16  5488.7  350.23  5560.2  353.48
#Mann= 8 ,-1 , 0
  3911.3     .11       0  4037.3     .17       0  4676.7     .15       0
    4978     .09       0  5007.4     .15       0  5227.6     .17       0
  5263.1     .11       0  5488.7     .17       0
Bank Sta=4978,5007.4
XS Rating Curve= 0 ,0
Exp/Cntr=0.3,0.1

Type RM Length L Ch R = 1 ,11965   ,451,451,451
BEGIN DESCRIPTION:
CCLC 086 22.0
END DESCRIPTION:
XS GIS Cut Line= 3
      3710017.84     10212961.08      3709667.11     10213181.97
      3709267.85     10213311.07
#Sta/Elev= 30
  4576.3  343.35  4657.6  341.17  4678.1  340.29  4706.3  337.53  4735.8  335.92
  4741.7  334.94  4765.4  334.11  4787.6  332.15  4793.5  332.36  4800.8   330.8
  4824.1   329.3  4866.5  328.24  4939.5  328.39  4945.4  327.56    4976  328.03
  4981.9  328.77  4987.4  327.42    4993  327.42  4997.9  324.44  5001.5  324.44
 5009.16327.4326    5011  328.25  5063.6  329.46  5104.9  331.75  5138.3  333.84
    5197  334.86  5223.7   336.6  5298.3  338.45  5347.3  340.67  5410.4   341.9
#Mann= 6 ,-1 , 0
  4576.3     .11       0  4657.6     .15       0    4993     .09       0
 5009.16     .15       0  5104.9     .11       0  5223.7     .17       0
Bank Sta=4993,5009.16
XS Rating Curve= 0 ,0
Exp/Cntr=0.3,0.1

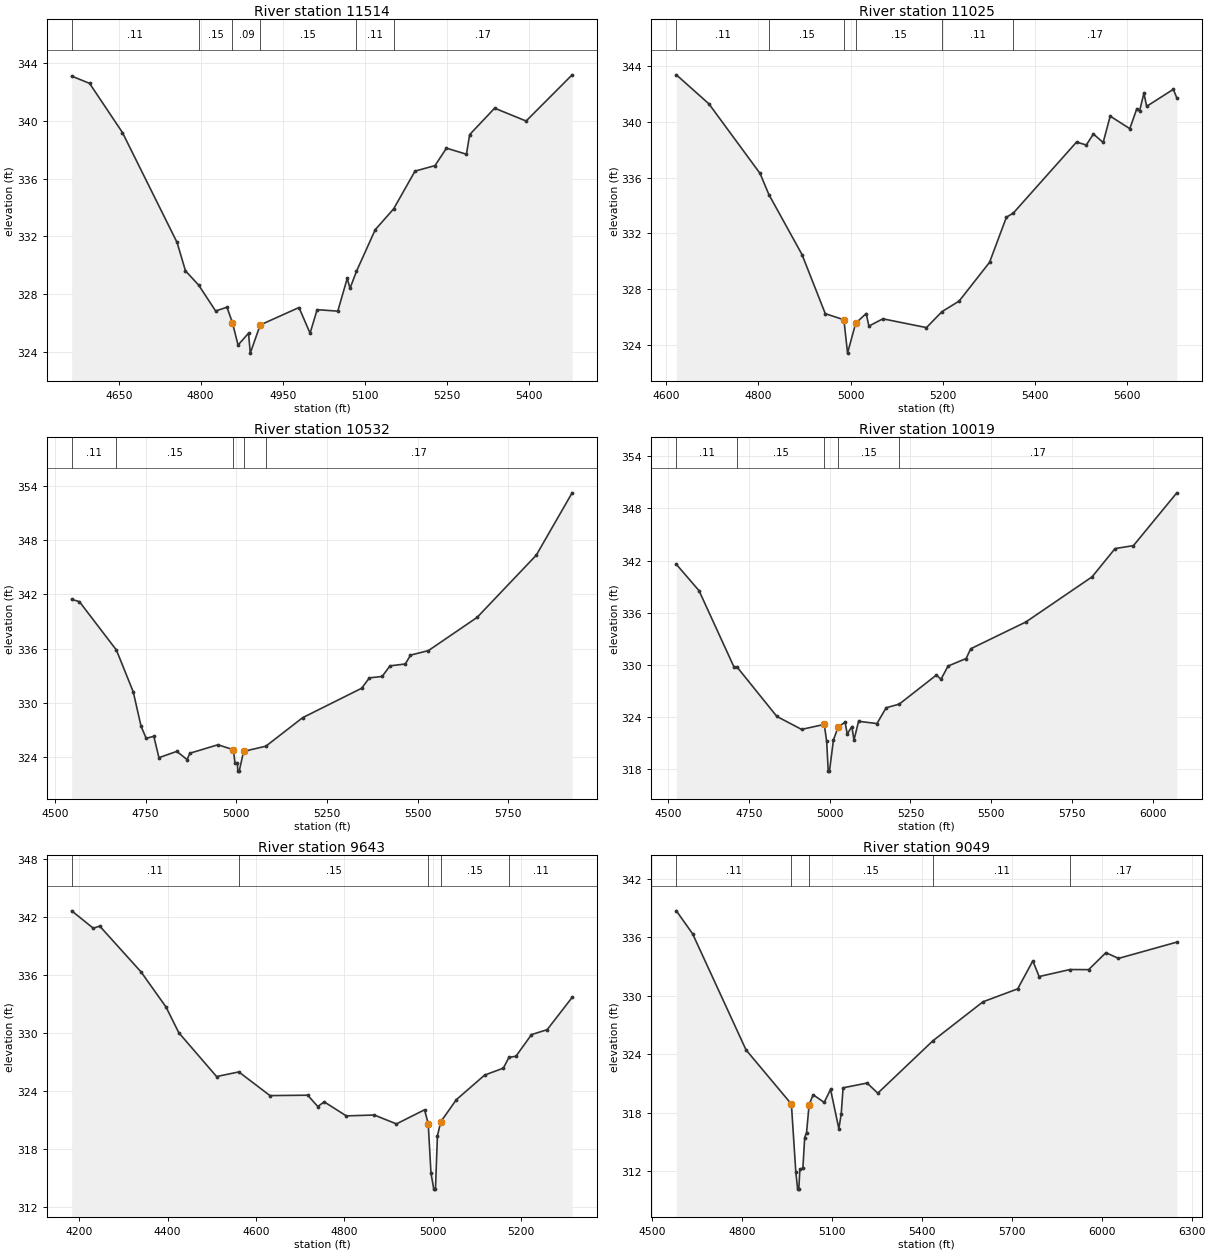
Type RM Length L Ch R = 1 ,11514   ,489,489,489
BEGIN DESCRIPTION:
CCLC 086 21.0
END DESCRIPTION:
XS GIS Cut Line= 3
      3709967.89     10212911.08      3709448.36     10212822.59
      3709240.02     10213150.73
#Sta/Elev= 30
    4564  343.11  4596.7  342.61  4656.9   339.2  4756.8  331.59  4772.2  329.62
  4796.4  328.63  4827.4  326.84  4848.1   327.1  4858.2  326.02  4868.4  324.48
  4887.6   325.3  4890.8  323.92  4908.9  325.87  4979.9  327.08  5000.2   325.3
  5013.1  326.93  5050.9  326.83  5068.2   329.1  5073.3  328.41  5085.1  329.59
  5119.4  332.47  5153.2  333.92  5192.2  336.53  5228.7  336.91  5249.8  338.12
  5286.3   337.7  5292.2  339.06  5337.9  340.89  5395.5     340  5479.7   343.2
#Mann= 6 ,-1 , 0
    4564     .11       0  4796.4     .15       0  4858.2     .09       0
  4908.9     .15       0  5085.1     .11       0  5153.2     .17       0
Bank Sta=4858.2,4908.9
XS Rating Curve= 0 ,0
Exp/Cntr=0.3,0.1

Type RM Length L Ch R = 1 ,11025   ,493,493,493
BEGIN DESCRIPTION:
CCLC 086 20.0
END DESCRIPTION:
XS GIS Cut Line= 3
      3709917.83     10212461.07      3709543.44     10212511.72
      3709167.86     10213111.06
#Sta/Elev= 30
  4622.2  343.37  4692.8  341.29  4803.7   336.3  4822.8  334.79  4894.6  330.49
  4945.1  326.25  4985.5  325.81  4993.4  323.42    5011  325.56  5033.8  326.26
  5039.7  325.36    5070  325.88  5164.5  325.25    5198  326.39  5235.3  327.15
  5301.3  329.93  5337.8  333.16  5353.1  333.47  5489.9  338.55  5511.1  338.34
  5526.4  339.13  5547.6  338.52  5562.9  340.41  5605.4  339.51  5620.7  340.95
  5626.6  340.77    5636  342.06  5641.9  341.11  5699.7  342.33  5707.3  341.72
#Mann= 6 ,-1 , 0
  4622.2     .11       0  4822.8     .15       0  4985.5     .09       0
    5011     .15       0    5198     .11       0  5353.1     .17       0
Bank Sta=4985.5,5011
XS Rating Curve= 0 ,0
Exp/Cntr=0.3,0.1

Type RM Length L Ch R = 1 ,10532   ,513,513,513
BEGIN DESCRIPTION:
CCLC 086 19.0
END DESCRIPTION:
XS GIS Cut Line= 3
      3709517.82      10212011.1      3709187.45     10212322.06
      3708517.84     10212961.09
#Sta/Elev= 30
  4546.3  341.44  4567.5   341.2  4669.6  335.83    4716   331.2  4737.4  327.41
  4751.6  326.05  4772.6  326.28  4786.8  323.91  4836.1  324.61  4864.5  323.69
  4871.8   324.4  4949.4  325.34  4991.9  324.79  4996.3  323.34  5002.9  323.34
  5004.2  322.42    5008  322.42  5020.2  324.61  5081.4  325.18  5182.8  328.34
  5345.4   331.6  5366.8  332.75  5402.1  332.91  5423.5  334.08  5465.9  334.29
  5480.1  335.27  5529.4  335.77  5663.7  339.45  5826.7  346.34  5925.6  353.25
#Mann= 5 ,-1 , 0
  4546.3     .11       0  4669.6     .15       0  4991.9     .09       0
  5020.2     .15       0  5081.4     .17       0
Bank Sta=4991.9,5020.2
XS Rating Curve= 0 ,0
Exp/Cntr=0.3,0.1

Type RM Length L Ch R = 1 ,10019   ,376,376,376
BEGIN DESCRIPTION:
CCLC 086 18.0
END DESCRIPTION:
XS GIS Cut Line= 3
      3709467.83     10211911.07      3709094.19     10211879.89
      3708317.87     10212761.05
#Sta/Elev= 30
  4525.4  341.57  4595.6  338.54  4703.4   329.8  4714.4  329.71  4836.5  324.08
    4913  322.59  4983.3  323.16  4990.8   321.2  4995.6  317.79  4999.4  317.79
  5011.7  321.37    5026  322.84  5047.7  323.43  5054.4  322.05  5068.6  322.92
  5075.3  321.36  5089.5  323.52  5146.4  323.26  5174.9  325.08  5215.2  325.49
  5330.5  328.84  5344.7  328.35  5366.5  329.87  5422.5  330.74  5436.7  331.86
  5607.5  334.94  5812.4  340.13  5883.6  343.38  5940.5  343.72  6074.7  349.79
#Mann= 5 ,-1 , 0
  4525.4     .11       0  4714.4     .15       0  4983.3     .09       0
    5026     .15       0  5215.2     .17       0
Bank Sta=4983.3,5026
XS Rating Curve= 0 ,0
Exp/Cntr=0.3,0.1

Type RM Length L Ch R = 1 ,9643    ,594,594,594
BEGIN DESCRIPTION:
CCLC 086 17.0
END DESCRIPTION:
XS GIS Cut Line= 3
      3709443.13     10211197.61      3708755.65     10211718.43
      3708567.87     10211911.06
#Sta/Elev= 30
  4183.3  342.61  4232.1  340.81  4246.7  341.03  4340.3  336.28  4396.5  332.66
  4425.6  329.99  4510.9  325.46  4561.2  325.94  4631.6  323.49  4716.9  323.53
  4739.7  322.36  4754.3  322.84  4804.2  321.39  4867.4  321.48  4917.6  320.56
  4981.1  322.02  4989.4  320.59  4995.7  315.45    5002  313.81  5005.8  313.81
  5010.2  319.32  5017.9  320.79  5053.1  323.07  5116.9  325.61  5159.3  326.33
  5172.1  327.46  5187.6  327.55  5222.9   329.8  5258.3  330.31  5314.8  333.65
#Mann= 5 ,-1 , 0
  4183.3     .11       0  4561.2     .15       0  4989.4     .09       0
  5017.9     .15       0  5172.1     .11       0
Bank Sta=4989.4,5017.9
XS Rating Curve= 0 ,0
Exp/Cntr=0.3,0.1

Type RM Length L Ch R = 1 ,9049    ,611,611,611
BEGIN DESCRIPTION:
CCLC 086 16.0
END DESCRIPTION:
XS GIS Cut Line= 3
      3709167.82     10211011.09      3708789.86     10211190.08
      3708067.85     10212211.08
#Sta/Elev= 30
  4581.8   338.7  4635.9  336.35  4814.1  324.44  4965.4  318.88  4980.1  311.92
  4986.2  310.16  4990.1  310.16  4993.7  312.19  5003.7  312.32  5009.7  315.45
  5015.9  315.96  5024.5  318.82    5038  319.84  5074.7  319.05  5095.9  320.39
  5123.7  316.35  5131.6  317.91  5137.7  320.55  5217.8  321.04  5253.5     320
  5437.1  325.37  5604.2  329.37    5720   330.7  5770.5  333.57  5791.4  331.96
  5894.5  332.68  5956.5  332.67  6014.2  334.41    6056  333.82  6250.5  335.49
#Mann= 5 ,-1 , 0
  4581.8     .11       0  4965.4     .09       0  5024.5     .15       0
  5437.1     .11       0  5894.5     .17       0
Bank Sta=4965.4,5024.5
XS Rating Curve= 0 ,0
Exp/Cntr=0.3,0.1

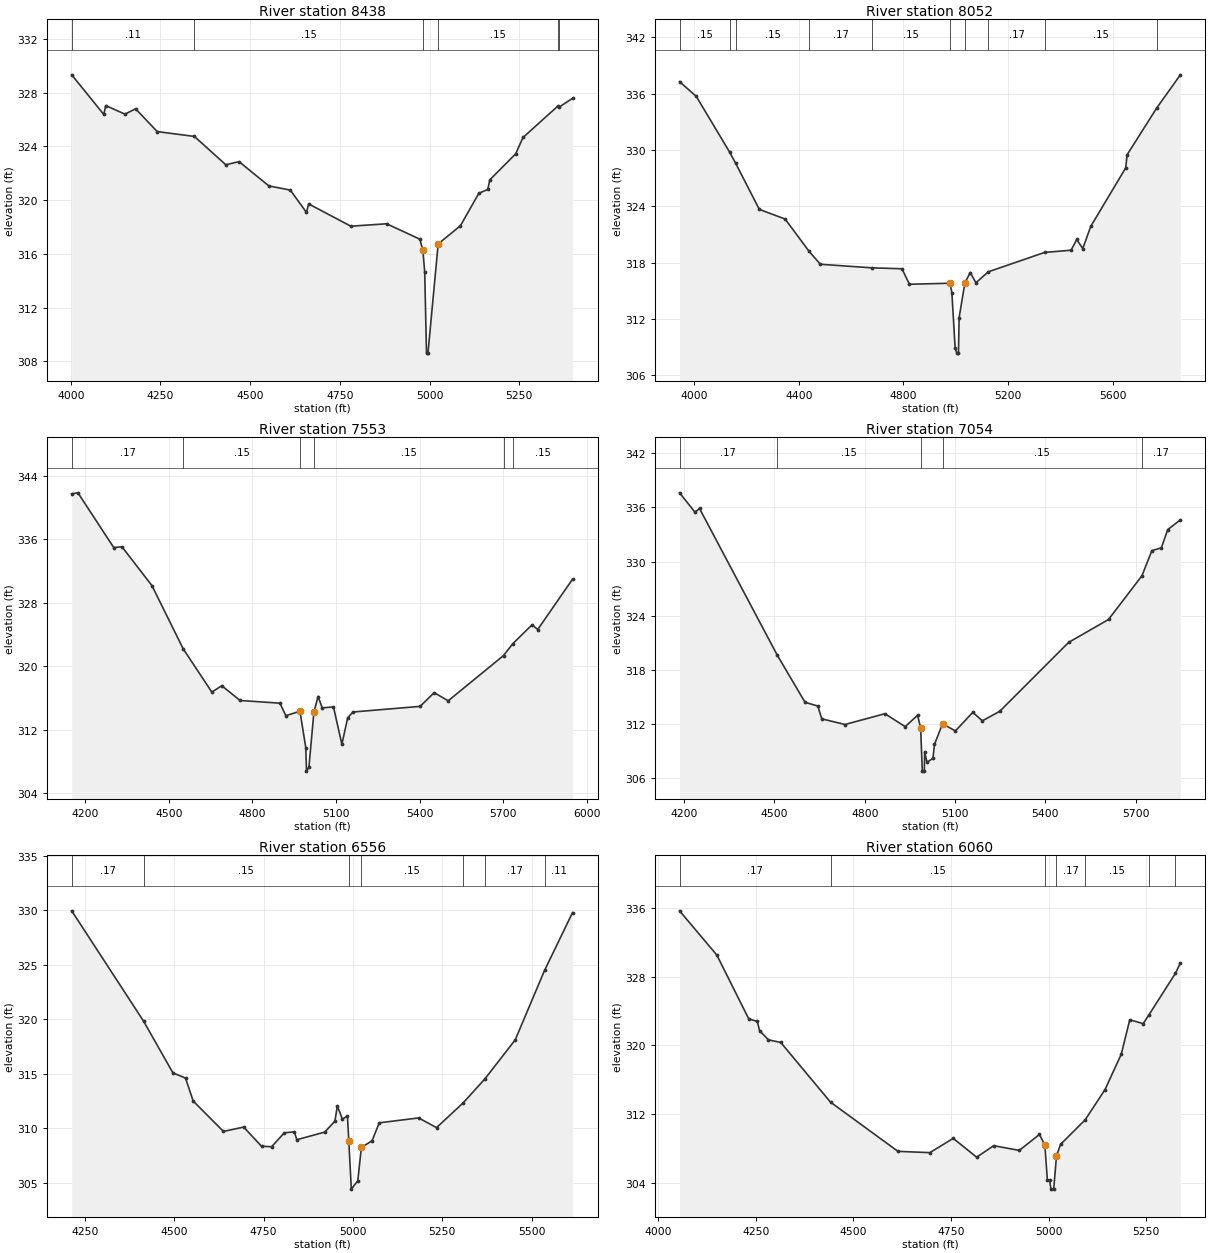
Type RM Length L Ch R = 1 ,8438    ,386,386,386
BEGIN DESCRIPTION:
CCLC 086 15.0
END DESCRIPTION:
XS GIS Cut Line= 3
      3709109.84     10210484.04      3708338.98     10210879.89
      3708219.19     10211395.51
#Sta/Elev= 30
  4002.6  329.34  4091.9  326.39  4097.5  327.05    4151  326.41  4180.6  326.81
  4240.9  325.11  4344.5  324.75    4432  322.64  4469.1  322.87  4552.2  321.06
  4611.9  320.75  4656.8  319.09  4663.1  319.72  4780.5  318.06  4880.6  318.24
    4973  317.09  4981.4  316.25  4986.5  314.64  4991.5   308.6  4995.6   308.6
    5024  316.74    5086  318.09  5137.3  320.51  5162.2   320.8  5168.1  321.52
    5240  323.45  5260.5  324.67  5357.1     327  5361.4  326.94  5398.5  327.59
#Mann= 6 ,-1 , 0
  4002.6     .11       0  4344.5     .15       0  4981.4     .09       0
    5024     .15       0  5357.1     .11       0  5361.4     .17       0
Bank Sta=4981.4,5024
XS Rating Curve= 0 ,0
Exp/Cntr=0.3,0.1

Type RM Length L Ch R = 1 ,8052    ,499,499,499
BEGIN DESCRIPTION:
CCLC 086 14.0
END DESCRIPTION:
XS GIS Cut Line= 3
      3708767.85     10209961.07      3708069.59     10210753.54
      3707267.85     10211061.07
#Sta/Elev= 30
  3943.8  337.28  4007.8  335.71  4135.1  329.78  4158.4  328.58  4248.8  323.67
  4347.5  322.64    4439   319.2  4482.2  317.82  4680.2  317.44  4794.3  317.34
  4822.7  315.69  4978.3   315.8    4985   314.8  4997.5   308.9  5004.1  308.35
  5010.3  308.35  5012.6  312.12 5034.94315.8535  5055.4  316.94  5076.8  315.85
  5124.7  317.02  5339.3  319.08    5441  319.32  5462.4  320.46  5485.5  319.49
    5516  321.86  5649.6  328.09  5655.2   329.5  5768.6  334.49  5858.7  338.01
#Mann= 10 ,-1 , 0
  3943.8     .15       0  4135.1     .17       0  4158.4     .15       0
    4439     .17       0  4680.2     .15       0  4978.3     .09       0
 5034.94     .15       0  5124.7     .17       0  5339.3     .15       0
  5768.6     .17       0
Bank Sta=4978.3,5034.94
XS Rating Curve= 0 ,0
Exp/Cntr=0.3,0.1

Type RM Length L Ch R = 1 ,7553    ,499,499,499
BEGIN DESCRIPTION:
CCLC 086 13.0
END DESCRIPTION:
XS GIS Cut Line= 3
      3708717.88     10209811.05      3708018.45     10210292.64
      3707073.36     10210385.09
#Sta/Elev= 30
  4150.8   341.7  4173.2  341.82  4301.7  334.93  4331.4  335.02    4439  330.13
  4551.2  322.17    4654  316.72  4689.9  317.52  4755.5  315.66  4898.9  315.32
  4919.8  313.74  4970.6  314.31  4991.5  309.73  4994.1  306.76  5002.8  307.26
  5020.7  314.19  5035.5  316.16  5050.8  314.73    5091  314.85  5121.2  310.15
  5142.1  313.49  5161.4  314.21  5402.5  314.92  5452.7  316.65    5503  315.62
  5701.8  321.32  5735.2  322.82  5804.4   325.2  5824.5   324.6  5949.6  330.94
#Mann= 6 ,-1 , 0
  4150.8     .17       0  4551.2     .15       0  4970.6     .09       0
  5020.7     .15       0  5701.8     .11       0  5735.2     .15       0
Bank Sta=4970.6,5020.7
XS Rating Curve= 0 ,0
Exp/Cntr=0.3,0.1

Type RM Length L Ch R = 1 ,7054    ,498,498,498
BEGIN DESCRIPTION:
CCLC 086 12.0
END DESCRIPTION:
XS GIS Cut Line= 3
      3708567.83     10209761.08      3707774.09     10209946.47
       3706967.8     10210211.09
#Sta/Elev= 30
  4184.9  337.63  4236.2  335.48  4251.2  335.89  4509.2  319.61  4601.7  314.36
  4644.2  313.94  4657.3  312.52  4734.4  311.89  4867.1  313.09  4934.5  311.65
  4975.6  312.92  4985.9  311.48  4991.3  306.71  4997.9  306.71  4999.1  308.85
  5006.6   307.7  5026.6  308.12  5031.8  309.68  5058.4  311.97  5101.3  311.18
  5159.1  313.24  5190.9   312.3  5248.6  313.36  5477.3  321.01  5609.9  323.56
    5721  328.42  5753.8   331.2  5785.4  331.52  5806.5  333.54  5848.6  334.63
#Mann= 5 ,-1 , 0
  4184.9     .17       0  4509.2     .15       0  4985.9     .09       0
  5058.4     .15       0    5721     .17       0
Bank Sta=4985.9,5058.4
XS Rating Curve= 0 ,0
Exp/Cntr=0.3,0.1

Type RM Length L Ch R = 1 ,6556    ,496,496,496
BEGIN DESCRIPTION:
CCLC 086 11.0
END DESCRIPTION:
XS GIS Cut Line= 3
      3708217.83     10208911.09      3707681.42     10209486.15
      3707067.83     10209511.07
#Sta/Elev= 30
  4213.6  329.94  4414.6  319.82  4496.7  315.08  4531.9   314.6  4553.3   312.5
  4637.9  309.71  4694.5  310.11  4744.4  308.35  4772.7  308.31  4807.9  309.58
  4836.2  309.68  4843.1  308.95  4921.2  309.65  4949.6  310.65  4956.4  312.05
  4970.6  310.84  4984.7  311.12  4988.5308.8327  4995.5  304.42  5013.6  305.18
  5023.6  308.24  5053.6  308.86  5073.6   310.5  5183.7  310.95  5233.8  310.06
    5308  312.32  5369.3  314.54  5453.9  318.11  5535.8  324.47  5614.1  329.78
#Mann= 7 ,-1 , 0
  4213.6     .17       0  4414.6     .15       0  4988.5     .09       0
  5023.6     .15       0    5308     .11       0  5369.3     .17       0
  5535.8     .11       0
Bank Sta=4988.5,5023.6
XS Rating Curve= 0 ,0
Exp/Cntr=0.3,0.1

Type RM Length L Ch R = 1 ,6060    ,509,509,509
BEGIN DESCRIPTION:
CCLC 086 10.0
END DESCRIPTION:
XS GIS Cut Line= 3
      3708167.84     10208761.08      3707337.12      10209212.2
      3707011.86     10209301.49
#Sta/Elev= 30
  4054.7  335.68  4150.2  330.53  4231.9   323.1  4253.8   322.8  4259.5  321.74
  4282.3  320.65  4313.7  320.36  4441.3   313.4    4614  307.67  4695.7  307.52
  4755.6  309.18  4815.5  306.99  4859.2  308.33  4924.8  307.78  4976.4  309.64
  4990.3  308.38  4996.7  304.32  5002.2  304.32  5006.1  303.27  5012.9  303.27
    5020  307.12  5030.4  308.48  5093.5  311.34  5144.4  314.87  5185.9  318.98
  5207.7  322.99  5242.1  322.54  5256.7  323.56  5324.6   328.4  5337.3   329.6
#Mann= 7 ,-1 , 0
  4054.7     .17       0  4441.3     .15       0  4990.3     .09       0
    5020     .17       0  5093.5     .15       0  5256.7     .11       0
  5324.6     .17       0
Bank Sta=4990.3,5020
XS Rating Curve= 0 ,0
Exp/Cntr=0.3,0.1

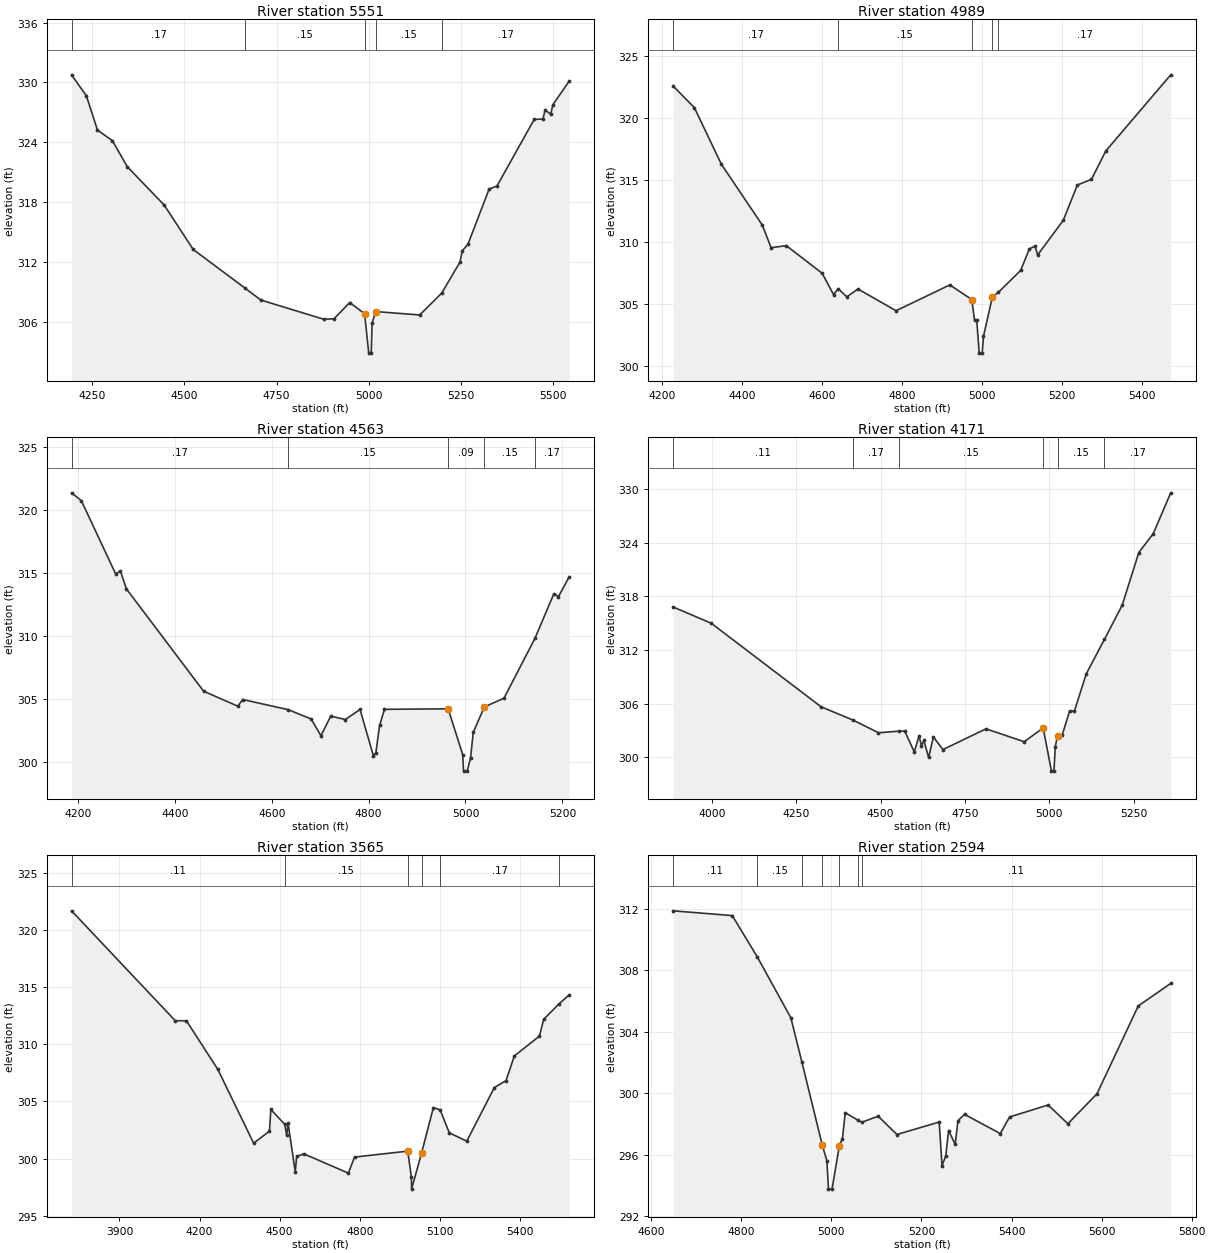
Type RM Length L Ch R = 1 ,5551    ,562,562,562
BEGIN DESCRIPTION:
CCLC 086 9.0
END DESCRIPTION:
XS GIS Cut Line= 3
      3708067.81     10208761.08      3707141.07     10208859.05
      3706917.87     10209211.05
#Sta/Elev= 30
  4194.5  330.77  4234.7  328.66  4264.8  325.22  4305.1  324.17  4345.3  321.56
  4445.8  317.69  4524.3  313.24  4665.2  309.35  4707.3  308.17  4878.2  306.24
  4905.6  306.28  4948.6  307.92  4988.9  306.79    5000  302.84  5006.8  302.84
    5009  305.86    5019  307.01  5138.2  306.67  5197.9  308.87  5247.2  311.97
  5253.5  313.12  5268.7  313.75  5326.3  319.31  5347.5  319.61  5448.5   326.3
  5472.1  326.33    5478  327.24  5493.2  326.82  5499.2  327.78  5543.2  330.13
#Mann= 5 ,-1 , 0
  4194.5     .17       0  4665.2     .15       0  4988.9     .09       0
    5019     .15       0  5197.9     .17       0
Bank Sta=4988.9,5019
XS Rating Curve= 0 ,0
Exp/Cntr=0.3,0.1

Type RM Length L Ch R = 1 ,4989    ,426,426,426
BEGIN DESCRIPTION:
CCLC 086 8.0
END DESCRIPTION:
XS GIS Cut Line= 3
      3707617.85     10208161.07      3706891.07     10208520.51
      3706567.87     10208811.05
#Sta/Elev= 30
  4227.5  322.57  4280.8  320.82  4348.1  316.27  4450.6  311.36  4472.9  309.53
  4510.7   309.7  4600.5  307.47  4629.1  305.75  4640.5  306.23  4662.2  305.57
  4690.2   306.2  4785.5  304.45  4920.1  306.53    4975  305.35  4981.9  303.68
  4987.4  303.68  4993.6  301.03    5001  301.03  5004.3  302.38  5026.7  305.59
  5041.2  305.92  5097.3   307.7    5119  309.42  5133.2  309.67  5139.9  308.95
    5204  311.74  5239.3  314.59  5274.5  315.04  5310.4  317.33  5472.9  323.47
#Mann= 5 ,-1 , 0
  4227.5     .17       0  4640.5     .15       0    4975     .09       0
  5026.7     .15       0  5041.2     .17       0
Bank Sta=4975,5026.7
XS Rating Curve= 0 ,0
Exp/Cntr=0.3,0.1

Type RM Length L Ch R = 1 ,4563    ,392,392,392
BEGIN DESCRIPTION:
CCLC 086 7.0
END DESCRIPTION:
XS GIS Cut Line= 3
      3707567.87     10208111.07      3706762.22     10208221.63
      3706567.82     10208311.09
#Sta/Elev= 30
  4186.8  321.35    4207  320.73  4277.7  314.92  4287.8  315.13    4300  313.72
  4459.4  305.59    4530   304.4  4540.1  304.93  4634.3  304.12  4681.4  303.38
  4701.6  302.05  4721.8  303.61  4752.1  303.34  4782.3  304.14  4809.8  300.47
  4814.9  300.68  4822.7  302.87  4832.8  304.15  4964.1  304.19  4994.3  300.55
    4996  299.24  5003.4  299.24  5010.5   300.3    5016  302.32  5038.9  304.34
  5079.4  305.03  5143.3  309.78  5182.3  313.32  5191.9   313.1    5214  314.67
#Mann= 5 ,-1 , 0
  4186.8     .17       0  4634.3     .15       0  4964.1     .09       0
  5038.9     .15       0  5143.3     .17       0
Bank Sta=4964.1,5038.9
XS Rating Curve= 0 ,0
Exp/Cntr=0.3,0.1

Type RM Length L Ch R = 1 ,4171    ,606,606,606
BEGIN DESCRIPTION:
CCLC 086 6.0
END DESCRIPTION:
XS GIS Cut Line= 3
      3707317.85     10207161.07      3706521.28     10207926.76
      3706245.27     10208171.52
#Sta/Elev= 30
  3885.7   316.8  3998.8  314.98  4324.2  305.63  4417.3  304.17    4494  302.73
  4553.7  302.91  4571.7  302.92    4600  300.59  4614.2  302.38  4621.1  301.28
  4628.3  301.87  4642.5  299.97  4656.6  302.26  4684.9  300.85  4812.3  303.17
  4925.5  301.73  4981.8  303.27  5006.2  298.44  5013.7  298.44  5017.5  301.15
  5024.2  302.42  5038.4  302.51  5060.1  305.17  5074.3  305.17  5109.5  309.33
  5163.2  313.18  5215.7  316.99    5265  322.89  5307.7     325  5359.5  329.57
#Mann= 6 ,-1 , 0
  3885.7     .11       0  4417.3     .17       0  4553.7     .15       0
  4981.8     .09       0  5024.2     .15       0  5163.2     .17       0
Bank Sta=4981.8,5024.2
XS Rating Curve= 0 ,0
Exp/Cntr=0.3,0.1

Type RM Length L Ch R = 1 ,3565    ,971,971,971
BEGIN DESCRIPTION:
CCLC 086 5.0
END DESCRIPTION:
XS GIS Cut Line= 3
      3707467.89     10207061.06      3706248.65     10207448.77
      3705967.85     10207961.07
#Sta/Elev= 30
  3720.6  321.66  4108.9  312.06  4150.9  312.05  4268.3  307.81  4402.7  301.35
  4461.8  302.41    4467   304.3  4519.5  302.99  4526.2  302.03  4531.5  303.09
  4558.5  298.85  4563.7   300.2  4590.7  300.42  4757.2  298.74  4780.5  300.14
  4979.8  300.66  4993.3  298.38    4994  297.34    5032  300.54  5075.6  304.46
  5100.8  304.27  5135.3  302.26  5200.7  301.53  5304.1  306.22  5347.7  306.82
  5378.9  308.98  5472.8  310.71  5488.9  312.18  5545.7  313.52  5584.2  314.31
#Mann= 6 ,-1 , 0
  3720.6     .11       0  4519.5     .15       0  4979.8     .09       0
    5032     .15       0  5100.8     .17       0  5545.7     .11       0
Bank Sta=4979.8,5032
XS Rating Curve= 0 ,0
Exp/Cntr=0.3,0.1

Type RM Length L Ch R = 1 ,2594    ,434,434,434
BEGIN DESCRIPTION:
CCLC 086 4.0
END DESCRIPTION:
XS GIS Cut Line= 3
      3706719.23     10206713.22      3706367.89     10206706.77
      3705917.83      10207311.1
#Sta/Elev= 30
  4648.6  311.86    4780  311.55  4835.8  308.85    4910  304.91  4934.4  302.05
    4980  296.61    4990  295.62  4993.6  293.77  5001.5  293.77  5017.8   296.6
  5024.6  297.05  5030.9  298.74  5058.4  298.26    5068  298.12  5103.9  298.51
  5145.6  297.32  5239.4  298.13  5245.7   295.3    5254  295.93  5260.3  297.58
  5274.9  296.68  5281.1  298.22  5295.7  298.63    5375  297.38  5395.8  298.46
  5481.3  299.24  5525.1  298.02  5589.8  299.97  5681.5  305.68  5753.5  307.14
#Mann= 7 ,-1 , 0
  4648.6     .11       0  4835.8     .15       0  4934.4     .11       0
    4980     .06       0  5017.8     .11       0  5058.4     .15       0
    5068     .11       0
Bank Sta=4980,5017.8
XS Rating Curve= 0 ,0
Exp/Cntr=0.3,0.1

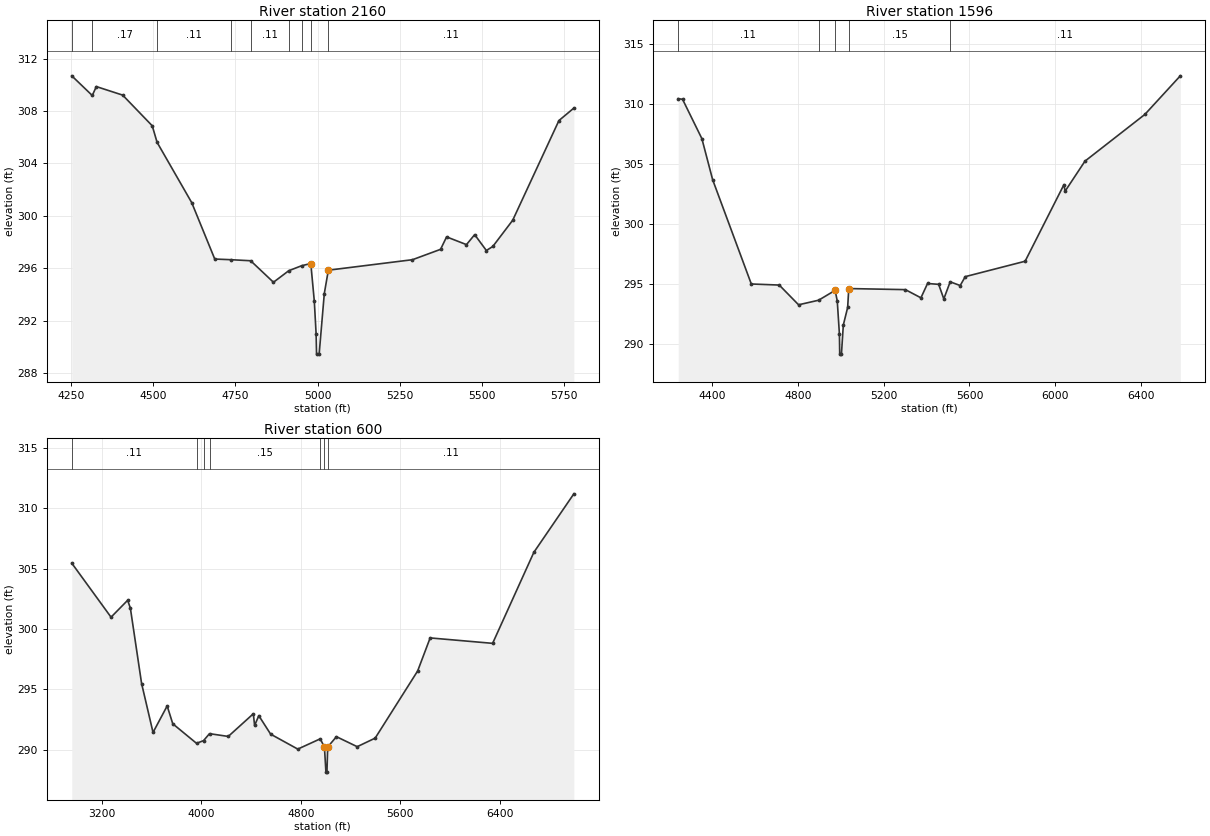
Type RM Length L Ch R = 1 ,2160    ,564,564,564
BEGIN DESCRIPTION:
CCLC 086 3.0
END DESCRIPTION:
XS GIS Cut Line= 3
      3706802.55     10206437.18      3706187.94     10206405.93
      3705867.85     10207261.08
#Sta/Elev= 30
  4251.7  310.68  4314.1  309.18  4326.5  309.86  4406.6  309.21  4496.7  306.87
  4511.4  305.61  4616.9  301.01    4687  296.71  4735.9  296.66  4796.3  296.58
  4865.7  294.94  4912.3  295.82  4951.4   296.2  4979.4  296.37  4990.1  293.49
  4995.6  290.99  4996.9  289.46  5004.8  289.46  5020.5  294.08  5032.8  295.86
    5289  296.66  5374.4  297.45  5392.8   298.4  5453.3  297.81  5478.3  298.57
  5513.9  297.36  5533.5  297.67  5594.1  299.67  5734.8  307.27  5780.2  308.22
#Mann= 9 ,-1 , 0
  4251.7     .11       0  4314.1     .17       0  4511.4     .11       0
  4735.9     .15       0  4796.3     .11       0  4912.3     .15       0
  4951.4     .11       0  4979.4     .06       0  5032.8     .11       0
Bank Sta=4979.4,5032.8
XS Rating Curve= 0 ,0
Exp/Cntr=0.3,0.1

Type RM Length L Ch R = 1 ,1596    ,996,996,996
BEGIN DESCRIPTION:
CCLC 086 2.0
END DESCRIPTION:
XS GIS Cut Line= 3
      3706717.89     10206061.07      3705962.17       10206029.
      3705567.85     10207561.07
#Sta/Elev= 30
  4243.6  310.42  4263.7  310.37  4353.7   307.1  4403.8  303.69  4583.9  295.02
  4714.1  294.93  4804.1  293.29  4897.3  293.67  4974.3  294.49  4984.3   293.6
  4994.3  290.85  4995.7  289.19  5003.7  289.19  5012.5  291.61  5032.7  293.07
  5037.8  294.64  5301.6  294.55  5373.9  293.87  5404.8  295.06  5456.5  294.99
  5480.5  293.78  5510.2   295.2  5556.8  294.89  5580.4  295.63  5859.2  296.91
  6040.1  303.28  6045.3  302.73    6138  305.23  6416.8  309.11    6582  312.32
#Mann= 5 ,-1 , 0
  4243.6     .11       0  4897.3     .15       0  4974.3     .09       0
  5037.8     .15       0  5510.2     .11       0
Bank Sta=4974.3,5037.8
XS Rating Curve= 0 ,0
Exp/Cntr=0.3,0.1

Type RM Length L Ch R = 1 ,600     ,0,0,0
BEGIN DESCRIPTION:
CCLC 086 1.0
END DESCRIPTION:
XS GIS Cut Line= 3
      3707167.87     10205261.07      3705167.31     10205675.83
      3705367.85     10207661.03
#Sta/Elev= 30
  2956.9  305.46  3272.8  300.98  3406.3  302.38  3428.3  301.73  3518.5  295.48
  3610.5  291.42  3724.2  293.62  3769.3  292.14  3960.2  290.52  4016.6  290.74
  4064.8  291.32  4215.6  291.09  4417.3  292.97  4427.5     292  4461.3  292.81
  4556.5  291.28  4774.8  290.04  4955.3  290.89  4989.2  290.21  5001.2  288.13
  5009.4  288.13  5015.3  290.21  5085.7  291.07  5252.8  290.24  5397.3  290.95
    5739  296.52  5839.5  299.26    6342  298.81  6673.7  306.36  6995.3  311.21
#Mann= 7 ,-1 , 0
  2956.9     .11       0  3960.2     .15       0  4016.6     .11       0
  4064.8     .15       0  4955.3     .11       0  4989.2     .06       0
  5015.3     .11       0
Bank Sta=4989.2,5015.3
XS Rating Curve= 0 ,0
Exp/Cntr=0.3,0.1

Chan Stop Cuts=-1
Use User Specified Reach Order=0
Composite Channel Slope=5