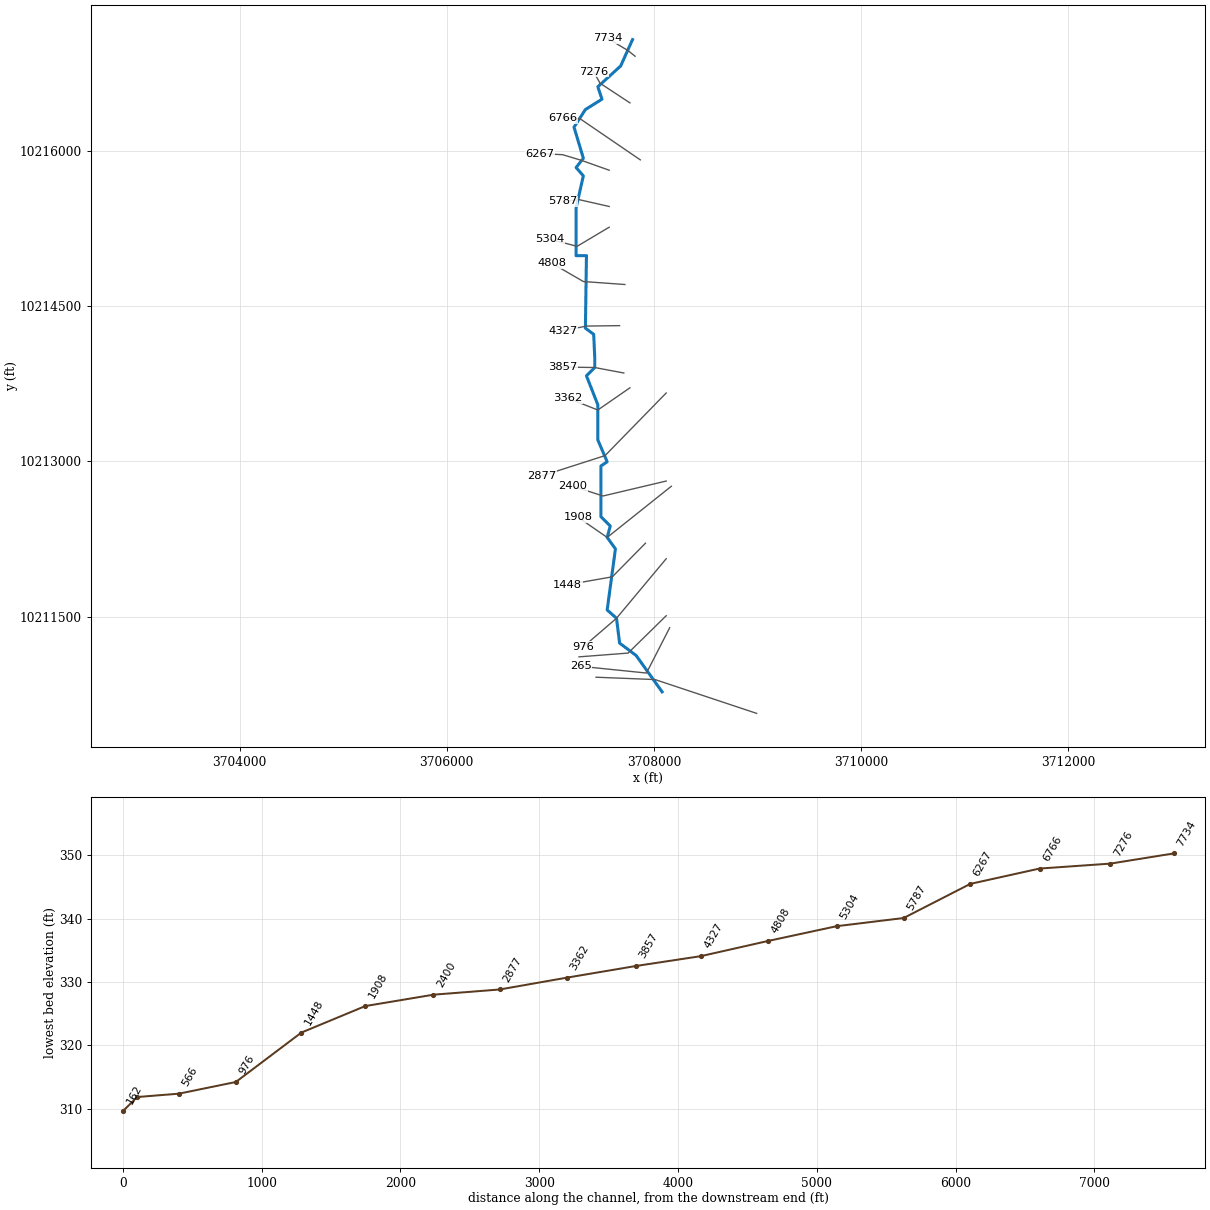
--- CCLC 087.prj (project) ---

Proj Title=CCLC 087 Base Level Engineering
Current Plan=p01
Default Exp/Contr=0.3,0.1
English Units
Geom File=g01
Flow File=f01
Flow File=f02
Plan File=p01
Y Axis Title=Elevation
X Axis Title(PF)=Main Channel Distance
X Axis Title(XS)=Station
BEGIN DESCRIPTION:
CCLC 087
END DESCRIPTION:
DSS Export Rating Curves= 0
DSS Export Rating Curve Sorted= 0
DSS Export Volume Flow Curves= 0
DXF OffsetX= 0
DXF OffsetY= 0
DXF ScaleX= 1
DXF ScaleY= 10

--- CCLC 087.p01 (plan) ---

Plan Title=Multiple Run
Short Identifier=Multiple
Geom File=g01
Flow File=f01
Subcritical Flow
K Sum by GR= 0
Std Step Tol= 0.01
Critical Tol= 0.01
Num of Std Step Trials= 20
Max Error Tol= 0.3
Flow Tol Ratio= 0.001
Split Flow NTrial= 30
Split Flow Tol= 0.02
Split Flow Ratio= 0.02
Log Output Level= 0
Friction Slope Method= 1
Unsteady Friction Slope Method= 2
Unsteady Bridges Friction Slope Method= 1
Parabolic Critical Depth
Global Vel Dist=  1 , 1 , 1
Global Log Level= 0
CheckData=True
Encroach Param= -1, 0, 0, 0
BEGIN DESCRIPTION:
Multiple Run
END DESCRIPTION:

--- CCLC 087.f01 (steady flow) ---

Flow Title=Multiple
Program Version=4.10
Number of Profiles= 7
Profile Names=10-year,25-year,50-year,1pct_min,100-year,1pct_plu,500-year
River Rch & RM=CCLC 087,Reach-1         ,7734
     527     712     959     426    1287    3887    2394
River Rch & RM=CCLC 087,Reach-1         ,6267
     716     979    1331     595    1798    5430    3390
River Rch & RM=CCLC 087,Reach-1         ,162
    1574    2238    3122    1428    4313   13025    8528
Boundary for River Rch & Prof#=CCLC 087,Reach-1         , 1
Up Type= 0
Dn Type= 3
Dn Slope=0.02
Boundary for River Rch & Prof#=CCLC 087,Reach-1         , 2
Up Type= 0
Dn Type= 3
Dn Slope=0.02
Boundary for River Rch & Prof#=CCLC 087,Reach-1         , 3
Up Type= 0
Dn Type= 3
Dn Slope=0.02
Boundary for River Rch & Prof#=CCLC 087,Reach-1         , 4
Up Type= 0
Dn Type= 3
Dn Slope=0.02
Boundary for River Rch & Prof#=CCLC 087,Reach-1         , 5
Up Type= 0
Dn Type= 3
Dn Slope=0.02
Boundary for River Rch & Prof#=CCLC 087,Reach-1         , 6
Up Type= 0
Dn Type= 3
Dn Slope=0.02
Boundary for River Rch & Prof#=CCLC 087,Reach-1         , 7
Up Type= 0
Dn Type= 3
Dn Slope=0.02
DSS Import GetInterval= 0
DSS Import GetPeak= 0
DSS Import FillOption= 0

--- CCLC 087.f02 (steady flow) ---

Flow Title=Orig_BLE_Flows
Program Version=4.10
Number of Profiles= 7
Profile Names=10-year,25-year,50-year,1pct_min,100-year,1pct_plu,500-year
River Rch & RM=CCLC 087,Reach-1         ,7734
     527     698     834     328     990    2990    1392
River Rch & RM=CCLC 087,Reach-1         ,6267
     716     960    1157     458    1383    4176    1971
River Rch & RM=CCLC 087,Reach-1         ,162
    1574    2194    2715    1099    3318   10021    4958
Boundary for River Rch & Prof#=CCLC 087,Reach-1         , 1
Up Type= 0
Dn Type= 3
Dn Slope=0.005
Boundary for River Rch & Prof#=CCLC 087,Reach-1         , 2
Up Type= 0
Dn Type= 3
Dn Slope=0.005
Boundary for River Rch & Prof#=CCLC 087,Reach-1         , 3
Up Type= 0
Dn Type= 3
Dn Slope=0.005
Boundary for River Rch & Prof#=CCLC 087,Reach-1         , 4
Up Type= 0
Dn Type= 3
Dn Slope=0.005
Boundary for River Rch & Prof#=CCLC 087,Reach-1         , 5
Up Type= 0
Dn Type= 3
Dn Slope=0.005
Boundary for River Rch & Prof#=CCLC 087,Reach-1         , 6
Up Type= 0
Dn Type= 3
Dn Slope=0.005
Boundary for River Rch & Prof#=CCLC 087,Reach-1         , 7
Up Type= 0
Dn Type= 3
Dn Slope=0.005
DSS Import GetInterval= 0
DSS Import GetPeak= 0
DSS Import FillOption= 0

--- CCLC 087.g01 (geometry) ---

Geom Title=Existing Conditions
Program Version=4.10

River Reach=CCLC 087        ,Reach-1
Reach XY= 30
      3707793.23     10217071.84      3707678.23     10216816.84
      3707458.23     10216616.84      3707498.23     10216496.84
      3707338.23     10216396.84      3707228.23     10216226.84
      3707318.23     10215926.84      3707248.23     10215836.84
      3707318.23     10215756.84      3707248.23     10215446.84
      3707248.23     10214986.84      3707348.23     10214986.84
      3707338.23     10214286.84      3707418.23     10214226.84
      3707428.23     10214006.84      3707428.23     10213906.84
      3707348.23     10213826.84      3707458.23     10213546.84
      3707458.23     10213206.84      3707548.23     10212996.84
      3707488.23     10212956.84      3707488.23     10212466.84
      3707578.23     10212376.84      3707548.23     10212266.84
      3707628.23     10212156.84      3707548.23     10211566.84
      3707638.23     10211486.84      3707668.23     10211246.84
      3707828.23     10211126.84      3708078.23     10210776.84

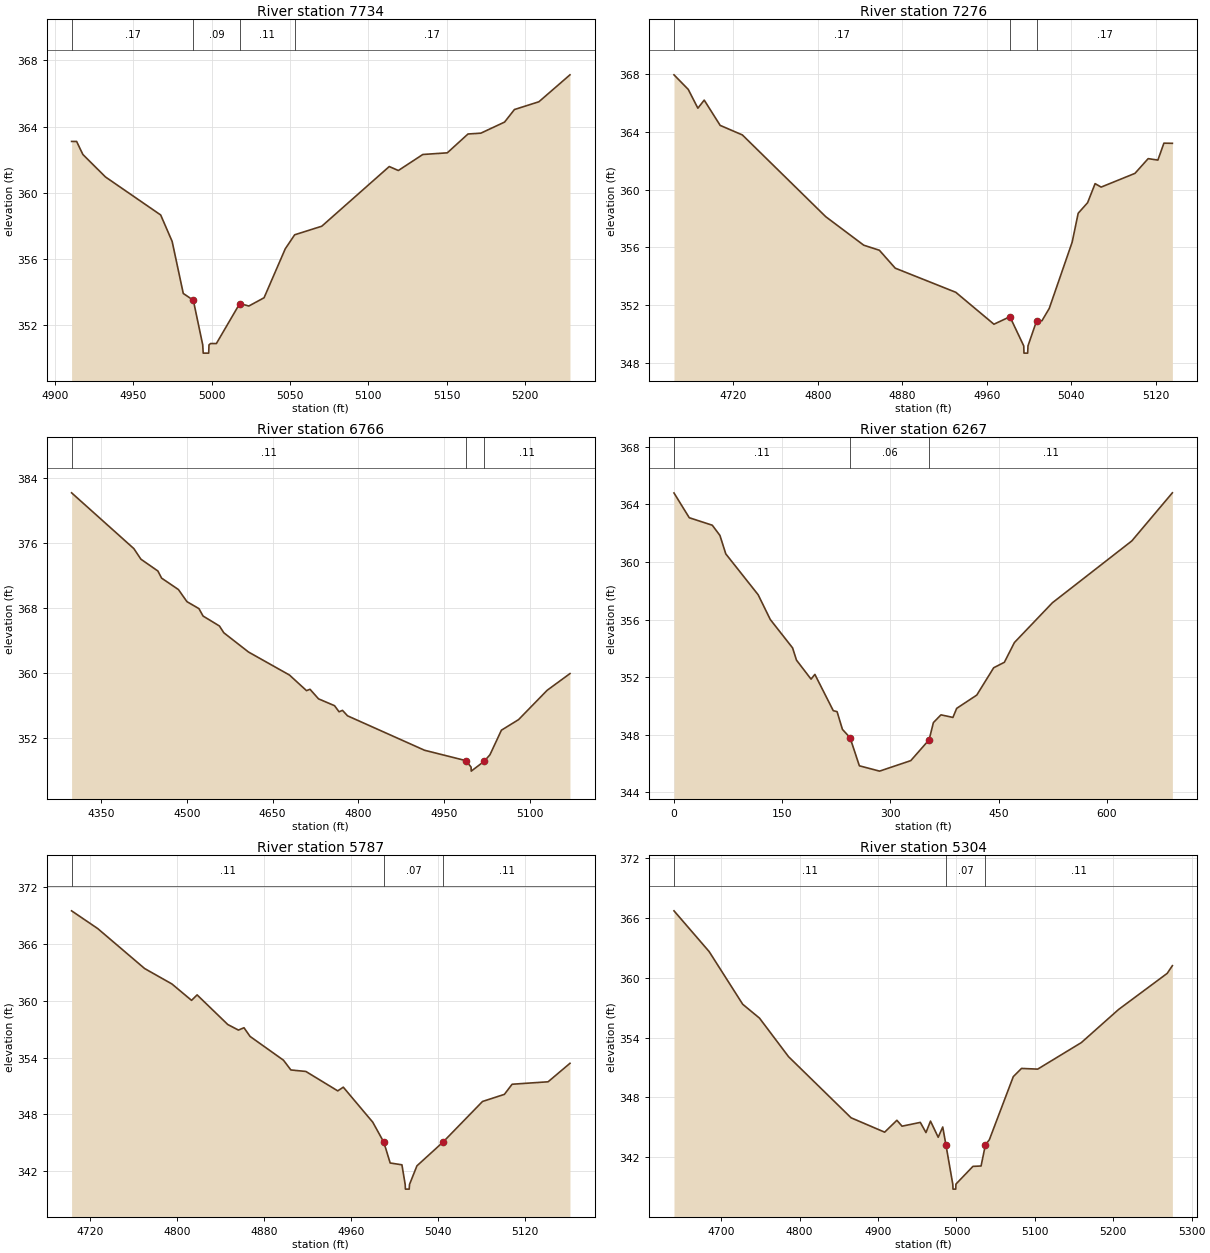
Type RM Length L Ch R = 1 ,7734    ,458,458,458
BEGIN DESCRIPTION:
CCLC 087 16.0
END DESCRIPTION:
XS GIS Cut Line= 3
      3707817.85     10216911.08      3707748.23     10216966.84
      3707552.05       10217084.
#Sta/Elev= 30
  4910.8   363.1    4914   363.1    4918  362.31  4932.4  360.95  4967.6  358.65
  4974.9  357.05    4982   353.9  4988.4  353.49  4994.4  350.79  4994.7  350.29
  4998.2  350.29  4998.4  350.79  4999.4  350.87  5003.1  350.87    5018  353.29
  5023.8  353.14  5033.5  353.64    5047   356.6    5053  357.45  5070.3  357.97
  5113.3  361.58  5119.1  361.34  5134.7  362.31  5150.3  362.41  5163.5  363.55
  5171.7   363.6  5186.8  364.27  5193.1  365.03  5208.7   365.5  5228.5  367.13
#Mann= 4 ,-1 , 0
  4910.8     .17       0  4988.4     .09       0    5018     .11       0
    5053     .17       0
Bank Sta=4988.4,5018
XS Rating Curve= 0 ,0
Exp/Cntr=0.3,0.1

Type RM Length L Ch R = 1 ,7276    ,510,510,510
BEGIN DESCRIPTION:
CCLC 087 15.0
END DESCRIPTION:
XS GIS Cut Line= 3
      3707767.84     10216461.08      3707479.61     10216650.72
      3707417.84     10216761.09
#Sta/Elev= 30
    4664  367.94  4677.5  366.93  4686.6  365.63  4692.6  366.19  4707.7  364.44
  4728.7  363.78  4807.6  358.12  4843.5  356.15  4858.3   355.8  4873.3  354.56
  4930.6  352.89  4966.7  350.68  4981.8   351.2  4994.9  349.18  4995.1  348.68
  4998.6  348.68  4998.9  349.18  5007.1  350.92  5012.1  350.92    5019  351.77
  5040.7  356.36  5046.4  358.36  5055.3  359.09  5062.4  360.41  5068.1  360.17
  5100.1  361.12  5112.6  362.14  5121.8  362.04  5127.5  363.21  5135.5   363.2
#Mann= 3 , 0 , 0
    4664     .17       0  4981.8     .09       0  5007.1     .17       0
Bank Sta=4981.8,5007.1
XS Rating Curve= 0 ,0
Exp/Cntr=0.3,0.1

Type RM Length L Ch R = 1 ,6766    ,499,499,499
BEGIN DESCRIPTION:
CCLC 087 14.0
END DESCRIPTION:
XS GIS Cut Line= 3
      3707867.89     10215911.04      3707288.23     10216306.84
      3707117.88     10216311.07
#Sta/Elev= 30
  4298.1  382.17  4407.1   375.3  4419.4     374  4449.2  372.54  4455.6  371.67
  4485.1  370.26    4500  368.77    4521  367.91  4528.2     367  4556.9  365.77
  4564.5  364.94  4607.7  362.57  4679.5  359.73  4709.3  357.81  4715.4  357.98
  4730.3   356.8  4758.3  355.96  4766.2  355.21  4772.3  355.38  4781.1  354.71
  4915.9  350.47  4988.3  349.19  4997.3   348.4  4997.6   347.9  5020.4  349.12
  5030.4  349.92  5050.4  352.94  5080.4  354.24  5130.4  357.85  5170.4  359.91
#Mann= 3 , 0 , 0
  4298.1     .11       0  4988.3     .06       0  5020.4     .11       0
Bank Sta=4988.3,5020.4
XS Rating Curve= 0 ,0
Exp/Cntr=0.3,0.1

Type RM Length L Ch R = 1 ,6267    ,480,480,480
BEGIN DESCRIPTION:
CCLC 087 13.0
END DESCRIPTION:
XS GIS Cut Line= 4
      3707567.85     10215811.07      3707298.23     10215906.84
      3707117.85     10215961.07      3706900.54      10215971.4
#Sta/Elev= 30
       0   364.8    21.2  363.08    53.1  362.56    63.7  361.85    71.8  360.57
   116.7  357.73   133.5  356.01   164.4  354.04   169.8  353.19     190  351.87
   195.3   352.2   220.8  349.68   226.1  349.61   233.5  348.38   244.1   347.8
     257  345.85     285  345.48   328.3  346.21   353.7  347.66   359.6  348.85
   370.1  349.39   386.7  349.21   391.9  349.84   419.7  350.76   443.2  352.66
     458  353.04   471.9  354.41   524.5  357.17   634.7  361.47   690.9  364.81
#Mann= 3 ,-1 , 0
       0     .11       0   244.1     .06       0   353.7     .11       0
Bank Sta=244.1,353.7
XS Rating Curve= 0 ,0
Exp/Cntr=0.3,0.1

Type RM Length L Ch R = 1 ,5787    ,483,483,483
BEGIN DESCRIPTION:
CCLC 087 12.0
END DESCRIPTION:
XS GIS Cut Line= 3
      3707567.86     10215461.07      3707278.23     10215526.84
       3707117.8     10215511.07
#Sta/Elev= 30
    4703   369.5  4727.1  367.62  4770.2   363.4  4795.3  361.77  4813.3  360.04
  4818.4  360.62  4846.6  357.49  4856.4   356.9  4861.5  357.15  4867.1  356.23
  4897.8  353.72  4904.6  352.69  4918.4  352.53  4947.7  350.48  4952.8  350.87
  4979.9  347.17  4990.1  345.05  4995.9  342.86  5006.7  342.67  5009.7   340.6
  5009.9   340.1  5013.4   340.1  5013.7   340.6  5020.5  342.56  5044.5345.0708
  5080.8  349.36  5100.9  350.11    5108  351.18  5141.1  351.44  5161.2  353.39
#Mann= 3 , 0 , 0
    4703     .11       0  4990.1     .07       0  5044.5     .11       0
Bank Sta=4990.1,5044.5
XS Rating Curve= 0 ,0
Exp/Cntr=0.3,0.1

Type RM Length L Ch R = 1 ,5304    ,496,496,496
BEGIN DESCRIPTION:
CCLC 087 11.0
END DESCRIPTION:
XS GIS Cut Line= 3
      3707567.86     10215261.08      3707258.23     10215076.84
      3706991.44     10215145.15
#Sta/Elev= 30
  4639.7  366.71  4684.5  362.63  4727.4  357.34  4748.8  355.95  4785.8  352.09
  4865.6  345.96  4908.4  344.52    4924  345.71  4930.6  345.12  4953.9   345.5
  4961.1  344.48  4966.9  345.63  4976.7  344.01  4982.5  345.04 4986.51343.2706
  4995.3  339.31  4995.6  338.81  4999.1  338.81  4999.3  339.31    5021  341.09
  5031.4  341.13  5036.9  343.24    5042  343.77  5072.5  350.09    5083  350.91
  5103.6  350.84  5159.3   353.5  5206.8  356.82  5268.8  360.44  5275.4  361.21
#Mann= 3 ,-1 , 0
  4639.7     .11       0 4986.51     .07       0  5036.9     .11       0
Bank Sta=4986.51,5036.9
XS Rating Curve= 0 ,0
Exp/Cntr=0.3,0.1

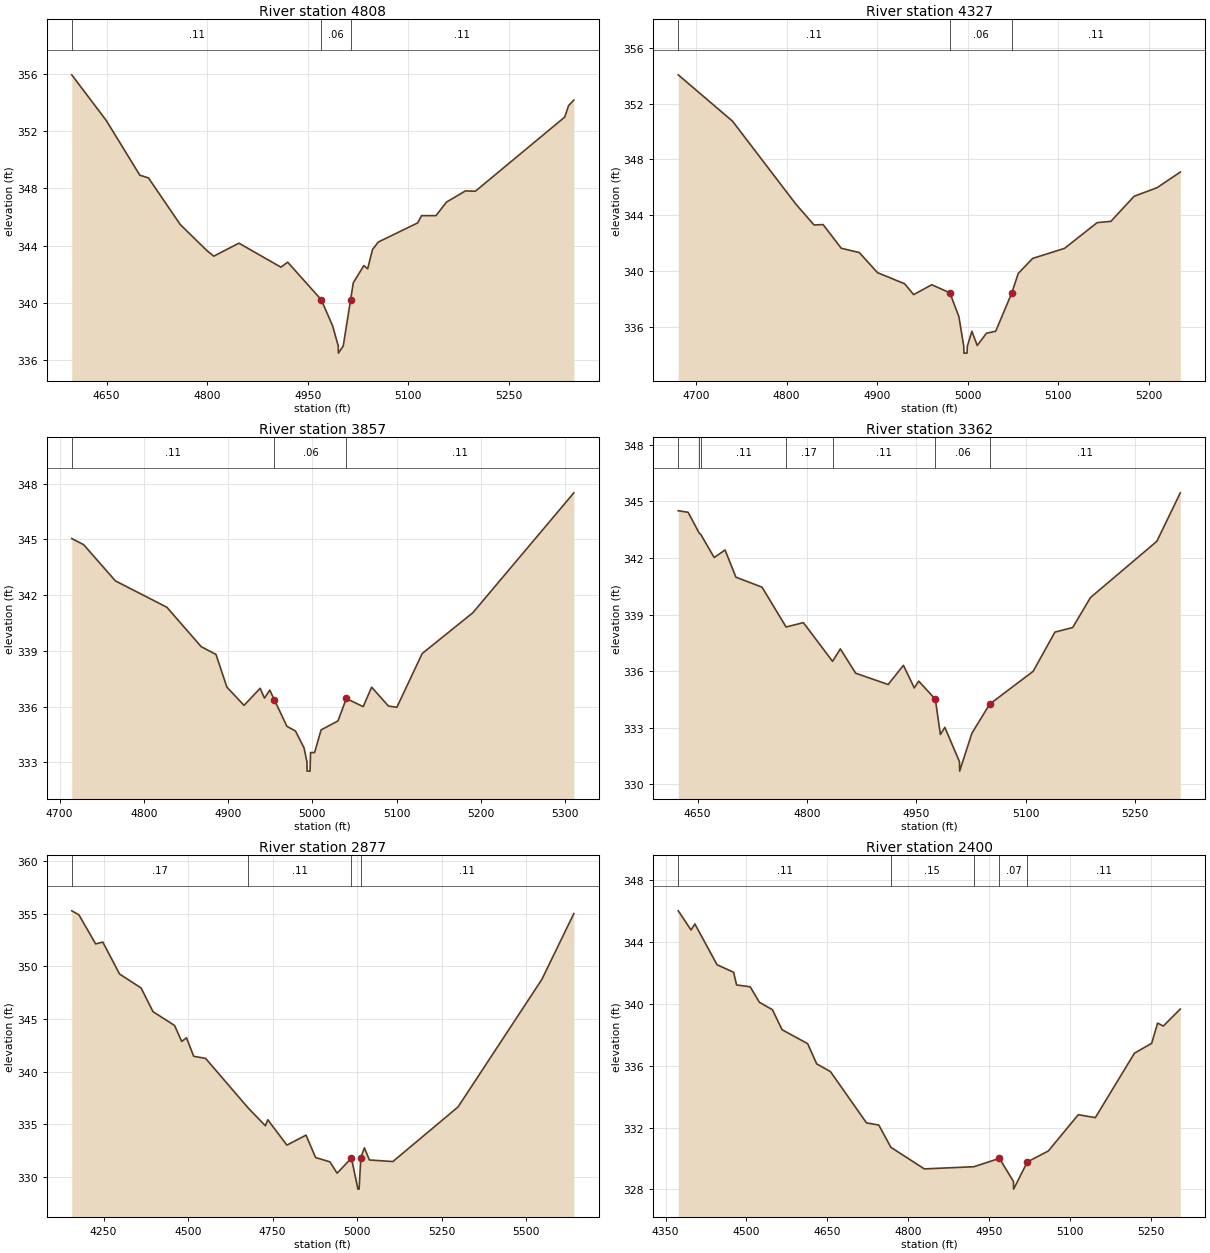
Type RM Length L Ch R = 1 ,4808    ,481,481,481
BEGIN DESCRIPTION:
CCLC 087 10.0
END DESCRIPTION:
XS GIS Cut Line= 3
      3707719.19     10214708.01      3707318.23     10214736.84
      3707017.89     10214911.05
#Sta/Elev= 30
    4598  355.96  4649.5  352.76  4699.6  348.93  4712.5  348.74  4759.8  345.48
  4799.9  343.64  4809.9  343.26  4847.4  344.17  4910.1  342.49  4920.2  342.84
  4970.3  340.21  4987.3  338.37  4995.7  336.97  4995.9  336.47  5003.1  336.97
 5014.08340.2127  5018.1   341.4  5033.8   342.6  5039.6  342.38  5046.7  343.72
  5055.4  344.25  5114.2  345.59  5119.9   346.1  5141.5   346.1  5157.2  347.05
  5185.4  347.83  5200.3  347.81  5333.6     353  5339.4  353.81  5347.2  354.19
#Mann= 3 , 0 , 0
    4598     .11       0  4970.3     .06       0 5014.08     .11       0
Bank Sta=4970.3,5014.08
XS Rating Curve= 0 ,0
Exp/Cntr=0.3,0.1

Type RM Length L Ch R = 1 ,4327    ,470,470,470
BEGIN DESCRIPTION:
CCLC 087 9.0
END DESCRIPTION:
XS GIS Cut Line= 3
       3707667.8     10214311.07      3707348.23     10214306.84
      3707117.83     10214261.07
#Sta/Elev= 30
  4680.4  354.07  4740.4  350.74  4810.4  344.78  4830.4  343.29  4840.4  343.32
  4860.4  341.62  4880.4  341.31  4900.4  339.87  4930.4  339.07  4940.4  338.29
  4960.4     339  4980.4  338.42  4990.4   336.7  4995.7  334.59  4995.9  334.09
  4999.4  334.09  4999.7  334.59  5004.7  335.66  5010.6  334.64  5020.8  335.52
    5031  335.66 5048.72338.3987  5055.9  339.81  5071.8  340.89    5107  341.61
  5143.1  343.46  5158.2  343.55  5183.9  345.35  5209.3  345.97  5234.9  347.09
#Mann= 3 , 0 , 0
  4680.4     .11       0  4980.4     .06       0 5048.72     .11       0
Bank Sta=4980.4,5048.72
XS Rating Curve= 0 ,0
Exp/Cntr=0.3,0.1

Type RM Length L Ch R = 1 ,3857    ,495,495,495
BEGIN DESCRIPTION:
CCLC 087 8.0
END DESCRIPTION:
XS GIS Cut Line= 3
      3707708.77     10213853.85      3707428.23     10213906.84
      3707117.86     10213911.07
#Sta/Elev= 30
  4714.5  345.05  4728.6  344.72  4766.3  342.77  4827.4  341.35  4868.1  339.23
  4885.7  338.81  4898.6  337.05    4919  336.07  4938.1  336.99  4943.2  336.46
  4949.5  336.89 4954.86336.3777  4969.9  334.94    4980  334.69  4990.2  333.78
  4993.6  333.03  4993.8  332.53  4997.3  332.53  4997.9  333.53  5002.7  333.53
  5010.4  334.75  5030.4  335.23  5040.4  336.44  5060.4     336  5070.4  337.05
  5090.4  336.03  5100.4  335.97  5130.4  338.86  5190.4  341.05  5310.4  347.51
#Mann= 3 , 0 , 0
  4714.5     .11       0 4954.86     .06       0  5040.4     .11       0
Bank Sta=4954.86,5040.4
XS Rating Curve= 0 ,0
Exp/Cntr=0.3,0.1

Type RM Length L Ch R = 1 ,3362    ,485,485,485
BEGIN DESCRIPTION:
CCLC 087 7.0
END DESCRIPTION:
XS GIS Cut Line= 3
      3707767.84     10213711.07      3707458.23     10213496.84
      3707167.89     10213611.06
#Sta/Elev= 30
  4623.5   344.5    4637  344.42  4652.2  343.32  4654.5  343.24  4672.8  342.02
  4687.7  342.42  4702.6  340.98  4738.4  340.45  4771.4  338.34  4795.1  338.57
  4835.1  336.52  4845.8  337.18  4866.8  335.89  4911.4  335.29  4932.3  336.31
  4947.2  335.11  4953.3  335.47  4976.1  334.51    4983  332.64  4989.1  333.02
  5009.2   331.2  5009.4   330.7  5026.2  332.71  5050.6  334.25  5110.2  335.99
  5140.1  338.07  5164.4  338.31  5188.8   339.9  5279.8  342.88    5312  345.45
#Mann= 7 ,-1 , 0
  4623.5     .11       0  4652.2     .17       0  4654.5     .11       0
  4771.4     .17       0  4835.1     .11       0  4976.1     .06       0
  5050.6     .11       0
Bank Sta=4976.1,5050.6
XS Rating Curve= 0 ,0
Exp/Cntr=0.3,0.1

Type RM Length L Ch R = 1 ,2877    ,477,477,477
BEGIN DESCRIPTION:
CCLC 087 6.0
END DESCRIPTION:
XS GIS Cut Line= 3
      3708117.82     10213661.04      3707528.23     10213056.84
      3706917.86     10212861.07
#Sta/Elev= 30
  4155.8  355.27    4177  354.89  4226.4  352.13  4247.7   352.3  4297.1  349.27
  4360.9  347.94  4396.1  345.69  4459.9  344.38    4481  342.86  4495.2  343.21
  4516.5  341.45  4551.7  341.25  4678.2  336.52  4728.6  334.85  4735.6  335.42
  4792.2  333.01  4848.8  333.96  4877.1  331.83  4919.5  331.42  4940.7  330.34
  4983.1  331.78  5002.3  328.83  5005.8  328.83  5010.9  331.83  5021.4  332.75
  5036.2   331.6  5105.7  331.45  5298.5  336.64  5546.5  348.76    5641  355.01
#Mann= 4 ,-1 , 0
  4155.8     .17       0  4678.2     .11       0  4983.1     .07       0
  5010.9     .11       0
Bank Sta=4983.1,5010.9
XS Rating Curve= 0 ,0
Exp/Cntr=0.3,0.1

Type RM Length L Ch R = 1 ,2400    ,492,492,492
BEGIN DESCRIPTION:
CCLC 087 5.0
END DESCRIPTION:
XS GIS Cut Line= 3
       3708117.9     10212811.08      3707508.23     10212666.84
      3707217.84     10212761.08
#Sta/Elev= 30
  4373.5  346.03  4397.3  344.79  4404.4  345.18  4445.5  342.54  4476.3  342.05
  4481.8  341.23  4507.1  341.11  4524.1  340.11  4548.2  339.63  4566.3  338.33
  4613.7  337.43  4630.5  336.12    4656  335.62  4722.9   332.3  4745.7  332.16
  4768.1  330.72  4830.2  329.32  4922.2  329.46  4969.6     330  4995.6  328.51
  4995.9  328.01  5021.4  329.77  5060.3  330.48    5116  332.83  5147.6  332.64
  5220.1  336.81  5252.1  337.45  5263.2  338.76  5273.7  338.57  5305.3  339.67
#Mann= 5 ,-1 , 0
  4373.5     .11       0  4768.1     .15       0  4922.2     .11       0
  4969.6     .07       0  5021.4     .11       0
Bank Sta=4969.6,5021.4
XS Rating Curve= 0 ,0
Exp/Cntr=0.3,0.1

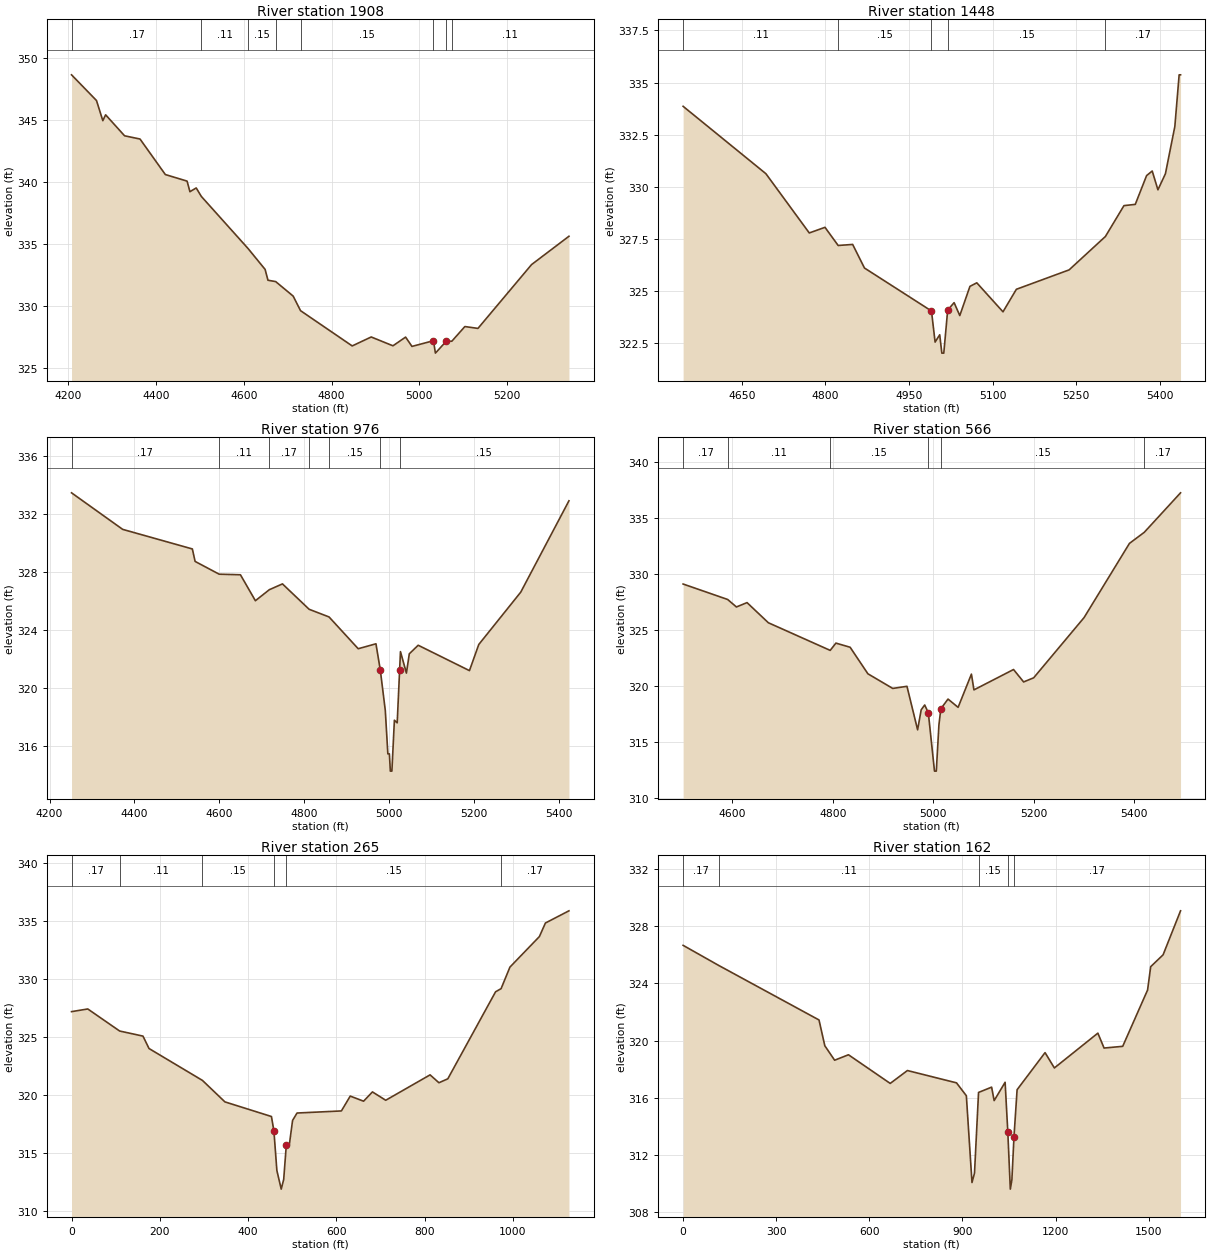
Type RM Length L Ch R = 1 ,1908    ,460,460,460
BEGIN DESCRIPTION:
CCLC 087 4.0
END DESCRIPTION:
XS GIS Cut Line= 3
      3708167.86     10212761.08      3707548.23     10212266.84
      3707267.84     10212461.08
#Sta/Elev= 30
  4207.4  348.62  4264.3  346.55  4278.7  344.93  4285.1   345.4  4328.3  343.71
  4363.5  343.45  4421.2  340.59  4470.8  340.06  4477.2  339.21  4491.6  339.51
  4503.2  338.83  4609.8  334.63  4648.6  332.95  4655.1  332.08  4672.7  331.97
  4712.6   330.8  4729.3  329.63  4847.1  326.79  4890.4  327.51    4940   326.8
  4968.8   327.5  4983.3  326.75  5032.3  327.21  5036.7  326.21  5061.3  327.16
  5074.2  327.17  5103.9  328.35  5133.7   328.2  5255.9  333.34  5341.1  335.62
#Mann= 8 ,-1 , 0
  4207.4     .17       0  4503.2     .11       0  4609.8     .15       0
  4672.7     .11       0  4729.3     .15       0  5032.3     .09       0
  5061.3     .15       0  5074.2     .11       0
Bank Sta=5032.3,5061.3
XS Rating Curve= 0 ,0
Exp/Cntr=0.3,0.1

Type RM Length L Ch R = 1 ,1448    ,472,472,472
BEGIN DESCRIPTION:
CCLC 087 3.0
END DESCRIPTION:
XS GIS Cut Line= 3
      3707917.86     10212211.08      3707598.23     10211886.84
      3707167.85     10211811.07
#Sta/Elev= 30
  4544.7  333.86  4693.2  330.63    4771  327.79  4799.2  328.06  4822.8  327.19
  4848.8  327.24    4870  326.11  4990.2  324.05  4996.7  322.56    5005  322.91
  5008.8  322.03  5012.3  322.03 5019.27324.0904  5030.8  324.45    5041  323.83
  5059.2  325.23  5071.5   325.4  5118.5  324.01  5142.5  325.09  5237.1  326.02
  5302.2  327.62  5335.5   329.1  5355.8  329.16  5376.1  330.54  5386.2  330.76
  5396.4  329.86  5409.9  330.63  5426.8   332.9  5434.5  335.37    5437  335.37
#Mann= 5 ,-1 , 0
  4544.7     .11       0  4822.8     .15       0  4990.2     .09       0
 5019.27     .15       0  5302.2     .17       0
Bank Sta=4990.2,5019.27
XS Rating Curve= 0 ,0
Exp/Cntr=0.3,0.1

Type RM Length L Ch R = 1 ,976     ,410,410,410
BEGIN DESCRIPTION:
CCLC 087 2.0
END DESCRIPTION:
XS GIS Cut Line= 3
      3708117.86     10212061.09      3707638.23     10211486.84
      3707317.87     10211211.09
#Sta/Elev= 30
  4251.8  333.43  4372.2  330.91  4536.2  329.56  4542.7   328.7  4599.3  327.82
  4649.4  327.78  4684.6  325.99  4717.4  326.75  4748.3  327.15  4811.1   325.4
    4858  324.87  4926.6  322.68  4968.4  323.02 4978.66321.2038  4990.4  318.42
  4996.4  315.43    5000  315.43  5002.3  314.24  5005.9  314.24  5011.8  317.75
  5018.4  317.57 5024.07321.1854  5026.1  322.48  5040.1     321  5046.9  322.33
  5067.8  322.92  5188.5  321.17  5210.4  322.97  5309.2  326.58  5422.7  332.88
#Mann= 7 ,-1 , 0
  4251.8     .17       0  4599.3     .11       0  4717.4     .17       0
  4811.1     .11       0    4858     .15       0 4978.66     .09       0
 5024.07     .15       0
Bank Sta=4978.66,5024.07
XS Rating Curve= 0 ,0
Exp/Cntr=0.3,0.1

Type RM Length L Ch R = 1 ,566     ,301,301,301
BEGIN DESCRIPTION:
CCLC 087 1.0
END DESCRIPTION:
XS GIS Cut Line= 3
      3708117.84     10211511.06      3707750.44     10211150.72
      3707276.45     10211114.26
#Sta/Elev= 30
  4502.3  329.12  4590.9  327.74  4608.4  327.07  4629.5  327.46  4671.9  325.66
    4795  323.19  4806.4  323.84  4834.7  323.47    4870   321.1  4919.5  319.79
  4947.8  319.98    4969  316.09  4976.1  317.88  4983.1  318.31  4990.3  317.62
  5002.6   312.4  5006.2   312.4  5011.4  316.52  5015.2  317.97  5029.5  318.84
  5049.6   318.1  5076.1  321.07  5081.1  319.66  5159.9  321.48    5180  320.37
    5200  320.74  5300.3  326.12  5390.6  332.75  5420.1  333.74  5492.3  337.27
#Mann= 6 ,-1 , 0
  4502.3     .17       0  4590.9     .11       0    4795     .15       0
  4990.3     .09       0  5015.2     .15       0  5420.1     .17       0
Bank Sta=4990.3,5015.2
XS Rating Curve= 0 ,0
Exp/Cntr=0.3,0.1

Type RM Length L Ch R = 1 ,265     ,103,103,103
BEGIN DESCRIPTION:
CCLC 087 1.0
END DESCRIPTION:
XS GIS Cut Line= 3
      3708151.55     10211395.14      3707927.53     10210958.01
      3707294.78     10211022.74
#Sta/Elev= 30
       0  327.17    36.8   327.4     109   325.5   161.9  325.06   175.6  323.99
   296.7  321.24   347.6  319.39     453  318.13   458.6  316.89   465.3  313.48
   475.2  311.87   480.8  312.71   486.7  315.68   493.5  315.68   500.9  317.79
     511  318.43   611.5  318.61   631.6  319.89   661.8  319.45   681.9  320.25
     712  319.53   812.5  321.72   832.6  321.04   852.7  321.38   960.9  328.88
   973.4  329.15   993.5  331.01  1060.2  333.64  1073.9  334.81  1127.2  335.86
#Mann= 6 ,-1 , 0
       0     .17       0     109     .11       0   296.7     .15       0
   458.6     .09       0   486.7     .15       0   973.4     .17       0
Bank Sta=458.6,486.7
XS Rating Curve= 0 ,0
Exp/Cntr=0.3,0.1

Type RM Length L Ch R = 1 ,162     ,0,0,0
BEGIN DESCRIPTION:
CCLC 087 1.0
END DESCRIPTION:
XS GIS Cut Line= 3
      3708990.96     10210568.75      3708010.06     10210895.14
      3707440.61     10210917.71
#Sta/Elev= 30
       0  326.65   116.1  325.23   437.8  321.44   456.5  319.64   488.1  318.63
   532.7  319.01   667.2  317.01   722.6  317.91   880.8  317.05   912.5  316.15
   930.7  310.09   938.8  310.75   951.8  316.38   993.9  316.75  1002.1  315.81
  1037.4  317.09    1046  313.65  1054.2  309.63  1059.2  310.28    1066  313.29
    1076  316.57  1166.1  319.16  1196.1  318.09  1336.2  320.52  1356.2  319.48
  1416.3   319.6  1496.4  323.53  1506.4  325.16  1546.4  325.99  1602.6  329.06
#Mann= 5 ,-1 , 0
       0     .17       0   116.1     .11       0   951.8     .15       0
    1046     .09       0    1066     .17       0
Bank Sta=1046,1066
XS Rating Curve= 0 ,0
Exp/Cntr=0.3,0.1

Chan Stop Cuts=-1
Use User Specified Reach Order=0
Composite Channel Slope=5