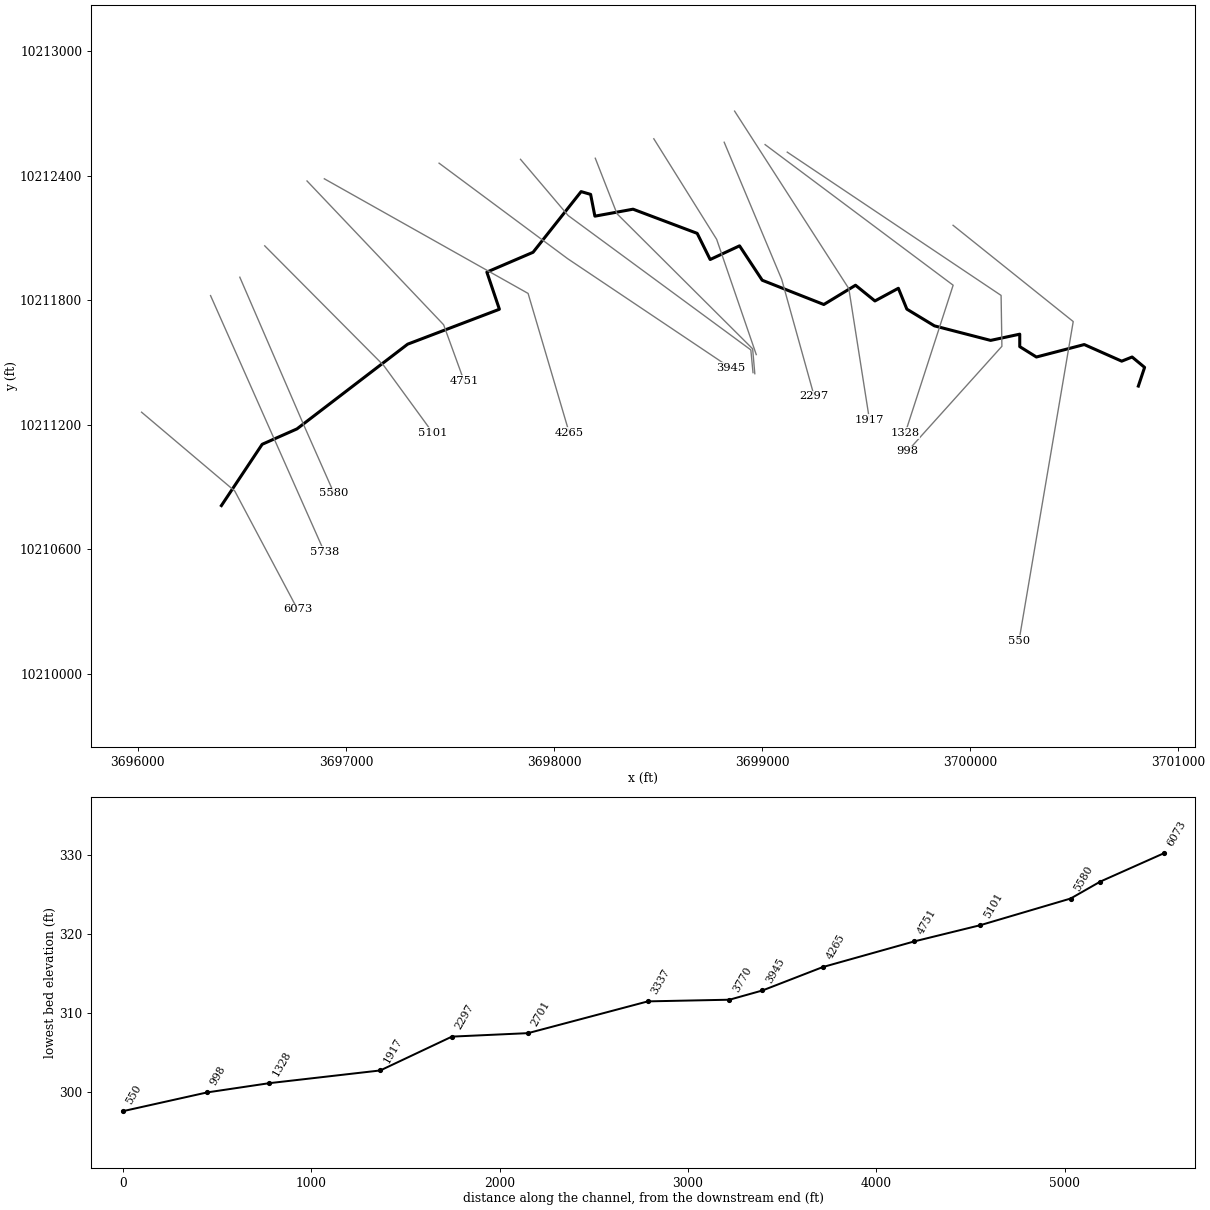
--- CCLC 088.prj (project) ---

Proj Title=CCLC 088 Base Level Engineering
Current Plan=p01
Default Exp/Contr=0.3,0.1
English Units
Geom File=g01
Flow File=f01
Flow File=f02
Plan File=p01
Y Axis Title=Elevation
X Axis Title(PF)=Main Channel Distance
X Axis Title(XS)=Station
BEGIN DESCRIPTION:
CCLC 088
END DESCRIPTION:
DSS Export Rating Curves= 0
DSS Export Rating Curve Sorted= 0
DSS Export Volume Flow Curves= 0
DXF OffsetX= 0
DXF OffsetY= 0
DXF ScaleX= 1
DXF ScaleY= 10

--- CCLC 088.p01 (plan) ---

Plan Title=Multiple Run
Short Identifier=Multiple
Geom File=g01
Flow File=f01
Subcritical Flow
K Sum by GR= 0
Std Step Tol= 0.01
Critical Tol= 0.01
Num of Std Step Trials= 20
Max Error Tol= 0.3
Flow Tol Ratio= 0.001
Split Flow NTrial= 30
Split Flow Tol= 0.02
Split Flow Ratio= 0.02
Log Output Level= 0
Friction Slope Method= 1
Unsteady Friction Slope Method= 2
Unsteady Bridges Friction Slope Method= 1
Parabolic Critical Depth
Global Vel Dist=  1 , 1 , 1
Global Log Level= 0
CheckData=True
Encroach Param= -1, 0, 0, 0
BEGIN DESCRIPTION:
Multiple Run
END DESCRIPTION:

--- CCLC 088.f01 (steady flow) ---

Flow Title=Multiple
Program Version=4.10
Number of Profiles= 7
Profile Names=10-year,25-year,50-year,1pct_min,100-year,1pct_plu,500-year
River Rch & RM=CCLC 088,Reach-1         ,6073
     584     796    1079     481    1453    4388    2731
River Rch & RM=CCLC 088,Reach-1         ,3337
     718     987    1348     605    1827    5517    3474
Boundary for River Rch & Prof#=CCLC 088,Reach-1         , 1
Up Type= 0
Dn Type= 3
Dn Slope=0.005
Boundary for River Rch & Prof#=CCLC 088,Reach-1         , 2
Up Type= 0
Dn Type= 3
Dn Slope=0.005
Boundary for River Rch & Prof#=CCLC 088,Reach-1         , 3
Up Type= 0
Dn Type= 3
Dn Slope=0.005
Boundary for River Rch & Prof#=CCLC 088,Reach-1         , 4
Up Type= 0
Dn Type= 3
Dn Slope=0.005
Boundary for River Rch & Prof#=CCLC 088,Reach-1         , 5
Up Type= 0
Dn Type= 3
Dn Slope=0.005
Boundary for River Rch & Prof#=CCLC 088,Reach-1         , 6
Up Type= 0
Dn Type= 3
Dn Slope=0.005
Boundary for River Rch & Prof#=CCLC 088,Reach-1         , 7
Up Type= 0
Dn Type= 3
Dn Slope=0.005
DSS Import GetInterval= 0
DSS Import GetPeak= 0
DSS Import FillOption= 0

--- CCLC 088.f02 (steady flow) ---

Flow Title=Orig_BLE_Flows
Program Version=4.10
Number of Profiles= 7
Profile Names=10-year,25-year,50-year,1pct_min,100-year,1pct_plu,500-year
River Rch & RM=CCLC 088,Reach-1         ,6073
     584     780     938     370    1118    3377    1588
River Rch & RM=CCLC 088,Reach-1         ,3337
     718     968    1172     465    1405    4244    2020
Boundary for River Rch & Prof#=CCLC 088,Reach-1         , 1
Up Type= 0
Dn Type= 3
Dn Slope=0.005
Boundary for River Rch & Prof#=CCLC 088,Reach-1         , 2
Up Type= 0
Dn Type= 3
Dn Slope=0.005
Boundary for River Rch & Prof#=CCLC 088,Reach-1         , 3
Up Type= 0
Dn Type= 3
Dn Slope=0.005
Boundary for River Rch & Prof#=CCLC 088,Reach-1         , 4
Up Type= 0
Dn Type= 3
Dn Slope=0.005
Boundary for River Rch & Prof#=CCLC 088,Reach-1         , 5
Up Type= 0
Dn Type= 3
Dn Slope=0.005
Boundary for River Rch & Prof#=CCLC 088,Reach-1         , 6
Up Type= 0
Dn Type= 3
Dn Slope=0.005
Boundary for River Rch & Prof#=CCLC 088,Reach-1         , 7
Up Type= 0
Dn Type= 3
Dn Slope=0.005
DSS Import GetInterval= 0
DSS Import GetPeak= 0
DSS Import FillOption= 0

--- CCLC 088.g01 (geometry) ---

Geom Title=Existing Conditions
Program Version=4.10

River Reach=CCLC 088        ,Reach-1
Reach XY= 30
      3696401.55     10210811.29      3696597.49     10211106.45
      3696764.55     10211180.56      3697296.57     10211588.63
      3697737.53     10211756.82      3697677.24     10211935.73
      3697899.33     10212031.21      3698130.24      10212323.4
      3698175.92     10212310.07      3698196.39     10212205.14
      3698379.83      10212238.7      3698688.12      10212122.3
      3698750.46     10211996.34      3698891.59     10212062.25
      3699000.63     10211896.56      3699296.62     10211779.69
      3699449.03     10211872.46      3699542.27     10211796.79
      3699654.85     10211857.81      3699695.68     10211757.44
      3699828.23     10211676.84      3700098.23     10211606.84
      3700238.23     10211636.84      3700238.23     10211576.84
      3700318.23     10211526.84      3700548.23     10211586.84
      3700728.23     10211506.84      3700778.23     10211526.84
      3700838.23     10211476.84      3700808.23     10211386.84

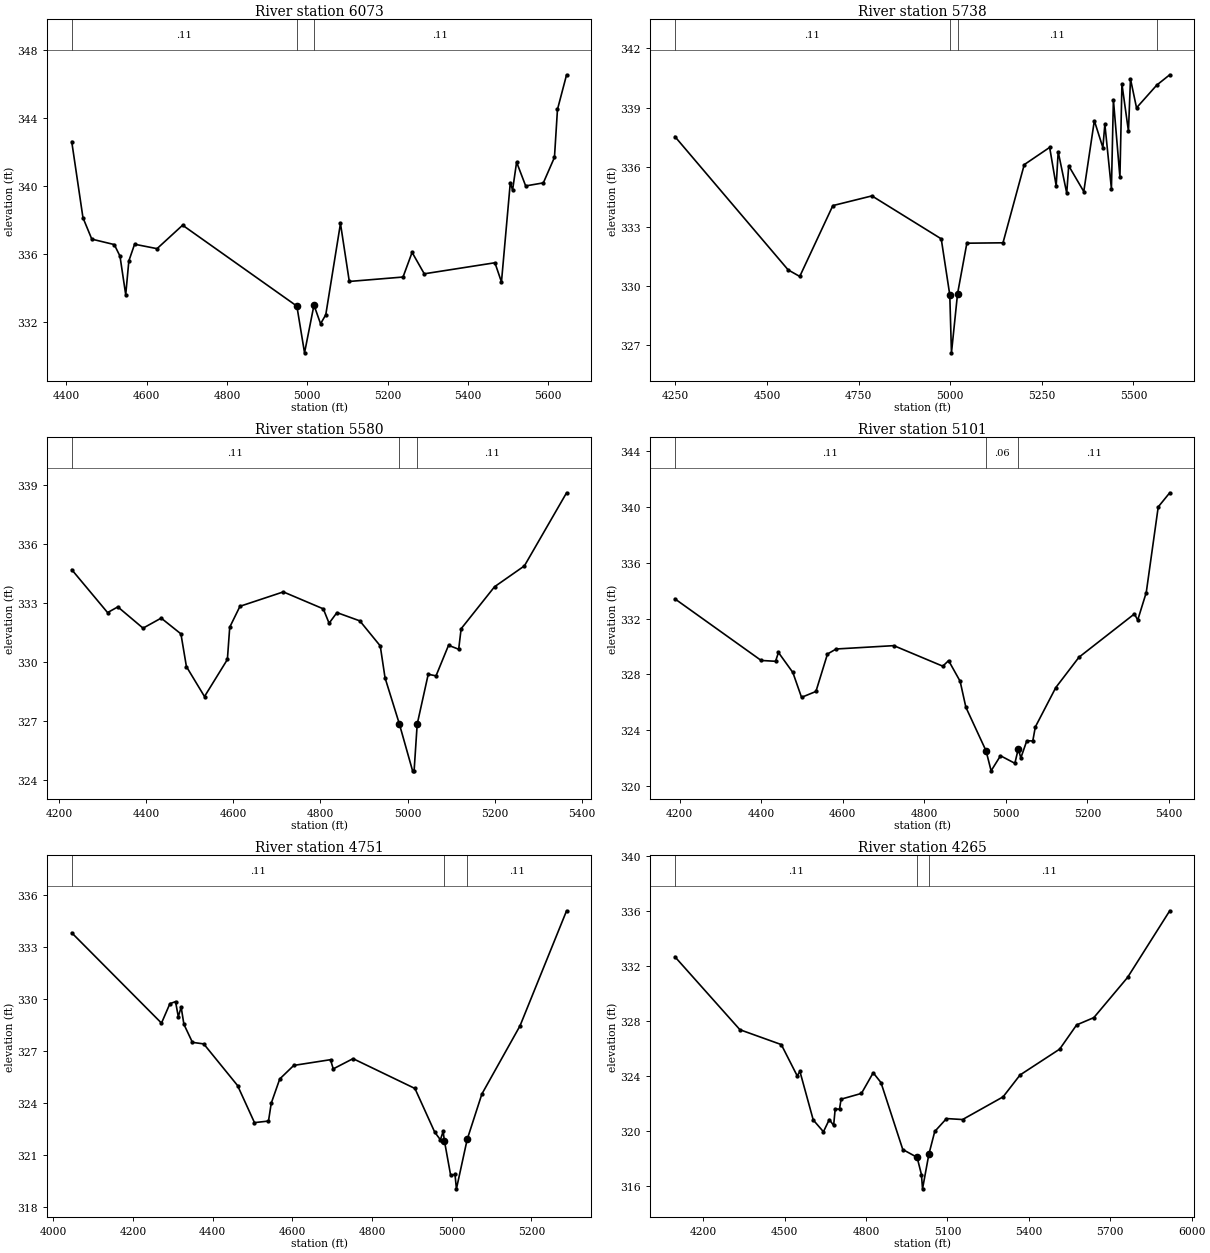
Type RM Length L Ch R = 1 ,6073    ,335,335,335
BEGIN DESCRIPTION:
CCLC 088 13.0
END DESCRIPTION:
XS GIS Cut Line= 3
      3696017.86     10211261.06      3696465.61     10210881.62
      3696767.87     10210311.04
#Sta/Elev= 30
  4413.1  342.61  4441.1  338.13  4463.1  336.87  4519.1  336.55  4533.3  335.87
  4547.6   333.6  4555.4  335.59  4569.7  336.57  4625.6  336.31  4689.3  337.69
  4973.9  332.93    4993  330.18  5016.5  332.99  5032.9  331.89  5045.9  332.42
  5082.5  337.79  5104.5  334.38  5238.3  334.64  5260.9  336.09  5291.2  334.83
  5467.2  335.48  5483.5  334.35  5505.5  340.19  5511.2  339.76  5521.2   341.4
  5543.8     340  5587.8  340.18  5615.5  341.68    5623   344.5  5645.7  346.54
#Mann= 3 , 0 , 0
  4413.1     .11       0  4973.9     .06       0  5016.5     .11       0
Bank Sta=4973.9,5016.5
XS Rating Curve= 0 ,0
Exp/Cntr=0.3,0.1

Type RM Length L Ch R = 1 ,5738    ,158,158,158
BEGIN DESCRIPTION:
Mapping XS 1d487e62
END DESCRIPTION:
XS GIS Cut Line= 2
       3696349.4      10211822.6      3696896.28     10210588.22
#Sta/Elev= 30
  4248.8  337.55  4557.9  330.81  4589.5  330.48  4679.8  334.06  4786.4  334.55
  4975.5  332.38  4998.8  329.55  5003.4  326.62    5020329.6045  5045.4  332.16
    5144  332.18    5202  336.13  5271.3     337  5289.1  335.06  5294.6  336.78
  5317.9  334.69  5323.3  336.07  5364.4  334.77  5393.2  338.35  5416.5  336.99
  5421.9  338.17  5439.8  334.91  5445.2  339.41    5463  335.49  5468.5   340.2
  5486.3  337.82  5491.8  340.46  5508.3     339  5563.6  340.15  5598.9  340.67
#Mann= 4 ,-1 , 0
  4248.8     .11       0  4998.8     .07       0    5020     .11       0
  5563.6    .125       0
Bank Sta=4998.8,5020
XS Rating Curve= 0 ,0
Exp/Cntr=0.3,0.1

Type RM Length L Ch R = 1 ,5580    ,479,479,479
BEGIN DESCRIPTION:
CCLC 088 12.0
END DESCRIPTION:
XS GIS Cut Line= 3
      3696490.04     10211911.11      3696795.51     10211203.42
      3696943.02     10210869.77
#Sta/Elev= 30
  4229.2  334.68  4311.5   332.5    4335  332.79  4392.9  331.71  4434.5  332.22
  4479.8  331.42  4492.4  329.76  4533.9  328.24  4586.4  330.12  4591.8  331.76
  4615.3  332.82  4714.8  333.55  4806.5  332.69  4819.8  331.96  4837.8   332.5
  4890.3  332.08  4937.2  330.81  4948.2  329.19  4980.8  326.87  5011.4  324.47
  5014.9  324.47    5022326.8407  5047.3  329.37  5065.2  329.29  5093.9  330.84
  5117.2  330.64  5122.8  331.68  5199.4  333.81    5268  334.87  5364.8  338.58
#Mann= 3 ,-1 , 0
  4229.2     .11       0  4980.8     .07       0    5022     .11       0
Bank Sta=4980.8,5022
XS Rating Curve= 0 ,0
Exp/Cntr=0.3,0.1

Type RM Length L Ch R = 1 ,5101    ,350,350,350
BEGIN DESCRIPTION:
CCLC 088 11.0
END DESCRIPTION:
XS GIS Cut Line= 3
       3696609.8      10212062.2      3697181.49     10211485.98
      3697417.86     10211161.06
#Sta/Elev= 30
  4188.3  333.41  4399.9     329  4435.2  328.94  4442.3  329.57  4477.6  328.14
  4498.9  326.36  4534.2  326.78  4562.5  329.46  4583.7  329.82  4725.2  330.06
  4845.3  328.59  4859.5  328.99  4887.8  327.51  4901.9  325.65  4951.4  322.53
  4963.8   321.1  4986.8  322.18    5022  321.64  5030.5  322.68  5036.6  322.02
  5051.3  323.25    5066  323.24  5072.2  324.24  5122.4  327.06  5179.2  329.23
  5315.2  332.33  5323.3  331.89  5344.2  333.86  5373.6  339.99  5401.8     341
#Mann= 3 , 0 , 0
  4188.3     .11       0  4951.4     .06       0  5030.5     .11       0
Bank Sta=4951.4,5030.5
XS Rating Curve= 0 ,0
Exp/Cntr=0.3,0.1

Type RM Length L Ch R = 1 ,4751    ,486,486,486
BEGIN DESCRIPTION:
CCLC 088 10.0
END DESCRIPTION:
XS GIS Cut Line= 3
      3696812.96     10212374.66      3697469.47      10211682.2
      3697567.84      10211411.1
#Sta/Elev= 30
  4045.8  333.82  4271.2  328.61  4292.3  329.73  4306.5  329.85  4313.4  328.98
  4320.6  329.53  4327.5  328.54  4348.9   327.5  4377.3  327.41  4462.2  325.01
  4504.7  322.87  4539.9  322.96  4546.8  323.99  4568.2  325.39  4603.4  326.17
  4695.6   326.5  4702.5  325.97  4752.2  326.56  4907.6  324.84  4957.3  322.32
  4971.5  321.88  4978.4  322.36  4981.6321.8266  4997.3  319.83  5008.2  319.88
  5011.8  319.05  5038.8   321.9  5075.7  324.52  5171.4  328.45  5288.4  335.09
#Mann= 3 , 0 , 0
  4045.8     .11       0  4981.6     .06       0  5038.8     .11       0
Bank Sta=4981.6,5038.8
XS Rating Curve= 0 ,0
Exp/Cntr=0.3,0.1

Type RM Length L Ch R = 1 ,4265    ,320,320,320
BEGIN DESCRIPTION:
CCLC 088 9.0
END DESCRIPTION:
XS GIS Cut Line= 3
      3696896.23     10212385.12      3697875.44     10211833.01
      3698073.12     10211161.95
#Sta/Elev= 30
  4095.5  332.68  4335.3  327.37  4487.7  326.29  4546.2  324.02  4556.3  324.34
  4605.4  320.81    4643  319.95  4664.6  320.84  4680.6  320.41  4686.3  321.61
  4702.2  321.59    4708  322.32  4783.1  322.74  4826.4  324.24    4855  323.53
  4935.4  318.66  4988.2  318.09  5004.2  316.84  5008.2   315.8  5031.6  318.32
  5053.2  319.97  5096.5  320.91  5155.8  320.84  5305.1  322.49  5367.6  324.08
  5513.6  325.96  5576.1  327.72  5639.5  328.25  5763.7  331.17  5919.2  336.02
#Mann= 3 , 0 , 0
  4095.5     .11       0  4988.2     .06       0  5031.6     .11       0
Bank Sta=4988.2,5031.6
XS Rating Curve= 0 ,0
Exp/Cntr=0.3,0.1

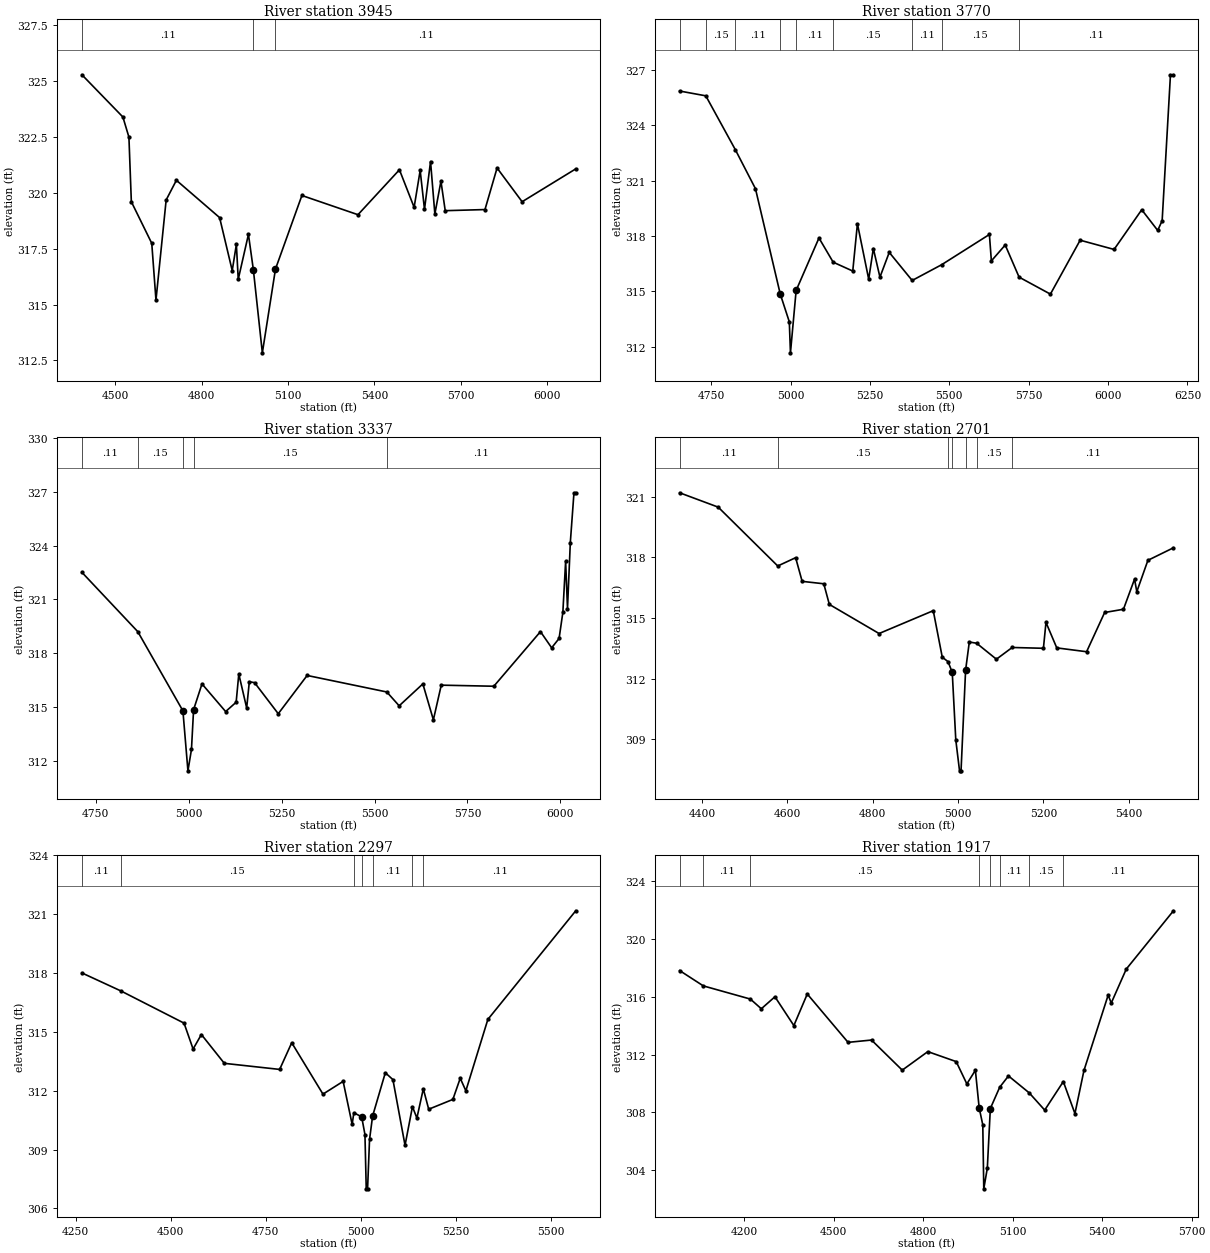
Type RM Length L Ch R = 1 ,3945    ,175,175,175
BEGIN DESCRIPTION:
Mapping XS e9ebad8a
END DESCRIPTION:
XS GIS Cut Line= 3
      3697447.66     10212460.31      3698065.69     10212000.26
      3698849.42     10211473.62
#Sta/Elev= 30
  4384.5  325.28  4526.8  323.39  4547.7  322.49  4556.1   319.6    4627  317.74
  4641.6   315.2    4677  319.68  4712.5  320.56  4862.6  318.89  4906.4  316.52
  4920.8  317.69  4927.3  316.13  4962.7  318.14 4979.81316.5543    5011  312.84
  5056.6  316.59  5148.3  319.88    5343  319.02    5487  321.03    5538  319.35
    5559     321    5574  319.26    5595   321.4    5610  319.05  5631.1  320.52
    5646   319.2    5784  319.25    5826  321.11    5913   319.6  6099.2  321.07
#Mann= 3 ,-1 , 0
  4384.5     .11       0 4979.81     .06       0  5056.6     .11       0
Bank Sta=4979.81,5056.6
XS Rating Curve= 0 ,0
Exp/Cntr=0.3,0.1

Type RM Length L Ch R = 1 ,3770    ,433,433,433
BEGIN DESCRIPTION:
CCLC 088 8.0
END DESCRIPTION:
XS GIS Cut Line= 4
      3697838.97     10212478.86      3698068.15     10212208.01
       3698945.9     10211561.02      3698956.32     10211451.65
#Sta/Elev= 30
  4650.7  325.85  4733.1  325.59  4825.9  322.68  4889.5  320.56  4967.5  314.86
  4996.1  313.35  4999.7  311.67  5017.6  315.05  5089.5  317.89  5134.2  316.58
  5195.9   316.1  5210.6  318.66  5246.1  315.66  5260.7  317.32  5281.5  315.77
  5310.8  317.11    5383  315.59  5475.5  316.44  5626.2  318.08  5632.4  316.65
    5676  317.51  5719.7  315.77  5818.3  314.85    5912  317.77  6018.8  317.27
  6105.9  319.42  6156.2   318.3  6170.2  318.83  6196.3  326.71  6205.8  326.73
#Mann= 9 ,-1 , 0
  4650.7     .11       0  4733.1     .15       0  4825.9     .11       0
  4967.5     .06       0  5017.6     .11       0  5134.2     .15       0
    5383     .11       0  5475.5     .15       0  5719.7     .11       0
Bank Sta=4967.5,5017.6
XS Rating Curve= 0 ,0
Exp/Cntr=0.3,0.1

Type RM Length L Ch R = 1 ,3337    ,636,636,636
BEGIN DESCRIPTION:
CCLC 088 7.0
END DESCRIPTION:
XS GIS Cut Line= 4
      3698198.35     10212484.08      3698302.68     10212216.82
      3698954.58     10211566.23        3698965.     10211446.49
#Sta/Elev= 30
  4713.1  322.51  4863.3  319.21  4984.7   314.8  4998.2  311.46  5007.7  312.65
 5013.42314.8655    5036   316.3  5099.6  314.76  5127.9  315.28    5135  316.85
  5156.2  314.96  5163.3  316.42  5177.4  316.37  5241.1  314.64  5318.8  316.77
  5533.1  315.85  5566.3  315.08    5630   316.3  5658.3   314.3  5679.5  316.23
  5820.9  316.17  5946.3  319.21  5976.4  318.31  5996.4  318.83  6006.5  320.28
    6014  323.13    6019  320.49  6026.6  324.17  6036.4  326.94  6041.2  326.94
#Mann= 5 ,-1 , 0
  4713.1     .11       0  4863.3     .15       0  4984.7     .09       0
 5013.42     .15       0  5533.1     .11       0
Bank Sta=4984.7,5013.42
XS Rating Curve= 0 ,0
Exp/Cntr=0.3,0.1

Type RM Length L Ch R = 1 ,2701    ,404,404,404
BEGIN DESCRIPTION:
CCLC 088 6.0
END DESCRIPTION:
XS GIS Cut Line= 3
      3698479.63     10212577.78      3698781.69     10212093.43
      3698971.94     10211538.45
#Sta/Elev= 30
  4347.4  321.19  4437.8  320.48  4577.4  317.57  4619.3  317.98  4634.6  316.81
  4685.3  316.69  4698.3  315.67  4814.9  314.23  4941.9  315.36    4963  313.06
  4976.5  312.84  4986.4  312.31  4994.7  308.97  5003.5  307.44    5007  307.44
  5017.7  312.42  5026.4  313.81  5043.5  313.75  5089.9  312.96  5126.9  313.54
  5200.1   313.5  5206.1  314.78  5231.4  313.52  5301.3  313.33  5343.6  315.27
  5387.7  315.43  5413.7  316.92    5419   316.3    5445  317.85  5504.9  318.47
#Mann= 7 ,-1 , 0
  4347.4     .11       0  4577.4     .15       0  4976.5     .11       0
  4986.4     .06       0  5017.7     .11       0  5043.5     .15       0
  5126.9     .11       0
Bank Sta=4986.4,5017.7
XS Rating Curve= 0 ,0
Exp/Cntr=0.3,0.1

Type RM Length L Ch R = 1 ,2297    ,380,380,380
BEGIN DESCRIPTION:
CCLC 088 5.0
END DESCRIPTION:
XS GIS Cut Line= 3
      3698817.84     10212561.11      3699094.19     10211900.72
      3699250.45      10211338.2
#Sta/Elev= 30
  4266.3  318.01  4369.1  317.09  4535.1  315.45  4558.9  314.13  4580.7  314.87
  4641.1   313.4  4786.7  313.09  4818.5  314.45  4900.7  311.83  4953.8  312.48
  4977.5  310.29    4982  310.88  5002.6  310.67  5011.2  309.77  5014.6     307
  5018.1     307  5023.3  309.52 5031.33 310.709  5064.8  312.92  5084.8  312.57
  5116.7  309.22  5136.2  311.19  5147.9  310.61  5164.8   312.1    5179  311.06
  5242.6  311.56    5262  312.64  5276.8     312  5334.7  315.64    5566  321.18
#Mann= 7 ,-1 , 0
  4266.3     .11       0  4369.1     .15       0    4982     .11       0
  5002.6     .06       0 5031.33     .11       0  5136.2     .15       0
  5164.8     .11       0
Bank Sta=5002.6,5031.33
XS Rating Curve= 0 ,0
Exp/Cntr=0.3,0.1

Type RM Length L Ch R = 1 ,1917    ,589,589,589
BEGIN DESCRIPTION:
CCLC 088 4.0
END DESCRIPTION:
XS GIS Cut Line= 3
      3698867.87     10212711.04      3699416.82      10211856.1
      3699515.88     10211224.83
#Sta/Elev= 30
    3984   317.8  4063.5  316.74  4221.1  315.83  4257.8  315.16  4303.4  315.99
  4366.8     314  4411.8  316.18  4548.5  312.84  4627.1     313  4730.1  310.92
  4815.8   312.2  4910.9  311.51  4946.6  309.97  4975.2  310.91 4987.88308.3133
    5000  307.14  5003.3  302.72  5015.2  304.15  5025.3  308.27  5056.7  309.74
  5086.1  310.52  5155.6  309.35  5207.5  308.16  5269.9  310.13  5308.8  307.92
  5339.1   310.9  5420.1   316.1  5430.6  315.56  5480.8   317.9    5639  321.93
#Mann= 8 ,-1 , 0
    3984     .17       0  4063.5     .11       0  4221.1     .15       0
 4987.88     .09       0  5025.3     .15       0  5056.7     .11       0
  5155.6     .15       0  5269.9     .11       0
Bank Sta=4987.88,5025.3
XS Rating Curve= 0 ,0
Exp/Cntr=0.3,0.1

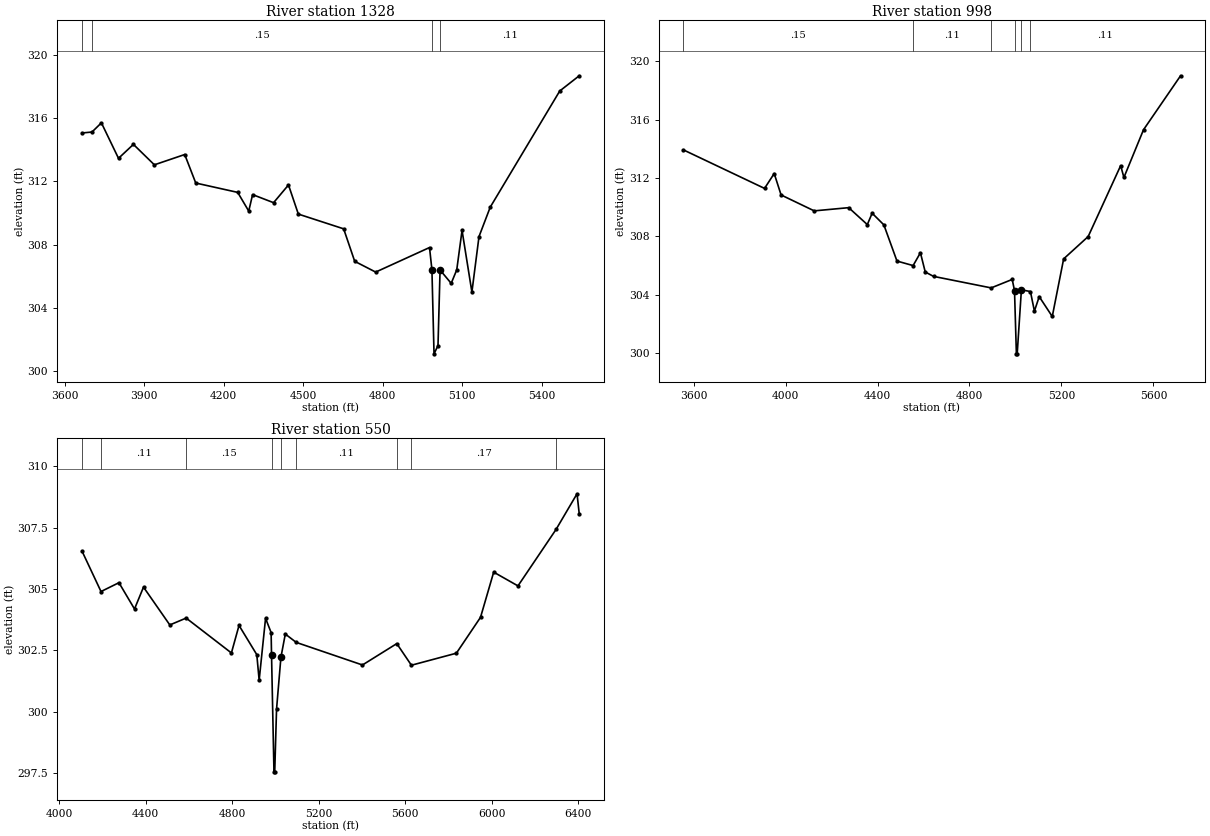
Type RM Length L Ch R = 1 ,1328    ,330,330,330
BEGIN DESCRIPTION:
CCLC 088 3.0
END DESCRIPTION:
XS GIS Cut Line= 3
      3699014.45     10212549.76      3699918.12     10211872.65
      3699687.95     10211161.16
#Sta/Elev= 30
    3665  315.05  3702.4  315.11  3737.9  315.69  3802.5  313.45  3858.8  314.33
  3937.9  313.04  4052.5  313.69  4094.2  311.89  4252.6   311.3  4294.2  310.12
  4308.8  311.16    4388  310.65  4444.3  311.77  4481.5  309.93  4652.6     309
  4694.3  306.95  4773.5  306.27  4976.8  307.82 4985.88306.4126  4993.8  301.11
  5008.8  301.63  5016.6   306.4  5058.6  305.56  5079.6  306.41  5099.6   308.9
  5136.8  305.01  5163.6  308.51  5206.1  310.37  5468.5   317.7    5542  318.66
#Mann= 4 ,-1 , 0
    3665     .11       0  3702.4     .15       0 4985.88     .09       0
  5016.6     .11       0
Bank Sta=4985.88,5016.6
XS Rating Curve= 0 ,0
Exp/Cntr=0.3,0.1

Type RM Length L Ch R = 1 ,998     ,448,448,448
BEGIN DESCRIPTION:
CCLC 088 2.0
END DESCRIPTION:
XS GIS Cut Line= 4
       3699120.9     10212513.51      3700148.59     10211823.43
       3700152.5     10211578.38      3699698.37     10211072.61
#Sta/Elev= 30
  3555.5  313.92  3908.4  311.28  3950.4   312.3  3980.4  310.83  4124.5  309.74
  4274.5  309.96  4355.5   308.8  4376.5  309.58  4427.5  308.78  4484.5   306.3
  4554.7  305.99  4586.5  306.87  4607.5  305.55  4643.5  305.25  4894.3  304.46
  4985.8  305.04  4995.8  304.28    5004  299.94  5007.5  299.94  5025.8  304.33
  5065.1  304.21  5082.4  302.87  5103.3  303.86  5160.1   302.5  5209.6  306.45
  5316.3  307.98  5457.6  312.84  5471.8  312.03    5557   315.3  5718.2     319
#Mann= 6 ,-1 , 0
  3555.5     .15       0  4554.7     .11       0  4894.3     .15       0
  4995.8     .09       0  5025.8     .15       0  5065.1     .11       0
Bank Sta=4995.8,5025.8
XS Rating Curve= 0 ,0
Exp/Cntr=0.3,0.1

Type RM Length L Ch R = 1 ,550     ,0,0,0
BEGIN DESCRIPTION:
CCLC 088 1.0
END DESCRIPTION:
XS GIS Cut Line= 3
      3699917.85     10212161.08      3700495.23     10211697.59
      3700234.81     10210161.11
#Sta/Elev= 30
  4106.7  306.54  4194.2   304.9  4277.1  305.26  4349.1  304.19  4390.7  305.08
  4512.4  303.54  4587.9  303.82  4797.2   302.4  4832.4  303.52  4914.6  302.33
  4925.5  301.29  4955.1  303.81  4980.8  303.23 4982.77   302.3    4994  297.56
  4997.5  297.56  5005.9  300.11  5026.1  302.22  5046.4  303.17  5096.8  302.83
  5403.2  301.91  5561.9  302.78  5629.5   301.9  5837.5  302.39  5949.1  303.85
    6010  305.69  6122.3  305.13  6298.5  307.43  6395.4  308.88  6405.5  308.07
#Mann= 9 ,-1 , 0
  4106.7     .15       0  4194.2     .11       0  4587.9     .15       0
 4982.77     .09       0  5026.1     .15       0  5096.8     .11       0
  5561.9     .15       0  5629.5     .17       0  6298.5     .11       0
Bank Sta=4982.77,5026.1
XS Rating Curve= 0 ,0
Exp/Cntr=0.3,0.1

Chan Stop Cuts=-1
Use User Specified Reach Order=0
Composite Channel Slope=5