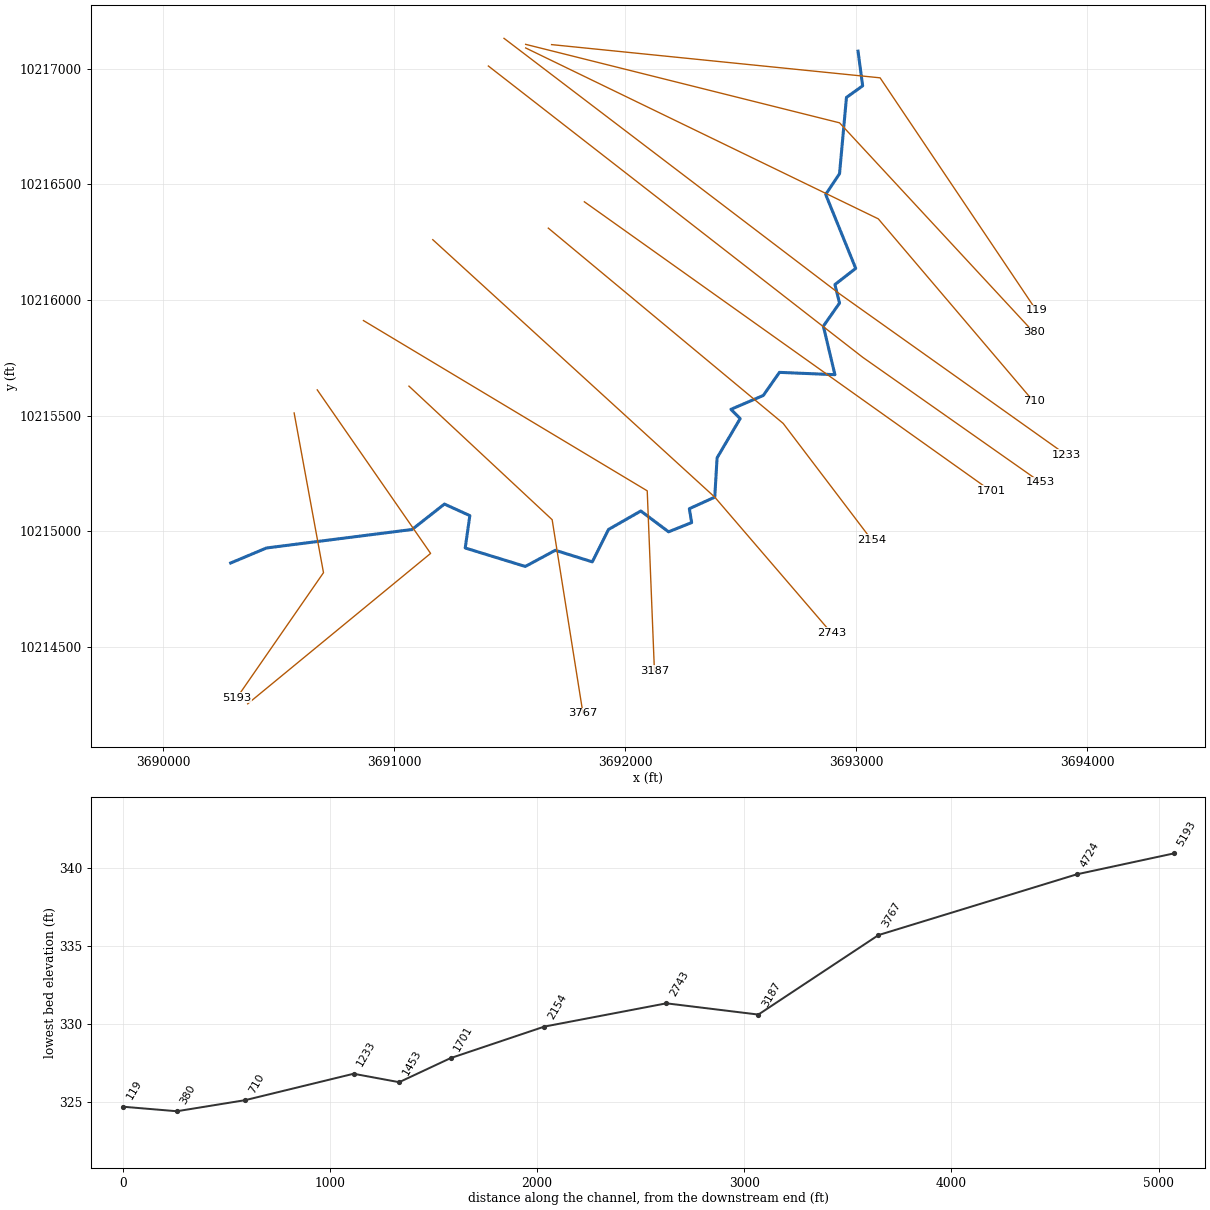
--- CCLC 089.prj (project) ---

Proj Title=CCLC 089 Base Level Engineering
Current Plan=p01
Default Exp/Contr=0.3,0.1
English Units
Geom File=g01
Flow File=f01
Flow File=f02
Plan File=p01
Y Axis Title=Elevation
X Axis Title(PF)=Main Channel Distance
X Axis Title(XS)=Station
BEGIN DESCRIPTION:
CCLC 089
END DESCRIPTION:
DSS Export Rating Curves= 0
DSS Export Rating Curve Sorted= 0
DSS Export Volume Flow Curves= 0
DXF OffsetX= 0
DXF OffsetY= 0
DXF ScaleX= 1
DXF ScaleY= 10

--- CCLC 089.p01 (plan) ---

Plan Title=Multiple Run
Short Identifier=Multiple
Geom File=g01
Flow File=f01
Subcritical Flow
K Sum by GR= 0
Std Step Tol= 0.01
Critical Tol= 0.01
Num of Std Step Trials= 20
Max Error Tol= 0.3
Flow Tol Ratio= 0.001
Split Flow NTrial= 30
Split Flow Tol= 0.02
Split Flow Ratio= 0.02
Log Output Level= 0
Friction Slope Method= 1
Unsteady Friction Slope Method= 2
Unsteady Bridges Friction Slope Method= 1
Parabolic Critical Depth
Global Vel Dist=  1 , 1 , 1
Global Log Level= 0
CheckData=True
Encroach Param= -1, 0, 0, 0
BEGIN DESCRIPTION:
Multiple Run
END DESCRIPTION:

--- CCLC 089.f01 (steady flow) ---

Flow Title=Multiple
Program Version=4.10
Number of Profiles= 7
Profile Names=10-year,25-year,50-year,1pct_min,100-year,1pct_plu,500-year
River Rch & RM=CCLC 089,Reach-1         ,5193
     474     632     845     373    1125    3397    2057
River Rch & RM=CCLC 089,Reach-1         ,4724
     807    1109    1511     677    2045    6176    3870
Boundary for River Rch & Prof#=CCLC 089,Reach-1         , 1
Up Type= 0
Dn Type= 3
Dn Slope=0.005
Boundary for River Rch & Prof#=CCLC 089,Reach-1         , 2
Up Type= 0
Dn Type= 3
Dn Slope=0.005
Boundary for River Rch & Prof#=CCLC 089,Reach-1         , 3
Up Type= 0
Dn Type= 3
Dn Slope=0.005
Boundary for River Rch & Prof#=CCLC 089,Reach-1         , 4
Up Type= 0
Dn Type= 3
Dn Slope=0.005
Boundary for River Rch & Prof#=CCLC 089,Reach-1         , 5
Up Type= 0
Dn Type= 3
Dn Slope=0.005
Boundary for River Rch & Prof#=CCLC 089,Reach-1         , 6
Up Type= 0
Dn Type= 3
Dn Slope=0.005
Boundary for River Rch & Prof#=CCLC 089,Reach-1         , 7
Up Type= 0
Dn Type= 3
Dn Slope=0.005
DSS Import GetInterval= 0
DSS Import GetPeak= 0
DSS Import FillOption= 0

--- CCLC 089.f02 (steady flow) ---

Flow Title=Orig_BLE_Flows
Program Version=4.10
Number of Profiles= 7
Profile Names=10-year,25-year,50-year,1pct_min,100-year,1pct_plu,500-year
River Rch & RM=CCLC 089,Reach-1         ,5193
     474     620     735     286     865    2613    1196
River Rch & RM=CCLC 089,Reach-1         ,4724
     807    1087    1314     521    1573    4749    2250
Boundary for River Rch & Prof#=CCLC 089,Reach-1         , 1
Up Type= 0
Dn Type= 3
Dn Slope=0.005
Boundary for River Rch & Prof#=CCLC 089,Reach-1         , 2
Up Type= 0
Dn Type= 3
Dn Slope=0.005
Boundary for River Rch & Prof#=CCLC 089,Reach-1         , 3
Up Type= 0
Dn Type= 3
Dn Slope=0.005
Boundary for River Rch & Prof#=CCLC 089,Reach-1         , 4
Up Type= 0
Dn Type= 3
Dn Slope=0.005
Boundary for River Rch & Prof#=CCLC 089,Reach-1         , 5
Up Type= 0
Dn Type= 3
Dn Slope=0.005
Boundary for River Rch & Prof#=CCLC 089,Reach-1         , 6
Up Type= 0
Dn Type= 3
Dn Slope=0.005
Boundary for River Rch & Prof#=CCLC 089,Reach-1         , 7
Up Type= 0
Dn Type= 3
Dn Slope=0.005
DSS Import GetInterval= 0
DSS Import GetPeak= 0
DSS Import FillOption= 0

--- CCLC 089.g01 (geometry) ---

Geom Title=Existing Conditions
Program Version=4.10

River Reach=CCLC 089        ,Reach-1
Reach XY= 30
      3690293.23     10214861.84      3690448.23     10214926.84
      3691078.23     10215006.84      3691218.23     10215116.84
      3691328.23     10215066.84      3691308.23     10214926.84
      3691568.23     10214846.84      3691698.23     10214916.84
      3691858.23     10214866.84      3691928.23     10215006.84
      3692068.23     10215086.84      3692188.23     10214996.84
      3692288.23     10215036.84      3692278.23     10215096.84
      3692388.23     10215146.84      3692398.23     10215316.84
      3692498.23     10215486.84      3692458.23     10215526.84
      3692598.23     10215586.84      3692668.23     10215686.84
      3692908.23     10215676.84      3692858.23     10215886.84
      3692928.23     10215986.84      3692908.23     10216066.84
      3692998.23     10216136.84      3692868.23     10216456.84
      3692928.23     10216546.84      3692958.23     10216876.84
      3693028.23     10216926.84      3693008.23     10217076.84

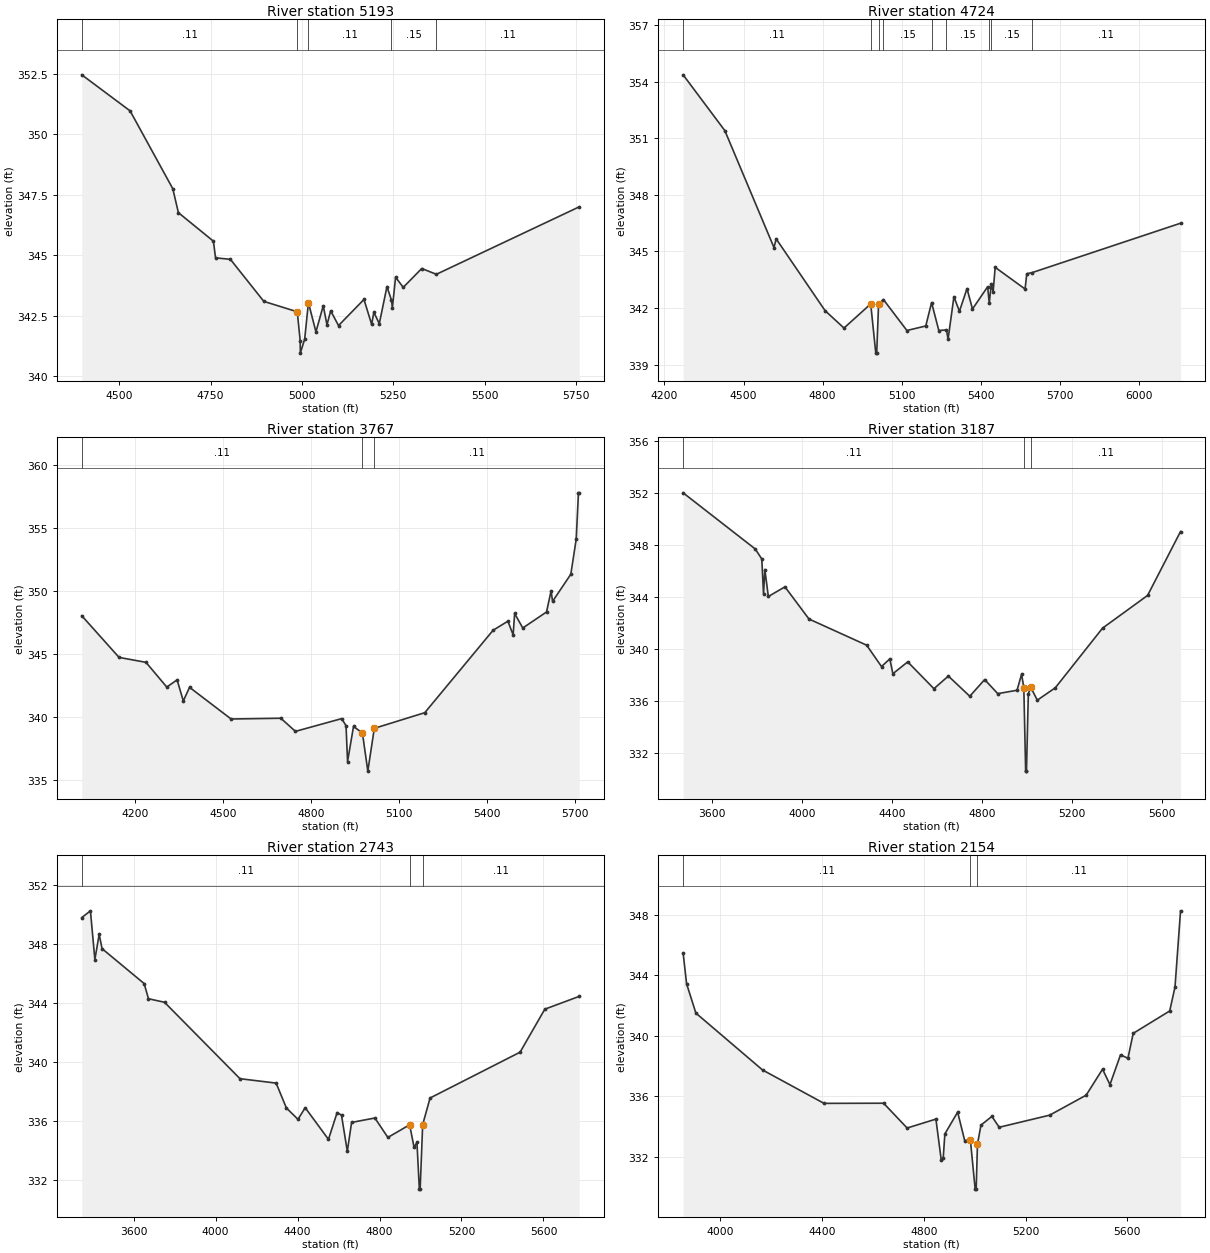
Type RM Length L Ch R = 1 ,5193    ,469,469,469
BEGIN DESCRIPTION:
CCLC 089 9.0
END DESCRIPTION:
XS GIS Cut Line= 3
      3690567.84     10215511.12      3690694.89     10214819.99
       3690319.9     10214278.33
#Sta/Elev= 30
  4397.2  352.46  4529.4  350.97  4646.3  347.75  4661.6  346.76  4757.5  345.58
  4763.3  344.89  4803.9  344.83  4895.5  343.09    4987  342.66  4995.1  341.45
  4995.4  340.95  5007.3  341.53  5017.5  343.04  5038.1  341.83  5058.1  342.91
  5068.3  342.12  5078.5   342.7  5099.9  342.09  5169.6  343.17  5190.6  342.14
  5196.6  342.64  5211.5  342.17  5232.5   343.7  5244.9  343.14  5247.3  342.82
  5256.1  344.09  5277.1  343.67  5327.7  344.45  5367.7  344.21  5758.7     347
#Mann= 5 ,-1 , 0
  4397.2     .11       0    4987     .06       0  5017.5     .11       0
  5244.9     .15       0  5367.7     .11       0
Bank Sta=4987,5017.5
XS Rating Curve= 0 ,0
Exp/Cntr=0.3,0.1

Type RM Length L Ch R = 1 ,4724    ,957,957,957
BEGIN DESCRIPTION:
CCLC 089 8.0
END DESCRIPTION:
XS GIS Cut Line= 3
      3690667.86     10215611.05      3691158.43     10214903.32
      3690366.77     10214252.29
#Sta/Elev= 30
  4270.9  354.37  4429.1  351.41  4615.4  345.21  4623.7  345.67  4809.3  341.86
  4880.9  340.94  4982.2  342.22  5001.4  339.61  5004.9  339.61    5012  342.21
  5030.4  342.45  5119.4  340.81  5190.9  341.05    5213  342.29  5240.4  340.81
  5269.4  340.84  5275.5  340.35  5297.7   342.6  5318.6  341.83  5347.3  343.03
  5368.1  341.95  5425.5  343.13  5431.7  342.26  5439.3  343.28  5446.3  342.85
  5454.1  344.16  5567.5  343.01    5574  343.82  5594.1  343.88    6157   346.5
#Mann= 9 ,-1 , 0
  4270.9     .11       0  4982.2     .06       0    5012     .11       0
  5030.4     .15       0    5213     .11       0  5269.4     .15       0
  5431.7     .11       0  5439.3     .15       0  5594.1     .11       0
Bank Sta=4982.2,5012
XS Rating Curve= 0 ,0
Exp/Cntr=0.3,0.1

Type RM Length L Ch R = 1 ,3767    ,580,580,580
BEGIN DESCRIPTION:
CCLC 089 7.0
END DESCRIPTION:
XS GIS Cut Line= 3
      3691064.71     10215627.25      3691684.47     10215049.16
      3691817.86     10214211.03
#Sta/Elev= 30
  4018.5  348.03  4145.6  344.73  4237.4  344.34  4308.3  342.38  4343.5  342.95
  4364.7  341.28    4386  342.36  4527.6  339.85  4697.2  339.91    4747  338.87
  4904.6  339.88  4919.6  339.32  4924.8  336.48  4945.1  339.26  4975.5  338.74
  4993.9  335.72    5016  339.11  5188.1  340.35    5421  346.88  5471.6   347.6
  5489.4  346.51  5494.5  348.21  5522.3  347.06  5603.3  348.33  5618.8     350
  5623.9  349.17  5686.1  351.32  5704.5   354.1  5712.1  357.77  5714.7  357.77
#Mann= 3 , 0 , 0
  4018.5     .11       0  4975.5    .065       0    5016     .11       0
Bank Sta=4975.5,5016
XS Rating Curve= 0 ,0
Exp/Cntr=0.3,0.1

Type RM Length L Ch R = 1 ,3187    ,444,444,444
BEGIN DESCRIPTION:
CCLC 089 6.0
END DESCRIPTION:
XS GIS Cut Line= 3
      3690867.85     10215911.07      3692095.93     10215174.16
      3692127.12     10214394.49
#Sta/Elev= 30
  3470.4     352  3791.1  347.69  3820.3  346.92    3828  344.23  3833.9  346.11
  3849.4  344.04  3923.3  344.78  4030.2  342.31  4286.8   340.3  4352.8  338.66
  4389.7  339.25  4403.4  338.11  4469.4  339.02    4586  336.96  4650.2  337.93
  4745.4  336.38  4811.6  337.66  4869.9  336.58  4955.7  336.84  4975.8  338.07
  4985.8  337.05  4993.9  330.63  4997.6  330.63  5005.8  336.54  5015.8  337.09
  5045.8  336.08  5125.9  337.03    5336  341.61  5536.2  344.12  5682.9  349.03
#Mann= 3 , 0 , 0
  3470.4     .11       0  4985.8    .065       0  5015.8     .11       0
Bank Sta=4985.8,5015.8
XS Rating Curve= 0 ,0
Exp/Cntr=0.3,0.1

Type RM Length L Ch R = 1 ,2743    ,589,589,589
BEGIN DESCRIPTION:
CCLC 089 5.0
END DESCRIPTION:
XS GIS Cut Line= 3
      3691167.87     10216261.06      3692388.23     10215146.84
      3692892.83     10214559.54
#Sta/Elev= 30
  3347.5  349.79  3389.7  350.25  3411.3  346.94  3432.3  348.65  3446.5  347.68
  3651.8  345.31  3672.8  344.28  3751.1  344.04  4119.3  338.85  4295.7  338.55
  4345.7  336.86  4402.4  336.09  4437.5  336.88    4551  334.73  4593.3  336.55
  4614.6  336.37  4642.9  333.92  4663.9  335.88  4777.4  336.18  4840.9  334.86
    4947  335.72  4968.6  334.19  4982.7  334.52  4994.4  331.35  4998.3  331.35
  5010.6  335.73  5046.8  337.54  5485.8  340.65  5606.5  343.57  5774.3  344.44
#Mann= 3 , 0 , 0
  3347.5     .11       0    4947    .065       0  5010.6     .11       0
Bank Sta=4947,5010.6
XS Rating Curve= 0 ,0
Exp/Cntr=0.3,0.1

Type RM Length L Ch R = 1 ,2154    ,453,453,453
BEGIN DESCRIPTION:
CCLC 089 4.0
END DESCRIPTION:
XS GIS Cut Line= 3
      3691667.87     10216311.06      3692684.47     10215465.82
      3693067.84     10214961.09
#Sta/Elev= 30
  3853.5  345.47  3867.1  343.44  3903.6   341.5  4165.6  337.74  4407.5  335.53
  4641.8  335.54  4734.3   333.9  4847.5  334.49  4868.4  331.79  4876.2  331.91
  4882.7  333.51  4932.9  334.95  4960.8  333.06  4982.9  333.13  5001.8  329.86
  5005.8  329.86  5010.9  332.83  5024.6  334.09  5067.6  334.67  5096.2  333.95
  5294.7  334.75  5438.2  336.07  5502.7  337.79  5531.8  336.77  5573.4  338.74
  5602.5  338.51  5623.3  340.16  5766.8  341.64  5787.6  343.22  5809.4  348.26
#Mann= 3 , 0 , 0
  3853.5     .11       0  4982.9     .06       0  5010.9     .11       0
Bank Sta=4982.9,5010.9
XS Rating Curve= 0 ,0
Exp/Cntr=0.3,0.1

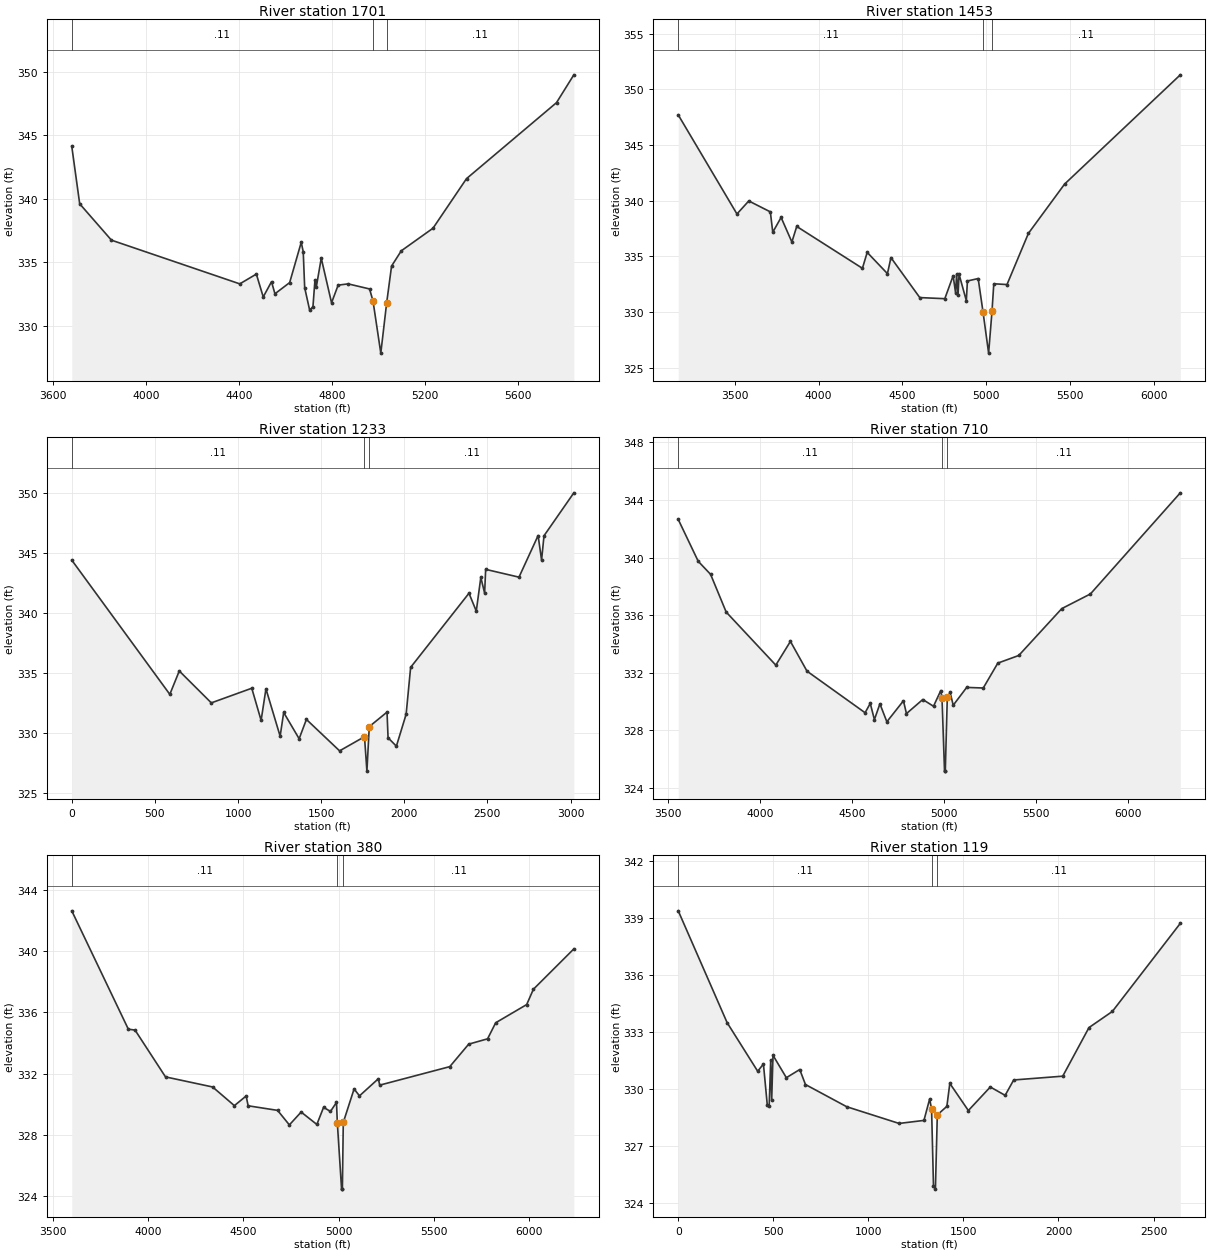
Type RM Length L Ch R = 1 ,1701    ,248,248,248
BEGIN DESCRIPTION:
Mapping XS 757679e3
END DESCRIPTION:
XS GIS Cut Line= 2
      3691823.91     10216425.06      3693584.15      10215173.2
#Sta/Elev= 30
  3681.7  344.11  3715.8  339.59  3852.3  336.73  4404.5  333.29  4475.8  334.06
  4505.4  332.26    4541  333.46  4555.8  332.51  4619.1  333.39  4668.9  336.56
  4677.5  335.82  4683.7  332.99    4705  331.23  4719.3  331.49  4727.9  333.58
  4734.1  333.08    4755  335.31  4799.3   331.8  4827.7  333.19  4870.6  333.29
  4962.8  332.89  4977.6  331.95  5011.2  327.84  5036.3  331.78  5057.5  334.69
  5099.3  335.89  5235.8  337.67  5379.9  341.57  5767.1  347.55  5841.7  349.74
#Mann= 3 , 0 , 0
  3681.7     .11       0  4977.6    .065       0  5036.3     .11       0
Bank Sta=4977.6,5036.3
XS Rating Curve= 0 ,0
Exp/Cntr=0.3,0.1

Type RM Length L Ch R = 1 ,1453    ,220,220,220
BEGIN DESCRIPTION:
Mapping XS d982baf6
END DESCRIPTION:
XS GIS Cut Line= 3
      3691408.44     10217012.69      3693028.22     10215752.28
      3693799.05     10215210.62
#Sta/Elev= 30
    3163   347.7  3513.2   338.8  3583.8  339.97  3712.3  338.99  3726.8  337.16
  3776.5  338.49  3840.8  336.28  3869.7  337.68  4261.5  333.92    4290  335.35
  4410.8  333.44  4431.6  334.88  4603.6  331.29  4752.9  331.19  4802.6  333.25
  4817.1  331.72  4823.4  333.39  4831.6  331.51  4837.9  333.39  4881.3  331.01
  4887.7  332.78  4951.9     333  4980.9  329.99  5014.2   326.3 5034.36330.0584
  5045.1  332.53  5123.8  332.46  5251.6  337.06  5467.6  341.49  6157.5   351.3
#Mann= 3 , 0 , 0
    3163     .11       0  4980.9    .065       0 5034.36     .11       0
Bank Sta=4980.9,5034.36
XS Rating Curve= 0 ,0
Exp/Cntr=0.3,0.1

Type RM Length L Ch R = 1 ,1233    ,523,523,523
BEGIN DESCRIPTION:
CCLC 089 3.0
END DESCRIPTION:
XS GIS Cut Line= 3
      3691476.14     10217132.48      3692928.23     10216026.84
      3693908.41     10215330.42
#Sta/Elev= 30
       0  344.43   589.7  333.24   646.6  335.19   839.3  332.53  1082.6  333.75
  1138.8  331.07  1167.9   333.7  1253.2  329.75  1274.5  331.73  1367.5  329.54
  1411.2  331.15  1610.8  328.53  1760.6  329.71  1775.1  326.84  1789.3  330.55
  1896.1  331.76  1902.3  329.62  1952.4  328.92    2011  331.58  2038.1  335.49
    2389  341.67  2432.9  340.18  2460.2  342.99  2483.1  341.68  2489.3  343.66
  2689.8  343.01  2804.8  346.48  2825.6  344.43  2840.2  346.46  3019.7  350.04
#Mann= 3 , 0 , 0
       0     .11       0  1760.6    .065       0  1789.3     .11       0
Bank Sta=1760.6,1789.3
XS Rating Curve= 0 ,0
Exp/Cntr=0.3,0.1

Type RM Length L Ch R = 1 ,710     ,330,330,330
BEGIN DESCRIPTION:
CCLC 089 2.0
END DESCRIPTION:
XS GIS Cut Line= 3
      3691569.92     10217090.81      3693095.93     10216351.24
      3693767.85     10215561.08
#Sta/Elev= 30
  3553.7  342.65  3662.5  339.74  3729.9  338.83  3814.7  336.21  4084.8  332.52
  4164.4  334.17  4254.7   332.1  4570.8  329.21    4599  329.86  4621.5  328.73
  4651.5  329.83  4689.3  328.58  4779.6  330.04    4796  329.15  4884.9  330.13
  4943.2  329.66  4982.8  330.75 4989.58330.2245  5003.2  325.15  5007.4  325.15
  5018.3  330.28  5033.5  330.63  5050.5  329.73  5123.8  330.97  5214.1  330.93
  5293.3  332.66  5407.2  333.19  5641.5  336.45  5797.5  337.47  6286.7   344.5
#Mann= 3 , 0 , 0
  3553.7     .11       0 4989.58     .06       0  5018.3     .11       0
Bank Sta=4989.58,5018.3
XS Rating Curve= 0 ,0
Exp/Cntr=0.3,0.1

Type RM Length L Ch R = 1 ,380     ,261,261,261
BEGIN DESCRIPTION:
CCLC 089 1.0
END DESCRIPTION:
XS GIS Cut Line= 3
      3691569.84     10217106.46      3692928.23     10216766.84
      3693767.87     10215861.05
#Sta/Elev= 30
  3599.8  342.64  3896.7   334.9    3932  334.84  4091.8  331.78  4339.1  331.12
  4453.3   329.9  4515.1  330.53  4525.5  329.89  4680.1  329.59  4741.9  328.64
  4803.8  329.48  4886.2  328.67  4921.5  329.79  4957.6  329.52  4989.3  330.11
 4993.68328.7793    5016  324.44  5020.2  324.44  5024.9   328.8  5081.6  330.99
    5110  330.54  5209.2  331.66    5216  331.24  5583.9  332.45  5683.1  333.92
  5782.3  334.27  5824.9  335.32  5987.6  336.51  6022.7  337.51  6235.1  340.15
#Mann= 3 , 0 , 0
  3599.8     .11       0 4993.68     .06       0  5024.9     .11       0
Bank Sta=4993.68,5024.9
XS Rating Curve= 0 ,0
Exp/Cntr=0.3,0.1

Type RM Length L Ch R = 1 ,119     ,0,0,0
BEGIN DESCRIPTION:
CCLC 089 0.5
END DESCRIPTION:
XS GIS Cut Line= 3
      3691682.03     10217105.34      3693103.75     10216961.57
      3693779.99     10215955.19
#Sta/Elev= 30
       0  339.39   257.1   333.5   417.9  330.94   448.1  331.32   468.2  329.18
   478.2  329.09   486.5  331.53   491.5  329.41   498.4  331.78   568.7   330.6
   639.1  331.03   669.2  330.24   886.3  329.07  1161.7  328.19  1292.4  328.35
  1322.5  329.48  1332.6  328.94  1342.6   324.9  1352.7  324.73  1362.7  328.64
    1413  329.09  1428.5   330.3    1526  328.87  1641.5  330.11  1719.5  329.67
  1764.5  330.48  2022.5  330.68  2160.5  333.24  2283.5  334.09  2640.9  338.73
#Mann= 3 , 0 , 0
       0     .11       0  1332.6     .06       0  1362.7     .11       0
Bank Sta=1332.6,1362.7
XS Rating Curve= 0 ,0
Exp/Cntr=0.3,0.1

Chan Stop Cuts=-1
Use User Specified Reach Order=0
Composite Channel Slope=5