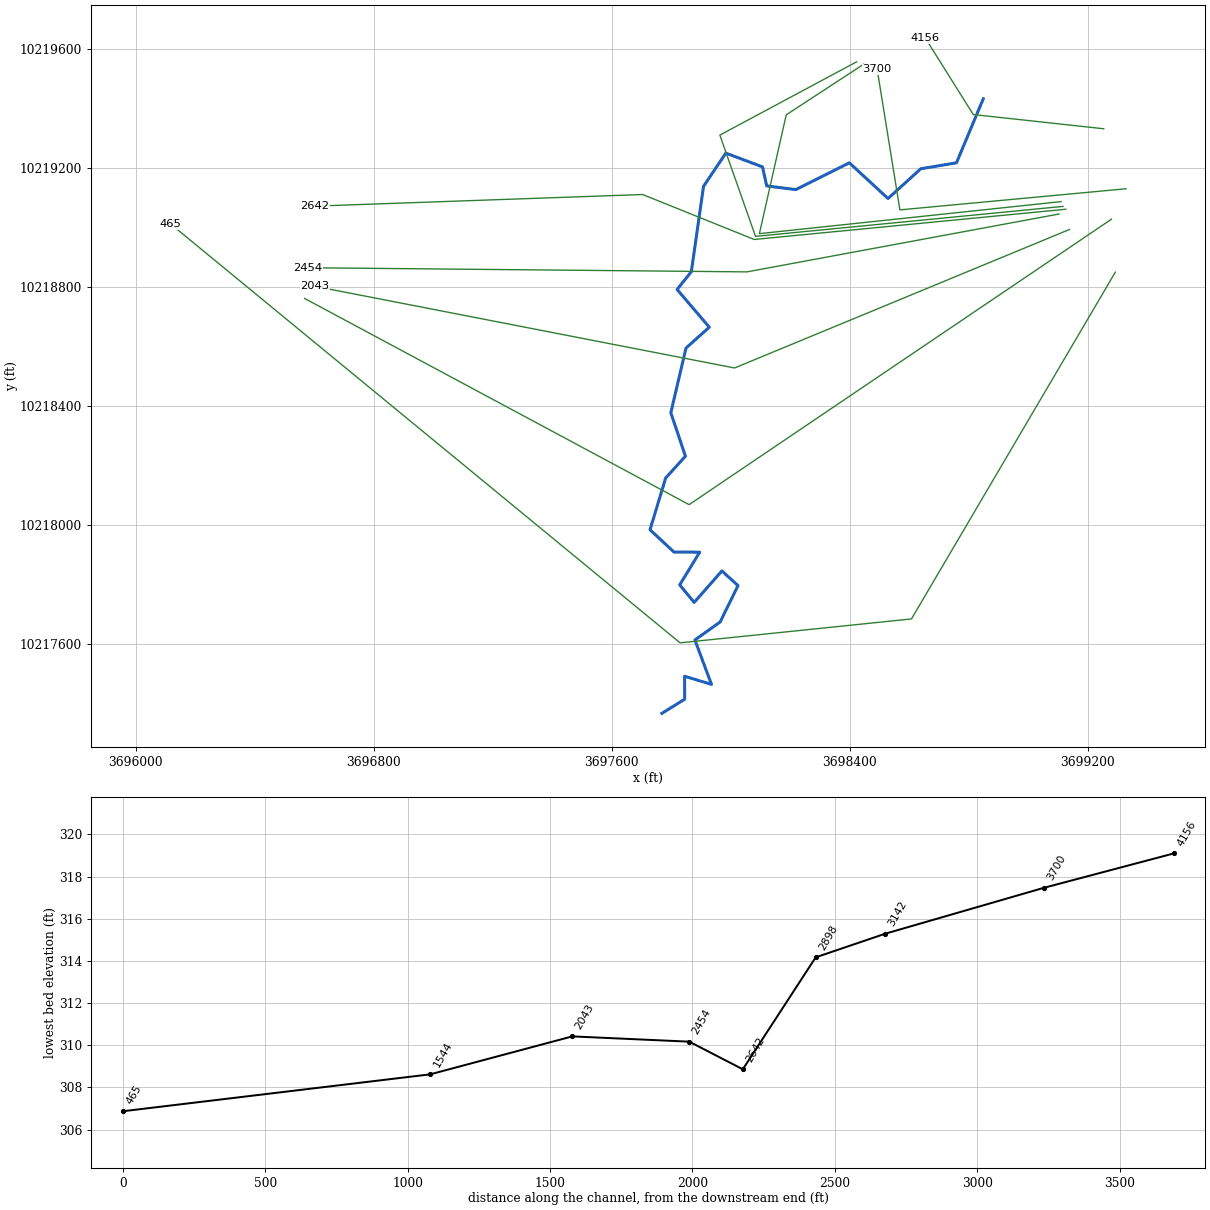
--- CCLC 091.prj (project) ---

Proj Title=CCLC 091 Base Level Engineering
Current Plan=p01
Default Exp/Contr=0.3,0.1
English Units
Geom File=g01
Flow File=f01
Flow File=f02
Plan File=p01
Y Axis Title=Elevation
X Axis Title(PF)=Main Channel Distance
X Axis Title(XS)=Station
BEGIN DESCRIPTION:
CCLC 091
END DESCRIPTION:
DSS Export Rating Curves= 0
DSS Export Rating Curve Sorted= 0
DSS Export Volume Flow Curves= 0
DXF OffsetX= 0
DXF OffsetY= 0
DXF ScaleX= 1
DXF ScaleY= 10

--- CCLC 091.p01 (plan) ---

Plan Title=Multiple Run
Short Identifier=Multiple
Geom File=g01
Flow File=f01
Subcritical Flow
K Sum by GR= 0
Std Step Tol= 0.01
Critical Tol= 0.01
Num of Std Step Trials= 20
Max Error Tol= 0.3
Flow Tol Ratio= 0.001
Split Flow NTrial= 30
Split Flow Tol= 0.02
Split Flow Ratio= 0.02
Log Output Level= 0
Friction Slope Method= 1
Unsteady Friction Slope Method= 2
Unsteady Bridges Friction Slope Method= 1
Parabolic Critical Depth
Global Vel Dist=  1 , 1 , 1
Global Log Level= 0
CheckData=True
Encroach Param= -1, 0, 0, 0
BEGIN DESCRIPTION:
Multiple Run
END DESCRIPTION:

--- CCLC 091.f01 (steady flow) ---

Flow Title=Multiple
Program Version=4.10
Number of Profiles= 7
Profile Names=10-year,25-year,50-year,1pct_min,100-year,1pct_plu,500-year
River Rch & RM=CCLC 091,Reach-1         ,4156
     424     562     748     328     991    2993    1797
River Rch & RM=CCLC 091,Reach-1         ,2898
    2090    2980    4166    1906    5756   17383   11385
Boundary for River Rch & Prof#=CCLC 091,Reach-1         , 1
Up Type= 0
Dn Type= 3
Dn Slope=0.005
Boundary for River Rch & Prof#=CCLC 091,Reach-1         , 2
Up Type= 0
Dn Type= 3
Dn Slope=0.005
Boundary for River Rch & Prof#=CCLC 091,Reach-1         , 3
Up Type= 0
Dn Type= 3
Dn Slope=0.005
Boundary for River Rch & Prof#=CCLC 091,Reach-1         , 4
Up Type= 0
Dn Type= 3
Dn Slope=0.005
Boundary for River Rch & Prof#=CCLC 091,Reach-1         , 5
Up Type= 0
Dn Type= 3
Dn Slope=0.005
Boundary for River Rch & Prof#=CCLC 091,Reach-1         , 6
Up Type= 0
Dn Type= 3
Dn Slope=0.005
Boundary for River Rch & Prof#=CCLC 091,Reach-1         , 7
Up Type= 0
Dn Type= 3
Dn Slope=0.005
DSS Import GetInterval= 0
DSS Import GetPeak= 0
DSS Import FillOption= 0

--- CCLC 091.f02 (steady flow) ---

Flow Title=Orig_BLE_Flows
Program Version=4.10
Number of Profiles= 7
Profile Names=10-year,25-year,50-year,1pct_min,100-year,1pct_plu,500-year
River Rch & RM=CCLC 091,Reach-1         ,4156
     424     551     650     252     762    2302    1045
River Rch & RM=CCLC 091,Reach-1         ,2898
    2090    2922    3623    1466    4428   13373    6619
Boundary for River Rch & Prof#=CCLC 091,Reach-1         , 1
Up Type= 0
Dn Type= 3
Dn Slope=0.005
Boundary for River Rch & Prof#=CCLC 091,Reach-1         , 2
Up Type= 0
Dn Type= 3
Dn Slope=0.005
Boundary for River Rch & Prof#=CCLC 091,Reach-1         , 3
Up Type= 0
Dn Type= 3
Dn Slope=0.005
Boundary for River Rch & Prof#=CCLC 091,Reach-1         , 4
Up Type= 0
Dn Type= 3
Dn Slope=0.005
Boundary for River Rch & Prof#=CCLC 091,Reach-1         , 5
Up Type= 0
Dn Type= 3
Dn Slope=0.005
Boundary for River Rch & Prof#=CCLC 091,Reach-1         , 6
Up Type= 0
Dn Type= 3
Dn Slope=0.005
Boundary for River Rch & Prof#=CCLC 091,Reach-1         , 7
Up Type= 0
Dn Type= 3
Dn Slope=0.005
DSS Import GetInterval= 0
DSS Import GetPeak= 0
DSS Import FillOption= 0

--- CCLC 091.g01 (geometry) ---

Geom Title=Existing Conditions
Program Version=4.10

River Reach=CCLC 091        ,Reach-1
Reach XY= 30
      3698848.23     10219431.84      3698758.23     10219216.84
      3698638.23     10219196.84      3698528.23     10219096.84
      3698398.23     10219216.84      3698218.23     10219126.84
      3698120.57     10219139.18      3698106.35     10219203.24
      3697983.15     10219249.44      3697908.37      10219137.9
      3697867.39     10218851.04      3697819.42     10218791.34
      3697927.68     10218664.32      3697849.46     10218594.56
      3697798.31     10218376.82      3697847.48      10218231.1
      3697781.02     10218157.62      3697728.48      10217983.9
      3697809.08     10217908.84      3697895.44     10217908.48
      3697828.23     10217798.69      3697876.82     10217739.68
      3697970.01     10217845.44      3698024.12     10217796.25
      3697964.18     10217674.01      3697879.25     10217613.52
      3697935.01     10217464.24      3697844.56     10217491.64
      3697844.95     10217414.33      3697768.23     10217366.84

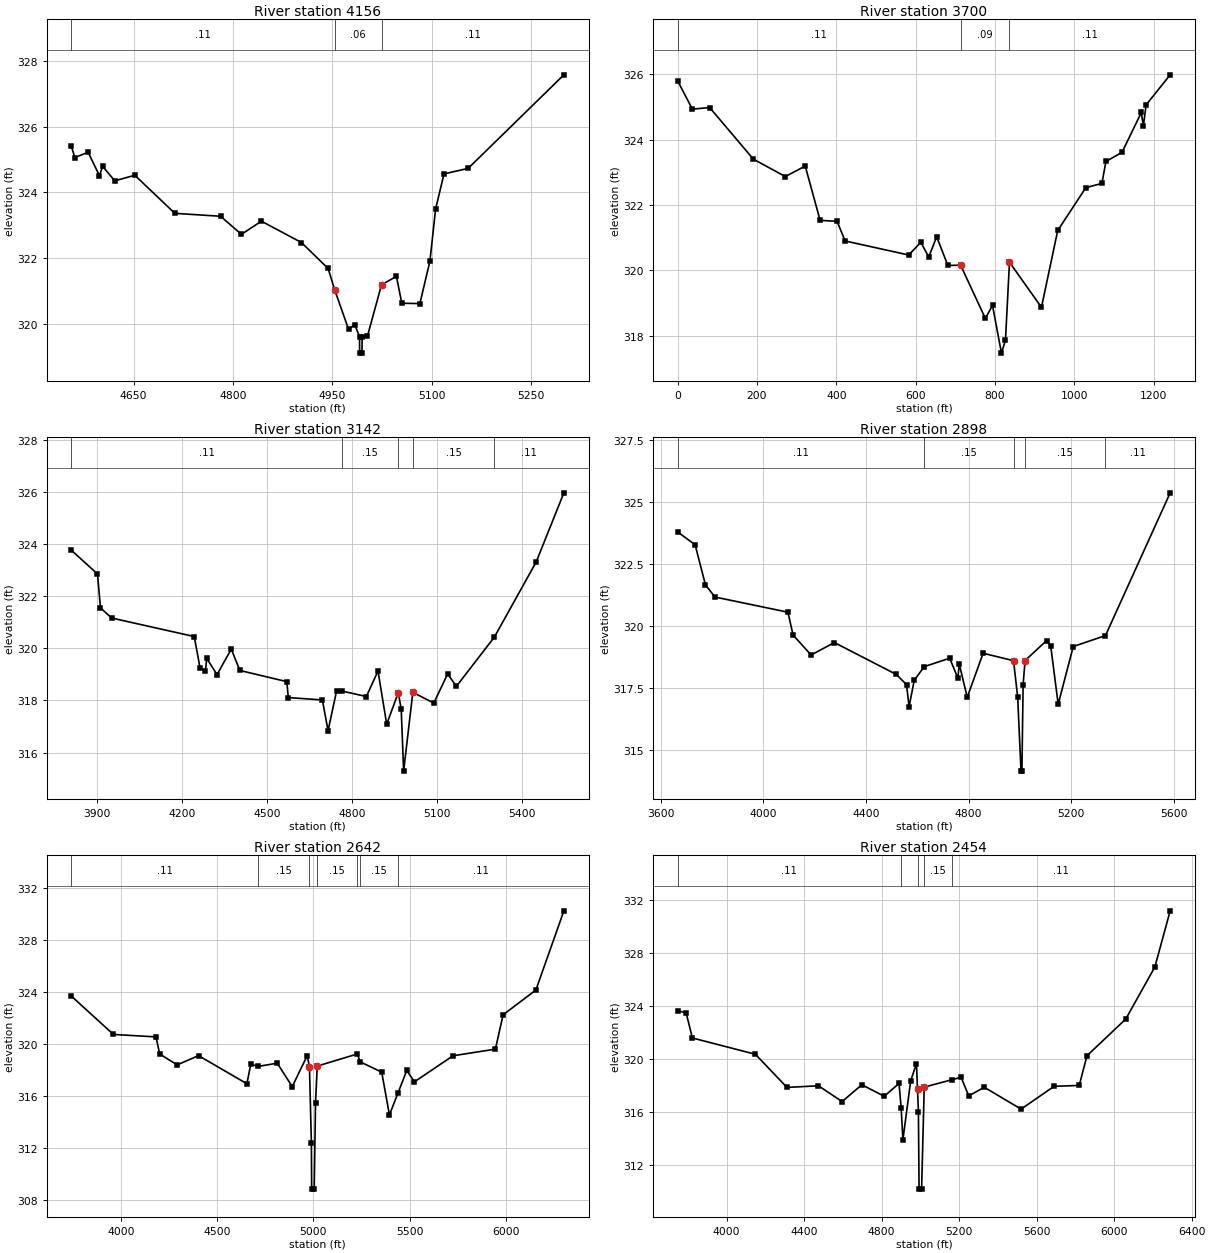
Type RM Length L Ch R = 1 ,4156    ,456,456,456
BEGIN DESCRIPTION:
CCLC 091 3.0
END DESCRIPTION:
XS GIS Cut Line= 3
      3699253.08     10219331.27      3698814.68     10219379.02
      3698654.07     10219635.13
#Sta/Elev= 30
  4555.9  325.41  4561.2  325.06  4581.3  325.22  4598.3  324.51  4603.3  324.79
  4621.5  324.35  4651.7  324.52  4712.1  323.36  4781.2  323.27  4812.6  322.72
  4842.8  323.12  4903.2  322.47  4943.4  321.68  4953.5  321.02  4974.2  319.83
  4983.6  319.97  4990.8   319.6    4991   319.1  4994.5   319.1  4994.8   319.6
  5002.8  319.62    5024  321.18  5046.5  321.44  5054.6  320.62  5081.9  320.61
  5097.1  321.91  5105.6  323.49  5118.3  324.56  5154.8  324.73  5299.2  327.58
#Mann= 3 , 0 , 0
  4555.9     .11       0  4953.5     .06       0    5024     .11       0
Bank Sta=4953.5,5024
XS Rating Curve= 0 ,0
Exp/Cntr=0.3,0.1

Type RM Length L Ch R = 1 ,3700    ,558,558,558
BEGIN DESCRIPTION:
Mapping XS e5311c83
END DESCRIPTION:
XS GIS Cut Line= 3
      3699328.26      10219129.7      3698568.15     10219058.71
      3698491.76     10219530.93
#Sta/Elev= 30
       0   325.8    37.3  324.93    80.8  324.98   191.2   323.4   271.6  322.87
   321.8  323.19   359.3  321.53   402.2   321.5   422.2   320.9   582.9  320.47
   613.1  320.86   633.2  320.41   653.2  321.03   681.3  320.15   713.5  320.16
   775.9  318.53   793.9  318.93   816.5  317.47   826.6  317.87   836.7  320.25
   917.3  318.87   958.3  321.22  1029.2  322.53  1069.7  322.66  1079.8  323.33
  1120.4  323.61  1169.1  324.83  1174.2  324.41  1181.1  325.06  1241.8  325.98
#Mann= 3 ,-1 , 0
       0     .11       0   713.5     .09       0   836.7     .11       0
Bank Sta=713.5,836.7
XS Rating Curve= 0 ,0
Exp/Cntr=0.3,0.1

Type RM Length L Ch R = 1 ,3142    ,244,244,244
BEGIN DESCRIPTION:
Mapping XS d6243f88
END DESCRIPTION:
XS GIS Cut Line= 4
      3699109.79     10219086.48      3698095.93     10218978.84
      3698186.21     10219378.15      3698446.61     10219548.28
#Sta/Elev= 30
  3808.2  323.76  3900.7  322.85  3911.3  321.55  3950.9  321.16  4242.6  320.45
  4262.7  319.26  4281.7  319.12  4286.8  319.61    4323  318.99  4373.3  319.97
  4403.5  319.15  4569.6  318.72  4574.7  318.11  4695.1  318.02  4715.2  316.84
  4745.4  318.37  4764.3  318.36  4850.5  318.15  4891.6  319.13  4922.3  317.09
  4963.3   318.3  4973.6  317.66  4982.1  315.29  5014.6  318.31  5088.7   317.9
  5137.6  319.02  5168.4  318.54  5302.7  320.43  5450.4  323.31  5548.2  325.96
#Mann= 5 ,-1 , 0
  3808.2     .11       0  4764.3     .15       0  4963.3     .09       0
  5014.6     .15       0  5302.7     .11       0
Bank Sta=4963.3,5014.6
XS Rating Curve= 0 ,0
Exp/Cntr=0.3,0.1

Type RM Length L Ch R = 1 ,2898    ,256,256,256
BEGIN DESCRIPTION:
Mapping XS 6db60125
END DESCRIPTION:
XS GIS Cut Line= 4
      3699115.94     10219070.39      3698082.91     10218969.69
      3697963.12     10219309.97      3698422.63      10219556.2
#Sta/Elev= 30
  3665.7  323.79  3734.1  323.27  3774.3  321.66  3811.4  321.17  4095.8  320.56
  4115.9  319.64  4186.2  318.84  4276.7  319.34  4517.8  318.06    4558  317.65
    4568  316.76  4588.1  317.82  4626.8  318.37  4726.3  318.71  4758.1  317.91
  4763.7  318.47  4794.7  317.14  4856.6  318.91  4975.1  318.61  4991.3  317.15
  5004.3  314.17  5007.8  314.17  5012.5  317.64  5020.1318.6151    5104  319.42
  5120.2  319.19  5149.2  316.86  5207.9  319.18  5333.5  319.62  5585.7  325.36
#Mann= 5 ,-1 , 0
  3665.7     .11       0  4626.8     .15       0  4975.1     .09       0
  5020.1     .15       0  5333.5     .11       0
Bank Sta=4975.1,5020.1
XS Rating Curve= 0 ,0
Exp/Cntr=0.3,0.1

Type RM Length L Ch R = 1 ,2642    ,188,188,188
BEGIN DESCRIPTION:
Mapping XS a856cb9d
END DESCRIPTION:
XS GIS Cut Line= 4
      3699125.49     10219060.84      3698078.57     10218959.27
      3697703.57     10219110.32      3696602.48     10219071.27
#Sta/Elev= 30
  3743.1   323.7  3961.8  320.75  4182.8  320.56  4202.3  319.24  4293.3  318.41
  4403.8  319.12    4655  316.96  4675.1  318.47  4713.4  318.29  4812.5  318.54
  4890.4  316.74  4968.2  319.12 4979.81318.2482  4989.8  312.43  4991.3  308.86
  5004.4  308.86  5011.3  315.49 5020.25318.3172    5229  319.25  5242.2  318.65
    5355  317.85  5395.1  314.56  5439.5  316.25  5485.1  317.98  5525.1  317.11
  5725.3  319.11  5945.4  319.62  5985.4  322.26  6155.5  324.16    6301  330.25
#Mann= 7 ,-1 , 0
  3743.1     .11       0  4713.4     .15       0 4979.81     .09       0
 5020.25     .15       0    5229     .11       0  5242.2     .15       0
  5439.5     .11       0
Bank Sta=4979.81,5020.25
XS Rating Curve= 0 ,0
Exp/Cntr=0.3,0.1

Type RM Length L Ch R = 1 ,2454    ,411,411,411
BEGIN DESCRIPTION:
Mapping XS 605e9c20
END DESCRIPTION:
XS GIS Cut Line= 3
      3699102.84     10219044.81      3698054.26     10218850.37
      3696578.58     10218864.26
#Sta/Elev= 30
  3746.9  323.64  3791.2  323.47  3823.2  321.58  4148.6  320.35  4311.3  317.85
  4474.1  317.97  4596.1  316.78  4697.8  318.05  4813.4  317.18  4889.8  318.15
  4900.8  316.28  4909.8   313.9  4949.8  318.34  4979.8  319.65 4985.14317.7168
  4989.8  316.03  4993.2  310.17  5006.3  310.17  5019.8  317.87  5165.5  318.44
  5209.8  318.61  5249.8  317.21  5329.8  317.86  5519.8  316.21  5689.8  317.93
  5819.8     318  5859.8  320.24  6059.8  323.01  6209.8  326.93  6289.1  331.18
#Mann= 5 ,-1 , 0
  3746.9     .11       0  4900.8     .15       0 4985.14     .09       0
  5019.8     .15       0  5165.5     .11       0
Bank Sta=4985.14,5019.8
XS Rating Curve= 0 ,0
Exp/Cntr=0.3,0.1

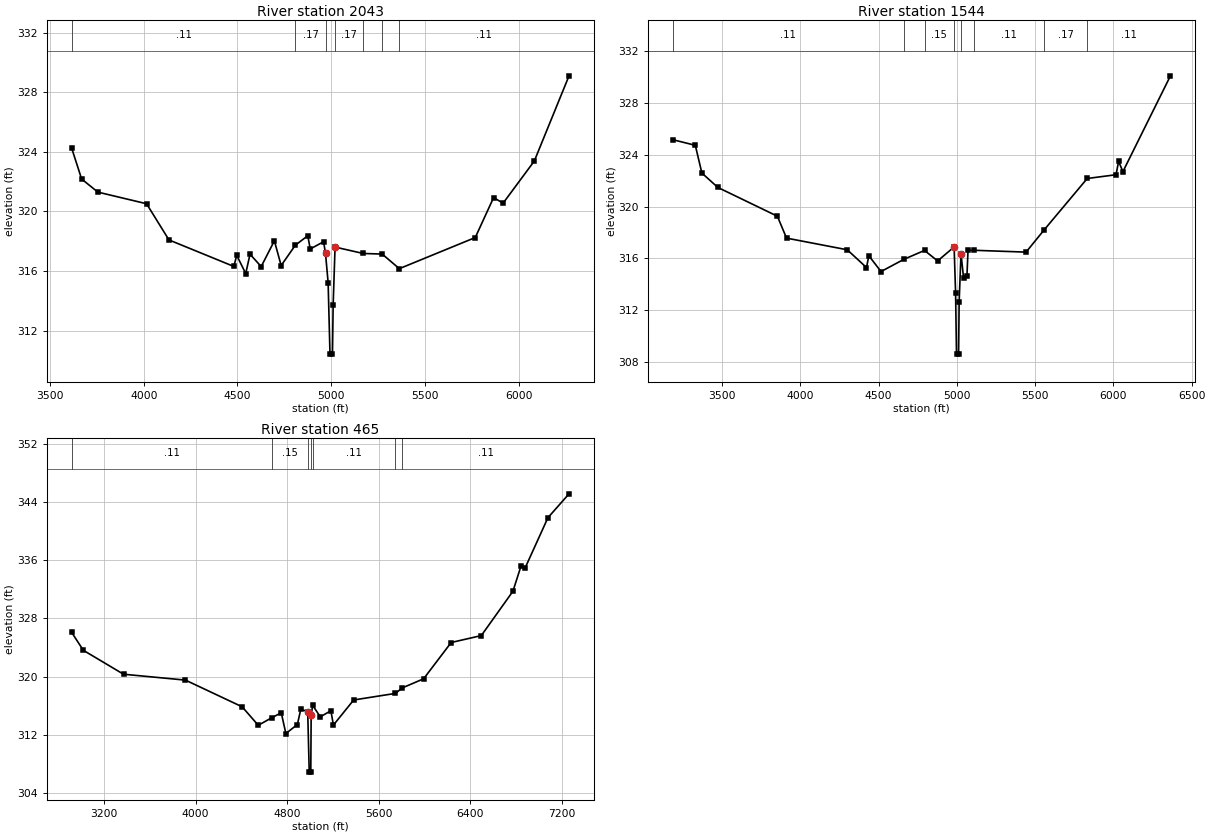
Type RM Length L Ch R = 1 ,2043    ,499,499,499
BEGIN DESCRIPTION:
Mapping XS 99f6f977
END DESCRIPTION:
XS GIS Cut Line= 3
      3699137.59     10218992.73       3698012.6     10218527.46
      3696602.85     10218801.77
#Sta/Elev= 30
    3615  324.28  3668.8  322.18  3755.4   321.3  4015.1  320.52  4134.6  318.09
  4480.4  316.31  4496.3  317.05  4544.1  315.83    4567  317.13  4626.6   316.3
  4696.9  318.03  4733.1  316.37    4809  317.74  4875.2  318.37  4888.2  317.48
  4959.5  317.97  4969.7  317.18  4983.6  315.23  4993.6  310.42  5006.8  310.42
  5010.4  313.72  5020.6  317.61  5170.5  317.18  5271.9  317.14  5363.5  316.16
  5768.5  318.25  5866.2  320.93  5917.1  320.56  6083.5  323.39  6268.6  329.11
#Mann= 7 ,-1 , 0
    3615     .11       0    4809     .17       0  4969.7     .09       0
  5020.6     .17       0  5170.5     .11       0  5271.9     .15       0
  5363.5     .11       0
Bank Sta=4969.7,5020.6
XS Rating Curve= 0 ,0
Exp/Cntr=0.3,0.1

Type RM Length L Ch R = 1 ,1544    ,1079,1079,1079
BEGIN DESCRIPTION:
CCLC 091 2.0
END DESCRIPTION:
XS GIS Cut Line= 3
       3699279.1     10219027.46      3697859.82     10218068.25
      3696567.88     10218761.06
#Sta/Elev= 30
  3185.4  325.16  3328.2  324.73  3370.2  322.59  3472.1  321.48  3852.7  319.26
  3911.1  317.57  4299.2  316.67  4422.1   315.3  4437.1  316.21    4515  314.99
  4660.4  315.93  4792.8  316.62  4876.7  315.81  4982.1  316.89  4991.4  313.37
  4997.3  308.62  5010.7  308.62  5014.1  312.63    5026  316.38  5042.2  314.52
  5064.1  314.67  5070.9  316.63  5111.5  316.63  5441.8  316.49  5559.1  318.23
  5832.7  322.17  6016.8  322.46  6033.1  323.49  6060.7   322.7  6364.4  330.09
#Mann= 8 ,-1 , 0
  3185.4     .11       0  4660.4     .17       0  4792.8     .15       0
  4982.1     .09       0    5026     .15       0  5111.5     .11       0
  5559.1     .17       0  5832.7     .11       0
Bank Sta=4982.1,5026
XS Rating Curve= 0 ,0
Exp/Cntr=0.3,0.1

Type RM Length L Ch R = 1 ,465     ,0,0,0
BEGIN DESCRIPTION:
CCLC 091 1.0
END DESCRIPTION:
XS GIS Cut Line= 4
      3699292.13     10218849.54      3698607.01     10217684.22
      3697829.44     10217603.84      3696117.87     10219011.06
#Sta/Elev= 30
  2915.7  326.11  3018.5  323.62  3370.1  320.33  3911.5  319.52  4407.4  315.85
  4548.1  313.31  4665.5  314.34  4749.2  315.03  4789.4  312.18    4890  313.41
  4920.1  315.53  4980.4  315.18  4993.7  306.87  5007.3  306.87  5010.6  314.71
  5023.9  316.05  5090.4  314.47  5182.9  315.31  5205.2  313.34  5382.4  316.79
  5746.6  317.69  5807.3  318.45  5993.7   319.7  6234.7  324.69    6498  325.64
  6774.3  331.73    6846  335.24  6881.2  334.94  7080.6  341.85    7265  345.13
#Mann= 7 ,-1 , 0
  2915.7     .11       0  4665.5     .15       0  4980.4     .09       0
  5010.6     .15       0  5023.9     .11       0  5746.6     .17       0
  5807.3     .11       0
Bank Sta=4980.4,5010.6
XS Rating Curve= 0 ,0
Exp/Cntr=0.3,0.1

Chan Stop Cuts=-1
Use User Specified Reach Order=0
Composite Channel Slope=5