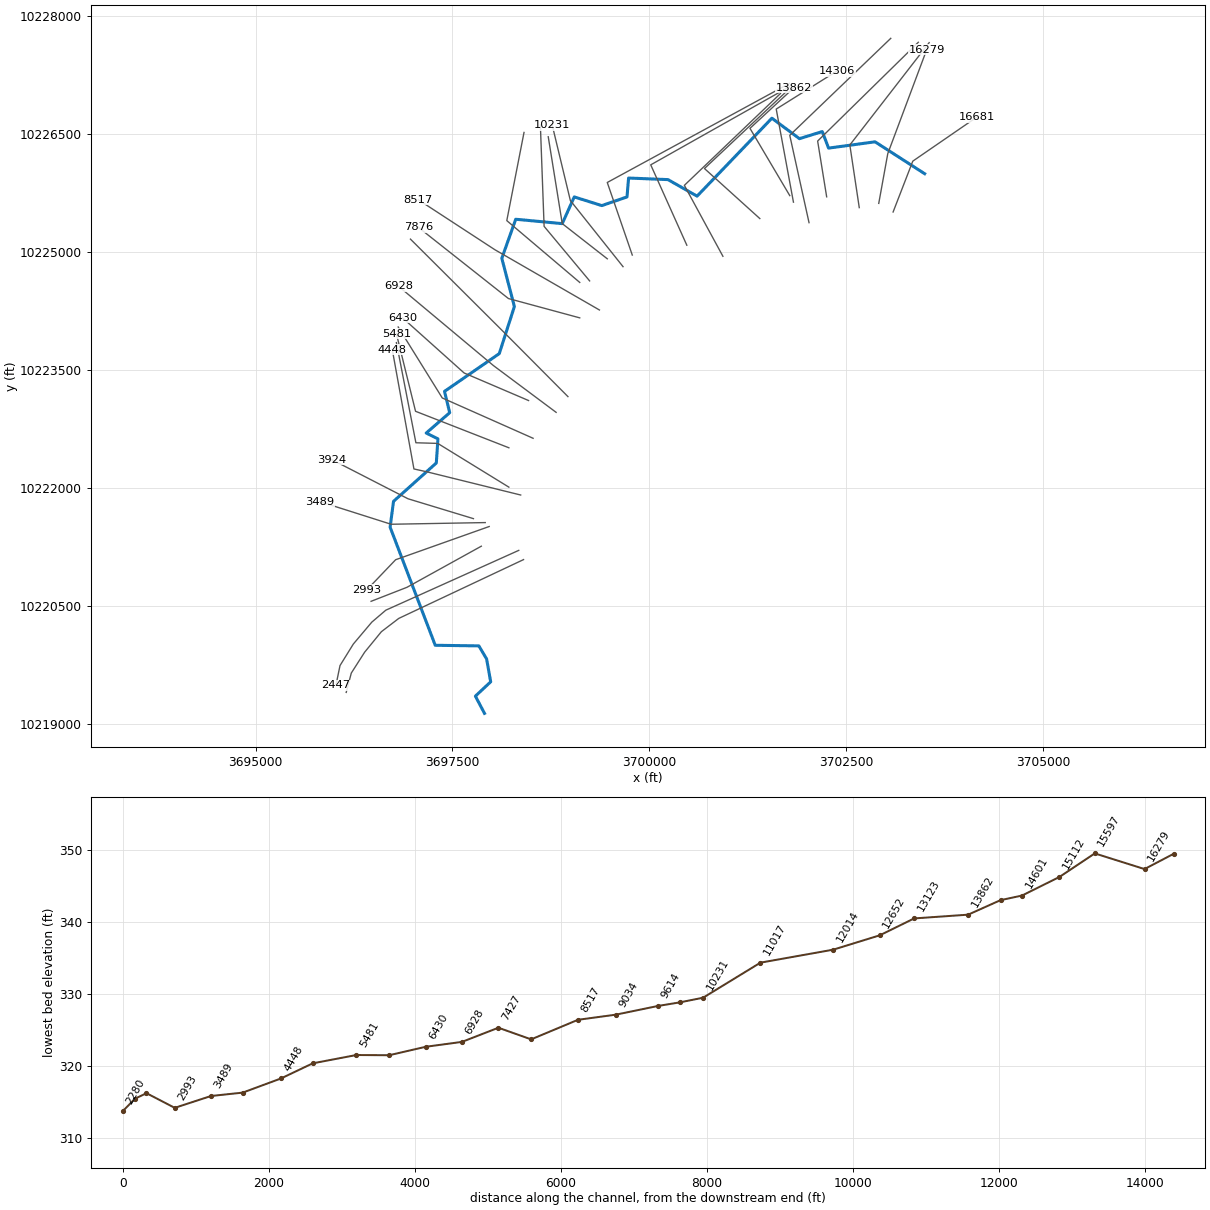
--- CCLC 092.prj (project) ---

Proj Title=CCLC 092 Base Level Engineering
Current Plan=p01
Default Exp/Contr=0.3,0.1
English Units
Geom File=g01
Flow File=f01
Flow File=f02
Plan File=p01
Y Axis Title=Elevation
X Axis Title(PF)=Main Channel Distance
X Axis Title(XS)=Station
BEGIN DESCRIPTION:
CCLC 092
END DESCRIPTION:
DSS Export Rating Curves= 0
DSS Export Rating Curve Sorted= 0
DSS Export Volume Flow Curves= 0
DXF OffsetX= 0
DXF OffsetY= 0
DXF ScaleX= 1
DXF ScaleY= 10

--- CCLC 092.p01 (plan) ---

Plan Title=Multiple Run
Short Identifier=Multiple
Geom File=g01
Flow File=f01
Subcritical Flow
K Sum by GR= 0
Std Step Tol= 0.01
Critical Tol= 0.01
Num of Std Step Trials= 20
Max Error Tol= 0.3
Flow Tol Ratio= 0.001
Split Flow NTrial= 30
Split Flow Tol= 0.02
Split Flow Ratio= 0.02
Log Output Level= 0
Friction Slope Method= 1
Unsteady Friction Slope Method= 2
Unsteady Bridges Friction Slope Method= 1
Parabolic Critical Depth
Global Vel Dist=  1 , 1 , 1
Global Log Level= 0
CheckData=True
Encroach Param= -1, 0, 0, 0
BEGIN DESCRIPTION:
Multiple Run
END DESCRIPTION:

--- CCLC 092.f01 (steady flow) ---

Flow Title=Multiple
Program Version=4.10
Number of Profiles= 7
Profile Names=10-year,25-year,50-year,1pct_min,100-year,1pct_plu,500-year
River Rch & RM=CCLC 092,Reach-1         ,16681
     510     689     929     413    1248    3769    2327
River Rch & RM=CCLC 092,Reach-1         ,15597
     833    1148    1567     704    2126    6420    4045
River Rch & RM=CCLC 092,Reach-1         ,10231
    1241    1735    2393    1083    3270    9875    6321
River Rch & RM=CCLC 092,Reach-1         ,3924
    1896    2704    3780    1730    5225   15779   10344
Boundary for River Rch & Prof#=CCLC 092,Reach-1         , 1
Up Type= 0
Dn Type= 3
Dn Slope=0.005
Boundary for River Rch & Prof#=CCLC 092,Reach-1         , 2
Up Type= 0
Dn Type= 3
Dn Slope=0.005
Boundary for River Rch & Prof#=CCLC 092,Reach-1         , 3
Up Type= 0
Dn Type= 3
Dn Slope=0.005
Boundary for River Rch & Prof#=CCLC 092,Reach-1         , 4
Up Type= 0
Dn Type= 3
Dn Slope=0.005
Boundary for River Rch & Prof#=CCLC 092,Reach-1         , 5
Up Type= 0
Dn Type= 3
Dn Slope=0.005
Boundary for River Rch & Prof#=CCLC 092,Reach-1         , 6
Up Type= 0
Dn Type= 3
Dn Slope=0.005
Boundary for River Rch & Prof#=CCLC 092,Reach-1         , 7
Up Type= 0
Dn Type= 3
Dn Slope=0.005
DSS Import GetInterval= 0
DSS Import GetPeak= 0
DSS Import FillOption= 0

--- CCLC 092.f02 (steady flow) ---

Flow Title=Orig_BLE_Flows
Program Version=4.10
Number of Profiles= 7
Profile Names=10-year,25-year,50-year,1pct_min,100-year,1pct_plu,500-year
River Rch & RM=CCLC 092,Reach-1         ,16681
     510     675     808     318     960    2900    1353
River Rch & RM=CCLC 092,Reach-1         ,15597
     833    1125    1363     541    1635    4938    2352
River Rch & RM=CCLC 092,Reach-1         ,10231
    1241    1701    2081     833    2515    7596    3675
River Rch & RM=CCLC 092,Reach-1         ,3924
    1896    2651    3287    1331    4019   12138    6014
Boundary for River Rch & Prof#=CCLC 092,Reach-1         , 1
Up Type= 0
Dn Type= 3
Dn Slope=0.005
Boundary for River Rch & Prof#=CCLC 092,Reach-1         , 2
Up Type= 0
Dn Type= 3
Dn Slope=0.005
Boundary for River Rch & Prof#=CCLC 092,Reach-1         , 3
Up Type= 0
Dn Type= 3
Dn Slope=0.005
Boundary for River Rch & Prof#=CCLC 092,Reach-1         , 4
Up Type= 0
Dn Type= 3
Dn Slope=0.005
Boundary for River Rch & Prof#=CCLC 092,Reach-1         , 5
Up Type= 0
Dn Type= 3
Dn Slope=0.005
Boundary for River Rch & Prof#=CCLC 092,Reach-1         , 6
Up Type= 0
Dn Type= 3
Dn Slope=0.005
Boundary for River Rch & Prof#=CCLC 092,Reach-1         , 7
Up Type= 0
Dn Type= 3
Dn Slope=0.005
DSS Import GetInterval= 0
DSS Import GetPeak= 0
DSS Import FillOption= 0

--- CCLC 092.g01 (geometry) ---

Geom Title=Existing Conditions
Program Version=4.10

River Reach=CCLC 092        ,Reach-1
Reach XY= 30
      3703498.23     10225991.84      3702868.23     10226396.84
      3702278.23     10226316.84      3702198.23     10226526.84
      3701908.23     10226436.84      3701558.23     10226696.84
      3700608.23     10225706.84      3700238.23     10225916.84
      3699738.23     10225936.84      3699718.23     10225696.84
      3699398.23     10225586.84      3699048.23     10225696.84
      3698895.82     10225357.85      3698304.87     10225413.45
      3698128.27     10224917.36      3698287.89     10224304.86
      3698095.94     10223706.87      3697400.43     10223227.25
      3697466.35      10222956.8      3697168.07     10222697.86
      3697316.98     10222624.74      3697296.27     10222317.62
       3696752.9     10221830.78       3696709.7     10221502.62
      3697282.68     10220002.72      3697836.85     10219995.02
      3697935.26     10219828.44      3697986.88     10219538.71
      3697792.59     10219356.83      3697908.37      10219137.9

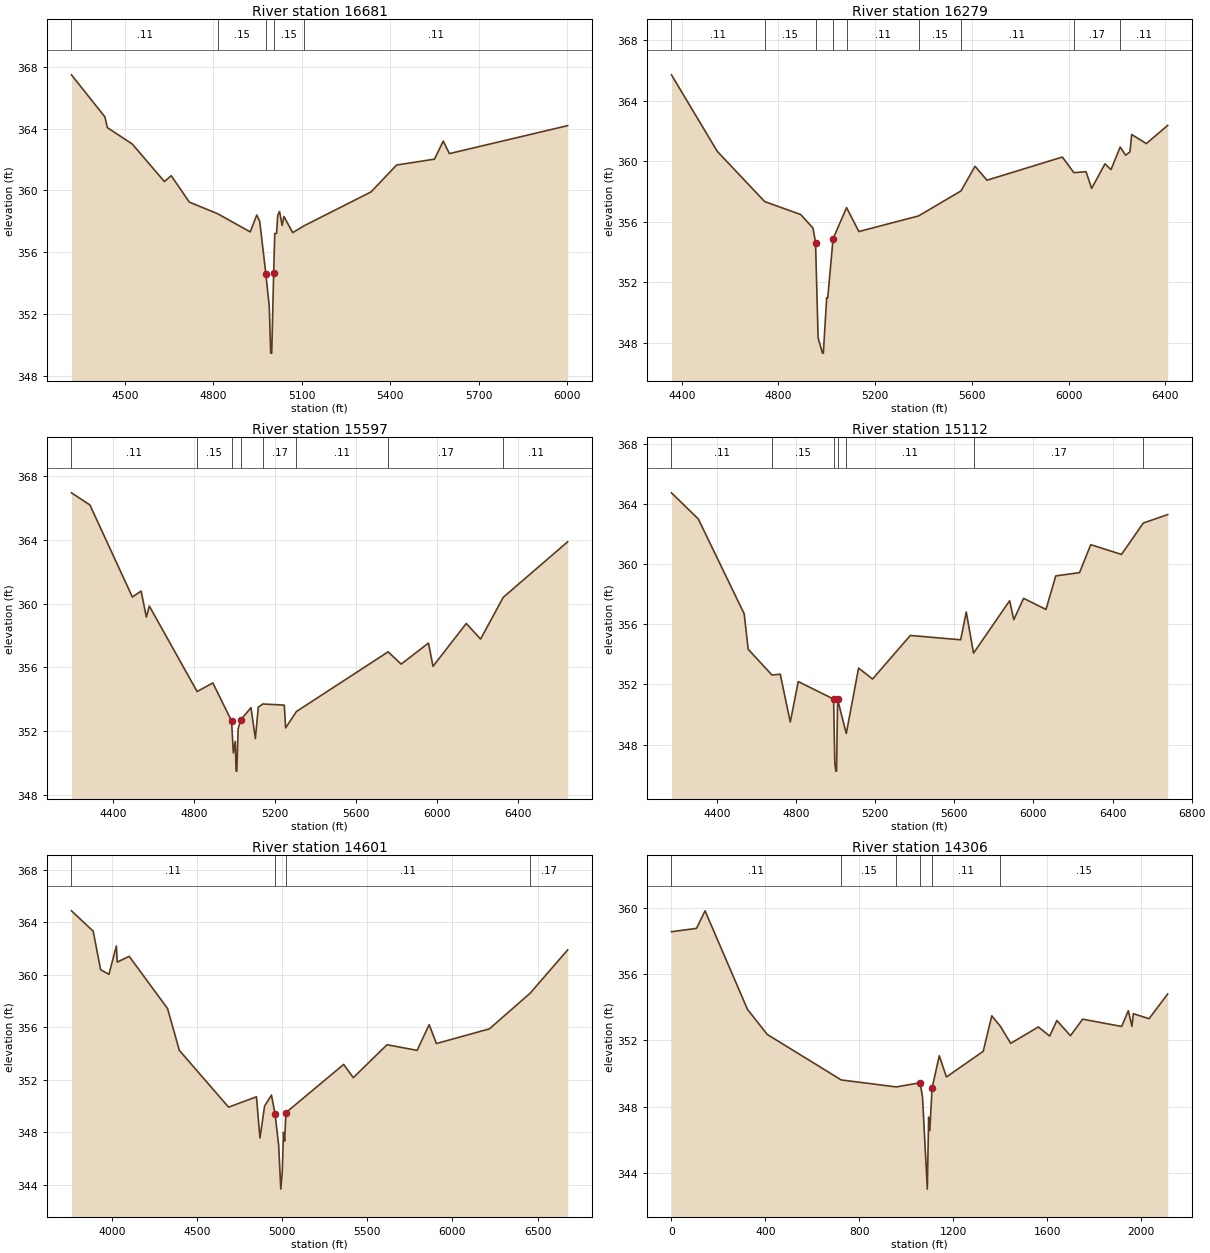
Type RM Length L Ch R = 1 ,16681   ,402,402,402
BEGIN DESCRIPTION:
CCLC 092 29.0
END DESCRIPTION:
XS GIS Cut Line= 3
      3703097.67     10225505.45      3703347.67     10226151.27
      3704164.12     10226712.92
#Sta/Elev= 30
  4318.2  367.48  4431.5  364.76  4440.1  364.06  4524.5     363  4633.5  360.57
  4656.6  360.95    4718  359.24  4814.8  358.48  4924.7  357.31  4946.8   358.4
  4956.9     358  4977.9354.5561  4989.1  352.53  4994.2  349.46  4997.7  349.46
 5004.16354.6375  5007.9  357.21  5013.9  357.21  5018.1   358.4  5024.2  358.63
    5033  357.73  5039.1  358.31  5068.8  357.26  5106.9   357.7  5334.7   359.9
  5421.3  361.64  5549.8  362.02  5579.6  363.19  5600.5  362.38  6001.7  364.19
#Mann= 5 ,-1 , 0
  4318.2     .11       0  4814.8     .15       0  4977.9     .09       0
 5004.16     .15       0  5106.9     .11       0
Bank Sta=4977.9,5004.16
XS Rating Curve= 0 ,0
Exp/Cntr=0.3,0.1

Type RM Length L Ch R = 1 ,16279   ,682,682,682
BEGIN DESCRIPTION:
Mapping XS c195b3f4
END DESCRIPTION:
XS GIS Cut Line= 3
      3702915.36     10225614.77      3703030.08     10226246.84
      3703524.41     10227567.03
#Sta/Elev= 30
  4357.6  365.71  4546.9  360.66  4742.9  357.34  4892.5  356.48  4943.3  355.58
  4953.5  354.62  4964.1  348.34  4982.2  347.33  4985.7  347.33  4999.6  350.99
    5004  350.99  5025.9  354.88  5081.8  356.94  5132.6  355.36  5379.3  356.39
  5554.7  358.04  5613.2  359.67  5662.5  358.75  5974.2  360.28  6021.8  359.25
  6072.3  359.31  6095.3  358.21  6150.5  359.83  6175.4  359.45  6213.3  360.94
    6236   360.4  6253.8  360.62  6260.9  361.77  6321.5  361.17  6409.7  362.37
#Mann= 9 ,-1 , 0
  4357.6     .11       0  4742.9     .15       0  4953.5     .09       0
  5025.9     .15       0  5081.8     .11       0  5379.3     .15       0
  5554.7     .11       0  6021.8     .17       0  6213.3     .11       0
Bank Sta=4953.5,5025.9
XS Rating Curve= 0 ,0
Exp/Cntr=0.3,0.1

Type RM Length L Ch R = 1 ,15597   ,485,485,485
BEGIN DESCRIPTION:
CCLC 092 28.0
END DESCRIPTION:
XS GIS Cut Line= 3
      3702667.85     10225561.09      3702548.23     10226356.84
      3703555.82     10227656.26
#Sta/Elev= 30
  4195.3  366.95  4286.3  366.19  4495.8  360.42  4539.1  360.79  4564.8  359.16
  4579.6  359.85  4815.4  354.49    4893  355.03  4985.5352.6444  4994.2  350.64
  5003.8  351.36  5007.8   349.5  5011.4   349.5  5017.8  352.15  5030.7  352.71
  5081.3  353.48  5102.9  351.54  5117.3  353.51  5139.3  353.71  5245.8  353.64
  5252.2  352.21  5305.8  353.24  5758.1  356.98  5822.5  356.21  5957.4  357.53
  5979.7  356.07  6143.9  358.76  6214.5  357.78  6326.5   360.4  6644.3  363.88
#Mann= 8 ,-1 , 0
  4195.3     .11       0  4815.4     .15       0  4985.5     .09       0
  5030.7     .15       0  5139.3     .17       0  5305.8     .11       0
  5758.1     .17       0  6326.5     .11       0
Bank Sta=4985.5,5030.7
XS Rating Curve= 0 ,0
Exp/Cntr=0.3,0.1

Type RM Length L Ch R = 1 ,15112   ,511,511,511
BEGIN DESCRIPTION:
CCLC 092 27.0
END DESCRIPTION:
XS GIS Cut Line= 3
      3702253.92     10225698.11      3702139.33     10226406.48
      3703417.82     10227661.04
#Sta/Elev= 30
  4169.8  364.75  4305.6  363.01  4537.5   356.7  4557.7  354.34  4677.7  352.63
  4719.8  352.68  4770.5   349.5    4811  352.19  4989.6351.0228  4995.7  346.77
  5000.9  346.23  5004.5  346.23  5009.8  351.01  5053.6  348.73  5115.9  353.09
  5186.6  352.36  5377.5  355.26    5632  354.97  5660.3  356.82  5697.1  354.08
  5879.6  357.57  5900.8  356.31  5950.2  357.73  6063.4  356.99  6112.9  359.22
  6233.1  359.44  6289.7   361.3  6445.3  360.65  6555.4  362.74  6678.6   363.3
#Mann= 7 ,-1 , 0
  4169.8     .11       0  4677.7     .15       0  4989.6     .09       0
  5009.8     .15       0  5053.6     .11       0  5697.1     .17       0
  6555.4     .11       0
Bank Sta=4989.6,5009.8
XS Rating Curve= 0 ,0
Exp/Cntr=0.3,0.1

Type RM Length L Ch R = 1 ,14601   ,295,295,295
BEGIN DESCRIPTION:
CCLC 092 26.0
END DESCRIPTION:
XS GIS Cut Line= 3
      3702029.97     10225369.98      3701785.17      10226479.4
      3703067.86     10227711.08
#Sta/Elev= 30
  3762.6  364.88  3890.1  363.33  3933.8  360.39  3982.6  360.04  4026.3   362.2
  4031.4  360.97  4101.7  361.41  4326.9  357.43  4396.2  354.24  4685.4  349.91
  4849.2   350.7  4869.7  347.56    4897     350  4937.2  350.83  4958.2  349.42
  4979.6     347    4992  343.66  5000.7  344.99  5007.9     348  5014.8  347.32
  5022.1  349.49  5361.4  353.17    5418  352.16  5616.1  354.67  5792.8  354.24
  5863.6   356.2  5906.1  354.76  6217.4  355.88  6456.6   358.6    6677   361.9
#Mann= 4 ,-1 , 0
  3762.6     .11       0  4958.2     .07       0  5022.1     .11       0
  6456.6     .17       0
Bank Sta=4958.2,5022.1
XS Rating Curve= 0 ,0
Exp/Cntr=0.3,0.1

Type RM Length L Ch R = 1 ,14306   ,444,444,444
BEGIN DESCRIPTION:
Mapping XS 6f113a05
END DESCRIPTION:
XS GIS Cut Line= 3
      3701832.04     10225630.44      3701613.29     10226812.73
      3702385.12     10227296.31
#Sta/Elev= 30
       0  358.56   106.4  358.76     143  359.82   323.2  353.88   407.4  352.36
   722.7  349.61   956.6  349.19  1058.3  349.44  1068.5  348.56  1088.8  343.02
  1094.4  347.37  1099.4  346.55  1109.1  349.12  1139.7  351.07  1170.2  349.79
  1326.7  351.34  1363.2  353.48  1399.7  352.85  1443.8  351.82  1561.2  352.81
  1609.5  352.26  1640.2   353.2  1697.9  352.28  1749.8  353.28  1915.8  352.84
  1944.2  353.79  1959.6  352.85  1965.5  353.61  2032.6  353.31  2111.6   354.8
#Mann= 6 ,-1 , 0
       0     .11       0   722.7     .15       0   956.6     .11       0
  1058.3     .06       0  1109.1     .11       0  1399.7     .15       0
Bank Sta=1058.3,1109.1
XS Rating Curve= 0 ,0
Exp/Cntr=0.3,0.1

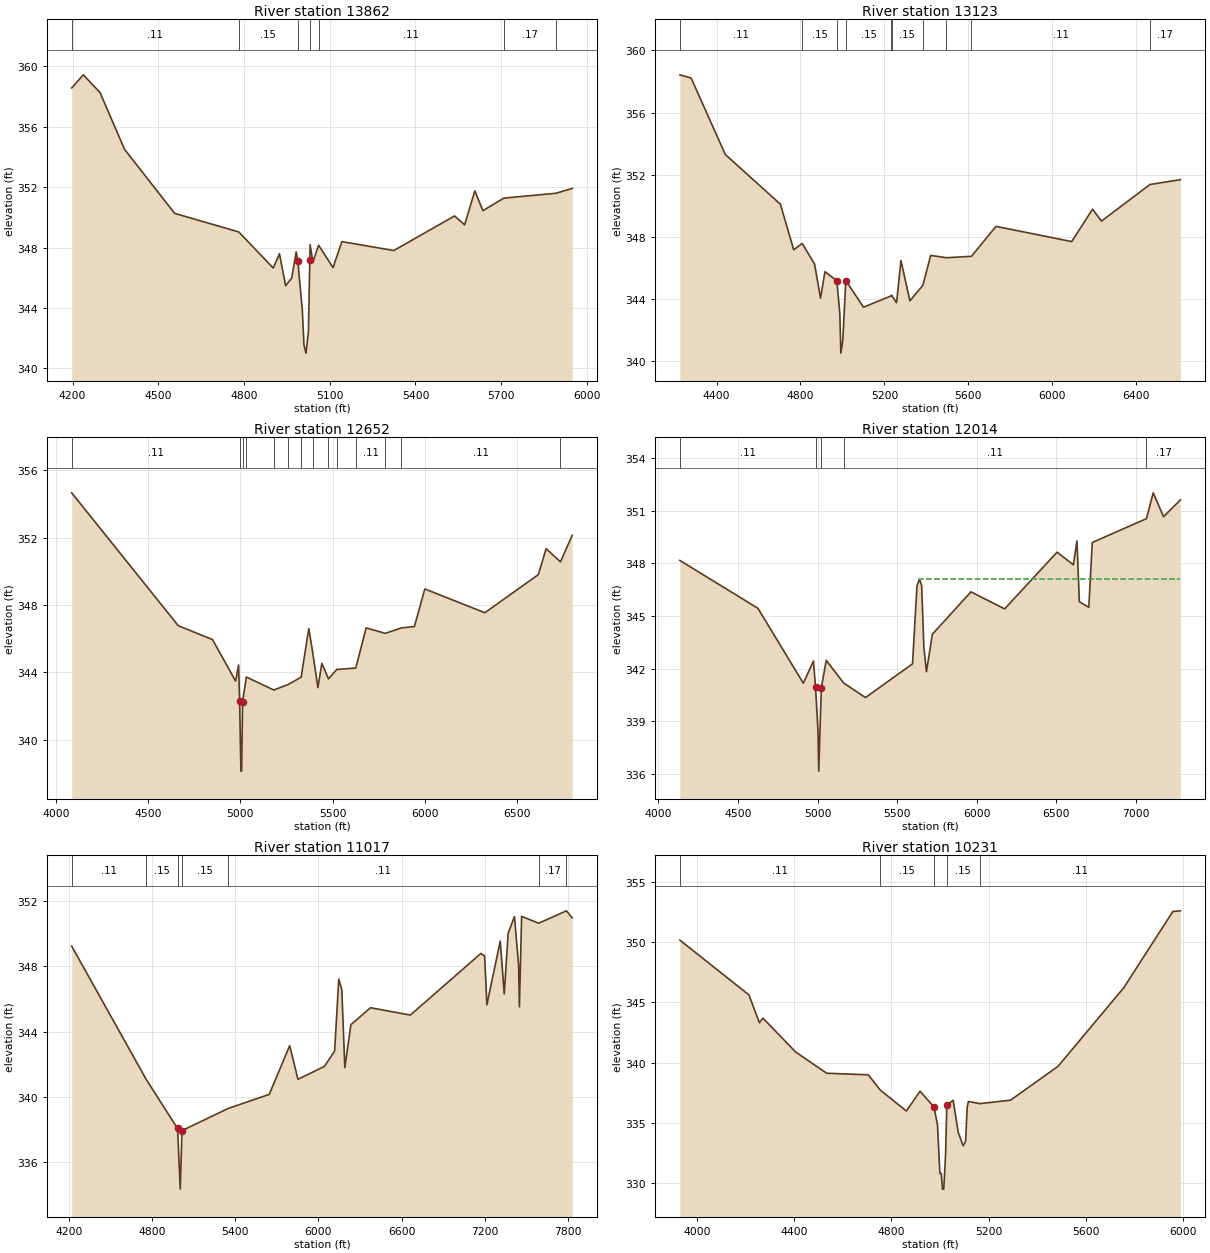
Type RM Length L Ch R = 1 ,13862   ,739,739,739
BEGIN DESCRIPTION:
Mapping XS e86b6d93
END DESCRIPTION:
XS GIS Cut Line= 3
      3701785.14     10225713.81      3701279.96     10226567.94
      3701837.26     10227083.58
#Sta/Elev= 30
    4197  358.56  4237.6  359.43  4296.1  358.26  4381.9   354.5  4557.4  350.26
  4781.8  349.03  4902.5  346.64  4924.1  347.59  4945.6  345.47    4967  345.98
  4982.6  347.71  4988.4   347.1  5004.1  343.86  5009.9  341.56  5016.9  341.01
  5025.5  342.44  5030.3347.1986  5031.3  348.19  5041.2  347.04  5061.1  348.15
  5111.7  346.67  5142.5  348.39  5324.3   347.8  5536.9  350.09  5572.1   349.5
  5607.8  351.75  5636.1  350.44  5709.4  351.27  5891.6  351.59  5948.6  351.91
#Mann= 7 ,-1 , 0
    4197     .11       0  4781.8     .15       0  4988.4     .09       0
  5030.3     .15       0  5061.1     .11       0  5709.4     .17       0
  5891.6     .15       0
Bank Sta=4988.4,5030.3
XS Rating Curve= 0 ,0
Exp/Cntr=0.3,0.1

Type RM Length L Ch R = 1 ,13123   ,471,471,471
BEGIN DESCRIPTION:
Mapping XS e29a1355
END DESCRIPTION:
XS GIS Cut Line= 3
      3701404.98     10225422.08      3700701.83     10226057.52
      3701748.68     10227041.88
#Sta/Elev= 30
  4225.4  358.43  4279.1  358.22    4442  353.29  4704.3  350.09  4767.8  347.15
  4808.4  347.56  4867.2  346.23  4895.5  344.03  4916.5  345.74  4973.3  345.16
  4987.5  343.03  4992.4  340.49  5001.7  341.34  5015.9  345.17  5100.4  343.45
  5233.6  344.19    5234  344.22  5257.8  343.74  5278.8  346.46  5321.3  343.86
  5383.2  344.86  5420.4  346.79  5495.5  346.64  5614.7  346.73  5731.5  348.66
  6092.5  347.68  6191.6  349.77  6234.1     349  6465.1  351.36  6610.1  351.67
#Mann= 10 ,-1 , 0
  4225.4     .11       0  4808.4     .15       0  4973.3     .09       0
  5015.9     .15       0  5233.6     .11       0    5234     .15       0
  5383.2     .11       0  5495.5     .15       0  5614.7     .11       0
  6465.1     .17       0
Bank Sta=4973.3,5015.9
XS Rating Curve= 0 ,0
Exp/Cntr=0.3,0.1

Type RM Length L Ch R = 1 ,12652   ,638,638,638
BEGIN DESCRIPTION:
CCLC 092 25.0
END DESCRIPTION:
XS GIS Cut Line= 3
       3700936.2     10224942.95      3700446.62     10225843.98
      3701667.87     10227011.09
#Sta/Elev= 30
  4085.1  354.65  4663.4  346.77  4848.7  345.95  4974.1  343.49  4990.3  344.44
  4995.9   342.3  5002.9  338.15  5006.7  338.15  5012.1  342.25  5032.3  343.73
  5181.3  342.96  5259.9  343.29  5329.5  343.72  5371.1   346.6  5391.6  345.24
  5420.5   343.1  5441.9  344.54  5477.7  343.62  5523.2  344.18  5625.9  344.26
  5682.2  346.64  5786.6  346.32  5873.7  346.64  5943.8  346.72  6000.5  348.95
    6326  347.54    6616   349.8  6658.4  351.34    6736  350.56  6799.8  352.13
#Mann= 14 ,-1 , 0
  4085.1     .11       0  4995.9     .06       0  5012.1     .11       0
  5032.3     .15       0  5181.3     .11       0  5259.9     .15       0
  5329.5     .11       0  5391.6     .15       0  5477.7     .11       0
  5523.2     .15       0  5625.9     .11       0  5786.6     .15       0
  5873.7     .11       0    6736     .17       0
Bank Sta=4995.9,5012.1
XS Rating Curve= 0 ,0
Exp/Cntr=0.3,0.1

Type RM Length L Ch R = 1 ,12014   ,997,997,997
BEGIN DESCRIPTION:
CCLC 092 24.0
END DESCRIPTION:
XS GIS Cut Line= 3
      3700477.86      10225083.6      3700019.54      10226104.4
      3701783.98     10227098.53
#Sta/Elev= 30
  4135.4  348.16  4625.9  345.43  4910.9  341.17  4974.5  342.43  4987.6  340.93
  5003.1  338.45  5007.7  336.16  5024.1340.9122  5054.9  342.47  5164.2  341.18
  5301.3  340.35  5596.8  342.27    5625  346.72  5640.9  347.09  5654.2  346.73
  5668.3   343.2  5684.2  341.82  5721.8  343.96  5964.1  346.37  6175.5   345.4
  6504.9  348.63  6607.5  347.91  6629.8  349.27    6645  345.81  6704.3  345.49
    6726  349.18  7066.5  350.54  7108.9  352.01  7173.9  350.65  7279.6  351.61
#Mann= 5 ,-1 , 0
  4135.4     .11       0  4987.6     .06       0  5024.1     .17       0
  5164.2     .11       0  7066.5     .17       0
#XS Ineff= 2 , 0
                         5638.59          347.09
Permanent Ineff=
       F       F
Bank Sta=4987.6,5024.1
XS Rating Curve= 0 ,0
Exp/Cntr=0.3,0.1

Type RM Length L Ch R = 1 ,11017   ,786,786,786
BEGIN DESCRIPTION:
CCLC 092 22.0
END DESCRIPTION:
XS GIS Cut Line= 3
      3699785.17     10224958.56      3699467.46     10225880.44
      3701783.97     10227140.21
#Sta/Elev= 30
  4219.1  349.23  4755.2   341.1  4983.3  338.07  5002.5  334.36    5015  337.94
  5346.7  339.29  5644.9  340.16  5792.2  343.14    5852  341.08    6043  341.87
  6116.7  342.81  6146.5  347.21  6168.4  346.57  6190.2  341.79  6233.9  344.42
  6375.5  345.46  6663.1  345.01  7171.6  348.78  7199.1  348.63  7215.3  345.64
  7311.9  349.54  7340.7  346.31  7368.8  350.01  7414.3  351.04  7444.2  348.08
  7449.9  345.52  7466.1  351.05  7589.3  350.63  7789.6  351.39  7831.1  350.96
#Mann= 7 ,-1 , 0
  4219.1     .11       0  4755.2     .15       0  4983.3     .09       0
    5015     .15       0  5346.7     .11       0  7589.3     .17       0
  7789.6     .15       0
Bank Sta=4983.3,5015
XS Rating Curve= 0 ,0
Exp/Cntr=0.3,0.1

Type RM Length L Ch R = 1 ,10231   ,322,322,322
BEGIN DESCRIPTION:
CCLC 092 21.0
END DESCRIPTION:
XS GIS Cut Line= 3
      3699667.86     10224811.06      3698998.71     10225651.27
      3698767.85     10226611.08
#Sta/Elev= 30
  3928.5  350.15  4212.8  345.61    4256   343.3  4270.5  343.68    4405  340.88
  4533.1  339.11  4704.5  338.98  4753.1  337.73  4861.4  335.98  4917.5  337.62
  4975.2  336.31  4989.6   334.8  4999.3   330.8  5005.1   330.8  5010.1   329.5
  5015.3   329.5  5022.7  332.31  5027.9  336.48  5053.8  336.87    5075  334.21
    5095   333.1  5105.3  333.45  5111.8   336.3  5116.9  336.77    5164  336.59
  5290.4  336.88  5485.8  339.68  5756.5   346.2  5958.9  352.53  5989.8  352.58
#Mann= 5 ,-1 , 0
  3928.5     .11       0  4753.1     .15       0  4975.2     .09       0
  5027.9     .15       0    5164     .11       0
Bank Sta=4975.2,5027.9
XS Rating Curve= 0 ,0
Exp/Cntr=0.3,0.1

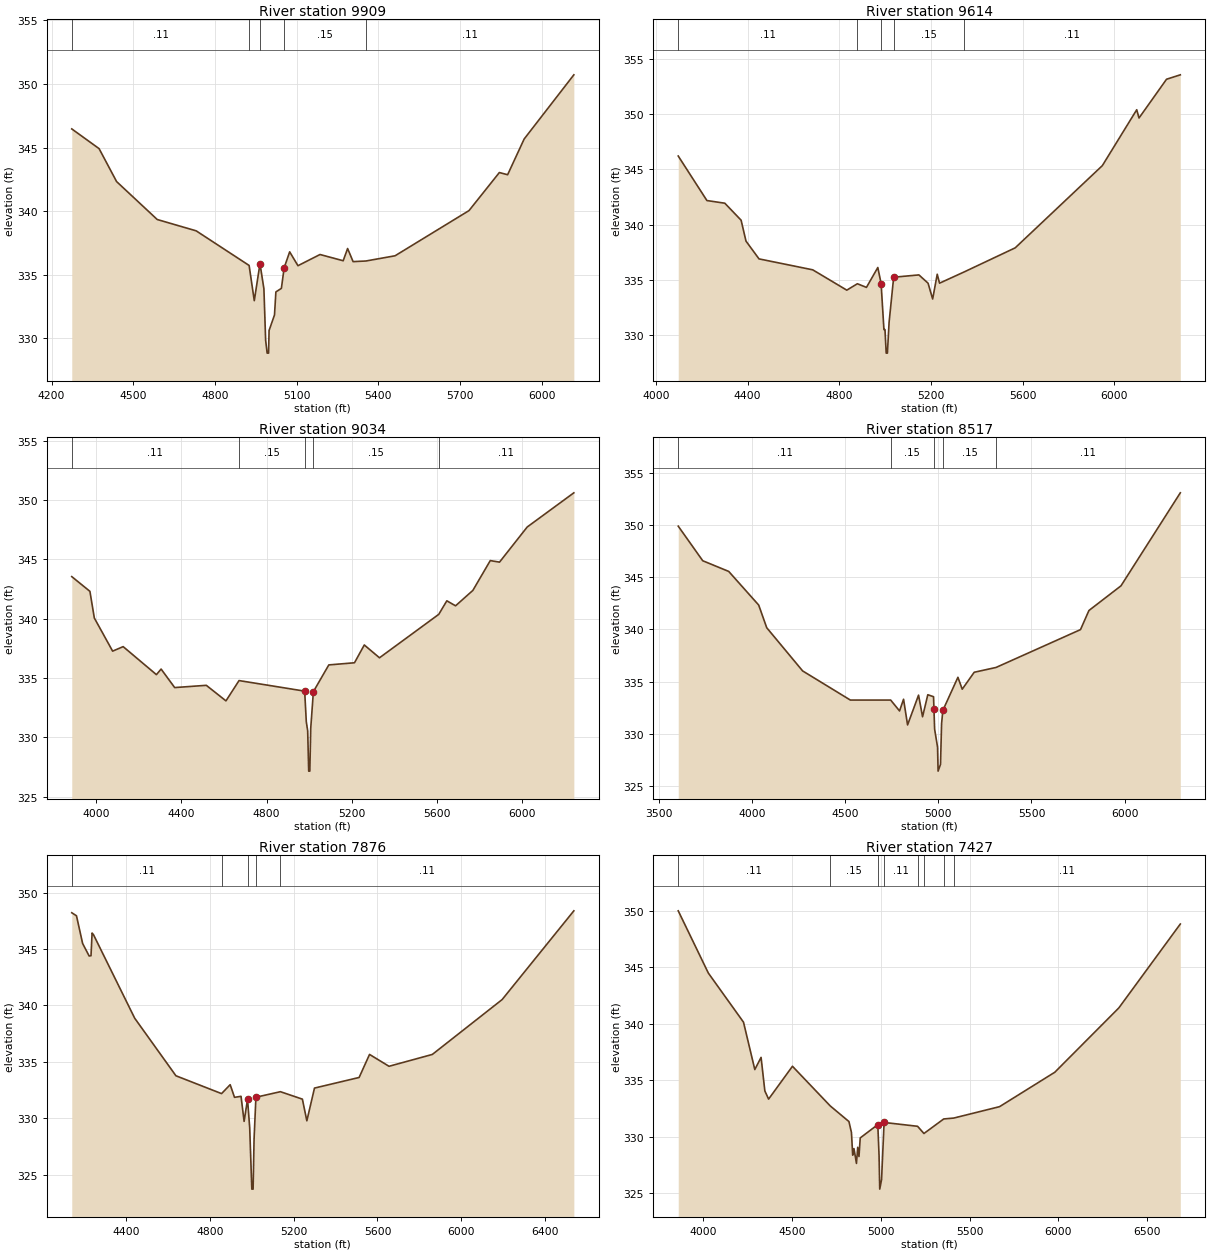
Type RM Length L Ch R = 1 ,9909    ,295,295,295
BEGIN DESCRIPTION:
CCLC 092 20.0
END DESCRIPTION:
XS GIS Cut Line= 3
      3699467.82     10224911.09      3698895.82     10225357.85
      3698717.85     10226461.09
#Sta/Elev= 30
  4274.2  346.47  4374.5  344.92  4438.8  342.33    4588  339.35  4730.9  338.46
  4925.3  335.74  4944.3  332.97  4965.2  335.88  4979.6  333.91    4986  329.85
  4991.5  328.85  4996.7  328.85  4998.6  330.63  5018.5  331.85  5023.6  333.66
  5043.8  333.94  5053.9  335.55  5074.2  336.81  5104.6  335.72  5185.6   336.6
  5270.7  336.11  5286.9  337.07  5307.1  336.04  5354.3  336.09  5461.2   336.5
  5732.6  340.05    5844  343.04  5874.4  342.87  5935.2  345.68  6117.5  350.72
#Mann= 5 ,-1 , 0
  4274.2     .11       0  4925.3     .15       0  4965.2     .09       0
  5053.9     .15       0  5354.3     .11       0
Bank Sta=4965.2,5053.9
XS Rating Curve= 0 ,0
Exp/Cntr=0.3,0.1

Type RM Length L Ch R = 1 ,9614    ,580,580,580
BEGIN DESCRIPTION:
CCLC 092 19.0
END DESCRIPTION:
XS GIS Cut Line= 3
       3699243.5     10224630.43      3698665.37     10225323.15
      3698617.85      10226611.1
#Sta/Elev= 30
  4097.4   346.2  4222.6  342.17  4300.7  341.93  4371.8  340.39  4393.1   338.5
  4449.9  336.89  4684.4   335.9    4833  334.06  4879.2  334.64  4918.8  334.31
  4968.4  336.11  4982.7  334.66  4995.1  330.49  4999.7  330.49    5005  328.36
  5010.2  328.36  5017.6  331.15  5037.6  335.23  5147.7  335.44  5187.7  334.69
  5207.7  333.26  5227.7   335.5  5237.8  334.69  5345.3  335.71    5568  337.89
  5948.2  345.33  6098.3  350.39  6108.3  349.64  6228.4  353.15  6288.5  353.55
#Mann= 5 ,-1 , 0
  4097.4     .11       0  4879.2     .15       0  4982.7     .09       0
  5037.6     .15       0  5345.3     .11       0
Bank Sta=4982.7,5037.6
XS Rating Curve= 0 ,0
Exp/Cntr=0.3,0.1

Type RM Length L Ch R = 1 ,9034    ,517,517,517
BEGIN DESCRIPTION:
CCLC 092 18.0
END DESCRIPTION:
XS GIS Cut Line= 3
      3699117.82      10224611.1      3698191.42     10225396.07
      3698410.16     10226515.85
#Sta/Elev= 30
  3886.4  343.54  3971.5   342.3  3992.3  340.05  4078.1  337.26  4127.5  337.64
  4283.5  335.28  4305.5  335.75  4369.2  334.19  4517.5  334.38  4609.7  333.07
  4671.1  334.78  4978.9  333.89  4986.6  331.31  4993.1  330.54  4997.8  327.15
  5003.1  327.15  5007.4  330.77 5019.78333.8465  5092.2   336.1  5212.6  336.28
  5258.6  337.78  5329.9   336.7  5607.9  340.36  5645.8   341.5  5686.8  341.08
    5768  342.38  5849.6  344.89    5893  344.76  6022.8  347.72  6241.6   350.6
#Mann= 5 ,-1 , 0
  3886.4     .11       0  4671.1     .15       0  4978.9     .09       0
 5019.78     .15       0  5607.9     .11       0
Bank Sta=4978.9,5019.78
XS Rating Curve= 0 ,0
Exp/Cntr=0.3,0.1

Type RM Length L Ch R = 1 ,8517    ,641,641,641
BEGIN DESCRIPTION:
CCLC 092 17.0
END DESCRIPTION:
XS GIS Cut Line= 3
      3699367.88     10224261.06      3698040.37     10225026.27
      3697067.87     10225661.06
#Sta/Elev= 30
  3604.9  349.88  3736.4  346.57  3875.7  345.55  4036.6  342.33  4079.7  340.16
  4272.2  336.03  4528.3  333.24  4744.6  333.24  4792.2   332.2  4813.7  333.32
  4835.3  330.86  4894.2  333.71  4915.7  331.64  4943.8  333.75  4974.6  333.56
 4976.83332.3681  4980.4  330.46  4996.2  328.73    4999  326.44    5012  327.09
  5017.7  330.98  5024.6  332.25  5105.4  335.42  5128.5  334.28  5192.8   335.9
  5309.9  336.36    5763  339.98  5808.3  341.81  5980.2  344.17  6298.5  353.07
#Mann= 5 ,-1 , 0
  3604.9     .11       0  4744.6     .15       0 4976.83     .09       0
  5024.6     .15       0  5309.9     .11       0
Bank Sta=4976.83,5024.6
XS Rating Curve= 0 ,0
Exp/Cntr=0.3,0.1

Type RM Length L Ch R = 1 ,7876    ,449,449,449
BEGIN DESCRIPTION:
CCLC 092 16.0
END DESCRIPTION:
XS GIS Cut Line= 3
      3699117.83     10224161.08      3698212.25     10224406.48
      3697067.84     10225311.08
#Sta/Elev= 30
  4140.5  348.21    4163  347.94  4192.3  345.49  4223.4  344.38  4232.3   344.4
  4237.5  346.41  4244.1  346.27  4440.9  338.87  4637.8  333.77  4855.6  332.19
  4896.8  332.98  4917.5  331.86  4948.6  331.95  4963.3  329.73  4979.7  331.69
    4990  329.16  5000.1  323.73  5006.2  323.73  5010.8  328.14 5019.65 331.869
  5136.7  332.36  5241.5   331.7  5262.8  329.78  5299.3  332.68  5512.4  333.62
  5562.1  335.66  5655.1  334.61  5861.9  335.66  6195.2  340.52  6537.5  348.38
#Mann= 5 ,-1 , 0
  4140.5     .11       0  4855.6     .15       0  4979.7     .09       0
 5019.65     .15       0  5136.7     .11       0
Bank Sta=4979.7,5019.65
XS Rating Curve= 0 ,0
Exp/Cntr=0.3,0.1

Type RM Length L Ch R = 1 ,7427    ,499,499,499
BEGIN DESCRIPTION:
CCLC 092 15.0
END DESCRIPTION:
XS GIS Cut Line= 3
      3698967.87     10223161.06      3698163.07     10223970.58
      3696967.82      10225161.1
#Sta/Elev= 30
  3858.5  350.01  4028.2  344.49  4226.2  340.14  4289.9  335.94  4325.2  337.02
  4346.4  334.05  4367.6  333.32    4502  336.23  4715.2  332.71  4820.2  331.33
  4834.3  330.36  4841.4  328.35  4848.5  328.93  4862.6  327.62  4869.7  329.05
  4876.7  328.23  4883.8  329.88  4982.8  331.06  4989.9   328.3  4993.7  325.34
    5004  326.19  5018.2  331.25  5206.9  330.91  5242.7  330.27  5354.1  331.56
  5410.8  331.64  5668.7  332.65  5979.9   335.7  6340.5   341.4    6687  348.84
#Mann= 8 ,-1 , 0
  3858.5     .11       0  4715.2     .15       0  4982.8     .06       0
  5018.2     .11       0  5206.9     .15       0  5242.7     .11       0
  5354.1     .15       0  5410.8     .11       0
Bank Sta=4982.8,5018.2
XS Rating Curve= 0 ,0
Exp/Cntr=0.3,0.1

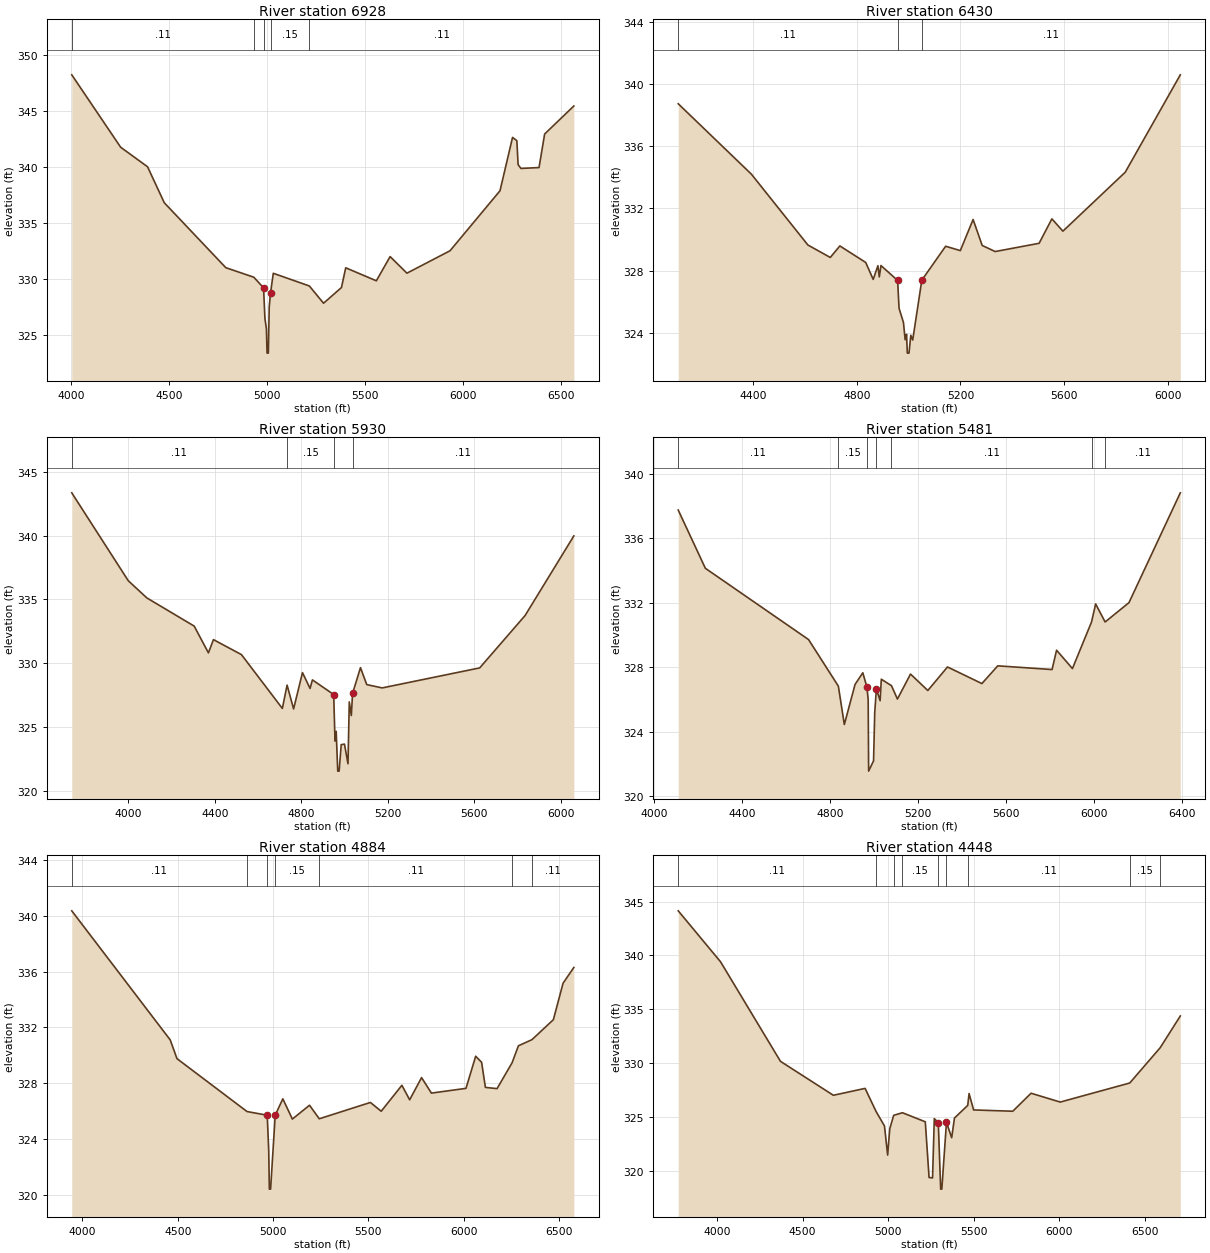
Type RM Length L Ch R = 1 ,6928    ,498,498,498
BEGIN DESCRIPTION:
CCLC 092 14.0
END DESCRIPTION:
XS GIS Cut Line= 3
      3698817.87     10222961.06      3698020.72     10223555.87
      3696817.85     10224561.08
#Sta/Elev= 30
  4005.4   348.2    4255  341.74  4392.2     340  4477.6  336.79  4791.5     331
  4934.4  330.15  4984.2   329.2  4991.1  326.47  4998.7  325.55  5002.1  323.38
  5008.5  323.38  5013.1   327.5  5019.6  328.74  5033.9   330.5  5217.8  329.37
  5290.3  327.83  5381.7  329.23  5403.5  330.99  5559.7  329.83    5630  331.99
  5715.8  330.51  5935.8  332.51  6190.8  337.86  6254.8  342.62  6276.7  342.33
  6283.2  340.19  6297.6  339.85    6390  339.93  6418.6  342.92  6567.6  345.42
#Mann= 5 ,-1 , 0
  4005.4     .11       0  4934.4     .15       0  4984.2     .09       0
  5019.6     .15       0  5217.8     .11       0
Bank Sta=4984.2,5019.6
XS Rating Curve= 0 ,0
Exp/Cntr=0.3,0.1

Type RM Length L Ch R = 1 ,6430    ,500,500,500
BEGIN DESCRIPTION:
CCLC 092 13.0
END DESCRIPTION:
XS GIS Cut Line= 3
      3698467.86     10223111.07      3697649.52     10223460.96
      3696867.82      10224161.1
#Sta/Elev= 30
    4110  338.73  4392.8   334.2  4610.9  329.65  4697.3  328.85  4734.3  329.59
  4834.1  328.53  4863.1  327.44  4881.3  328.32  4886.7   327.6  4893.1  328.33
  4957.5  327.37  4962.9  325.59  4980.1  324.66  4986.5  323.56    4992  323.91
  4994.9   322.7  5001.4   322.7  5008.3  323.85  5015.7  323.54  5050.9  327.39
  5142.9  329.57  5199.7  329.29    5249  331.29  5284.2  329.62  5334.3  329.23
    5504  329.76  5553.3  331.33  5595.9  330.54  5836.7  334.33  6049.4  340.59
#Mann= 3 , 0 , 0
    4110     .11       0  4957.5     .06       0  5050.9     .11       0
Bank Sta=4957.5,5050.9
XS Rating Curve= 0 ,0
Exp/Cntr=0.3,0.1

Type RM Length L Ch R = 1 ,5930    ,449,449,449
BEGIN DESCRIPTION:
CCLC 092 12.0
END DESCRIPTION:
XS GIS Cut Line= 3
      3698525.58     10222631.64      3697372.06     10223143.77
      3696812.17     10224045.01
#Sta/Elev= 30
  3737.9  343.37  3999.4  336.47  4085.5  335.12  4304.4  332.91  4370.2  330.81
  4393.5  331.85  4523.2  330.67  4712.3  326.45  4734.2  328.28  4764.3  326.41
  4805.4  329.26  4840.5  328.02  4851.4  328.69  4949.9  327.54  4955.9  323.89
  4961.4  324.65  4968.5  321.53    4975  321.53  4984.6  323.61  4999.6  323.65
    5016  322.11  5021.9  326.96  5031.3  325.89  5037.2  327.63  5073.8  329.65
  5102.8  328.32  5174.2  328.06  5625.3  329.63  5835.4  333.74    6061  339.99
#Mann= 4 ,-1 , 0
  3737.9     .11       0  4734.2     .15       0  4949.9     .09       0
  5037.2     .11       0
Bank Sta=4949.9,5037.2
XS Rating Curve= 0 ,0
Exp/Cntr=0.3,0.1

Type RM Length L Ch R = 1 ,5481    ,597,597,597
BEGIN DESCRIPTION:
CCLC 092 11.0
END DESCRIPTION:
XS GIS Cut Line= 3
      3698217.84     10222511.08      3697032.56      10222974.5
      3696789.97     10223957.87
#Sta/Elev= 30
  4108.7  337.75  4232.2  334.14  4701.9  329.72  4837.6  326.83  4864.8  324.45
  4913.7  326.94  4948.9  327.66  4967.7  326.77  4973.4  325.99  4975.4  321.56
  4997.8   322.2  5003.2  325.19  5010.6  326.66  5027.7  325.93  5033.1  327.26
  5079.4  326.86  5106.5  326.03  5166.1  327.58  5244.9  326.56  5334.4  328.02
  5491.1  326.99  5563.2  328.09  5810.4  327.86    5831  329.06  5903.1  327.92
  5990.1  330.81  6008.8  331.93    6052  330.81  6160.6  332.01  6394.2  338.82
#Mann= 7 ,-1 , 0
  4108.7     .11       0  4837.6     .15       0  4967.7     .09       0
  5010.6     .15       0  5079.4     .11       0  5990.1     .15       0
    6052     .11       0
Bank Sta=4967.7,5010.6
XS Rating Curve= 0 ,0
Exp/Cntr=0.3,0.1

Type RM Length L Ch R = 1 ,4884    ,436,436,436
BEGIN DESCRIPTION:
CCLC 092 10.0
END DESCRIPTION:
XS GIS Cut Line= 4
      3698217.84     10222011.08      3697314.68     10222566.52
      3697037.02     10222574.78      3696789.59     10223846.46
#Sta/Elev= 30
    3944  340.35  4460.5   331.1  4495.8  329.76  4863.2  325.97 4969.33325.7031
  4977.1  323.18  4980.4  320.41    4987  320.41  5011.1   325.7  5051.1  326.88
  5101.2  325.43  5191.2  326.42  5242.2  325.45  5510.4  326.62  5567.2  325.99
  5675.6  327.85  5716.4  326.81  5778.9   328.4  5830.5  327.29  6011.8  327.63
  6062.7  329.93  6093.8   329.5  6113.7   327.7  6174.8  327.61  6253.9  329.47
  6286.9  330.68    6358  331.12  6470.2  332.55  6521.2  335.17  6577.6  336.29
#Mann= 7 ,-1 , 0
    3944     .11       0  4863.2     .15       0 4969.33     .09       0
  5011.1     .15       0  5242.2     .11       0  6253.9     .15       0
    6358     .11       0
Bank Sta=4969.33,5011.1
XS Rating Curve= 0 ,0
Exp/Cntr=0.3,0.1

Type RM Length L Ch R = 1 ,4448    ,524,524,524
BEGIN DESCRIPTION:
CCLC 092 9.0
END DESCRIPTION:
XS GIS Cut Line= 4
      3698367.89     10221911.06      3697176.98      10222205.6
      3697012.05     10222242.03      3696737.43     10223755.72
#Sta/Elev= 30
  3773.2  344.14  4020.5  339.41  4370.7  330.17  4679.8  327.02  4865.2  327.66
  4929.9   325.5  4978.5  324.17    4997  321.47  5009.3  323.91  5032.3  325.16
  5083.5   325.4    5217  324.56  5239.1  319.39  5259.4  319.35  5269.6  324.85
 5292.96 324.493  5306.9  318.31  5313.6  318.31  5340.7  324.51  5371.2  323.08
  5387.5  324.91    5465  326.08  5472.8  327.18  5499.4  325.66  5728.3  325.54
  5835.1  327.21  6005.5  326.39  6411.8  328.16    6590  331.44  6707.3  334.38
#Mann= 9 ,-1 , 0
  3773.2     .11       0  4929.9     .15       0  5032.3     .11       0
  5083.5     .15       0 5292.96     .09       0  5340.7     .15       0
    5465     .11       0  6411.8     .15       0    6590     .11       0
Bank Sta=5292.96,5340.7
XS Rating Curve= 0 ,0
Exp/Cntr=0.3,0.1

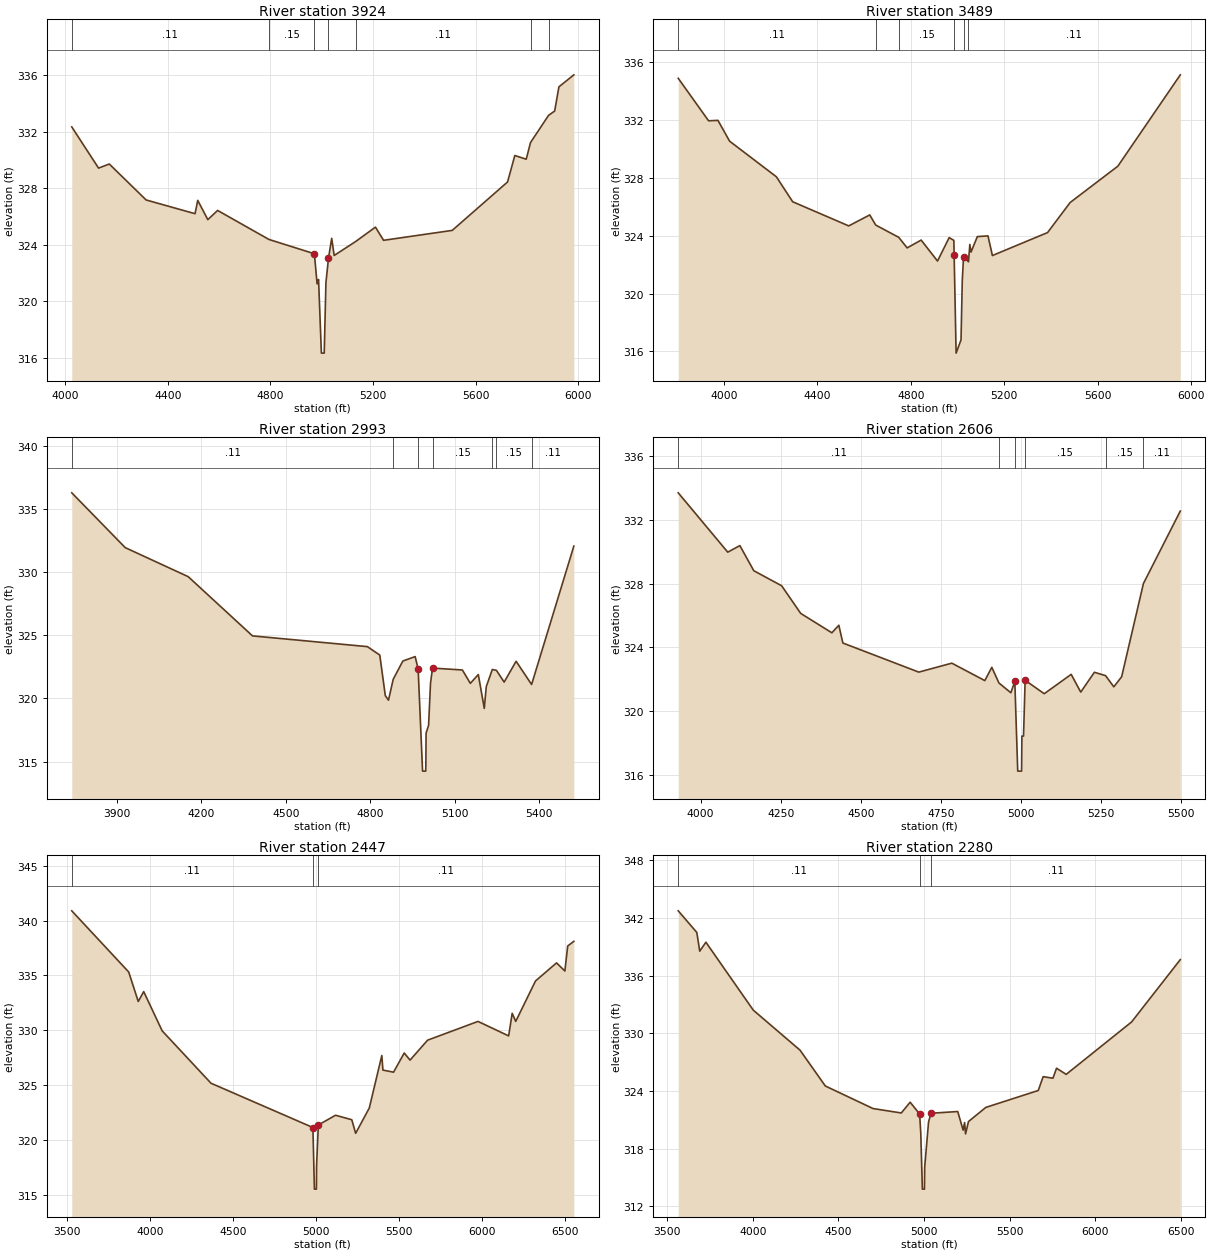
Type RM Length L Ch R = 1 ,3924    ,435,435,435
BEGIN DESCRIPTION:
CCLC 092 8.0
END DESCRIPTION:
XS GIS Cut Line= 3
      3697767.81     10221611.08      3696937.07     10221863.39
      3695967.89     10222361.05
#Sta/Elev= 30
  4025.7  332.33  4130.2  329.42    4172  329.71  4315.6  327.17  4506.4   326.2
  4516.9  327.14  4556.2  325.78  4594.3  326.43  4794.6  324.38  4971.7  323.37
  4982.3  321.24    4988  321.55    4999  316.35  5010.1  316.35  5016.7  321.32
  5026.7  323.05  5039.2  324.46  5048.9  323.25  5132.3  324.23  5209.8  325.25
  5241.5  324.32  5509.2  325.02  5724.9  328.44  5753.3  330.31  5797.7  330.05
  5814.6  331.23    5885  333.15  5908.6  333.45  5925.2  335.16  5983.4  336.01
#Mann= 7 ,-1 , 0
  4025.7     .11       0  4794.6     .15       0  4971.7     .09       0
  5026.7     .15       0  5132.3     .11       0  5814.6     .15       0
    5885     .11       0
Bank Sta=4971.7,5026.7
XS Rating Curve= 0 ,0
Exp/Cntr=0.3,0.1

Type RM Length L Ch R = 1 ,3489    ,496,496,496
BEGIN DESCRIPTION:
CCLC 092 7.0
END DESCRIPTION:
XS GIS Cut Line= 3
      3697917.85     10221561.07      3696722.24     10221539.81
      3695812.92     10221828.68
#Sta/Elev= 30
  3804.2  334.89  3934.2  331.95  3974.2  331.98  4024.2  330.54  4224.3  328.08
  4294.3  326.35  4534.3  324.68  4624.3  325.44  4649.7  324.74  4748.3  323.89
  4784.4  323.16  4844.4   323.7  4914.4  322.25  4964.4  323.87  4984.4  323.68
  4985.7322.6483  4994.1  315.88  5015.1   316.8  5020.5  320.91  5025.8  322.54
  5047.1   322.2  5052.8   323.4    5058  322.87    5085  323.94  5130.5  323.99
  5149.5  322.63  5385.8  324.22  5482.5   326.3  5686.6  328.81  5954.1  335.13
#Mann= 6 ,-1 , 0
  3804.2     .11       0  4649.7     .17       0  4748.3     .15       0
  4985.7     .09       0  5025.8     .15       0  5047.1     .11       0
Bank Sta=4985.7,5025.8
XS Rating Curve= 0 ,0
Exp/Cntr=0.3,0.1

Type RM Length L Ch R = 1 ,2993    ,387,387,387
BEGIN DESCRIPTION:
CCLC 092 6.0
END DESCRIPTION:
XS GIS Cut Line= 3
      3697967.85     10221511.07       3696779.8      10221089.3
      3696417.86     10220711.08
#Sta/Elev= 30
  3739.3  336.28  3929.3  331.94  4153.1  329.64  4381.6  324.95  4789.8   324.1
  4833.9  323.43  4853.5  320.22  4864.8  319.86  4881.7  321.52  4915.9  322.96
  4959.6  323.31  4970.2  322.33  4985.9  314.24  4997.1  314.24  4997.6  314.74
  4998.4  317.25  5007.3  317.86  5014.2  321.22  5021.4   322.4  5127.4  322.25
  5155.7  321.19    5184  321.89  5205.2  319.21  5212.3  320.93  5233.8  322.29
  5248.5  322.22  5275.8  321.29  5318.3  322.94  5373.4   321.1  5523.5  332.06
#Mann= 7 ,-1 , 0
  3739.3     .11       0  4881.7     .15       0  4970.2     .09       0
  5021.4     .15       0  5233.8     .11       0  5248.5     .15       0
  5373.4     .11       0
Bank Sta=4970.2,5021.4
XS Rating Curve= 0 ,0
Exp/Cntr=0.3,0.1

Type RM Length L Ch R = 1 ,2606    ,159,159,159
BEGIN DESCRIPTION:
CCLC 092 5.0
END DESCRIPTION:
XS GIS Cut Line= 3
      3697867.88     10221261.09      3696924.05     10220739.26
      3696467.89     10220561.09
#Sta/Elev= 30
  3929.9  333.67  4084.6  329.96  4122.4  330.37  4165.9   328.8  4252.9  327.86
  4312.5  326.13  4409.8  324.92  4431.6  325.39  4444.1  324.28  4681.3  322.46
  4784.4  323.02  4887.5  321.93  4909.3  322.76  4931.6  321.78  4968.8  321.17
  4981.2  321.88  4990.3  316.27  5002.3  316.27  5003.3  318.46  5008.4  318.46
  5013.4  321.95  5073.1  321.11  5157.3  322.32  5187.1  321.21  5229.7  322.45
  5264.7  322.24  5290.4  321.54  5314.9  322.17  5382.9     328  5498.1  332.53
#Mann= 6 ,-1 , 0
  3929.9     .11       0  4931.6     .15       0  4981.2     .06       0
  5013.4     .15       0  5264.7     .15       0  5382.9     .11       0
Bank Sta=4981.2,5013.4
XS Rating Curve= 0 ,0
Exp/Cntr=0.3,0.1

Type RM Length L Ch R = 1 ,2447    ,167,167,167
BEGIN DESCRIPTION:
Mapping XS 40a6e0ba
END DESCRIPTION:
XS GIS Cut Line= 6
      3698343.32     10221208.01      3696654.96     10220448.46
      3696477.01     10220296.55      3696242.63     10220018.77
      3696073.36     10219745.34      3696021.52      10219494.8
#Sta/Elev= 30
  3528.1  340.89  3871.3  335.31  3928.8  332.62  3961.7  333.52    4073  329.94
  4367.5  325.16  4981.5  321.12  4990.6   315.5  5002.6   315.5  5003.5   317.6
  5014.3  321.35  5117.9  322.24    5216  321.83  5239.1  320.59  5321.4   322.9
  5396.9  327.69  5403.5  326.36  5467.7  326.17    5532  327.92  5567.1  327.27
  5672.9  329.09  5976.7   330.8  6161.4  329.48  6182.7  331.54    6204   330.8
  6323.2  334.49    6450  336.14  6500.2   335.4  6517.3  337.68  6554.3  338.11
#Mann= 3 ,-1 , 0
  3528.1     .11       0  4981.5     .07       0  5014.3     .11       0
Bank Sta=4981.5,5014.3
XS Rating Curve= 0 ,0
Exp/Cntr=0.3,0.1

Type RM Length L Ch R = 1 ,2280    ,284,284,284
BEGIN DESCRIPTION:
Mapping XS e4af26f9
END DESCRIPTION:
XS GIS Cut Line= 6
      3698404.09     10221090.83      3696819.89      10220344.3
      3696598.53     10220175.02      3696385.86     10219914.61
      3696216.59     10219649.85      3696151.95     10219404.23
#Sta/Elev= 30
  3563.8  342.75  3672.3   340.5  3689.5  338.55  3725.5  339.48  4002.3  332.41
  4275.7  328.24  4423.5  324.51  4702.4  322.16  4867.4   321.7  4919.4  322.82
  4974.6  321.59  4981.3  319.62  4990.7  313.77  5002.8  313.77  5004.1  316.03
  5026.9  320.77    5041  321.67  5197.4  321.85  5228.9  319.91  5237.5   320.7
    5243  319.52  5260.3  320.81  5361.6  322.28  5667.9  324.04  5696.6  325.48
  5753.8  325.32  5774.9  326.36  5831.3  325.72  6213.6  331.18  6498.2  337.67
#Mann= 3 ,-1 , 0
  3563.8     .11       0  4974.6     .07       0    5041     .11       0
Bank Sta=4974.6,5041
XS Rating Curve= 0 ,0
Exp/Cntr=0.3,0.1