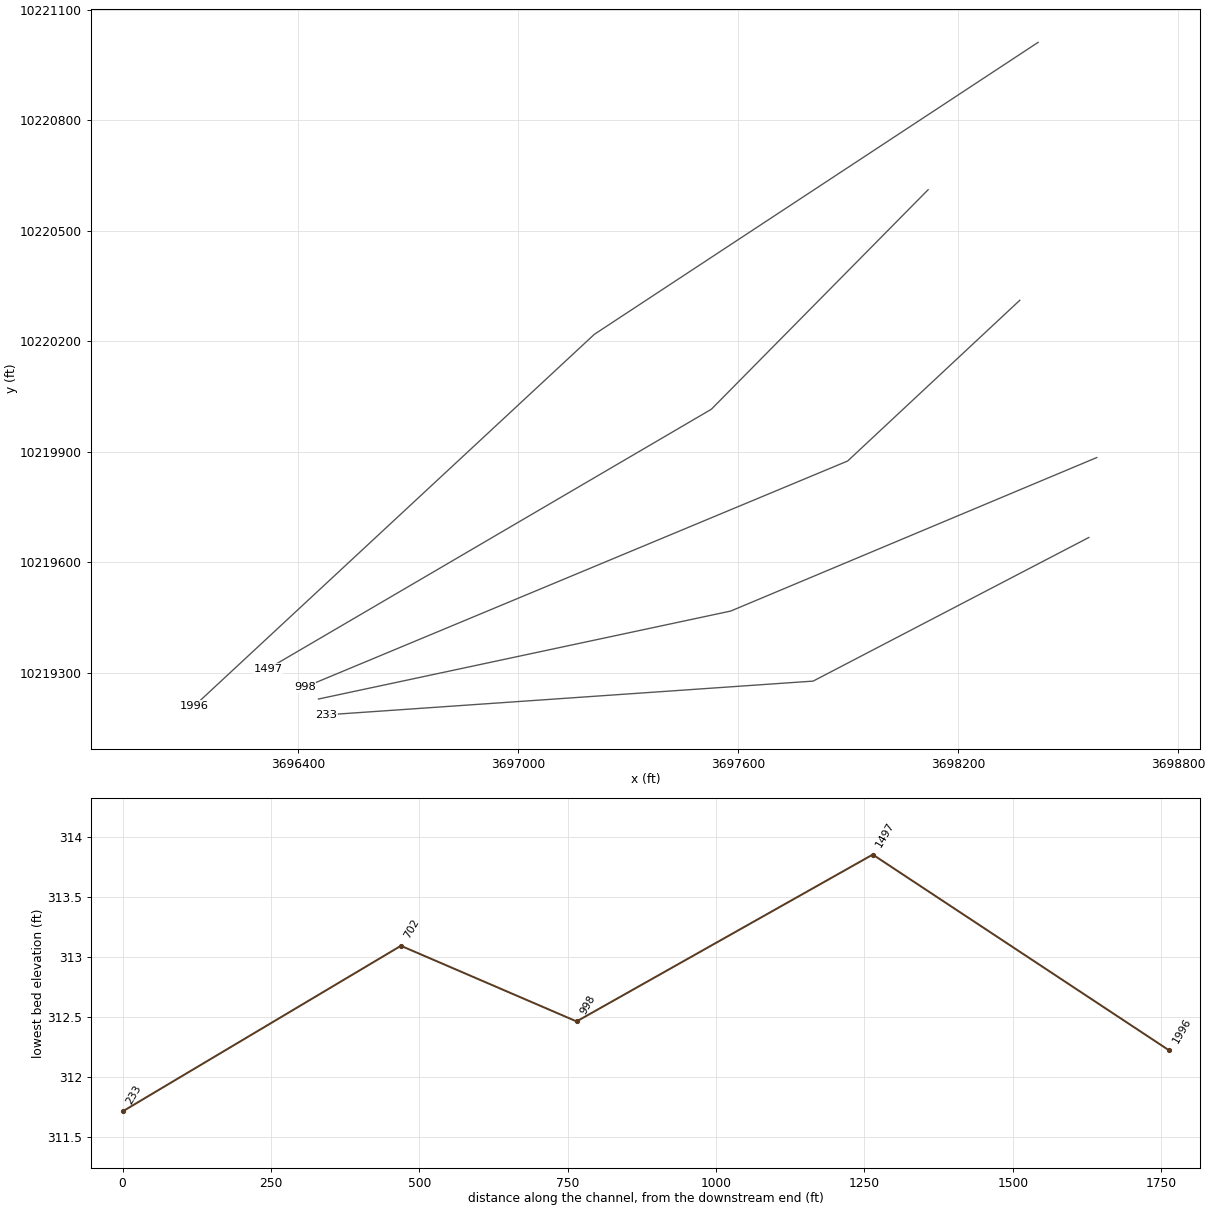
HEC-RAS study CCLC 092.prj: CCLC 092 Base Level Engineering

--- CCLC 092.g01 (geometry) --- (continued)

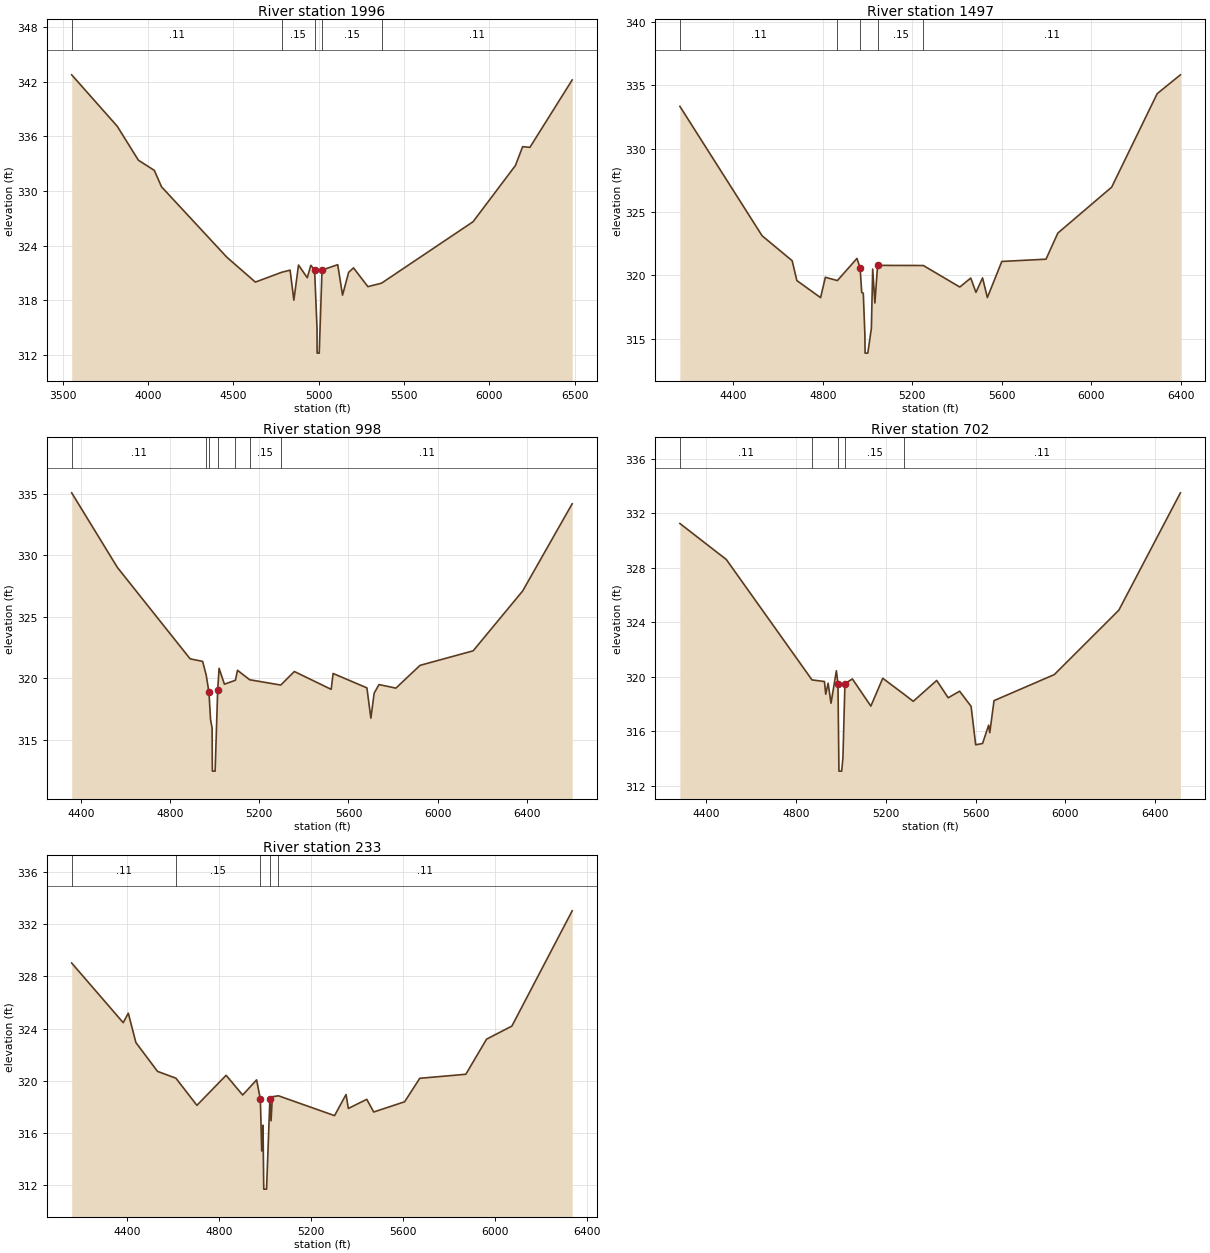
Type RM Length L Ch R = 1 ,1996    ,499,499,499
BEGIN DESCRIPTION:
CCLC 092 4.0
END DESCRIPTION:
XS GIS Cut Line= 3
      3698417.85     10221011.07      3697207.67      10220218.7
      3696117.82     10219211.04
#Sta/Elev= 30
  3553.5  342.74  3820.3   337.1    3944  333.38  4037.4  332.26  4079.6  330.46
  4462.5  322.73  4629.3  320.01  4782.1  321.08  4832.4  321.32  4854.6  318.03
  4881.6  321.88  4932.9  320.49    4954  321.85  4975.9  321.33  4990.2  314.92
  4990.4  312.72  4990.9  312.22    5003  312.22  5019.4  321.33  5111.3  321.92
  5139.6  318.58  5175.3  321.08  5203.7  321.57  5288.2  319.51  5367.7  319.89
  5903.9  326.63  6151.7  332.79  6194.2  334.86  6236.8  334.79  6484.3  342.18
#Mann= 5 ,-1 , 0
  3553.5     .11       0  4782.1     .15       0  4975.9     .09       0
  5019.4     .15       0  5367.7     .11       0
Bank Sta=4975.9,5019.4
XS Rating Curve= 0 ,0
Exp/Cntr=0.3,0.1

Type RM Length L Ch R = 1 ,1497    ,499,499,499
BEGIN DESCRIPTION:
CCLC 092 3.0
END DESCRIPTION:
XS GIS Cut Line= 3
      3698117.82     10220611.04      3697526.65     10220015.26
      3696317.82     10219311.05
#Sta/Elev= 30
  4160.7  333.34  4528.3  323.12  4662.7  321.15  4683.9  319.58    4790  318.23
  4811.2  319.84    4865  319.58  4952.6  321.33  4966.7  320.58  4973.8  318.64
  4980.9  318.58    4988  315.32    4989  313.85  5001.1  313.85  5017.1  315.82
  5022.9  320.49  5032.8  317.81  5044.9  320.78  5249.5  320.77  5412.5  319.07
  5461.5  319.78  5484.7  318.65  5514.3  319.79  5535.8  318.24  5600.4  321.09
    5798  321.27  5850.9  323.33  6091.7  326.96  6295.1  334.34    6399  335.83
#Mann= 5 ,-1 , 0
  4160.7     .11       0    4865     .15       0  4966.7     .09       0
  5044.9     .15       0  5249.5     .11       0
Bank Sta=4966.7,5044.9
XS Rating Curve= 0 ,0
Exp/Cntr=0.3,0.1

Type RM Length L Ch R = 1 ,998     ,296,296,296
BEGIN DESCRIPTION:
CCLC 092 2.0
END DESCRIPTION:
XS GIS Cut Line= 3
      3698367.84     10220311.06      3697898.45     10219874.84
      3696417.82     10219261.06
#Sta/Elev= 30
  4359.2  335.06  4564.1     329  4890.1  321.58  4946.2  321.37  4962.2  320.26
  4974.6  318.86  4981.9  316.61  4988.7  315.96  4989.5  312.96    4990  312.46
  5002.2  312.46  5013.6  319.01  5019.9  320.81  5043.8  319.52  5093.2  319.84
  5102.4  320.65  5157.1  319.88  5296.4  319.45  5357.4  320.55  5522.4   319.1
  5531.1  320.39  5682.6  319.22  5700.4  316.76  5715.1  318.79  5736.8  319.49
  5812.5   319.2  5920.8  321.05  6158.9  322.23  6380.8  327.09  6602.8  334.17
#Mann= 7 ,-1 , 0
  4359.2     .11       0  4962.2     .15       0  4974.6     .09       0
  5013.6     .15       0  5093.2     .11       0  5157.1     .15       0
  5296.4     .11       0
Bank Sta=4974.6,5013.6
XS Rating Curve= 0 ,0
Exp/Cntr=0.3,0.1

Type RM Length L Ch R = 1 ,702     ,469,469,469
BEGIN DESCRIPTION:
Mapping XS 1498b97c
END DESCRIPTION:
XS GIS Cut Line= 3
      3698577.69     10219884.22      3697579.44     10219467.56
      3696455.32     10219228.85
#Sta/Elev= 30
  4282.1  331.25  4489.1  328.61    4871  319.78  4926.5  319.66  4932.1  318.73
  4942.9  319.54  4955.7  318.07  4979.6  320.45 4986.74 319.489    4991  313.09
  5003.2  313.09  5008.8  314.06 5017.73319.5074    5051  319.85  5133.3  317.86
  5186.3   319.9  5281.2  318.73  5322.2  318.21  5426.8  319.74  5477.9  318.47
    5529  318.95  5580.1  317.84  5600.6  315.02  5631.2  315.12  5658.3  316.46
  5663.4  315.91  5682.3  318.26    5951  320.17  6238.5  324.89    6513   333.5
#Mann= 5 ,-1 , 0
  4282.1     .11       0    4871     .15       0 4986.74     .09       0
 5017.73     .15       0  5281.2     .11       0
Bank Sta=4986.74,5017.73
XS Rating Curve= 0 ,0
Exp/Cntr=0.3,0.1

Type RM Length L Ch R = 1 ,233     ,0,0,0
BEGIN DESCRIPTION:
CCLC 092 1.0
END DESCRIPTION:
XS GIS Cut Line= 3
      3698556.01     10219667.22      3697804.26     10219277.46
      3696476.11      10219185.8
#Sta/Elev= 30
  4157.8  329.03  4382.1  324.46  4404.2  325.19  4437.2  322.94  4531.4  320.73
  4611.3  320.21  4702.7  318.13  4829.9  320.43  4901.9  318.92  4962.6  320.08
 4978.84318.6005  4984.8  314.63  4990.4  316.61  4993.6  311.71  5005.8  311.71
  5020.4  318.63  5025.4  316.94  5031.1  318.79  5057.7  318.86  5301.7  317.34
  5351.8  318.96  5361.8  317.89    5442  318.59  5472.1  317.62  5606.6   318.4
  5672.6   320.2  5873.1  320.51  5963.3   323.2  6073.5   324.2  6335.9  333.03
#Mann= 5 ,-1 , 0
  4157.8     .11       0  4611.3     .15       0 4978.84     .09       0
  5020.4     .15       0  5057.7     .11       0
Bank Sta=4978.84,5020.4
XS Rating Curve= 0 ,0
Exp/Cntr=0.3,0.1

Chan Stop Cuts=-1
Use User Specified Reach Order=0
Composite Channel Slope=5