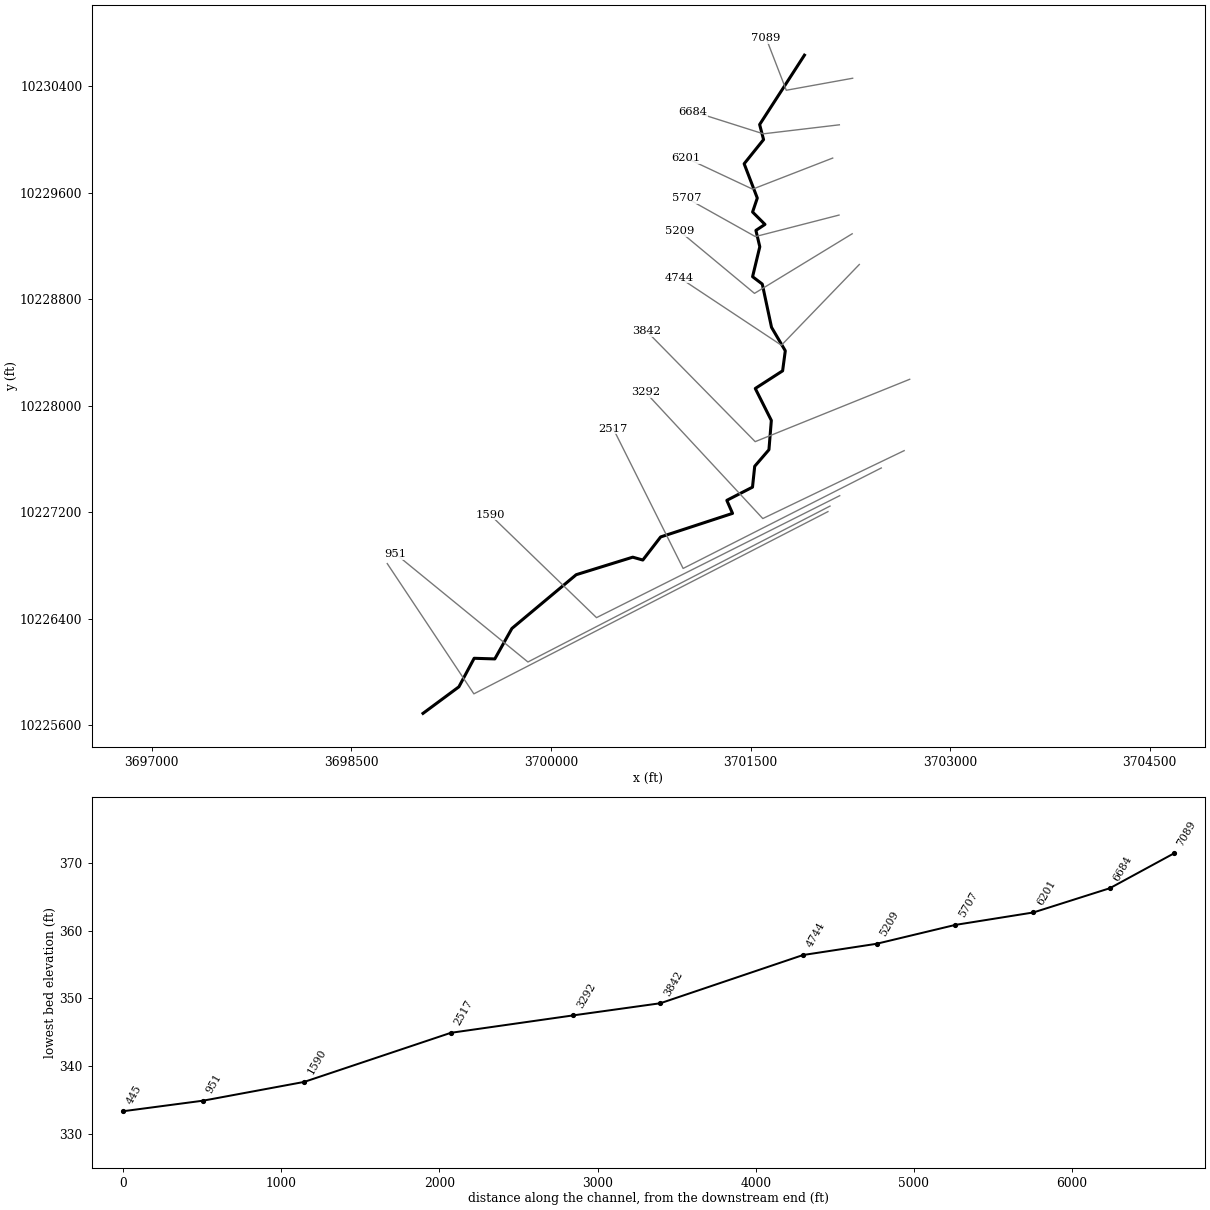
--- CCLC 093.prj (project) ---

Proj Title=CCLC 093 Base Level Engineering
Current Plan=p01
Default Exp/Contr=0.3,0.1
English Units
Geom File=g01
Flow File=f01
Flow File=f02
Plan File=p01
Y Axis Title=Elevation
X Axis Title(PF)=Main Channel Distance
X Axis Title(XS)=Station
BEGIN DESCRIPTION:
CCLC 093
END DESCRIPTION:
DSS Export Rating Curves= 0
DSS Export Rating Curve Sorted= 0
DSS Export Volume Flow Curves= 0
DXF OffsetX= 0
DXF OffsetY= 0
DXF ScaleX= 1
DXF ScaleY= 10

--- CCLC 093.p01 (plan) ---

Plan Title=Multiple Run
Short Identifier=Multiple
Geom File=g01
Flow File=f01
Subcritical Flow
K Sum by GR= 0
Std Step Tol= 0.01
Critical Tol= 0.01
Num of Std Step Trials= 20
Max Error Tol= 0.3
Flow Tol Ratio= 0.001
Split Flow NTrial= 30
Split Flow Tol= 0.02
Split Flow Ratio= 0.02
Log Output Level= 0
Friction Slope Method= 1
Unsteady Friction Slope Method= 2
Unsteady Bridges Friction Slope Method= 1
Parabolic Critical Depth
Global Vel Dist=  1 , 1 , 1
Global Log Level= 0
CheckData=True
Encroach Param= -1, 0, 0, 0
BEGIN DESCRIPTION:
Multiple Run
END DESCRIPTION:

--- CCLC 093.f01 (steady flow) ---

Flow Title=Multiple
Program Version=4.10
Number of Profiles= 7
Profile Names=10-year,25-year,50-year,1pct_min,100-year,1pct_plu,500-year
River Rch & RM=CCLC 093,Reach-1         ,7089
     552     744    1001     444    1340    4047    2485
Boundary for River Rch & Prof#=CCLC 093,Reach-1         , 1
Up Type= 0
Dn Type= 3
Dn Slope=0.005
Boundary for River Rch & Prof#=CCLC 093,Reach-1         , 2
Up Type= 0
Dn Type= 3
Dn Slope=0.005
Boundary for River Rch & Prof#=CCLC 093,Reach-1         , 3
Up Type= 0
Dn Type= 3
Dn Slope=0.005
Boundary for River Rch & Prof#=CCLC 093,Reach-1         , 4
Up Type= 0
Dn Type= 3
Dn Slope=0.005
Boundary for River Rch & Prof#=CCLC 093,Reach-1         , 5
Up Type= 0
Dn Type= 3
Dn Slope=0.005
Boundary for River Rch & Prof#=CCLC 093,Reach-1         , 6
Up Type= 0
Dn Type= 3
Dn Slope=0.005
Boundary for River Rch & Prof#=CCLC 093,Reach-1         , 7
Up Type= 0
Dn Type= 3
Dn Slope=0.005
DSS Import GetInterval= 0
DSS Import GetPeak= 0
DSS Import FillOption= 0

--- CCLC 093.f02 (steady flow) ---

Flow Title=Orig_BLE_Flows
Program Version=4.10
Number of Profiles= 7
Profile Names=10-year,25-year,50-year,1pct_min,100-year,1pct_plu,500-year
River Rch & RM=CCLC 093,Reach-1         ,7089
     552     729     870     341    1031    3114    1445
Boundary for River Rch & Prof#=CCLC 093,Reach-1         , 1
Up Type= 0
Dn Type= 3
Dn Slope=0.005
Boundary for River Rch & Prof#=CCLC 093,Reach-1         , 2
Up Type= 0
Dn Type= 3
Dn Slope=0.005
Boundary for River Rch & Prof#=CCLC 093,Reach-1         , 3
Up Type= 0
Dn Type= 3
Dn Slope=0.005
Boundary for River Rch & Prof#=CCLC 093,Reach-1         , 4
Up Type= 0
Dn Type= 3
Dn Slope=0.005
Boundary for River Rch & Prof#=CCLC 093,Reach-1         , 5
Up Type= 0
Dn Type= 3
Dn Slope=0.005
Boundary for River Rch & Prof#=CCLC 093,Reach-1         , 6
Up Type= 0
Dn Type= 3
Dn Slope=0.005
Boundary for River Rch & Prof#=CCLC 093,Reach-1         , 7
Up Type= 0
Dn Type= 3
Dn Slope=0.005
DSS Import GetInterval= 0
DSS Import GetPeak= 0
DSS Import FillOption= 0

--- CCLC 093.g01 (geometry) ---

Geom Title=Existing Conditions
Program Version=4.10

River Reach=CCLC 093        ,Reach-1
Reach XY= 30
      3701905.44     10230634.58      3701568.67     10230113.12
      3701598.16     10229999.83      3701452.27     10229818.25
      3701551.08     10229560.32      3701515.66     10229455.46
      3701608.72      10229362.4      3701540.66     10229317.26
      3701569.83     10229194.34      3701515.66     10228969.34
      3701588.58     10228913.79      3701658.02     10228588.79
       3701761.5      10228412.4      3701741.36     10228261.71
       3701535.8     10228129.07      3701656.63     10227888.79
      3701638.58     10227668.65      3701531.63     10227544.34
      3701514.97      10227387.4      3701321.91     10227288.09
      3701364.93     10227190.21      3700824.56     10227013.07
      3700690.53     10226839.46      3700614.84     10226860.99
      3700189.85     10226729.26      3699706.57     10226325.31
      3699577.92     10226096.14      3699422.78     10226101.02
      3699307.94     10225886.36      3699038.23     10225686.84

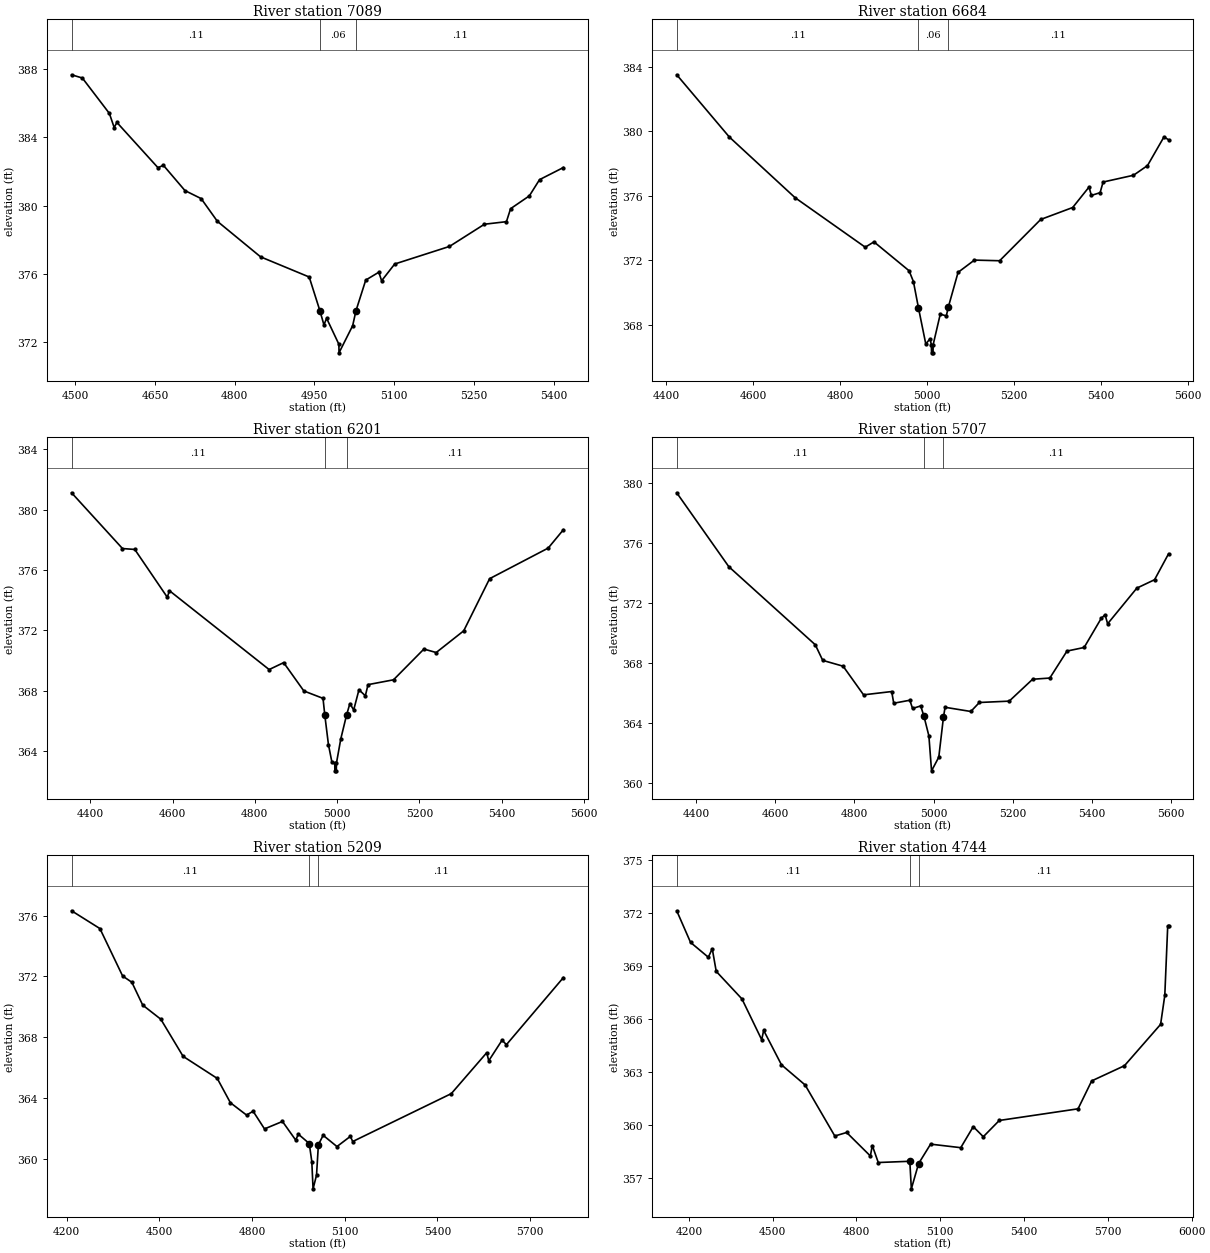
Type RM Length L Ch R = 1 ,7089    ,405,405,405
BEGIN DESCRIPTION:
CCLC 093 8.0
END DESCRIPTION:
XS GIS Cut Line= 3
      3702267.86     10230461.07      3701768.87     10230370.74
      3701617.86     10230761.05
#Sta/Elev= 30
  4492.9  387.67  4513.2  387.48    4564  385.41  4573.1  384.58  4578.2  384.88
  4655.5  382.23  4665.7  382.37  4706.3  380.89  4736.8  380.42  4767.3  379.09
  4848.6  377.01  4940.1  375.83  4960.4  373.84  4967.8  373.03  4972.9  373.41
    4996  371.89  4996.2  371.39  5021.9  372.98  5028.1373.8515  5046.5  375.65
  5071.1  376.11  5076.4  375.61    5101  376.59  5204.1  377.62  5269.9  378.92
  5311.3  379.07  5319.1  379.83  5354.4  380.58  5373.6  381.53  5418.5  382.24
#Mann= 3 , 0 , 0
  4492.9     .11       0  4960.4     .06       0  5028.1     .11       0
Bank Sta=4960.4,5028.1
XS Rating Curve= 0 ,0
Exp/Cntr=0.3,0.1

Type RM Length L Ch R = 1 ,6684    ,483,483,483
BEGIN DESCRIPTION:
CCLC 093 7.0
END DESCRIPTION:
XS GIS Cut Line= 3
       3702167.9     10230111.08       3701596.6     10230043.28
      3701067.89     10230211.06
#Sta/Elev= 30
  4424.7  383.49  4545.6  379.63  4696.6  375.87  4857.8   372.8  4877.9  373.13
  4958.5  371.34  4968.5  370.67    4980  369.05  4996.9   366.8  5006.6  367.12
  5009.8  366.75  5010.1  366.25  5013.6  366.25  5013.8  366.75  5030.2  368.65
  5044.1  368.54  5048.5 369.068  5071.1  371.24  5108.6     372  5166.6  371.96
    5261  374.52  5334.4  375.26    5372  376.53  5377.3  376.01  5397.4  376.18
  5404.3  376.84  5474.1  377.26  5506.3  377.86  5544.2  379.64  5554.7  379.46
#Mann= 3 , 0 , 0
  4424.7     .11       0    4980     .06       0  5048.5     .11       0
Bank Sta=4980,5048.5
XS Rating Curve= 0 ,0
Exp/Cntr=0.3,0.1

Type RM Length L Ch R = 1 ,6201    ,494,494,494
BEGIN DESCRIPTION:
CCLC 093 6.0
END DESCRIPTION:
XS GIS Cut Line= 3
      3702117.82     10229861.06       3701515.9     10229627.36
      3701017.82     10229861.09
#Sta/Elev= 30
  4354.3  381.12  4478.1  377.42    4508  377.36    4587  374.19  4592.4  374.62
  4834.7  369.39    4870  369.85  4919.1  367.97  4965.7  367.48  4970.1366.3518
  4978.9  364.41  4987.2  363.26  4994.3  363.17  4994.5  362.67    4998  362.67
  4998.3  363.17  5008.9  364.79    5023  366.38    5031  367.13  5040.3  366.71
  5053.1  368.05  5068.6  367.65  5075.2  368.39  5137.1  368.71    5211  370.75
  5240.9  370.52  5307.8  371.96  5370.8  375.42  5513.2  377.45  5550.2  378.67
#Mann= 3 , 0 , 0
  4354.3     .11       0  4970.1     .06       0    5023     .11       0
Bank Sta=4970.1,5023
XS Rating Curve= 0 ,0
Exp/Cntr=0.3,0.1

Type RM Length L Ch R = 1 ,5707    ,498,498,498
BEGIN DESCRIPTION:
CCLC 093 5.0
END DESCRIPTION:
XS GIS Cut Line= 3
      3702165.42     10229432.54       3701536.5     10229270.73
      3701017.83     10229561.08
#Sta/Elev= 30
  4350.6  379.38  4482.3  374.45    4701  369.24  4719.8   368.2  4771.4  367.81
  4823.1   365.9  4894.2  366.12  4899.4  365.34  4940.1  365.54    4947  364.99
  4967.6  365.16  4975.7  364.48  4988.3  363.16    4995  360.83  5013.3  361.74
  5025.1364.4024  5029.2  365.07  5094.3  364.79    5116  365.39  5191.4  365.48
  5250.6  366.94  5294.1  367.02  5337.5  368.82  5380.9  369.06  5424.3  371.01
  5433.9  371.24  5440.3  370.64  5514.2  373.02    5559  373.58  5594.4  375.31
#Mann= 3 , 0 , 0
  4350.6     .11       0  4975.7     .06       0  5025.1     .11       0
Bank Sta=4975.7,5025.1
XS Rating Curve= 0 ,0
Exp/Cntr=0.3,0.1

Type RM Length L Ch R = 1 ,5209    ,465,465,465
BEGIN DESCRIPTION:
CCLC 093 4.0
END DESCRIPTION:
XS GIS Cut Line= 3
      3702264.31     10229291.89      3701529.96     10228843.98
      3700967.86     10229311.06
#Sta/Elev= 30
  4216.4  376.32  4308.1  375.15  4381.6  372.03  4411.4  371.62  4446.5  370.12
  4505.1  369.19  4577.2  366.75  4687.6   365.3  4730.2   363.7  4782.4  362.89
  4803.7  363.14  4840.5  361.98  4898.6  362.47  4941.2  361.25  4950.2  361.63
  4985.3  361.02  4993.5  359.83  4997.6  358.04  5008.8  358.94  5014.8  360.94
  5030.2  361.56  5074.9  360.82  5118.3  361.49  5125.8  361.15  5444.8   364.3
  5559.4  366.99  5565.9  366.46  5608.9  367.81  5623.2  367.52  5807.4  371.93
#Mann= 3 , 0 , 0
  4216.4     .11       0  4985.3     .06       0  5014.8     .11       0
Bank Sta=4985.3,5014.8
XS Rating Curve= 0 ,0
Exp/Cntr=0.3,0.1

Type RM Length L Ch R = 1 ,4744    ,902,902,902
BEGIN DESCRIPTION:
CCLC 093 3.0
END DESCRIPTION:
XS GIS Cut Line= 3
      3702317.86     10229061.08      3701732.33     10228454.07
      3700967.87     10228961.06
#Sta/Elev= 30
  4156.6  372.12  4206.1  370.33  4269.7  369.49  4283.8  369.97    4298  368.69
  4390.1  367.13  4460.8  364.82  4467.8  365.35  4531.6   363.4  4616.2  362.26
  4722.5  359.37  4764.9  359.57  4849.8  358.24  4856.7  358.83  4878.1  357.87
    4991  357.94  4996.5  356.38  5022.5  357.81  5065.4  358.91  5173.4  358.71
  5218.1   359.9  5254.1  359.33  5311.3  360.25  5593.3  360.91  5642.1  362.49
  5759.4  363.35  5888.8  365.69  5903.8  367.33  5914.3  371.27  5917.3  371.27
#Mann= 3 , 0 , 0
  4156.6     .11       0    4991     .06       0  5022.5     .11       0
Bank Sta=4991,5022.5
XS Rating Curve= 0 ,0
Exp/Cntr=0.3,0.1

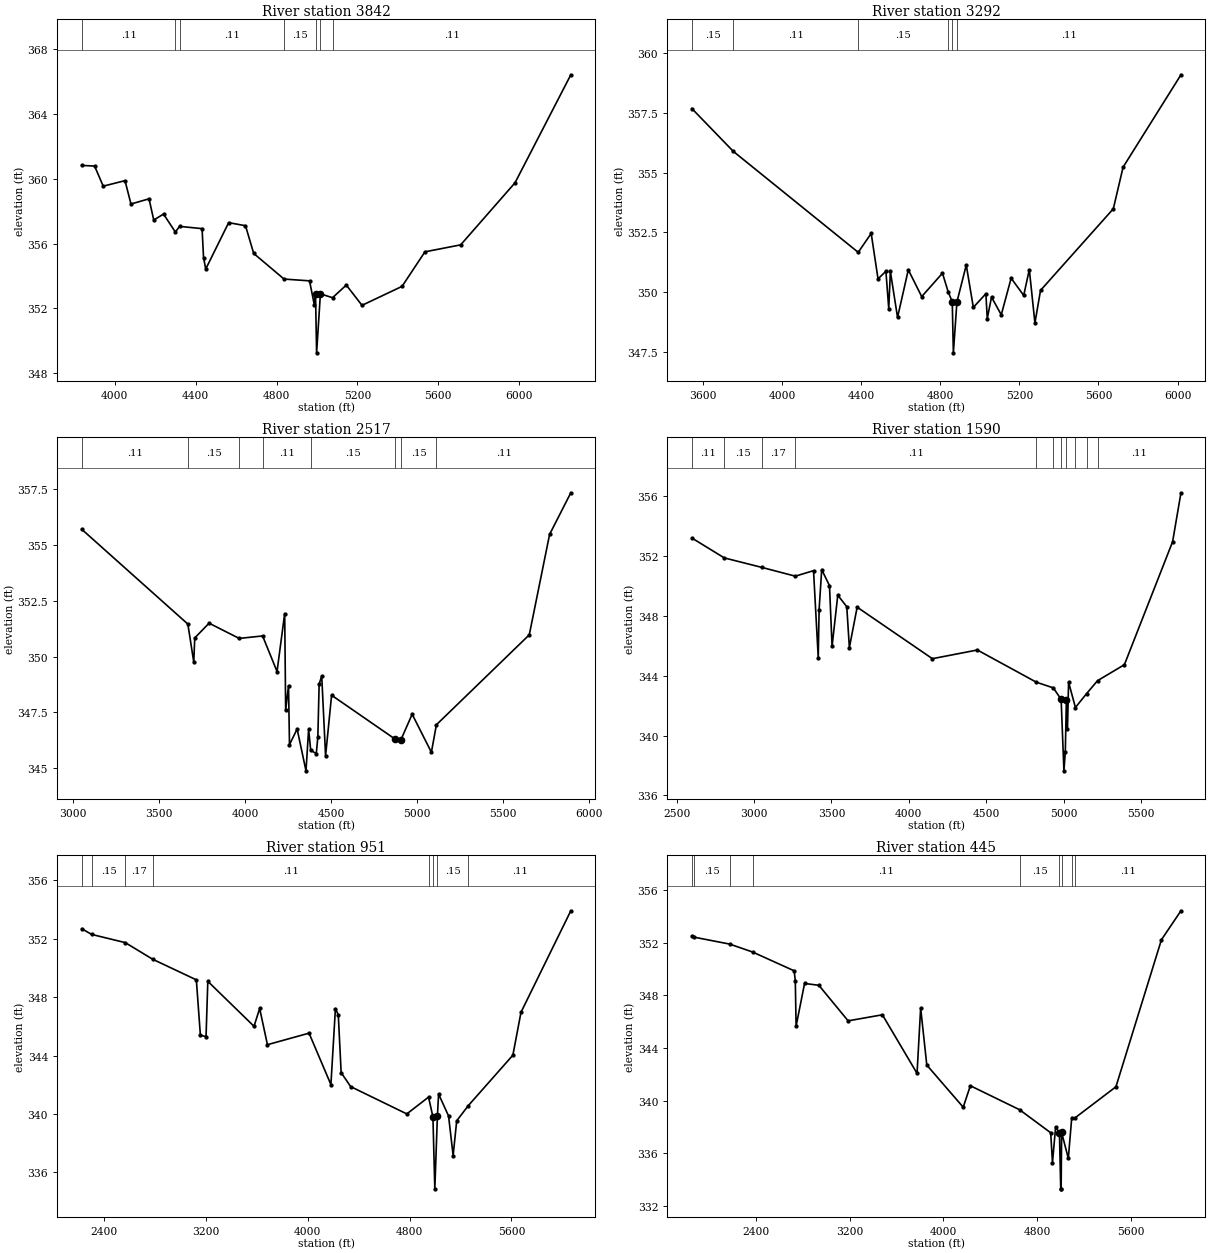
Type RM Length L Ch R = 1 ,3842    ,550,550,550
BEGIN DESCRIPTION:
CCLC 093 2.0
END DESCRIPTION:
XS GIS Cut Line= 3
      3702696.65     10228198.16      3701535.17      10227729.4
      3700717.82      10228561.1
#Sta/Elev= 30
  3836.4  360.82  3900.3  360.78  3942.9  359.54  4050.6  359.88  4080.1  358.44
  4169.4  358.76  4192.8  357.45  4241.1  357.82  4299.6  356.71  4320.3  357.06
  4431.7  356.92    4439  355.13  4449.8  354.43  4563.2  357.29  4646.4   357.1
    4687  355.39  4837.1  353.81  4963.1   353.7  4987.2  352.19  4992.6   352.9
    4998  349.26  5016.8   352.9  5076.8  352.66  5144.8  353.44  5222.5  352.19
  5420.5  353.36  5533.7  355.49  5710.4  355.92  5979.2  359.75    6255  366.41
#Mann= 7 ,-1 , 0
  3836.4     .11       0  4299.6     .17       0  4320.3     .11       0
  4837.1     .15       0  4992.6     .09       0  5016.8     .15       0
  5076.8     .11       0
Bank Sta=4992.6,5016.8
XS Rating Curve= 0 ,0
Exp/Cntr=0.3,0.1

Type RM Length L Ch R = 1 ,3292    ,775,775,775
BEGIN DESCRIPTION:
Mapping XS 4a2a0aff
END DESCRIPTION:
XS GIS Cut Line= 3
      3702654.95     10227661.69      3701592.46     10227151.27
      3700712.52      10228098.9
#Sta/Elev= 30
  3544.9  357.68  3754.4  355.89  4385.7  351.67  4451.4  352.46  4485.9  350.56
  4525.7  350.88  4540.1  349.32  4548.3  350.87  4584.5  348.95  4638.9  350.94
  4706.6  349.82  4811.6   350.8    4841     350    4861  349.61  4866.6  347.47
  4884.6349.5938  4931.8  351.14  4967.5  349.37    5031  349.94  5037.9   348.9
  5059.4   349.8  5108.7  349.06  5158.6  350.59  5222.1  349.87  5250.4  350.95
  5278.8  348.72  5307.1  350.08    5675  353.49  5724.4  355.23  6016.8  359.09
#Mann= 6 ,-1 , 0
  3544.9     .15       0  3754.4     .11       0  4385.7     .15       0
    4841     .11       0    4861     .06       0  4884.6     .11       0
Bank Sta=4861,4884.6
XS Rating Curve= 0 ,0
Exp/Cntr=0.3,0.1

Type RM Length L Ch R = 1 ,2517    ,927,927,927
BEGIN DESCRIPTION:
Mapping XS a1c27603
END DESCRIPTION:
XS GIS Cut Line= 3
      3702483.12      10227531.5       3700993.5     10226776.27
      3700468.04      10227827.2
#Sta/Elev= 30
  3049.9  355.69  3667.5  351.45  3701.9  349.75  3707.5  350.83  3790.9  351.49
  3966.1  350.81  4102.2  350.92  4186.2  349.33  4230.7  351.92  4236.3   347.6
    4253   348.7  4258.6  346.06  4303.1  346.76  4354.6  344.89  4369.9  346.74
  4382.1  345.81  4414.5  345.66  4423.6  346.41  4431.1  348.77  4446.1  349.13
  4468.5  345.56  4503.5  348.27  4870.7  346.32  4905.1  346.25  4972.2  347.42
    5084  345.72  5113.2  346.95  5653.4  350.97  5771.6  355.46    5895  357.32
#Mann= 8 ,-1 , 0
  3049.9     .11       0  3667.5     .15       0  3966.1     .17       0
  4102.2     .11       0  4382.1     .15       0  4870.7     .09       0
  4905.1     .15       0  5113.2     .11       0
#Block Obstruct= 2 , 0
         4502.33  348.24
Bank Sta=4870.7,4905.1
XS Rating Curve= 0 ,0
Exp/Cntr=0.3,0.1

Type RM Length L Ch R = 1 ,1590    ,639,639,639
BEGIN DESCRIPTION:
Mapping XS f300919c
END DESCRIPTION:
XS GIS Cut Line= 3
      3702170.58     10227323.15      3700342.46     10226406.48
      3699541.61     10227181.32
#Sta/Elev= 30
  2598.5  353.19  2808.3  351.86  3049.2  351.23  3267.3  350.64  3384.6  351.01
    3415   345.2  3420.6  348.41  3437.4  351.08  3487.6  350.01  3504.4  345.96
  3541.2  349.37  3599.3   348.6  3616.1  345.87  3666.4  348.57  4152.3  345.13
  4442.7  345.71  4823.8  343.56  4933.5  343.18  4983.9 342.412  5001.9  337.64
  5010.8  338.89  5017.9342.3828    5025  340.45    5032  343.56  5076.2  341.87
  5147.8  342.79    5219  343.66  5392.6  344.73  5703.9  352.94  5757.9  356.21
#Mann= 11 ,-1 , 0
  2598.5     .11       0  2808.3     .15       0  3049.2     .17       0
  3267.3     .11       0  4823.8     .15       0  4933.5     .11       0
  4983.9     .07       0  5017.9     .15       0  5076.2     .11       0
  5147.8     .15       0    5219     .11       0
Bank Sta=4983.9,5017.9
XS Rating Curve= 0 ,0
Exp/Cntr=0.3,0.1

Type RM Length L Ch R = 1 ,951     ,506,506,506
BEGIN DESCRIPTION:
Mapping XS 16d0ae22
END DESCRIPTION:
XS GIS Cut Line= 3
      3702097.64     10227245.01      3699826.83     10226073.15
      3698832.42     10226885.34
#Sta/Elev= 30
  2226.6  352.68  2305.5  352.29  2568.6  351.73    2784  350.59  3126.6  349.18
  3158.3  345.39  3202.7  345.29  3216.6  349.08  3579.3     346  3623.6  347.22
  3684.5  344.74  4011.2  345.53  4182.8  342.01  4218.2  347.21  4240.7  346.79
  4263.2  342.83  4337.9  341.87  4778.8     340  4949.1  341.15  4983.5339.8009
  4998.4  334.87 5018.57339.8252  5028.1  341.36  5106.3  339.86  5142.2  337.15
  5170.2  339.53  5261.5  340.57    5611  344.02  5674.9  346.96  6065.9  353.91
#Mann= 8 ,-1 , 0
  2226.6     .11       0  2305.5     .15       0  2568.6     .17       0
    2784     .11       0  4949.1     .15       0  4983.5     .09       0
 5018.57     .15       0  5261.5     .11       0
Bank Sta=4983.5,5018.57
XS Rating Curve= 0 ,0
Exp/Cntr=0.3,0.1

Type RM Length L Ch R = 1 ,445     ,0,0,0
BEGIN DESCRIPTION:
CCLC 093 1.0
END DESCRIPTION:
XS GIS Cut Line= 3
      3702082.08     10227203.38      3699420.58     10225833.57
      3698769.52     10226812.76
#Sta/Elev= 30
  1855.8  352.51  1878.3  352.42  2178.6   351.9  2373.1   351.3  2728.1  349.87
  2737.8   349.1  2744.6  345.67  2816.8  348.91  2938.6  348.77  3188.1  346.07
  3480.1  346.53  3775.5  342.08  3806.2  347.05  3858.6  342.71    4169  339.51
  4229.9  341.14  4649.2  339.32  4914.7  337.57  4929.8   335.3  4956.8  338.03
  4989.2337.5307  5000.2  333.31  5003.7  333.31  5007.9  337.59    5065  335.62
    5094  338.72    5119  338.68  5470.6  341.06  5858.6  352.23    6025  354.43
#Mann= 9 ,-1 , 0
  1855.8     .11       0  1878.3     .15       0  2178.6     .17       0
  2373.1     .11       0  4649.2     .15       0  4989.2     .06       0
  5007.9     .11       0    5094     .15       0    5119     .11       0
Bank Sta=4989.2,5007.9
XS Rating Curve= 0 ,0
Exp/Cntr=0.3,0.1

Chan Stop Cuts=-1
Use User Specified Reach Order=0
Composite Channel Slope=5