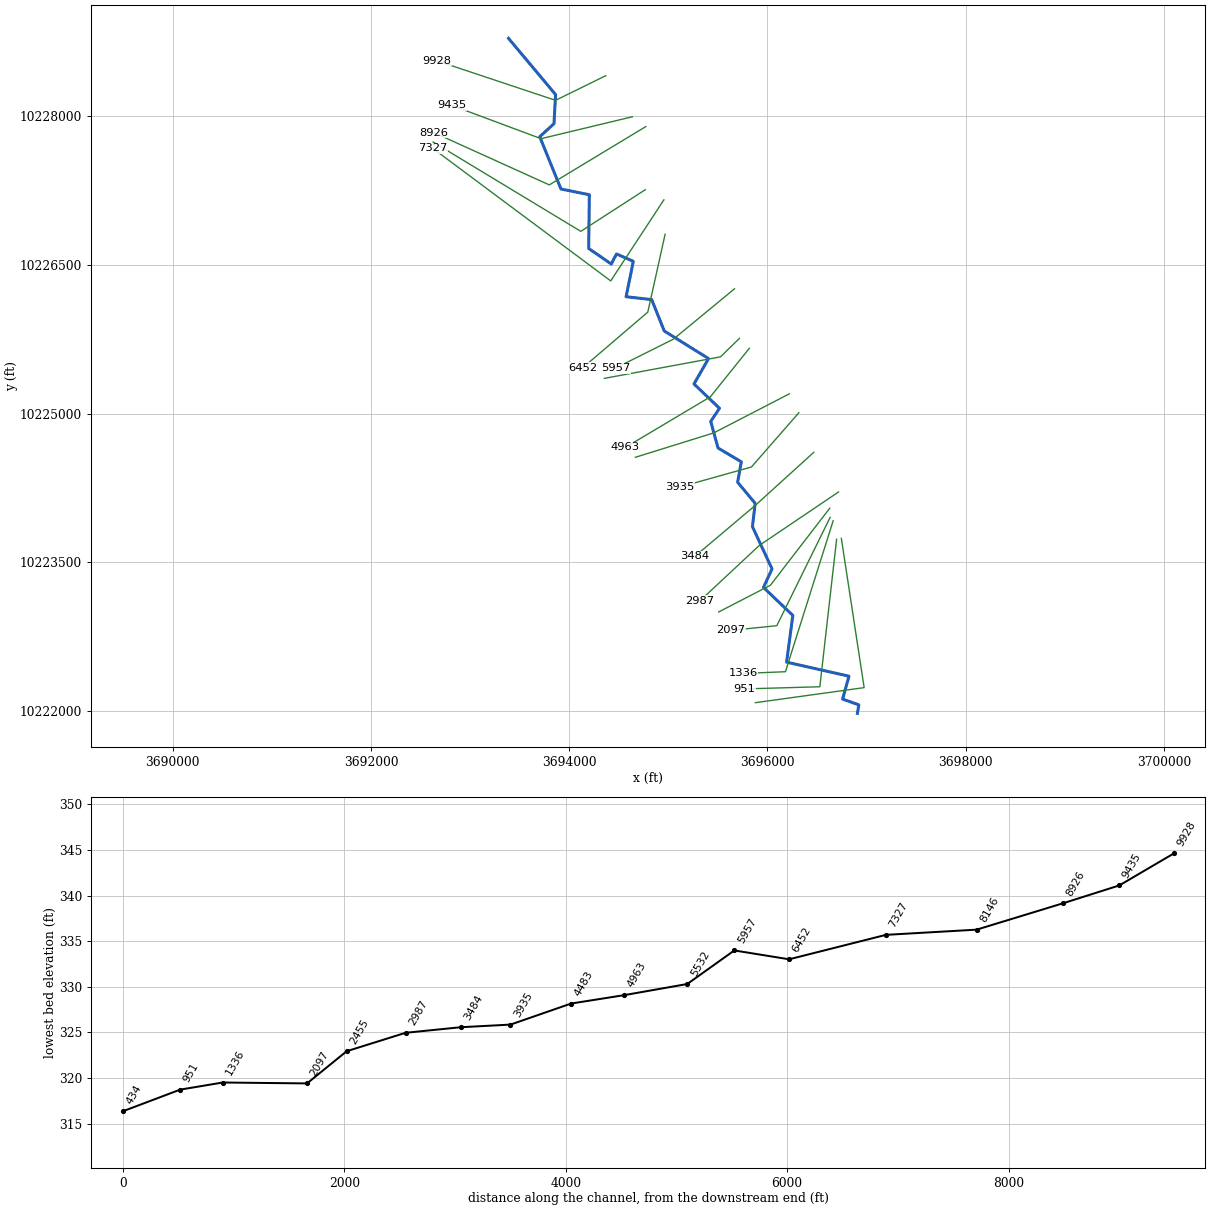
--- CCLC 094.prj (project) ---

Proj Title=CCLC 094 Base Level Engineering
Current Plan=p01
Default Exp/Contr=0.3,0.1
English Units
Geom File=g01
Flow File=f01
Flow File=f02
Plan File=p01
Y Axis Title=Elevation
X Axis Title(PF)=Main Channel Distance
X Axis Title(XS)=Station
BEGIN DESCRIPTION:
CCLC 094
END DESCRIPTION:
DSS Export Rating Curves= 0
DSS Export Rating Curve Sorted= 0
DSS Export Volume Flow Curves= 0
DXF OffsetX= 0
DXF OffsetY= 0
DXF ScaleX= 1
DXF ScaleY= 10

--- CCLC 094.p01 (plan) ---

Plan Title=Multiple Run
Short Identifier=Multiple
Geom File=g01
Flow File=f01
Subcritical Flow
K Sum by GR= 0
Std Step Tol= 0.01
Critical Tol= 0.01
Num of Std Step Trials= 20
Max Error Tol= 0.3
Flow Tol Ratio= 0.001
Split Flow NTrial= 30
Split Flow Tol= 0.02
Split Flow Ratio= 0.02
Log Output Level= 0
Friction Slope Method= 1
Unsteady Friction Slope Method= 2
Unsteady Bridges Friction Slope Method= 1
Parabolic Critical Depth
Global Vel Dist=  1 , 1 , 1
Global Log Level= 0
CheckData=True
Encroach Param= -1, 0, 0, 0
BEGIN DESCRIPTION:
Multiple Run
END DESCRIPTION:

--- CCLC 094.f01 (steady flow) ---

Flow Title=Multiple
Program Version=4.10
Number of Profiles= 7
Profile Names=10-year,25-year,50-year,1pct_min,100-year,1pct_plu,500-year
River Rch & RM=CCLC 094,Reach-1         ,9928
     304     390     506     217     654    1975    1128
River Rch & RM=CCLC 094,Reach-1         ,6452
     842    1150    1559     694    2097    6333    3925
Boundary for River Rch & Prof#=CCLC 094,Reach-1         , 1
Up Type= 0
Dn Type= 3
Dn Slope=0.005
Boundary for River Rch & Prof#=CCLC 094,Reach-1         , 2
Up Type= 0
Dn Type= 3
Dn Slope=0.005
Boundary for River Rch & Prof#=CCLC 094,Reach-1         , 3
Up Type= 0
Dn Type= 3
Dn Slope=0.005
Boundary for River Rch & Prof#=CCLC 094,Reach-1         , 4
Up Type= 0
Dn Type= 3
Dn Slope=0.005
Boundary for River Rch & Prof#=CCLC 094,Reach-1         , 5
Up Type= 0
Dn Type= 3
Dn Slope=0.005
Boundary for River Rch & Prof#=CCLC 094,Reach-1         , 6
Up Type= 0
Dn Type= 3
Dn Slope=0.005
Boundary for River Rch & Prof#=CCLC 094,Reach-1         , 7
Up Type= 0
Dn Type= 3
Dn Slope=0.005
DSS Import GetInterval= 0
DSS Import GetPeak= 0
DSS Import FillOption= 0

--- CCLC 094.f02 (steady flow) ---

Flow Title=Orig_BLE_Flows
Program Version=4.10
Number of Profiles= 7
Profile Names=10-year,25-year,50-year,1pct_min,100-year,1pct_plu,500-year
River Rch & RM=CCLC 094,Reach-1         ,9928
     304     382     440     167     503    1520     656
River Rch & RM=CCLC 094,Reach-1         ,6452
     842    1127    1356     534    1613    4871    2282
Boundary for River Rch & Prof#=CCLC 094,Reach-1         , 1
Up Type= 0
Dn Type= 3
Dn Slope=0.005
Boundary for River Rch & Prof#=CCLC 094,Reach-1         , 2
Up Type= 0
Dn Type= 3
Dn Slope=0.005
Boundary for River Rch & Prof#=CCLC 094,Reach-1         , 3
Up Type= 0
Dn Type= 3
Dn Slope=0.005
Boundary for River Rch & Prof#=CCLC 094,Reach-1         , 4
Up Type= 0
Dn Type= 3
Dn Slope=0.005
Boundary for River Rch & Prof#=CCLC 094,Reach-1         , 5
Up Type= 0
Dn Type= 3
Dn Slope=0.005
Boundary for River Rch & Prof#=CCLC 094,Reach-1         , 6
Up Type= 0
Dn Type= 3
Dn Slope=0.005
Boundary for River Rch & Prof#=CCLC 094,Reach-1         , 7
Up Type= 0
Dn Type= 3
Dn Slope=0.005
DSS Import GetInterval= 0
DSS Import GetPeak= 0
DSS Import FillOption= 0

--- CCLC 094.g01 (geometry) ---

Geom Title=Existing Conditions
Program Version=4.10

River Reach=CCLC 094        ,Reach-1
Reach XY= 30
       3693387.6     10228788.54      3693862.43      10228221.2
      3693846.55     10227927.51      3693702.72     10227795.82
      3693916.54     10227268.37      3694203.33     10227210.18
      3694196.43     10226668.19      3694424.51     10226511.44
      3694476.99     10226612.59      3694646.82     10226538.53
      3694573.99     10226181.35      3694832.93     10226151.85
      3694959.29     10225835.43      3695406.14     10225556.97
      3695259.06     10225301.02      3695516.63     10225055.24
      3695427.99     10224923.22      3695501.86     10224654.41
      3695736.81     10224515.38      3695699.67     10224309.33
       3695876.4     10224096.25      3695848.93     10223860.97
       3696046.6     10223434.39      3695960.25      10223247.7
      3696256.61     10222965.28      3696193.38     10222493.82
      3696823.12     10222351.86      3696758.81     10222120.98
      3696922.43     10222062.94      3696908.23     10221976.84

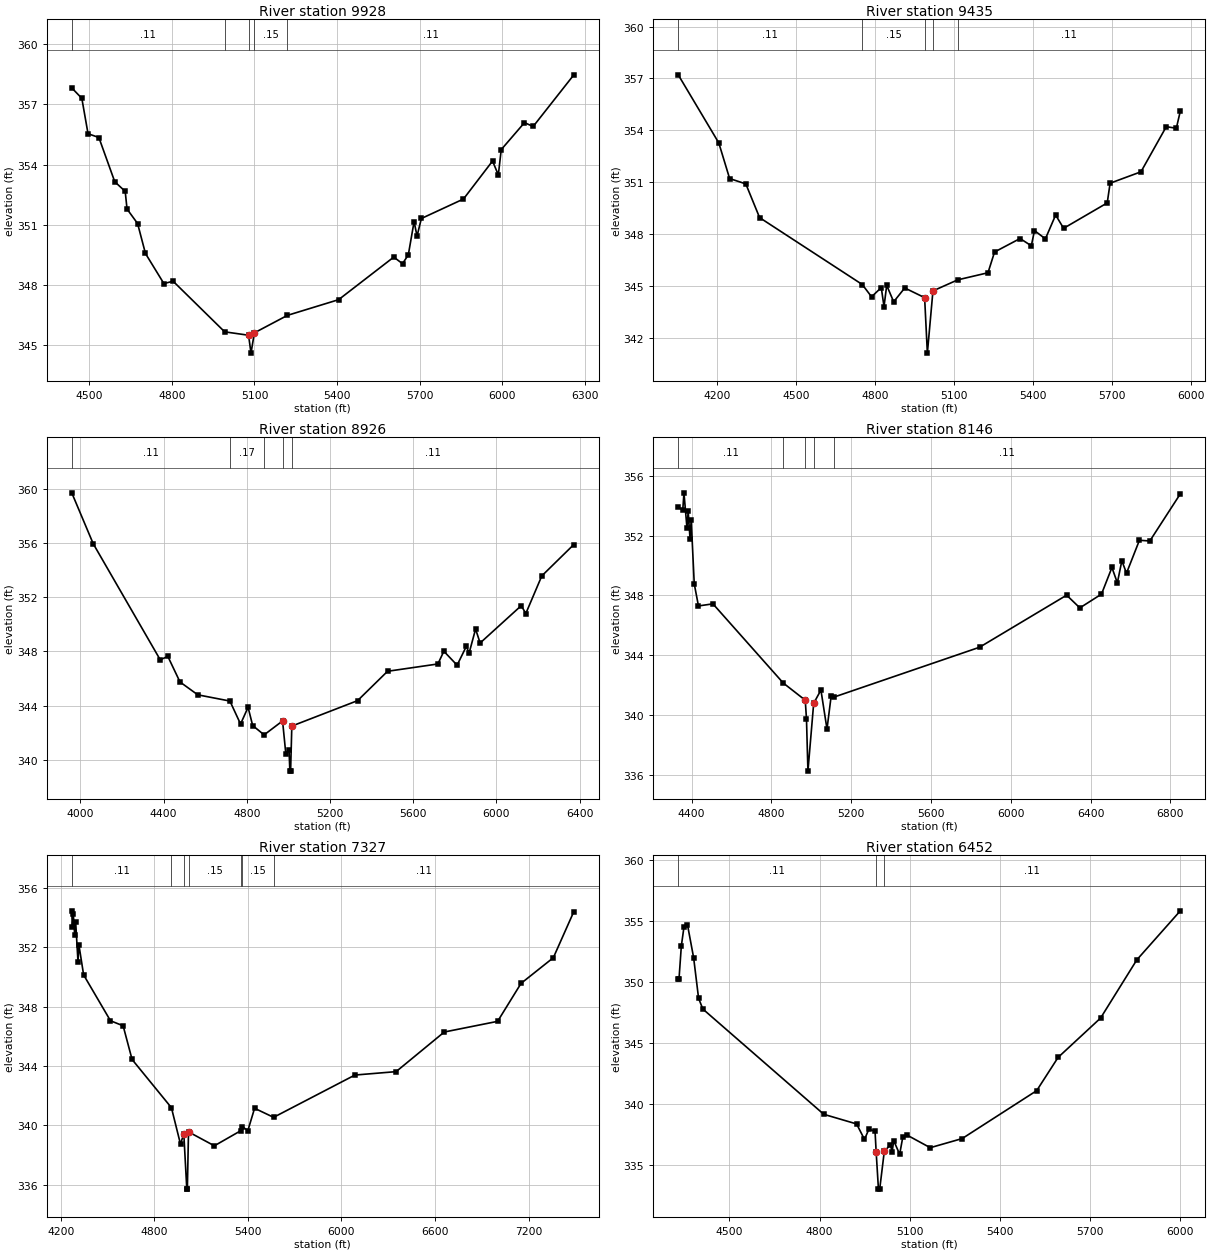
Type RM Length L Ch R = 1 ,9928    ,493,493,493
BEGIN DESCRIPTION:
CCLC 094 14.0
END DESCRIPTION:
XS GIS Cut Line= 3
      3694367.88     10228411.09      3693862.43     10228162.89
      3692667.85     10228561.07
#Sta/Elev= 30
  4436.9  357.82  4473.4   357.3  4495.9  355.54  4535.3  355.35  4592.9  353.15
  4630.8  352.67  4637.5  351.79  4675.8  351.07  4704.3  349.58  4771.3  348.08
  4804.6   348.2  4991.8  345.68  5078.6  345.51  5087.4  344.62  5099.7  345.63
  5219.7   346.5  5405.4  347.28  5605.7   349.4  5637.3  349.07  5658.4  349.51
  5679.4  351.17    5690  350.44  5705.8  351.32  5858.6  352.29  5964.1  354.18
  5985.1  353.49  5995.7  354.75    6080  356.09  6111.6   355.9  6259.2  358.47
#Mann= 5 ,-1 , 0
  4436.9     .11       0  4991.8     .15       0  5078.6     .09       0
  5099.7     .15       0  5219.7     .11       0
Bank Sta=5078.6,5099.7
XS Rating Curve= 0 ,0
Exp/Cntr=0.3,0.1

Type RM Length L Ch R = 1 ,9435    ,509,509,509
BEGIN DESCRIPTION:
CCLC 094 13.0
END DESCRIPTION:
XS GIS Cut Line= 3
      3694637.56     10227997.07      3693715.91     10227775.98
      3692817.88     10228111.06
#Sta/Elev= 30
  4052.2  357.21  4206.2  353.27  4247.3  351.21  4308.8   350.9  4361.1  348.95
  4750.9  345.08  4786.2  344.37  4823.1   344.9  4833.5   343.8  4843.7  345.03
  4870.2  344.08  4912.2  344.88  4987.7  344.32  4998.1  341.11  5019.3  344.71
  5113.5  345.35  5228.3  345.76  5253.2  346.96  5350.1  347.74  5392.8  347.32
  5404.8   348.2  5446.2  347.72  5485.1   349.1  5515.4  348.33    5681   349.8
  5691.9  350.94  5809.1   351.6  5905.2  354.21  5943.4  354.12  5958.5  355.11
#Mann= 5 ,-1 , 0
  4052.2     .11       0  4750.9     .15       0  4987.7     .09       0
  5019.3     .15       0  5113.5     .11       0
Bank Sta=4987.7,5019.3
XS Rating Curve= 0 ,0
Exp/Cntr=0.3,0.1

Type RM Length L Ch R = 1 ,8926    ,780,780,780
BEGIN DESCRIPTION:
CCLC 094 12.0
END DESCRIPTION:
XS GIS Cut Line= 3
      3694773.02     10227898.12      3693799.05     10227309.57
      3692637.61     10227835.61
#Sta/Elev= 30
  3958.8  359.72  4061.8  355.96  4383.9  347.38  4420.5  347.63  4478.9  345.74
  4564.4  344.79  4718.8  344.33    4770  342.63  4806.1  343.87  4828.2  342.52
  4883.3  341.83  4971.9  342.86  4987.4  340.45  5002.9  340.72    5007  339.15
  5010.5  339.15  5016.4  342.48  5332.4  344.36  5476.5  346.53  5718.4  347.07
    5747  348.01  5810.8  346.98  5855.6  348.39    5868  347.85  5899.5  349.65
  5921.4  348.62    6119  351.38    6141   350.8  6217.8  353.58  6371.8   355.9
#Mann= 5 ,-1 , 0
  3958.8     .11       0  4718.8     .17       0  4883.3     .15       0
  4971.9     .06       0  5016.4     .11       0
Bank Sta=4971.9,5016.4
XS Rating Curve= 0 ,0
Exp/Cntr=0.3,0.1

Type RM Length L Ch R = 1 ,8146    ,819,819,819
BEGIN DESCRIPTION:
CCLC 094 11.0
END DESCRIPTION:
XS GIS Cut Line= 3
      3694767.87     10227261.08      3694116.76     10226840.82
      3692627.14     10227741.89
#Sta/Elev= 30
  4333.4  353.89  4356.2  353.73  4362.1  354.86  4377.3  352.48  4383.2  353.62
  4392.5  351.79  4398.4  353.05  4413.6  348.78  4434.7   347.3  4507.3  347.44
  4859.5  342.15  4969.9     341  4976.1  339.72  4983.3  336.26  5012.1  340.79
  5048.4  341.68  5078.8  339.07  5099.9   341.3  5116.4  341.22  5843.4  344.54
  6279.7  348.02  6345.9  347.17  6454.3  348.09  6506.7  349.87  6533.8  348.84
  6556.3  350.32  6579.7  349.49  6644.4  351.69  6696.5  351.64  6849.3  354.79
#Mann= 5 ,-1 , 0
  4333.4     .11       0  4859.5     .15       0  4969.9     .09       0
  5012.1     .15       0  5116.4     .11       0
Bank Sta=4969.9,5012.1
XS Rating Curve= 0 ,0
Exp/Cntr=0.3,0.1

Type RM Length L Ch R = 1 ,7327    ,875,875,875
BEGIN DESCRIPTION:
CCLC 094 10.0
END DESCRIPTION:
XS GIS Cut Line= 3
       3694955.3     10227158.52      3694418.85     10226340.82
      3692622.45     10227679.01
#Sta/Elev= 30
  4271.3  354.45    4275  353.34    4281  354.26  4290.1  352.79  4296.1  353.72
  4311.2  351.02  4317.1  352.15  4347.3  350.13  4519.4  347.04  4600.5   346.7
  4657.8  344.43    4910  341.18  4968.2  338.72  4989.3  339.43  5008.6  335.69
  5012.1  335.69  5019.5  339.55  5185.2  338.61  5353.1  339.62  5363.6   339.9
  5400.1  339.64    5443  341.14  5564.9  340.53    6086  343.38  6350.1  343.61
  6658.7  346.28  7000.7     347  7150.9  349.56  7357.9  351.29  7489.3   354.4
#Mann= 7 ,-1 , 0
  4271.3     .11       0    4910     .15       0  4989.3     .09       0
  5019.5     .15       0  5353.1     .11       0  5363.6     .15       0
  5564.9     .11       0
Bank Sta=4989.3,5019.5
XS Rating Curve= 0 ,0
Exp/Cntr=0.3,0.1

Type RM Length L Ch R = 1 ,6452    ,495,495,495
BEGIN DESCRIPTION:
CCLC 094 9.0
END DESCRIPTION:
XS GIS Cut Line= 3
      3694967.86     10226811.11      3694792.98     10226025.72
      3694133.28      10225461.5
#Sta/Elev= 30
  4329.3  350.27  4331.9  350.27  4339.6  352.96  4348.5  354.54  4360.1  354.71
  4380.6     352  4397.1  348.67  4411.3  347.79  4814.2  339.15  4923.5  338.36
  4949.8  337.09  4964.5  337.93    4985  337.76 4988.75336.0386  4996.3  333.01
  5000.5  333.01  5015.8  336.11  5036.2  336.65  5041.9  336.06  5047.1  336.99
    5067  335.87  5077.2  337.25  5090.5  337.46  5168.9  336.41  5275.3  337.16
  5523.4  341.09  5594.8  343.82  5736.4  347.05  5857.2  351.83    6002  355.85
#Mann= 3 , 0 , 0
  4329.3     .11       0 4988.75     .06       0  5015.8     .11       0
Bank Sta=4988.75,5015.8
XS Rating Curve= 0 ,0
Exp/Cntr=0.3,0.1

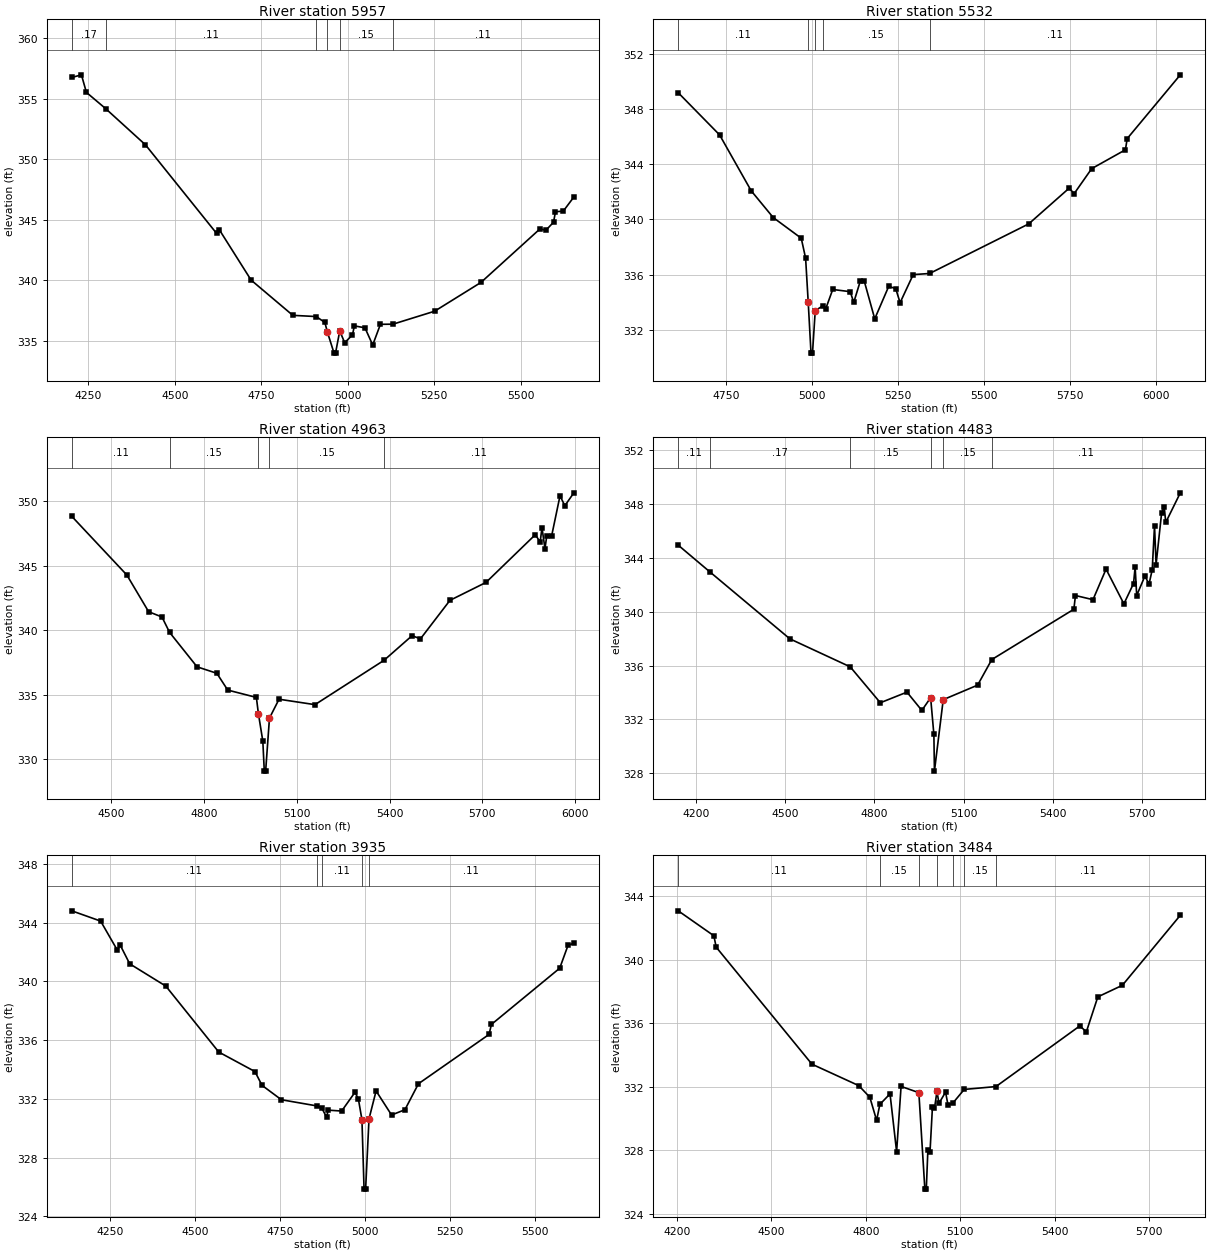
Type RM Length L Ch R = 1 ,5957    ,425,425,425
BEGIN DESCRIPTION:
CCLC 094 8.0
END DESCRIPTION:
XS GIS Cut Line= 3
      3695667.81     10226261.04       3695052.2     10225753.44
      3694467.86     10225461.07
#Sta/Elev= 30
  4202.1  356.74    4230  356.96  4244.4  355.51    4300  354.17  4415.1  351.18
  4620.9  343.86  4628.8  344.16  4720.5  340.01  4841.1   337.1  4908.9     337
  4933.7  336.51  4940.8  335.74  4960.2  333.98  4964.5  333.98  4976.7  335.81
    4991  334.84  5013.5  335.49    5019  336.23  5049.6  336.07    5072  334.65
  5094.3  336.36  5130.4  336.37  5250.9  337.44    5385  339.82  5555.6  344.24
  5572.4  344.12  5594.7  344.79  5600.3  345.66  5622.7   345.7  5653.4  346.87
#Mann= 6 ,-1 , 0
  4202.1     .17       0    4300     .11       0  4908.9     .15       0
  4940.8     .09       0  4976.7     .15       0  5130.4     .11       0
Bank Sta=4940.8,4976.7
XS Rating Curve= 0 ,0
Exp/Cntr=0.3,0.1

Type RM Length L Ch R = 1 ,5532    ,569,569,569
BEGIN DESCRIPTION:
CCLC 094 7.0
END DESCRIPTION:
XS GIS Cut Line= 3
      3695717.84     10225761.06      3695526.48     10225574.33
      3694354.57     10225357.31
#Sta/Elev= 30
  4611.8   349.2    4732  346.14  4823.9  342.08  4887.9  340.14  4969.3  338.64
    4982  337.19  4989.6  333.98  4997.7   330.3    5002   330.3    5010  333.39
  5032.1  333.73  5040.5  333.52  5060.8  334.92  5111.7  334.76  5121.9  333.98
  5140.7  335.51  5152.4  335.53  5182.9  332.79  5223.6  335.15  5243.9  334.98
  5256.6  333.96  5294.7     336  5342.3  336.08  5630.4  339.68  5747.8  342.27
  5762.6  341.88  5813.4  343.69  5911.5  345.06  5916.6  345.87    6071   350.5
#Mann= 5 ,-1 , 0
  4611.8     .11       0  4989.6     .06       0    5010     .11       0
  5032.1     .15       0  5342.3     .11       0
Bank Sta=4989.6,5010
XS Rating Curve= 0 ,0
Exp/Cntr=0.3,0.1

Type RM Length L Ch R = 1 ,4963    ,480,480,480
BEGIN DESCRIPTION:
CCLC 094 6.0
END DESCRIPTION:
XS GIS Cut Line= 3
      3695817.86     10225661.09       3695424.2     10225171.02
      3694567.84     10224661.06
#Sta/Elev= 30
  4371.4  348.82  4549.8  344.27  4620.2  341.43  4663.4  341.02    4688  339.83
    4777  337.16    4841  336.66  4876.2  335.36    4969  334.79  4975.5  333.54
  4989.9   331.4  4994.6  329.08    4999  329.08  5011.4  333.19  5042.3  334.65
  5158.7  334.23  5382.5  337.67  5472.9  339.57  5500.2  339.33  5595.6  342.31
  5712.4   343.7  5872.1   347.4  5887.7  346.82  5893.5  347.94  5903.2  346.32
  5909.1  347.31  5924.7  347.29  5951.9  350.41  5967.5  349.64  5996.7  350.64
#Mann= 5 ,-1 , 0
  4371.4     .11       0    4688     .15       0  4975.5     .09       0
  5011.4     .15       0  5382.5     .11       0
Bank Sta=4975.5,5011.4
XS Rating Curve= 0 ,0
Exp/Cntr=0.3,0.1

Type RM Length L Ch R = 1 ,4483    ,548,548,548
BEGIN DESCRIPTION:
CCLC 094 5.0
END DESCRIPTION:
XS GIS Cut Line= 3
      3696220.92     10225201.06      3695458.16     10224806.87
       3694667.8     10224561.06
#Sta/Elev= 30
  4141.4  344.95  4247.4  342.97  4516.3  337.99    4719  335.91  4820.2  333.24
  4909.6  334.03  4959.6  332.67  4989.1  333.62    5000  330.89  5001.9  328.16
  5031.4  333.47  5146.9  334.55  5194.5  336.45  5470.2  340.19  5475.5  341.21
  5534.4   340.9  5578.3  343.17  5638.2  340.59  5670.6   342.1    5676  343.34
  5681.2  341.21  5708.5  342.64  5722.9  342.08  5733.4  343.13  5741.1  346.41
  5746.3  343.51  5764.8  347.33  5773.6  347.81  5778.8  346.64  5827.7  348.84
#Mann= 6 ,-1 , 0
  4141.4     .11       0  4247.4     .17       0    4719     .15       0
  4989.1     .09       0  5031.4     .15       0  5194.5     .11       0
Bank Sta=4989.1,5031.4
XS Rating Curve= 0 ,0
Exp/Cntr=0.3,0.1

Type RM Length L Ch R = 1 ,3935    ,451,451,451
BEGIN DESCRIPTION:
CCLC 094 4.0
END DESCRIPTION:
XS GIS Cut Line= 3
      3696317.85     10225011.07      3695838.98     10224463.22
      3695117.81     10224261.06
#Sta/Elev= 30
  4136.8  344.81  4221.7  344.11  4271.1  342.12  4278.7   342.5  4307.2   341.2
  4413.5  339.68  4569.1  335.19  4675.5  333.86  4696.3  332.92  4753.3  331.94
  4857.5  331.52  4871.3  331.41    4886  330.76  4891.2  331.23  4930.5  331.17
  4969.8  332.45  4979.8  331.98  4990.2  330.58  4996.4  325.85    5001  325.85
    5011  330.64  5031.8  332.54  5077.3   330.9  5116.6  331.26  5156.4  333.03
  5364.1  336.39  5370.9  337.07  5571.8   340.9  5596.3  342.46  5613.4   342.6
#Mann= 5 ,-1 , 0
  4136.8     .11       0  4857.5     .15       0  4871.3     .11       0
  4990.2     .06       0    5011     .11       0
Bank Sta=4990.2,5011
XS Rating Curve= 0 ,0
Exp/Cntr=0.3,0.1

Type RM Length L Ch R = 1 ,3484    ,497,497,497
BEGIN DESCRIPTION:
CCLC 094 3.0
END DESCRIPTION:
XS GIS Cut Line= 3
      3696467.82     10224611.04       3695878.5     10224076.25
      3695267.88      10223561.1
#Sta/Elev= 30
  4204.2  343.09  4317.3  341.52  4324.8   340.8  4628.9  333.43  4777.6  332.08
  4812.7  331.35  4834.3  329.89  4844.6   330.9  4876.9  331.56  4897.8  327.92
    4912  332.03 4968.47331.6362  4987.5  325.56  4992.1  325.56  4997.1  328.01
  5003.8  327.87  5011.6  330.72  5018.1  330.64  5025.9  331.71  5032.4  330.97
  5053.3  331.67    5061  330.86  5076.5  330.98  5112.5  331.84  5213.3  332.02
  5479.7  335.84  5500.5  335.47  5536.9  337.67  5614.9   338.4  5798.9  342.81
#Mann= 7 ,-1 , 0
  4204.2     .11       0  4844.6     .15       0 4968.47     .09       0
  5025.9     .15       0  5076.5     .11       0  5112.5     .15       0
  5213.3     .11       0
Bank Sta=4968.47,5025.9
XS Rating Curve= 0 ,0
Exp/Cntr=0.3,0.1

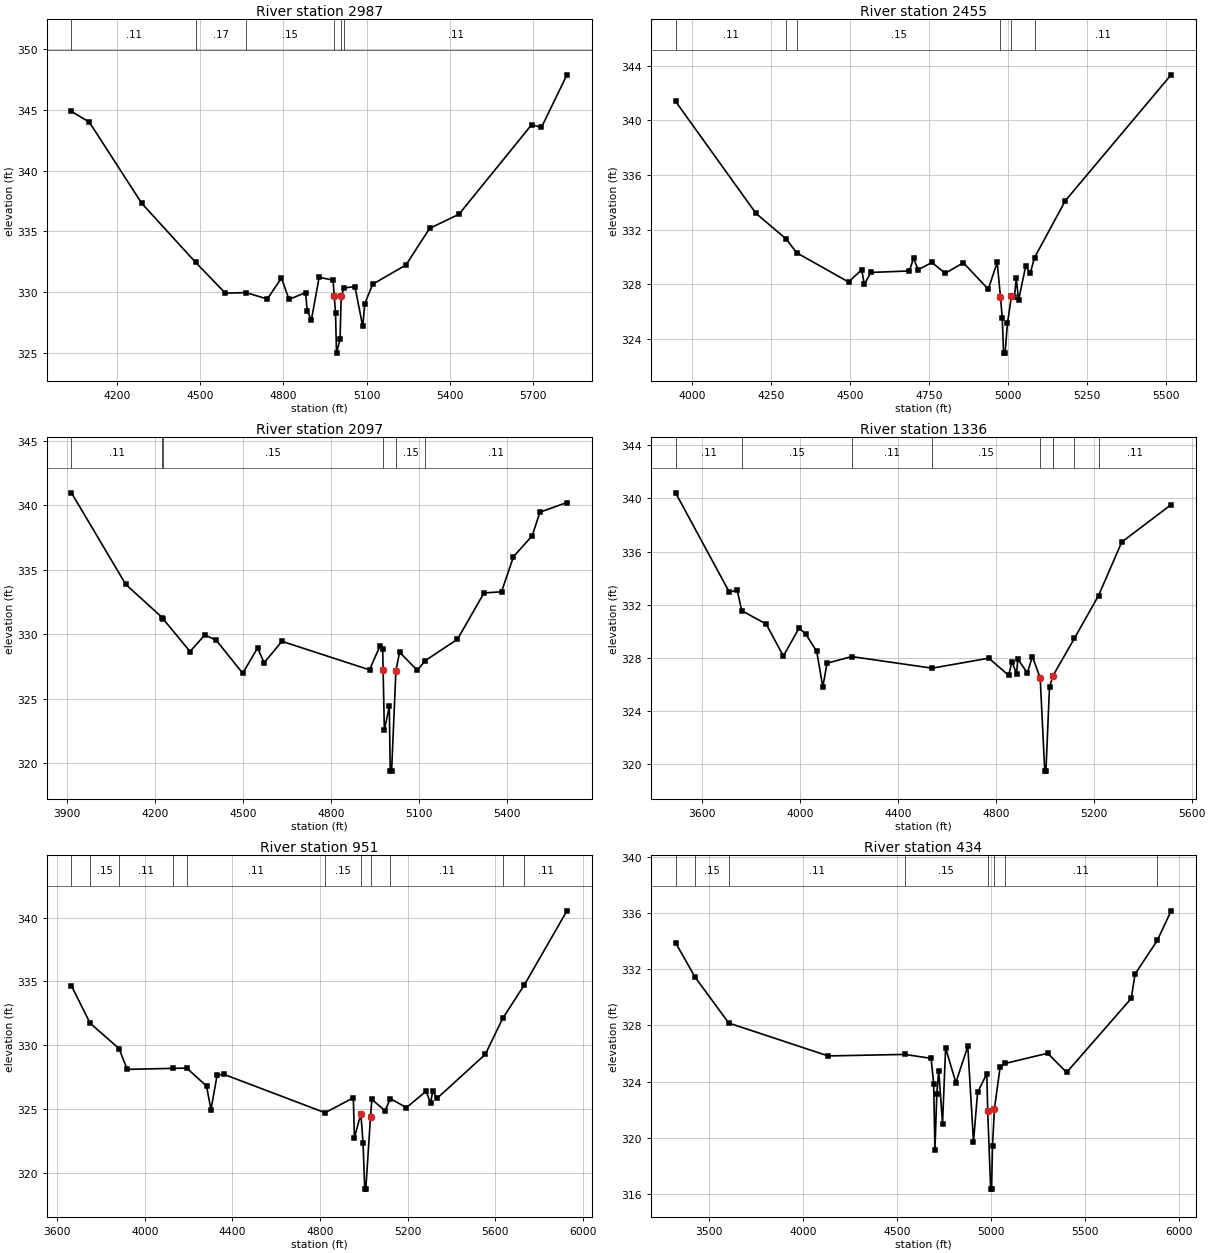
Type RM Length L Ch R = 1 ,2987    ,532,532,532
BEGIN DESCRIPTION:
CCLC 094 2.0
END DESCRIPTION:
XS GIS Cut Line= 3
      3696717.85     10224211.07      3695918.95     10223671.94
      3695317.87     10223111.09
#Sta/Elev= 30
  4036.2  344.87  4100.7  343.99  4289.5   337.3  4483.4  332.44  4591.1  329.89
  4665.4  329.94  4742.1  329.41  4793.1  331.14  4820.4  329.38    4880  329.94
    4886  328.43    4901  327.68  4928.9   331.2    4979  330.97 4983.36329.6522
  4987.9  328.28  4991.6  324.95  5004.2  326.08  5008.5   329.7  5019.6  330.32
  5057.8  330.44  5086.1  327.15  5093.5  329.03  5121.8  330.63    5242  332.22
    5327  335.23    5433   336.4  5694.9  343.78    5730  343.55  5822.1  347.89
#Mann= 6 ,-1 , 0
  4036.2     .11       0  4483.4     .17       0  4665.4     .15       0
 4983.36     .09       0  5008.5     .15       0  5019.6     .11       0
Bank Sta=4983.36,5008.5
XS Rating Curve= 0 ,0
Exp/Cntr=0.3,0.1

Type RM Length L Ch R = 1 ,2455    ,358,358,358
BEGIN DESCRIPTION:
Mapping XS a427882c
END DESCRIPTION:
XS GIS Cut Line= 3
      3696628.92     10224046.56      3696029.96     10223269.64
      3695509.16     10223000.56
#Sta/Elev= 30
  3948.7   341.4  4203.1  333.18  4298.7   331.3  4331.8  330.29  4495.7  328.15
  4537.3  329.05  4545.5  327.97  4566.3  328.85    4688  328.96  4701.3  329.89
  4715.8  329.05  4759.3  329.58  4801.6  328.79  4858.9  329.56  4937.6  327.62
  4965.8  329.59  4976.3  327.03  4981.9  325.52    4986  322.93  4990.7  322.93
  4998.4  325.14  5010.9  327.09  5020.5  327.05  5026.2  328.46  5033.4  326.81
  5055.9   329.3  5070.5  328.81    5084  329.94  5181.2  334.11  5515.9  343.35
#Mann= 6 ,-1 , 0
  3948.7     .11       0  4298.7     .17       0  4331.8     .15       0
  4976.3     .09       0  5010.9     .15       0    5084     .11       0
Bank Sta=4976.3,5010.9
XS Rating Curve= 0 ,0
Exp/Cntr=0.3,0.1

Type RM Length L Ch R = 1 ,2097    ,761,761,761
BEGIN DESCRIPTION:
Mapping XS a4ea318e
END DESCRIPTION:
XS GIS Cut Line= 3
      3696633.25      10223955.4      3696095.06     10222861.66
      3695626.27     10222813.91
#Sta/Elev= 30
  3914.4  340.97  4099.8  333.87  4224.7  331.29  4227.8  331.18  4318.9  328.67
  4369.5  329.96  4408.8  329.53  4498.7  326.98  4549.2  328.95  4571.7   327.8
  4632.5  329.46  4931.2  327.25  4966.9  329.11  4976.1  328.85 4977.57327.2045
  4981.7  322.58  4998.6  324.41  5001.8   319.4  5006.5   319.4  5021.1  327.17
  5033.7  328.62  5094.1  327.21  5120.9  327.96  5231.1  329.62  5321.6  333.21
  5381.4   333.3  5422.1  336.02    5486  337.64  5512.5  339.47  5604.6  340.22
#Mann= 6 ,-1 , 0
  3914.4     .11       0  4224.7     .17       0  4227.8     .15       0
 4977.57     .09       0  5021.1     .15       0  5120.9     .11       0
Bank Sta=4977.57,5021.1
XS Rating Curve= 0 ,0
Exp/Cntr=0.3,0.1

Type RM Length L Ch R = 1 ,1336    ,385,385,385
BEGIN DESCRIPTION:
Mapping XS 65fca118
END DESCRIPTION:
XS GIS Cut Line= 3
      3696663.63     10223920.67      3696181.87     10222397.25
       3695756.5     10222379.89
#Sta/Elev= 30
  3492.6  340.42  3712.4  332.94  3743.9  333.13  3762.7  331.56  3862.3  330.56
  3932.7  328.15  3996.8  330.25  4023.8  329.81    4069   328.5  4093.7  325.82
    4111  327.61  4211.6  328.11  4540.2  327.24  4771.7  327.99  4852.7   326.7
  4866.1  327.72    4885  326.82  4890.2  327.92    4929  326.88  4949.6  328.11
  4981.5   326.5  5000.1   319.5  5004.9   319.5  5019.5  325.83  5033.4  326.62
  5033.9  326.68  5121.2  329.48  5219.9   332.7  5314.6  336.72  5516.1  339.53
#Mann= 9 ,-1 , 0
  3492.6     .11       0  3762.7     .15       0  4211.6     .11       0
  4540.2     .15       0  4981.5     .09       0  5033.4     .12       0
  5033.9     .11       0  5121.2     .15       0  5219.9     .11       0
Bank Sta=4981.5,5033.4
XS Rating Curve= 0 ,0
Exp/Cntr=0.3,0.1

Type RM Length L Ch R = 1 ,951     ,517,517,517
BEGIN DESCRIPTION:
Mapping XS e7cb5853
END DESCRIPTION:
XS GIS Cut Line= 3
      3696698.36     10223734.06      3696529.09     10222245.34
      3695765.22     10222223.64
#Sta/Elev= 30
  3664.9  334.66  3750.2  331.73  3882.1  329.74  3919.5  328.11  4130.5  328.19
  4191.2  328.21  4281.8   326.8    4302  324.95  4330.2  327.67  4362.4  327.71
  4822.8  324.71    4952  325.88    4957  322.76  4986.4  324.63  4996.4  322.33
  5004.1  318.72  5008.9  318.72  5030.4324.3859  5036.5  325.76  5097.1  324.86
  5120.8  325.82  5194.5  325.11  5284.5   326.4  5304.5  325.45  5314.5  326.41
  5334.5  325.84  5554.6  329.29  5633.8   332.1  5732.4  334.72  5927.4  340.54
#Mann= 11 ,-1 , 0
  3664.9     .11       0  3750.2     .15       0  3882.1     .11       0
  4130.5     .15       0  4191.2     .11       0  4822.8     .15       0
  4986.4     .09       0  5030.4     .15       0  5120.8     .11       0
  5633.8     .15       0  5732.4     .11       0
Bank Sta=4986.4,5030.4
XS Rating Curve= 0 ,0
Exp/Cntr=0.3,0.1

Type RM Length L Ch R = 1 ,434     ,0,0,0
BEGIN DESCRIPTION:
CCLC 094 1.0
END DESCRIPTION:
XS GIS Cut Line= 3
       3696746.1     10223742.75      3696976.14     10222236.66
      3695878.05     10222084.75
#Sta/Elev= 30
  3324.3  333.87  3428.4  331.41  3606.8  328.16  4135.3  325.82  4540.9  325.93
  4681.5  325.65  4695.2  323.85  4701.8   319.1  4711.9  323.11    4722  324.78
  4742.2  321.01  4758.6  326.39    4813  323.92  4876.4  326.51  4906.7  319.72
  4928.5  323.23  4977.4  324.55  4982.2 321.917  4997.9  316.35  5002.8  316.35
  5007.7  319.43  5017.7  322.04    5048  325.02  5075.4  325.29  5300.4  326.01
  5401.4  324.65  5744.6  329.91  5764.8  331.64  5883.4  334.04  5956.4  336.14
#Mann= 8 ,-1 , 0
  3324.3     .11       0  3428.4     .15       0  3606.8     .11       0
  4540.9     .15       0  4982.2     .09       0  5017.7     .15       0
  5075.4     .11       0  5883.4     .15       0
Bank Sta=4982.2,5017.7
XS Rating Curve= 0 ,0
Exp/Cntr=0.3,0.1

Chan Stop Cuts=-1
Use User Specified Reach Order=0
Composite Channel Slope=5