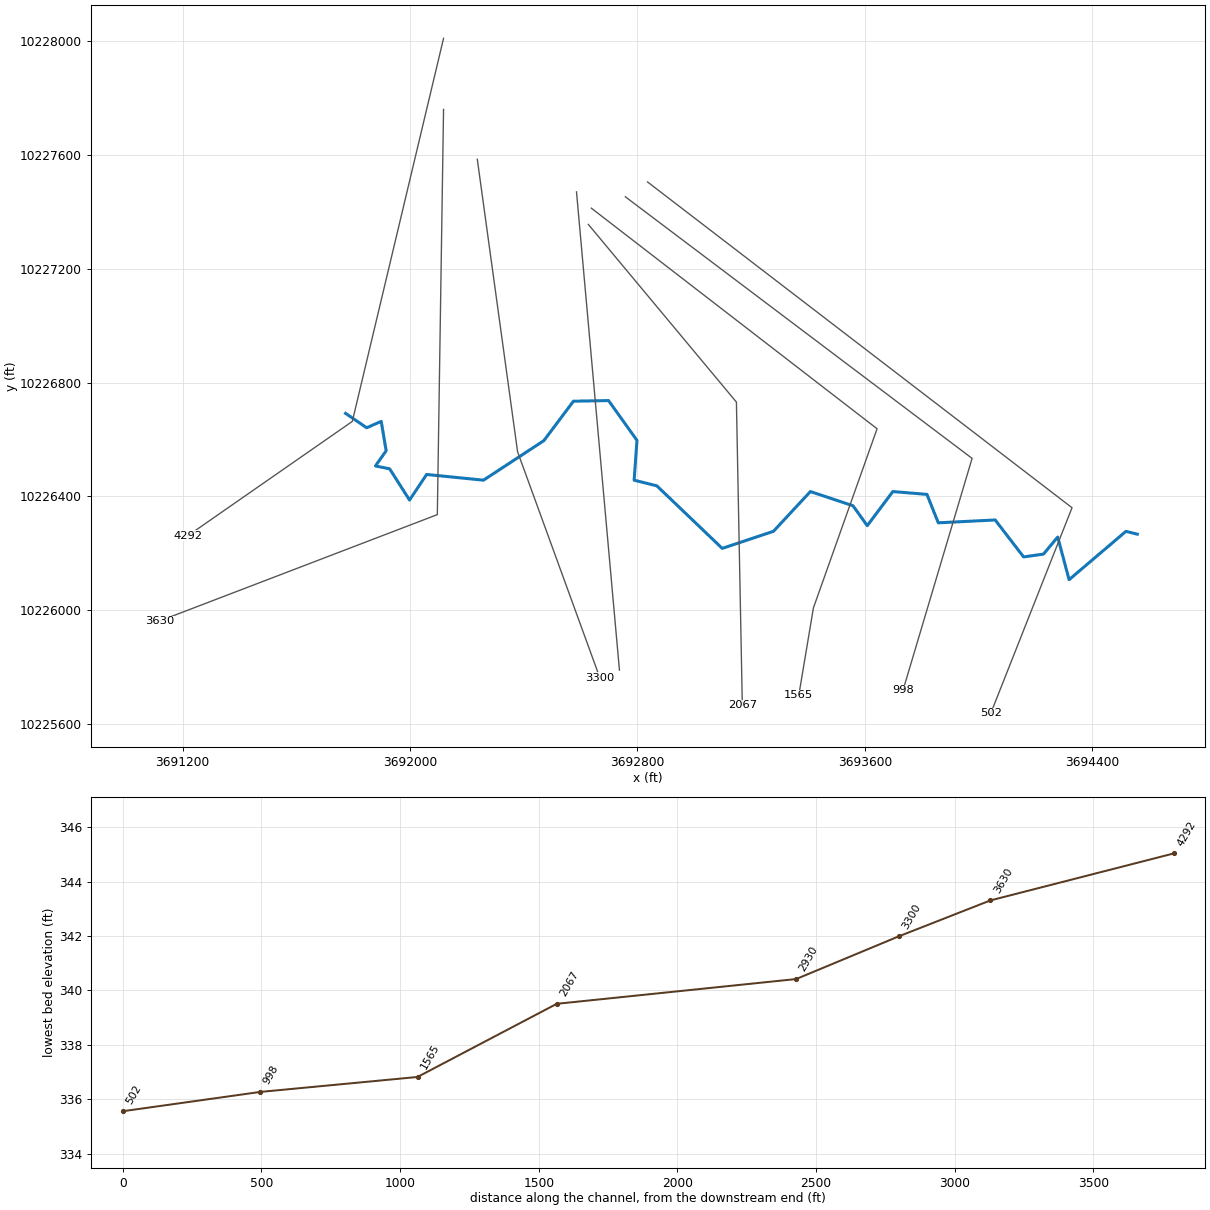
--- CCLC 095.prj (project) ---

Proj Title=CCLC 095 Base Level Engineering
Current Plan=p01
Default Exp/Contr=0.3,0.1
English Units
Geom File=g01
Flow File=f01
Flow File=f02
Plan File=p01
Y Axis Title=Elevation
X Axis Title(PF)=Main Channel Distance
X Axis Title(XS)=Station
BEGIN DESCRIPTION:
CCLC 095
END DESCRIPTION:
DSS Export Rating Curves= 0
DSS Export Rating Curve Sorted= 0
DSS Export Volume Flow Curves= 0
DXF OffsetX= 0
DXF OffsetY= 0
DXF ScaleX= 1
DXF ScaleY= 10

--- CCLC 095.p01 (plan) ---

Plan Title=Multiple Run
Short Identifier=Multiple
Geom File=g01
Flow File=f01
Subcritical Flow
K Sum by GR= 0
Std Step Tol= 0.01
Critical Tol= 0.01
Num of Std Step Trials= 20
Max Error Tol= 0.3
Flow Tol Ratio= 0.001
Split Flow NTrial= 30
Split Flow Tol= 0.02
Split Flow Ratio= 0.02
Log Output Level= 0
Friction Slope Method= 1
Unsteady Friction Slope Method= 2
Unsteady Bridges Friction Slope Method= 1
Parabolic Critical Depth
Global Vel Dist=  1 , 1 , 1
Global Log Level= 0
CheckData=True
Encroach Param= -1, 0, 0, 0
BEGIN DESCRIPTION:
Multiple Run
END DESCRIPTION:

--- CCLC 095.f01 (steady flow) ---

Flow Title=Multiple
Program Version=4.10
Number of Profiles= 7
Profile Names=10-year,25-year,50-year,1pct_min,100-year,1pct_plu,500-year
River Rch & RM=CCLC 095,Reach-1         ,4292
     535     716     959     423    1277    3856    2337
Boundary for River Rch & Prof#=CCLC 095,Reach-1         , 1
Up Type= 0
Dn Type= 3
Dn Slope=0.005
Boundary for River Rch & Prof#=CCLC 095,Reach-1         , 2
Up Type= 0
Dn Type= 3
Dn Slope=0.005
Boundary for River Rch & Prof#=CCLC 095,Reach-1         , 3
Up Type= 0
Dn Type= 3
Dn Slope=0.005
Boundary for River Rch & Prof#=CCLC 095,Reach-1         , 4
Up Type= 0
Dn Type= 3
Dn Slope=0.005
Boundary for River Rch & Prof#=CCLC 095,Reach-1         , 5
Up Type= 0
Dn Type= 3
Dn Slope=0.005
Boundary for River Rch & Prof#=CCLC 095,Reach-1         , 6
Up Type= 0
Dn Type= 3
Dn Slope=0.005
Boundary for River Rch & Prof#=CCLC 095,Reach-1         , 7
Up Type= 0
Dn Type= 3
Dn Slope=0.005
DSS Import GetInterval= 0
DSS Import GetPeak= 0
DSS Import FillOption= 0

--- CCLC 095.f02 (steady flow) ---

Flow Title=Orig_BLE_Flows
Program Version=4.10
Number of Profiles= 7
Profile Names=10-year,25-year,50-year,1pct_min,100-year,1pct_plu,500-year
River Rch & RM=CCLC 095,Reach-1         ,4292
     535     702     834     325     982    2965    1359
Boundary for River Rch & Prof#=CCLC 095,Reach-1         , 1
Up Type= 0
Dn Type= 3
Dn Slope=0.005
Boundary for River Rch & Prof#=CCLC 095,Reach-1         , 2
Up Type= 0
Dn Type= 3
Dn Slope=0.005
Boundary for River Rch & Prof#=CCLC 095,Reach-1         , 3
Up Type= 0
Dn Type= 3
Dn Slope=0.005
Boundary for River Rch & Prof#=CCLC 095,Reach-1         , 4
Up Type= 0
Dn Type= 3
Dn Slope=0.005
Boundary for River Rch & Prof#=CCLC 095,Reach-1         , 5
Up Type= 0
Dn Type= 3
Dn Slope=0.005
Boundary for River Rch & Prof#=CCLC 095,Reach-1         , 6
Up Type= 0
Dn Type= 3
Dn Slope=0.005
Boundary for River Rch & Prof#=CCLC 095,Reach-1         , 7
Up Type= 0
Dn Type= 3
Dn Slope=0.005
DSS Import GetInterval= 0
DSS Import GetPeak= 0
DSS Import FillOption= 0

--- CCLC 095.g01 (geometry) ---

Geom Title=Existing Conditions
Program Version=4.10

River Reach=CCLC 095        ,Reach-1
Reach XY= 30
      3691773.23     10226691.84      3691847.34     10226641.23
      3691898.59     10226663.55      3691915.95     10226560.23
      3691878.23     10226506.84      3691928.23     10226496.84
      3691998.23     10226386.84      3692058.23     10226476.84
      3692258.23     10226456.84      3692470.56     10226595.77
      3692574.71     10226734.63      3692698.23     10226736.84
      3692798.23     10226596.84      3692788.23     10226456.84
      3692868.23     10226436.84      3693098.23     10226216.84
      3693278.23     10226276.84      3693408.23     10226416.84
      3693558.23     10226366.84      3693608.23     10226296.84
      3693698.23     10226416.84      3693818.23     10226406.84
      3693858.23     10226306.84      3694058.23     10226316.84
      3694158.23     10226186.84      3694228.23     10226196.84
      3694278.23     10226256.84      3694318.23     10226106.84
      3694518.23     10226276.84      3694558.23     10226266.84

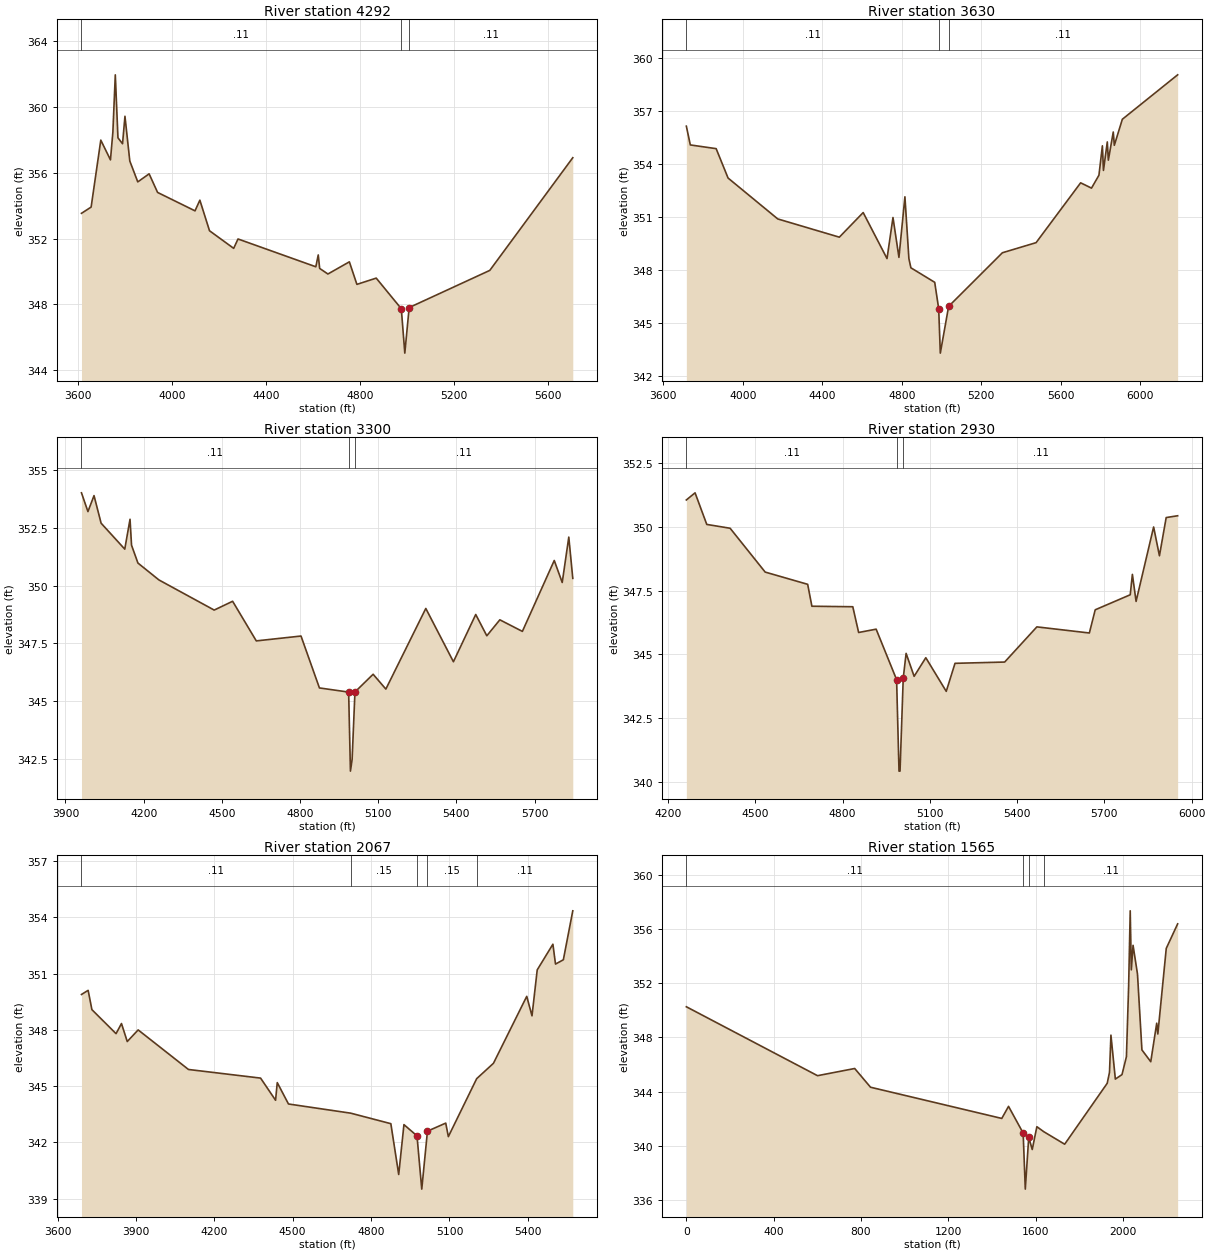
Type RM Length L Ch R = 1 ,4292    ,662,662,662
BEGIN DESCRIPTION:
CCLC 095 4.0
END DESCRIPTION:
XS GIS Cut Line= 3
      3692117.85     10228011.06      3691796.92     10226663.55
      3691217.85     10226261.07
#Sta/Elev= 30
  3614.8  353.54  3655.9  353.92    3697  357.99  3738.1  356.79  3748.4  358.48
  3758.7  361.96    3770  358.13  3789.5  357.77  3799.8  359.44  3820.4  356.72
  3854.3  355.45  3902.6  355.94  3938.6  354.81  4097.9  353.69  4118.5  354.34
  4159.6  352.48  4262.4  351.41  4280.8  351.98  4611.9  350.29  4622.2  351.01
  4628.2  350.19  4663.3  349.85  4754.6  350.59  4786.7  349.22  4868.9   349.6
  4975.6  347.74  4990.5  345.04    5009  347.81  5352.1  350.07  5705.2  356.92
#Mann= 3 , 0 , 0
  3614.8     .11       0  4975.6     .06       0    5009     .11       0
Bank Sta=4975.6,5009
XS Rating Curve= 0 ,0
Exp/Cntr=0.3,0.1

Type RM Length L Ch R = 1 ,3630    ,330,330,330
BEGIN DESCRIPTION:
CCLC 095 3.0
END DESCRIPTION:
XS GIS Cut Line= 3
      3692117.85     10227761.09      3692095.93     10226335.62
      3691117.84     10225961.07
#Sta/Elev= 30
  3715.6  356.13  3735.6  355.07  3865.6  354.86  3925.6   353.2  4175.7  350.89
  4485.7  349.86  4605.7  351.25  4725.7  348.65  4755.7  350.97  4785.7  348.72
  4815.8  352.14  4835.8  348.65  4845.8  348.13  4965.8  347.31  4985.8  345.82
    4994  343.31  5035.8  345.95  5306.5  348.98    5476  349.55  5700.3  352.93
    5755  352.63  5792.4  353.36  5809.8  355.02  5815.1  353.63  5834.5  355.24
  5839.8  354.21  5864.5   355.8  5869.9  355.05  5910.2  356.52  6188.6  359.03
#Mann= 3 , 0 , 0
  3715.6     .11       0  4985.8     .06       0  5035.8     .11       0
Bank Sta=4985.8,5035.8
XS Rating Curve= 0 ,0
Exp/Cntr=0.3,0.1

Type RM Length L Ch R = 1 ,3300    ,370,370,370
BEGIN DESCRIPTION:
CCLC 095 2.0
END DESCRIPTION:
XS GIS Cut Line= 3
      3692236.55     10227585.63      3692378.23     10226556.84
      3692667.84     10225761.11
#Sta/Elev= 30
  3961.5     354  3986.3  353.19  4009.6  353.88  4036.8  352.69  4127.6  351.57
  4147.8  352.86  4153.6  351.74  4178.1  350.97  4258.8  350.24  4470.8  348.94
  4541.5  349.32  4632.3  347.61  4803.9  347.82  4874.6  345.58 4986.67345.4004
  4993.6  341.99    5000  342.49 5010.91345.4046  5080.6  346.17  5129.5  345.53
  5282.8  349.01  5388.8  346.71  5474.4  348.75  5516.9  347.83  5566.9  348.52
  5653.4  348.02  5775.7  351.08  5806.3  350.13  5831.5  352.09  5846.8  350.31
#Mann= 3 , 0 , 0
  3961.5     .11       0 4986.67     .06       0 5010.91     .11       0
Bank Sta=4986.67,5010.91
XS Rating Curve= 0 ,0
Exp/Cntr=0.3,0.1

Type RM Length L Ch R = 1 ,2930    ,863,863,863
BEGIN DESCRIPTION:
Mapping XS 466cdd32
END DESCRIPTION:
XS GIS Cut Line= 2
      3692585.52     10227470.99      3692736.55     10225788.76
#Sta/Elev= 30
  4262.9  351.06  4292.9  351.34  4333.1   350.1  4413.4  349.95  4533.9  348.23
    4680  347.75  4694.5  346.89  4835.1  346.87  4855.2  345.86  4915.4  345.99
  4985.7  344.01    4994  340.42  4997.5  340.42  5008.5344.0663  5018.4  345.04
    5046  344.14  5086.1  344.87  5156.4  343.55  5186.5  344.65  5357.2   344.7
  5467.9  346.08  5648.4  345.84  5668.5  346.75  5788.9  347.34  5796.3  348.14
    5809  347.08  5869.3     350  5889.3  348.87  5912.5  350.37  5951.9  350.44
#Mann= 3 , 0 , 0
  4262.9     .11       0  4985.7     .06       0  5008.5     .11       0
Bank Sta=4985.7,5008.5
XS Rating Curve= 0 ,0
Exp/Cntr=0.3,0.1

Type RM Length L Ch R = 1 ,2067    ,502,502,502
BEGIN DESCRIPTION:
Mapping XS 4e425849
END DESCRIPTION:
XS GIS Cut Line= 3
      3692627.16     10227356.47      3693148.01     10226731.45
      3693168.82     10225664.95
#Sta/Elev= 30
  3691.7  349.89  3717.2  350.11  3731.6  349.08    3824   347.8  3844.8  348.34
  3866.9  347.38  3908.6     348  4101.2  345.89  4377.2  345.43  4434.5  344.25
    4441  345.19  4483.9  344.05  4722.2  343.56  4875.7     343  4905.8  340.29
  4925.8  342.95  4975.8  342.35    4994  339.51  5015.8   342.6  5085.8  343.03
  5095.8  342.31  5204.2   345.4  5268.4  346.22  5395.8  349.79  5415.9  348.75
  5435.9   351.2  5495.9  352.57  5505.9  351.51  5535.9  351.74    5572  354.35
#Mann= 5 ,-1 , 0
  3691.7     .11       0  4722.2     .15       0  4975.8     .09       0
  5015.8     .15       0  5204.2     .11       0
Bank Sta=4975.8,5015.8
XS Rating Curve= 0 ,0
Exp/Cntr=0.3,0.1

Type RM Length L Ch R = 1 ,1565    ,567,567,567
BEGIN DESCRIPTION:
Mapping XS 5e42ef7d
END DESCRIPTION:
XS GIS Cut Line= 4
       3692637.6     10227413.74       3693642.8      10226637.7
      3693418.85     10226007.49      3693367.36     10225699.59
#Sta/Elev= 30
       0  350.26     601  345.18   771.3  345.71   843.8  344.33  1445.2  342.03
  1476.1  342.92  1543.1  340.95  1552.9  336.82  1568.6  340.64  1584.7  339.74
  1605.9  341.42  1637.8  341.05  1733.3  340.13  1928.2  344.62  1938.7  345.43
  1945.2  348.17  1965.5  344.93  1995.9  345.26  2016.2  346.58  2026.4  351.81
  2033.6  357.33  2038.6  352.98  2046.6  354.79  2066.9  352.67  2087.2  347.08
  2127.7  346.21    2155  349.05  2160.1  348.25  2198.7  354.56  2250.9  356.37
#Mann= 4 ,-1 , 0
       0     .11       0  1543.1     .09       0  1568.6     .15       0
  1637.8     .11       0
Bank Sta=1543.1,1568.6
XS Rating Curve= 0 ,0
Exp/Cntr=0.3,0.1

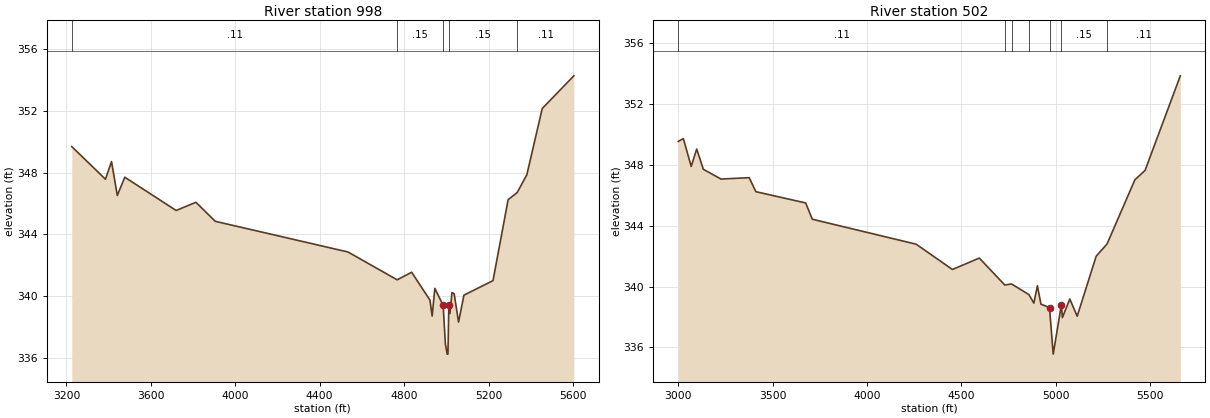
Type RM Length L Ch R = 1 ,998     ,496,496,496
BEGIN DESCRIPTION:
Mapping XS c26bd1aa
END DESCRIPTION:
XS GIS Cut Line= 3
      3692757.43     10227453.64      3693977.01     10226533.53
      3693733.96      10225717.6
#Sta/Elev= 30
  3225.3  349.68  3384.9  347.57  3413.7  348.71  3441.1  346.52  3476.5   347.7
    3720  345.55  3813.7  346.08  3905.3  344.85  4533.9  342.87  4767.4  341.07
  4835.8  341.56  4922.6  339.76    4933  338.73  4945.7  340.52  4985.2  339.42
  4995.6  336.94  5004.3  336.27  5007.8  336.27    5012  339.47  5017.2  338.89
  5026.9  340.25  5037.3  340.17  5058.2  338.34  5083.6  340.08  5221.4  341.02
    5293  346.25  5335.9  346.71  5381.7  347.86  5454.7  352.14  5604.4  354.25
#Mann= 5 ,-1 , 0
  3225.3     .11       0  4767.4     .15       0  4985.2     .09       0
    5012     .15       0  5335.9     .11       0
Bank Sta=4985.2,5012
XS Rating Curve= 0 ,0
Exp/Cntr=0.3,0.1

Type RM Length L Ch R = 1 ,502     ,0,0,0
BEGIN DESCRIPTION:
CCLC 095 1.0
END DESCRIPTION:
XS GIS Cut Line= 3
      3692835.51     10227505.76      3694328.57     10226359.92
      3694042.68     10225636.53
#Sta/Elev= 30
  2999.7  349.53  3026.8  349.72  3068.4  347.89  3097.5  349.03  3132.8   347.7
  3226.2  347.06  3375.7  347.15  3411.1  346.23  3674.8  345.49  3710.2  344.42
  4260.4  342.78  4452.3  341.12  4594.8  341.87  4729.7   340.1  4765.4  340.17
  4857.6  339.47  4883.8  338.91  4902.4  340.05  4921.3  338.84  4966.6  338.62
  4986.3  335.56  5029.5   338.8  5034.9  337.96  5074.1  339.18  5113.3  338.05
  5213.9  341.99  5271.7   342.8  5418.9  347.01    5473  347.63  5659.6  353.84
#Mann= 7 ,-1 , 0
  2999.7     .11       0  4729.7     .15       0  4765.4     .11       0
  4857.6     .15       0  4966.6     .06       0  5029.5     .15       0
  5271.7     .11       0
Bank Sta=4966.6,5029.5
XS Rating Curve= 0 ,0
Exp/Cntr=0.3,0.1

Chan Stop Cuts=-1
Use User Specified Reach Order=0
Composite Channel Slope=5