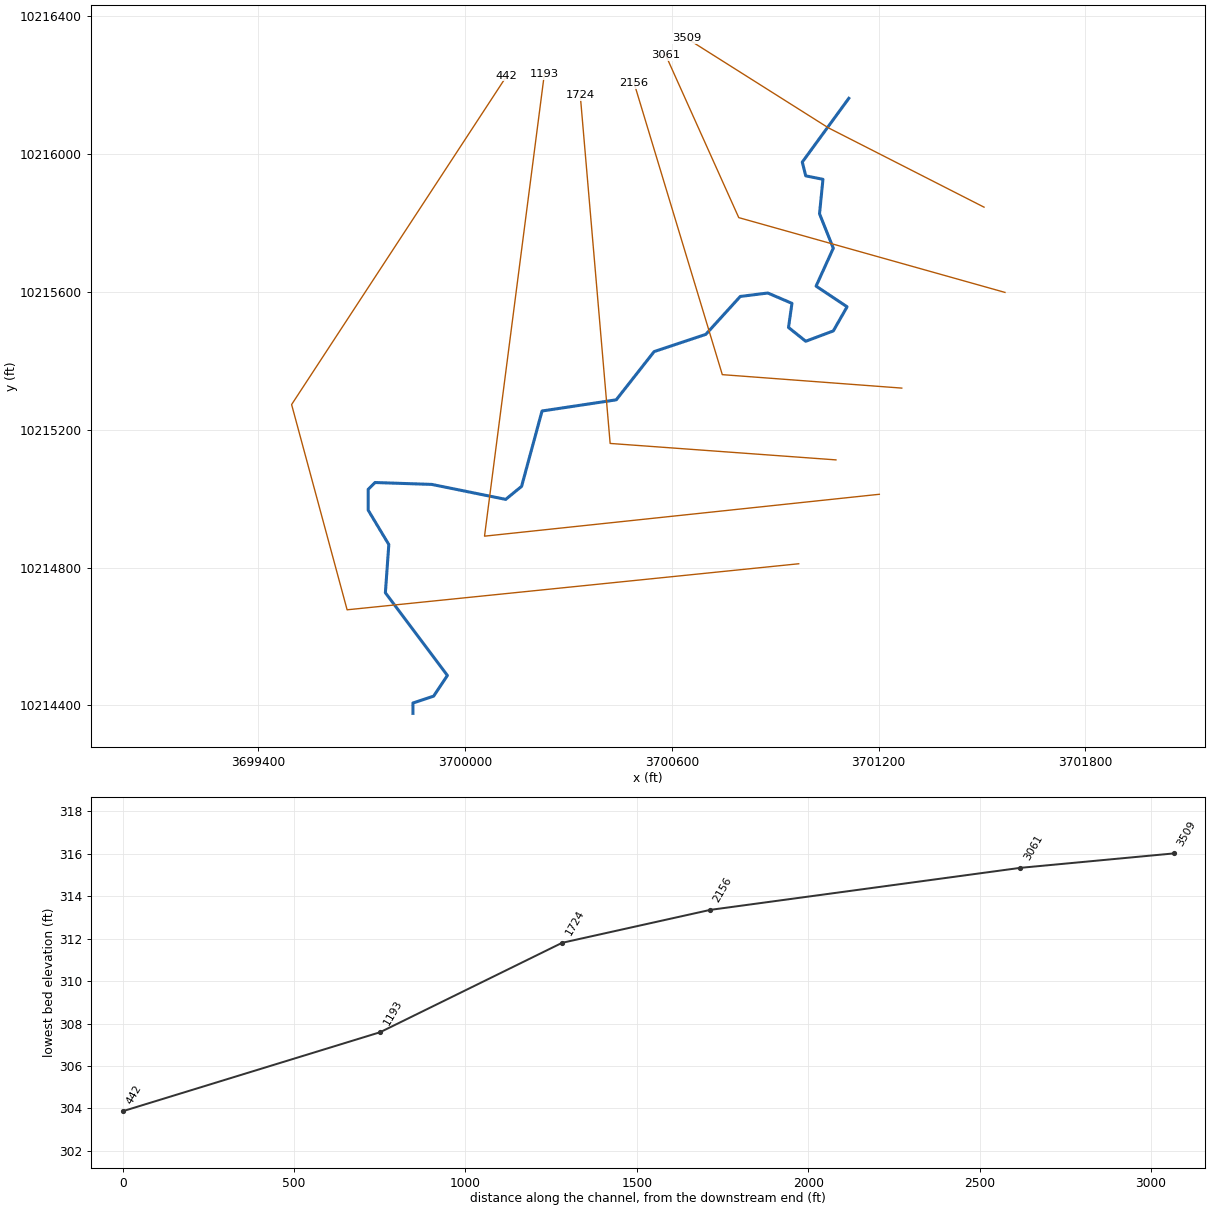
--- CCLC 096.prj (project) ---

Proj Title=CCLC 096 Base Level Engineering
Current Plan=p01
Default Exp/Contr=0.3,0.1
English Units
Geom File=g01
Flow File=f01
Flow File=f02
Plan File=p01
Y Axis Title=Elevation
X Axis Title(PF)=Main Channel Distance
X Axis Title(XS)=Station
BEGIN DESCRIPTION:
CCLC 096
END DESCRIPTION:
DSS Export Rating Curves= 0
DSS Export Rating Curve Sorted= 0
DSS Export Volume Flow Curves= 0
DXF OffsetX= 0
DXF OffsetY= 0
DXF ScaleX= 1
DXF ScaleY= 10

--- CCLC 096.p01 (plan) ---

Plan Title=Multiple Run
Short Identifier=Multiple
Geom File=g01
Flow File=f01
Subcritical Flow
K Sum by GR= 0
Std Step Tol= 0.01
Critical Tol= 0.01
Num of Std Step Trials= 20
Max Error Tol= 0.3
Flow Tol Ratio= 0.001
Split Flow NTrial= 30
Split Flow Tol= 0.02
Split Flow Ratio= 0.02
Log Output Level= 0
Friction Slope Method= 1
Unsteady Friction Slope Method= 2
Unsteady Bridges Friction Slope Method= 1
Parabolic Critical Depth
Global Vel Dist=  1 , 1 , 1
Global Log Level= 0
CheckData=True
Encroach Param= -1, 0, 0, 0
BEGIN DESCRIPTION:
Multiple Run
END DESCRIPTION:

--- CCLC 096.f01 (steady flow) ---

Flow Title=Multiple
Program Version=4.10
Number of Profiles= 7
Profile Names=10-year,25-year,50-year,1pct_min,100-year,1pct_plu,500-year
River Rch & RM=CCLC 096,Reach-1         ,3509
     535     717     963     425    1284    3878    2363
Boundary for River Rch & Prof#=CCLC 096,Reach-1         , 1
Up Type= 0
Dn Type= 3
Dn Slope=0.005
Boundary for River Rch & Prof#=CCLC 096,Reach-1         , 2
Up Type= 0
Dn Type= 3
Dn Slope=0.005
Boundary for River Rch & Prof#=CCLC 096,Reach-1         , 3
Up Type= 0
Dn Type= 3
Dn Slope=0.005
Boundary for River Rch & Prof#=CCLC 096,Reach-1         , 4
Up Type= 0
Dn Type= 3
Dn Slope=0.005
Boundary for River Rch & Prof#=CCLC 096,Reach-1         , 5
Up Type= 0
Dn Type= 3
Dn Slope=0.005
Boundary for River Rch & Prof#=CCLC 096,Reach-1         , 6
Up Type= 0
Dn Type= 3
Dn Slope=0.005
Boundary for River Rch & Prof#=CCLC 096,Reach-1         , 7
Up Type= 0
Dn Type= 3
Dn Slope=0.005
DSS Import GetInterval= 0
DSS Import GetPeak= 0
DSS Import FillOption= 0

--- CCLC 096.f02 (steady flow) ---

Flow Title=Orig_BLE_Flows
Program Version=4.10
Number of Profiles= 7
Profile Names=10-year,25-year,50-year,1pct_min,100-year,1pct_plu,500-year
River Rch & RM=CCLC 096,Reach-1         ,3509
     535     703     837     327     988    2983    1374
Boundary for River Rch & Prof#=CCLC 096,Reach-1         , 1
Up Type= 0
Dn Type= 3
Dn Slope=0.005
Boundary for River Rch & Prof#=CCLC 096,Reach-1         , 2
Up Type= 0
Dn Type= 3
Dn Slope=0.005
Boundary for River Rch & Prof#=CCLC 096,Reach-1         , 3
Up Type= 0
Dn Type= 3
Dn Slope=0.005
Boundary for River Rch & Prof#=CCLC 096,Reach-1         , 4
Up Type= 0
Dn Type= 3
Dn Slope=0.005
Boundary for River Rch & Prof#=CCLC 096,Reach-1         , 5
Up Type= 0
Dn Type= 3
Dn Slope=0.005
Boundary for River Rch & Prof#=CCLC 096,Reach-1         , 6
Up Type= 0
Dn Type= 3
Dn Slope=0.005
Boundary for River Rch & Prof#=CCLC 096,Reach-1         , 7
Up Type= 0
Dn Type= 3
Dn Slope=0.005
DSS Import GetInterval= 0
DSS Import GetPeak= 0
DSS Import FillOption= 0

--- CCLC 096.g01 (geometry) ---

Geom Title=Existing Conditions
Program Version=4.10

River Reach=CCLC 096        ,Reach-1
Reach XY= 30
      3701113.23     10216161.84      3700978.23     10215976.84
      3700988.23     10215936.84      3701038.23     10215926.84
      3701028.23     10215826.84      3701068.23     10215726.84
      3701018.23     10215616.84      3701108.23     10215556.84
      3701068.23     10215486.84      3700988.23     10215456.84
      3700938.23     10215496.84      3700948.23     10215566.84
      3700878.23     10215596.84      3700798.23     10215586.84
      3700698.23     10215476.84      3700548.23     10215426.84
      3700438.23     10215286.84      3700222.93     10215254.44
      3700163.54     10215035.67      3700117.46     10214997.92
      3699902.73     10215041.35      3699738.23     10215046.84
      3699718.23     10215026.84      3699718.23     10214966.84
      3699778.23     10214866.84      3699768.23     10214726.84
      3699948.23     10214486.84      3699908.23     10214426.84
      3699848.23     10214406.84      3699848.23     10214376.84

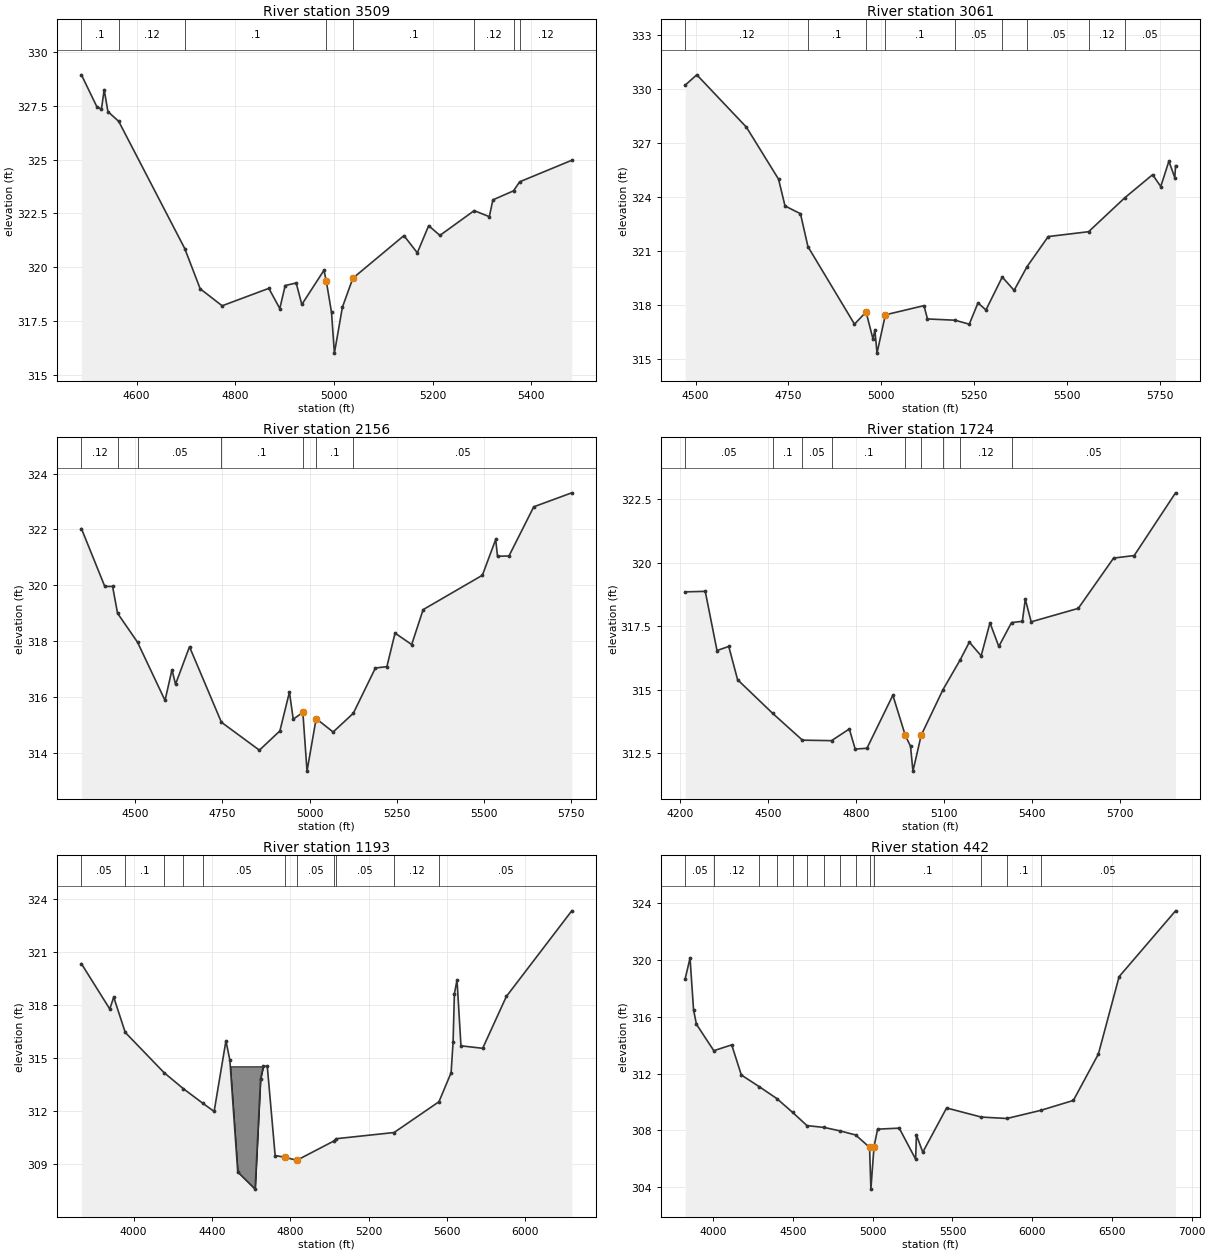
Type RM Length L Ch R = 1 ,3509    ,448,448,448
BEGIN DESCRIPTION:
CCLC 096 3.0
END DESCRIPTION:
XS GIS Cut Line= 3
      3701505.69     10215846.01      3701054.26     10216076.07
      3700642.73     10216335.98
#Sta/Elev= 30
  4488.4  328.94  4519.6  327.46  4528.9  327.34  4534.5  328.25  4542.1  327.23
  4563.9  326.78  4697.7  320.87    4729     319  4773.5  318.21  4868.1  319.02
  4890.3  318.08  4901.2  319.15  4923.5  319.27  4934.9  318.27  4979.8  319.86
 4984.44319.3648  4995.1   317.9  5000.9  316.01  5017.1  318.14  5038.3  319.49
  5141.8  321.47  5168.9  320.67  5191.9  321.93  5214.7  321.48  5284.1  322.63
  5314.8  322.35    5322  323.13  5363.8  323.55  5376.3  323.97  5481.8  324.97
#Mann= 8 ,-1 , 0
  4488.4      .1       0  4563.9     .12       0  4697.7      .1       0
 4984.44     .07       0  5038.3      .1       0  5284.1     .12       0
  5363.8      .1       0  5376.3     .12       0
Bank Sta=4984.44,5038.3
XS Rating Curve= 0 ,0
Exp/Cntr=0.3,0.1

Type RM Length L Ch R = 1 ,3061    ,905,905,905
BEGIN DESCRIPTION:
Mapping XS 0cdef884
END DESCRIPTION:
XS GIS Cut Line= 3
      3701566.46     10215598.62      3700793.85     10215815.65
      3700581.79     10216287.36
#Sta/Elev= 30
  4472.1  330.23  4503.3   330.8  4636.8  327.89  4723.3     325  4740.7  323.51
  4782.3  323.08  4802.4  321.25  4927.7  316.94  4958.8  317.62  4977.4  316.12
  4982.6  316.61  4988.3  315.33  5010.8  317.46  5114.7  317.97  5124.1  317.23
    5198  317.16  5236.6  316.94  5260.1  318.12  5281.5  317.73  5325.4  319.56
  5357.3  318.82  5391.9  320.13  5449.1  321.81  5557.8  322.08  5655.4  323.97
  5730.1  325.25    5752  324.59  5773.9     326  5789.8  325.08  5791.8  325.75
#Mann= 9 ,-1 , 0
  4472.1     .12       0  4802.4      .1       0  4958.8     .07       0
  5010.8      .1       0    5198     .05       0  5325.4      .1       0
  5391.9     .05       0  5557.8     .12       0  5655.4     .05       0
Bank Sta=4958.8,5010.8
XS Rating Curve= 0 ,0
Exp/Cntr=0.3,0.1

Type RM Length L Ch R = 1 ,2156    ,432,432,432
BEGIN DESCRIPTION:
Mapping XS fa09c99b
END DESCRIPTION:
XS GIS Cut Line= 3
      3701266.96     10215320.86       3700746.1     10215359.92
      3700490.04     10216206.21
#Sta/Elev= 30
  4345.5  322.03  4412.5  319.96  4434.9  319.96  4449.1     319  4506.6  317.96
  4585.3  315.88  4605.3  316.98  4615.4  316.46  4655.5   317.8    4747   315.1
    4856   314.1  4914.8  314.79  4942.2  316.18    4953  315.21  4980.7  315.45
  4992.6  313.35  5018.8  315.23  5067.5  314.75  5125.4  315.42  5188.7  317.04
  5221.7  317.09  5245.1  318.29  5292.8  317.88  5325.7  319.13  5495.6  320.36
  5533.8  321.64    5539  321.04  5571.9  321.05    5643  322.81    5752  323.31
#Mann= 7 ,-1 , 0
  4345.5     .12       0  4449.1      .1       0  4506.6     .05       0
    4747      .1       0  4980.7     .07       0  5018.8      .1       0
  5125.4     .05       0
Bank Sta=4980.7,5018.8
XS Rating Curve= 0 ,0
Exp/Cntr=0.3,0.1

Type RM Length L Ch R = 1 ,1724    ,531,531,531
BEGIN DESCRIPTION:
Mapping XS 8c9e5d48
END DESCRIPTION:
XS GIS Cut Line= 3
      3701075.94     10215112.53      3700420.58     10215160.27
      3700333.78     10216171.56
#Sta/Elev= 30
  4217.5  318.86  4285.8  318.88  4325.9  316.55    4366  316.71  4396.1   315.4
  4516.2  314.07  4617.2  313.02  4716.4     313  4777.1  313.46  4797.1  312.67
  4837.2   312.7  4925.6  314.79  4967.9  313.21  4985.8  312.78  4994.1   311.8
 5022.17313.2116  5096.5  315.01  5154.6  316.17  5186.5  316.88  5226.7  316.34
  5256.8  317.64  5286.9  316.71  5330.2  317.65  5367.2   317.7  5377.2  318.57
  5397.3  317.68  5557.9  318.21  5678.3  320.19  5748.6  320.29  5889.6  322.76
#Mann= 9 ,-1 , 0
  4217.5     .05       0  4516.2      .1       0  4617.2     .05       0
  4716.4      .1       0  4967.9     .07       0 5022.17      .1       0
  5096.5     .05       0  5154.6     .12       0  5330.2     .05       0
Bank Sta=4967.9,5022.17
XS Rating Curve= 0 ,0
Exp/Cntr=0.3,0.1

Type RM Length L Ch R = 1 ,1193    ,751,751,751
BEGIN DESCRIPTION:
CCLC 096 2.0
END DESCRIPTION:
XS GIS Cut Line= 3
      3701201.86      10215012.7        3700056.     10214891.17
      3700229.61      10216232.3
#Sta/Elev= 30
  3733.5  320.33  3878.3  317.77  3898.4  318.44  3957.2  316.45    4155  314.18
  4253.8  313.27  4352.7  312.45  4411.3  311.98  4471.6  315.97  4491.7  314.88
    4532  308.56  4620.7  307.59  4648.6  313.83  4662.7  314.53  4682.8  314.54
    4723  309.49  4773.3  309.39  4833.6  309.22    5023  310.31    5035  310.44
  5330.6  310.79  5559.8  312.53  5621.8  314.17  5631.9   315.9  5638.6  318.63
    5652  319.41  5672.2  315.69  5783.1  315.55  5904.1  318.48  6238.1  323.32
#Mann= 11 ,-1 , 0
  3733.5     .05       0  3957.2      .1       0    4155     .12       0
  4253.8      .1       0  4352.7     .05       0  4773.3     .04       0
  4833.6     .05       0    5023      .1       0    5035     .05       0
  5330.6     .12       0  5559.8     .05       0
#Block Obstruct= 1 ,-1
 4494.57 4671.58  314.53
Bank Sta=4773.3,4833.6
XS Rating Curve= 0 ,0
Exp/Cntr=0.3,0.1

Type RM Length L Ch R = 1 ,442     ,0,0,0
BEGIN DESCRIPTION:
CCLC 096 1.0
END DESCRIPTION:
XS GIS Cut Line= 4
      3700967.87     10214811.07      3699657.17     10214677.43
       3699496.1     10215273.12      3700120.51     10216227.07
#Sta/Elev= 30
  3824.3  318.68  3854.5  320.13  3876.6  316.48  3894.7  315.47  4003.6  313.61
  4115.8  314.02  4176.1   311.9    4287  311.09  4398.9  310.24  4497.7  309.27
  4587.6  308.34  4695.4  308.21  4794.3  307.97  4893.1  307.68  4980.3  306.81
  4988.6  303.87    5008306.8332  5030.5  308.09  5166.3  308.16    5269  305.98
  5274.2  307.68    5314  306.47  5463.2  309.58  5680.9  308.94  5841.2  308.84
  6052.9  309.41  6258.3  310.11    6415  313.37  6545.2  318.82    6899  323.45
#Mann= 14 ,-1 , 0
  3824.3     .05       0  4003.6     .12       0    4287     .05       0
  4398.9     .12       0  4497.7      .1       0  4587.6     .12       0
  4695.4     .05       0  4794.3     .12       0  4893.1      .1       0
  4980.3     .07       0    5008      .1       0  5680.9     .05       0
  5841.2      .1       0  6052.9     .05       0
Bank Sta=4980.3,5008
XS Rating Curve= 0 ,0
Exp/Cntr=0.3,0.1

Chan Stop Cuts=-1
Use User Specified Reach Order=0
Composite Channel Slope=5