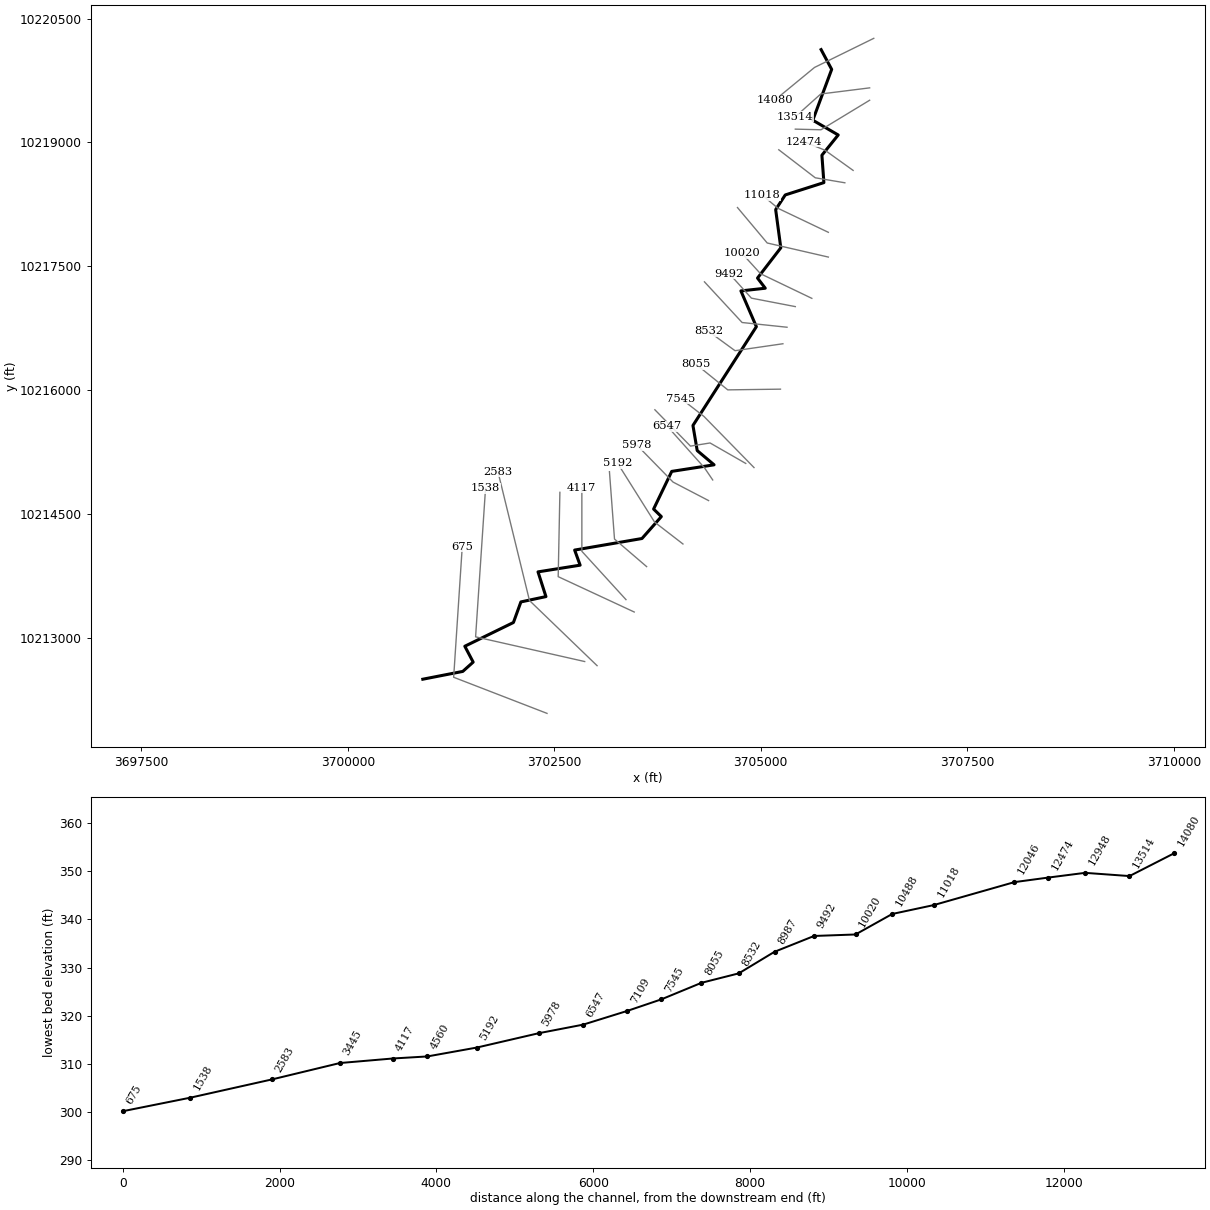
--- CCLC 097.prj (project) ---

Proj Title=CCLC 097 Base Level Engineering
Current Plan=p01
Default Exp/Contr=0.3,0.1
English Units
Geom File=g01
Flow File=f01
Flow File=f02
Plan File=p01
Y Axis Title=Elevation
X Axis Title(PF)=Main Channel Distance
X Axis Title(XS)=Station
BEGIN DESCRIPTION:
CCLC 097
END DESCRIPTION:
DSS Export Rating Curves= 0
DSS Export Rating Curve Sorted= 0
DSS Export Volume Flow Curves= 0
DXF OffsetX= 0
DXF OffsetY= 0
DXF ScaleX= 1
DXF ScaleY= 10

--- CCLC 097.p01 (plan) ---

Plan Title=Multiple Run
Short Identifier=Multiple
Geom File=g01
Flow File=f01
Subcritical Flow
K Sum by GR= 0
Std Step Tol= 0.01
Critical Tol= 0.01
Num of Std Step Trials= 20
Max Error Tol= 0.3
Flow Tol Ratio= 0.001
Split Flow NTrial= 30
Split Flow Tol= 0.02
Split Flow Ratio= 0.02
Log Output Level= 0
Friction Slope Method= 1
Unsteady Friction Slope Method= 2
Unsteady Bridges Friction Slope Method= 1
Parabolic Critical Depth
Global Vel Dist=  1 , 1 , 1
Global Log Level= 0
CheckData=True
Encroach Param= -1, 0, 0, 0
BEGIN DESCRIPTION:
Multiple Run
END DESCRIPTION:

--- CCLC 097.f01 (steady flow) ---

Flow Title=Multiple
Program Version=4.10
Number of Profiles= 7
Profile Names=10-year,25-year,50-year,1pct_min,100-year,1pct_plu,500-year
River Rch & RM=CCLC 097,Reach-1         ,14080
     670     912    1236     551    1664    5025    3118
River Rch & RM=CCLC 097,Reach-1         ,6547
     742    1011    1370     610    1843    5566    3452
Boundary for River Rch & Prof#=CCLC 097,Reach-1         , 1
Up Type= 0
Dn Type= 3
Dn Slope=0.005
Boundary for River Rch & Prof#=CCLC 097,Reach-1         , 2
Up Type= 0
Dn Type= 3
Dn Slope=0.005
Boundary for River Rch & Prof#=CCLC 097,Reach-1         , 3
Up Type= 0
Dn Type= 3
Dn Slope=0.005
Boundary for River Rch & Prof#=CCLC 097,Reach-1         , 4
Up Type= 0
Dn Type= 3
Dn Slope=0.005
Boundary for River Rch & Prof#=CCLC 097,Reach-1         , 5
Up Type= 0
Dn Type= 3
Dn Slope=0.005
Boundary for River Rch & Prof#=CCLC 097,Reach-1         , 6
Up Type= 0
Dn Type= 3
Dn Slope=0.005
Boundary for River Rch & Prof#=CCLC 097,Reach-1         , 7
Up Type= 0
Dn Type= 3
Dn Slope=0.005
DSS Import GetInterval= 0
DSS Import GetPeak= 0
DSS Import FillOption= 0

--- CCLC 097.f02 (steady flow) ---

Flow Title=Orig_BLE_Flows
Program Version=4.10
Number of Profiles= 7
Profile Names=10-year,25-year,50-year,1pct_min,100-year,1pct_plu,500-year
River Rch & RM=CCLC 097,Reach-1         ,14080
     670     894    1075     424    1280    3865    1813
River Rch & RM=CCLC 097,Reach-1         ,6547
     742     991    1191     469    1418    4282    2007
Boundary for River Rch & Prof#=CCLC 097,Reach-1         , 1
Up Type= 0
Dn Type= 3
Dn Slope=0.005
Boundary for River Rch & Prof#=CCLC 097,Reach-1         , 2
Up Type= 0
Dn Type= 3
Dn Slope=0.005
Boundary for River Rch & Prof#=CCLC 097,Reach-1         , 3
Up Type= 0
Dn Type= 3
Dn Slope=0.005
Boundary for River Rch & Prof#=CCLC 097,Reach-1         , 4
Up Type= 0
Dn Type= 3
Dn Slope=0.005
Boundary for River Rch & Prof#=CCLC 097,Reach-1         , 5
Up Type= 0
Dn Type= 3
Dn Slope=0.005
Boundary for River Rch & Prof#=CCLC 097,Reach-1         , 6
Up Type= 0
Dn Type= 3
Dn Slope=0.005
Boundary for River Rch & Prof#=CCLC 097,Reach-1         , 7
Up Type= 0
Dn Type= 3
Dn Slope=0.005
DSS Import GetInterval= 0
DSS Import GetPeak= 0
DSS Import FillOption= 0

--- CCLC 097.g01 (geometry) ---

Geom Title=Existing Conditions
Program Version=4.10

River Reach=CCLC 097        ,Reach-1
Reach XY= 30
      3705730.31     10220124.49       3705858.2     10219884.83
       3705629.7     10219269.33      3705937.21     10219090.29
      3705739.92     10218845.07      3705763.92     10218513.28
      3705296.34     10218363.86      3705180.12     10218186.14
      3705242.33     10217723.29      3704960.34     10217356.72
      3705054.35      10217233.7      3704759.42     10217201.16
      3704946.42     10216767.64      3704178.67     10215570.86
      3704230.23     10215266.95      3704434.64     10215094.33
      3703921.94     10215014.68      3703702.47     10214558.18
      3703796.11     10214466.88      3703561.61     10214201.48
      3702746.55     10214061.41      3702812.86     10213878.49
      3702302.95     10213797.31      3702398.99     10213497.77
      3702095.72     10213433.29      3702005.32     10213183.88
      3701416.85     10212896.22      3701518.02       10212704.
      3701392.06     10212591.41      3700908.23     10212496.84

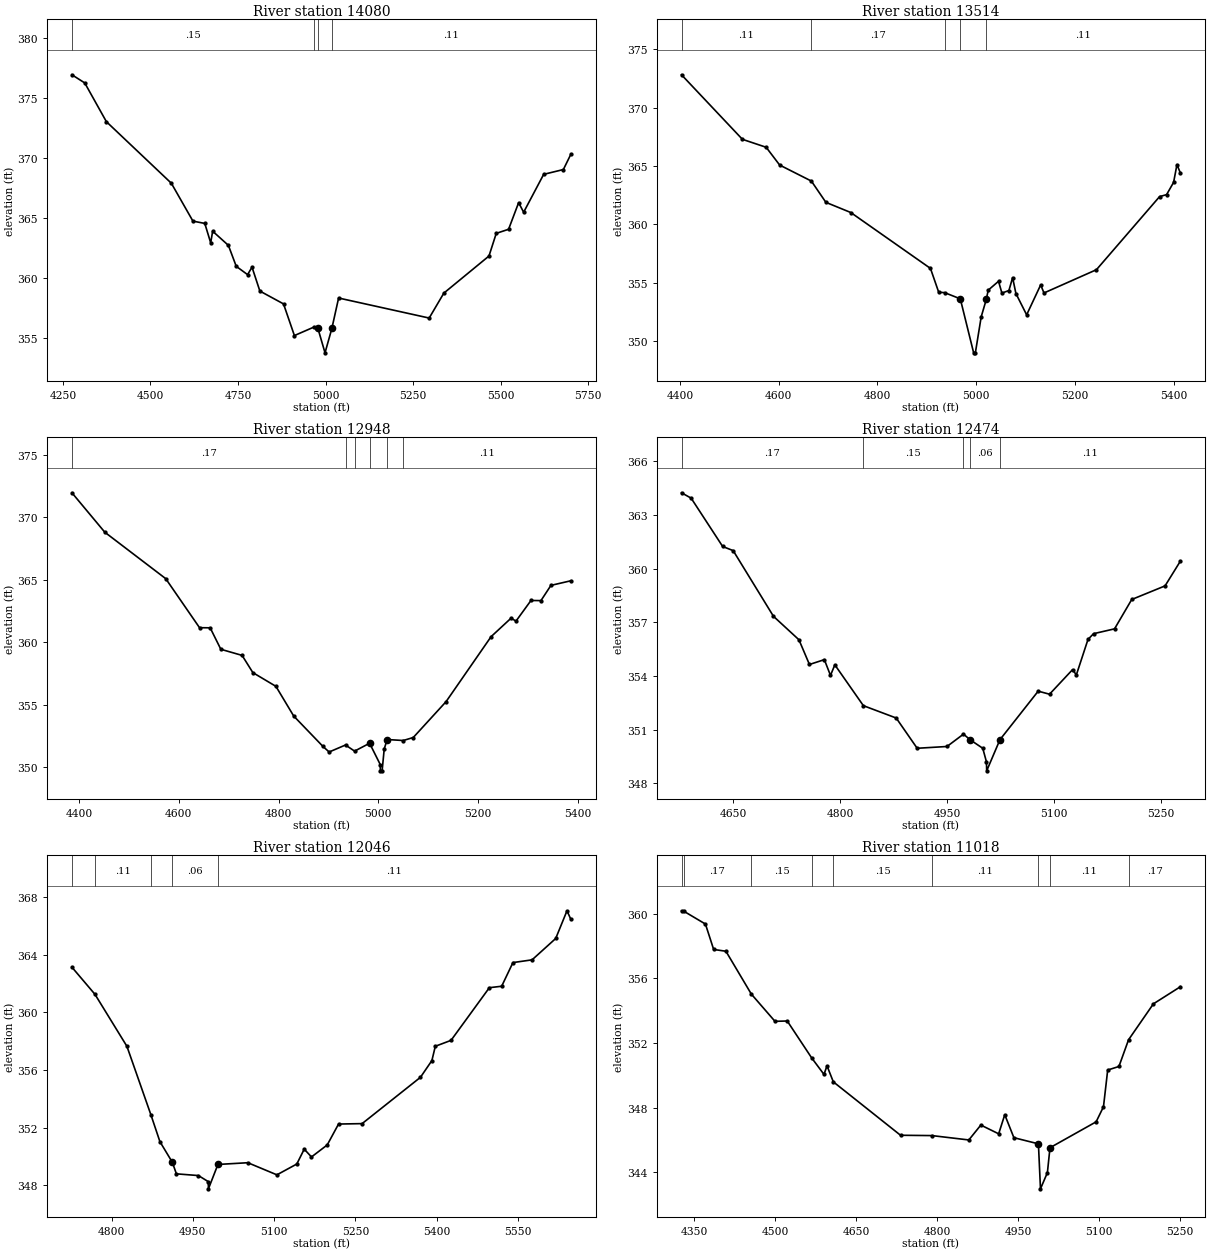
Type RM Length L Ch R = 1 ,14080   ,566,566,566
BEGIN DESCRIPTION:
CCLC 097 23.0
END DESCRIPTION:
XS GIS Cut Line= 3
       3706367.9     10220261.09      3705650.62     10219908.53
      3705167.83     10219511.05
#Sta/Elev= 30
  4275.7  376.91  4312.3  376.23  4374.1     373  4559.5  367.87  4621.2  364.71
    4655  364.52  4671.9   362.9  4677.5  363.87  4722.4  362.69  4744.9  360.94
  4777.2  360.25  4789.9  360.87  4812.3  358.88  4879.8  357.81  4910.9  355.17
  4967.6  355.89  4977.7   355.8  4998.3  353.73  5017.8355.7608  5037.1   358.3
  5295.7  356.63  5337.6  358.71  5466.4   361.8  5487.2  363.69  5522.4  364.03
  5551.1  366.25  5565.4  365.45  5622.6  368.61  5678.8  369.01  5700.3  370.29
#Mann= 4 ,-1 , 0
  4275.7     .15       0  4967.6     .11       0  4977.7     .06       0
  5017.8     .11       0
Bank Sta=4977.7,5017.8
XS Rating Curve= 0 ,0
Exp/Cntr=0.3,0.1

Type RM Length L Ch R = 1 ,13514   ,566,566,566
BEGIN DESCRIPTION:
CCLC 097 22.0
END DESCRIPTION:
XS GIS Cut Line= 3
      3706317.89     10219661.08      3705725.93     10219586.82
      3705417.82     10219311.05
#Sta/Elev= 30
  4403.4   372.8  4526.7  367.28  4574.8   366.6  4602.1  365.08  4666.3  363.71
  4695.7  361.89  4746.1  361.02  4907.4  356.24  4924.1   354.2  4935.9  354.17
  4967.8  353.64  4994.8  349.02  4998.3  349.02  5010.1   352.1  5020.4353.5844
  5024.3  354.38  5045.2  355.14    5052  354.13  5066.2  354.35  5073.7  355.45
  5080.4  354.09  5102.1  352.27  5130.5  354.83  5137.2  354.14  5243.4  356.13
  5371.2  362.38  5385.4  362.55  5399.6   363.6  5406.4  365.12  5413.5  364.38
#Mann= 5 ,-1 , 0
  4403.4     .11       0  4666.3     .17       0  4935.9     .11       0
  4967.8     .06       0  5020.4     .11       0
Bank Sta=4967.8,5020.4
XS Rating Curve= 0 ,0
Exp/Cntr=0.3,0.1

Type RM Length L Ch R = 1 ,12948   ,474,474,474
BEGIN DESCRIPTION:
CCLC 097 21.0
END DESCRIPTION:
XS GIS Cut Line= 3
      3706317.84     10219511.06      3705728.74     10219153.32
      3705417.85     10219161.07
#Sta/Elev= 30
  4385.8  371.97  4451.7  368.81  4573.8  365.09  4641.6  361.16  4662.9  361.15
  4684.3  359.43  4726.9  358.94  4748.5  357.56  4794.7  356.46  4830.4  354.08
  4888.9  351.65  4901.4   351.2  4934.2  351.76  4952.4  351.27  4982.5   351.9
  5003.9  350.19  5004.1  349.69  5007.6  349.69  5011.8  351.44  5017.7   352.2
  5049.9  352.12    5070  352.36  5135.9  355.24    5226  360.44    5266  361.92
    5276  361.69    5306  363.34    5326  363.33    5346  364.55    5386  364.92
#Mann= 6 ,-1 , 0
  4385.8     .17       0  4934.2     .11       0  4952.4     .17       0
  4982.5     .09       0  5017.7     .17       0  5049.9     .11       0
Bank Sta=4982.5,5017.7
XS Rating Curve= 0 ,0
Exp/Cntr=0.3,0.1

Type RM Length L Ch R = 1 ,12474   ,428,428,428
BEGIN DESCRIPTION:
CCLC 097 20.0
END DESCRIPTION:
XS GIS Cut Line= 3
      3706117.85     10218661.07      3705776.48     10218905.93
      3705517.84     10219011.08
#Sta/Elev= 30
  4577.8  364.23  4591.3  363.93  4635.5  361.23  4650.2     361  4706.7  357.33
  4742.4  356.02  4757.1  354.64    4778  354.91  4786.6  354.03  4792.7  354.62
  4832.7  352.34  4878.7  351.65  4908.1  349.96  4949.9  350.06    4973  350.75
 4982.24 350.438    5000  349.96  5005.2   349.2  5005.5   348.7  5024.1  350.44
  5077.7  353.15  5093.6  352.98  5125.8  354.35  5131.2  354.06  5147.5  356.04
  5155.3  356.36  5184.7  356.63  5208.8  358.27  5255.5  359.03  5277.1  360.42
#Mann= 5 ,-1 , 0
  4577.8     .17       0  4832.7     .15       0    4973     .11       0
 4982.24     .06       0  5024.1     .11       0
Bank Sta=4982.24,5024.1
XS Rating Curve= 0 ,0
Exp/Cntr=0.3,0.1

Type RM Length L Ch R = 1 ,12046   ,1028,1028,1028
BEGIN DESCRIPTION:
CCLC 097 19.0
END DESCRIPTION:
XS GIS Cut Line= 3
      3706017.84     10218511.07       3705659.3     10218571.73
      3705217.88     10218911.05
#Sta/Elev= 30
    4727  363.12  4769.5  361.24  4828.4  357.64  4872.7  352.89  4889.3  351.03
  4912.2349.6015  4919.7   348.8  4960.3  348.68  4978.5  348.26  4978.8  347.76
  4996.3  349.45  5051.5  349.57  5105.1  348.73  5141.8  349.48  5155.5  350.51
  5168.9  349.97  5197.9   350.8  5218.8  352.25  5262.3  352.28  5369.9  355.49
    5391  356.65  5397.3  357.64  5426.3  358.05    5497   361.7  5519.7   361.8
  5540.5  363.44  5575.8  363.63  5619.4  365.11  5640.2  367.03  5647.4  366.43
#Mann= 5 ,-1 , 0
    4727     .17       0  4769.5     .11       0  4872.7     .15       0
  4912.2     .06       0  4996.3     .11       0
Bank Sta=4912.2,4996.3
XS Rating Curve= 0 ,0
Exp/Cntr=0.3,0.1

Type RM Length L Ch R = 1 ,11018   ,530,530,530
BEGIN DESCRIPTION:
CCLC 097 18.0
END DESCRIPTION:
XS GIS Cut Line= 3
      3705817.86     10217911.07      3705210.24      10218200.9
      3705017.88     10218361.05
#Sta/Elev= 30
  4326.8  360.17  4330.7  360.15  4371.1  359.35  4386.3  357.78    4409  357.67
  4456.1  355.02  4499.8  353.34  4522.5  353.36  4567.5  351.09  4590.5  350.06
  4596.1  350.59  4607.8   349.6  4732.2   346.3  4790.4  346.28  4858.6  346.01
  4880.8  346.93  4913.8  346.39  4925.1  347.57    4942  346.15  4987.4  345.77
  4991.2  342.99    5004  343.99  5008.8  345.53  5094.2  347.13  5107.8  348.06
  5115.6  350.33  5136.4  350.55  5154.2   352.2  5200.2  354.42  5250.3  355.48
#Mann= 9 ,-1 , 0
  4326.8     .11       0  4330.7     .17       0  4456.1     .15       0
  4567.5     .11       0  4607.8     .15       0  4790.4     .11       0
  4987.4     .06       0  5008.8     .11       0  5154.2     .17       0
Bank Sta=4987.4,5008.8
XS Rating Curve= 0 ,0
Exp/Cntr=0.3,0.1

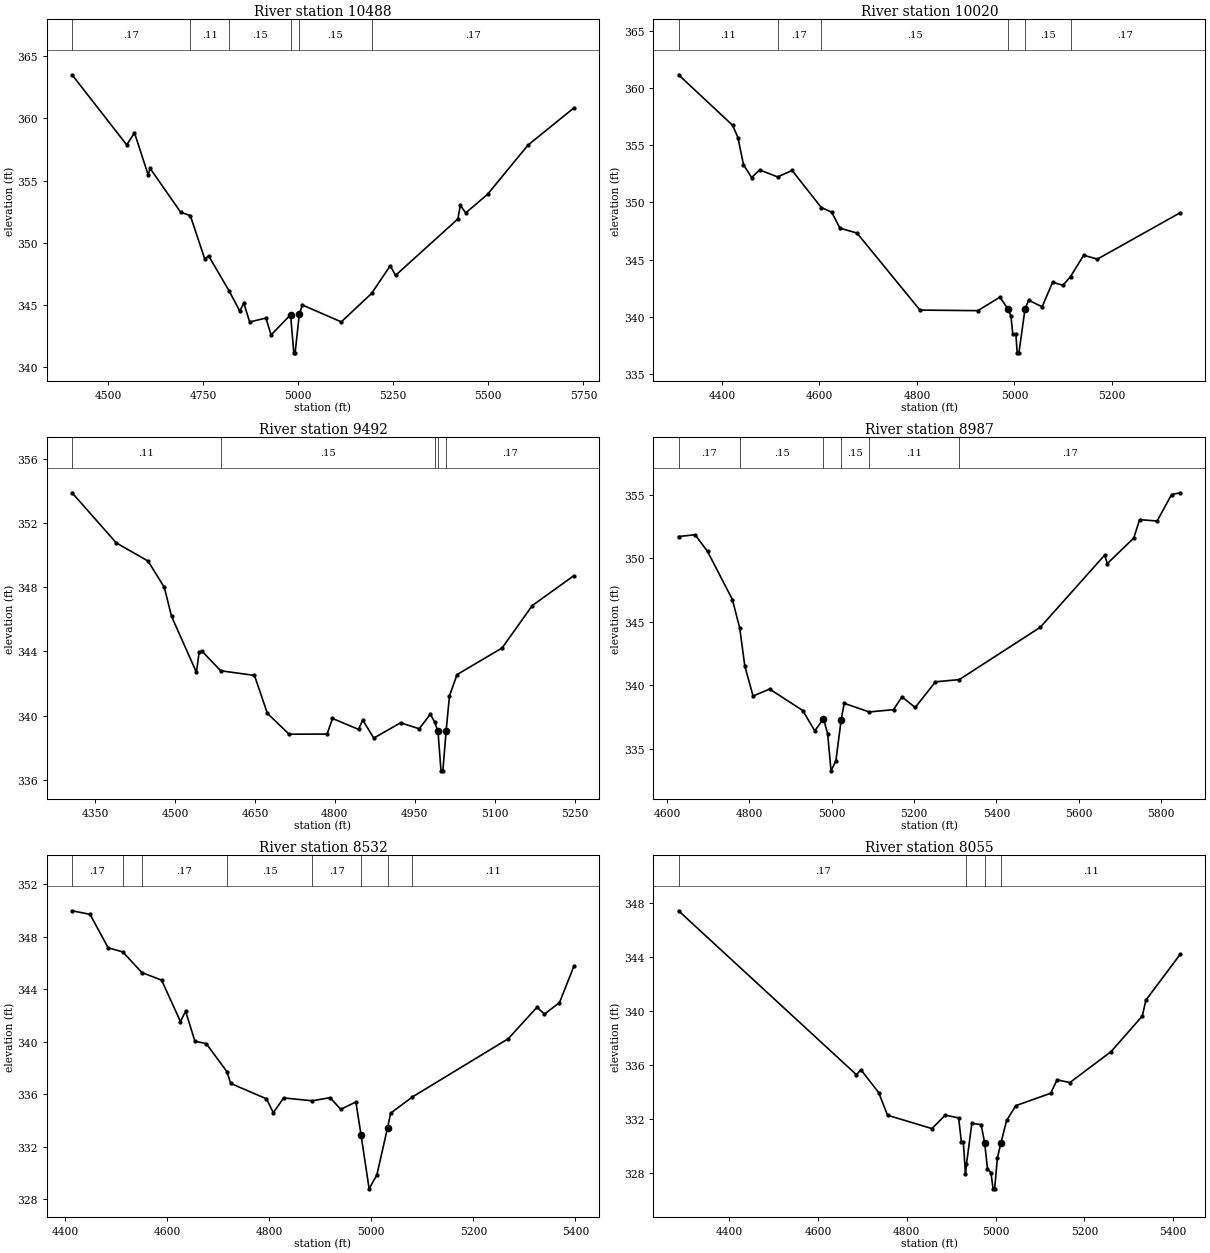
Type RM Length L Ch R = 1 ,10488   ,468,468,468
BEGIN DESCRIPTION:
CCLC 097 17.0
END DESCRIPTION:
XS GIS Cut Line= 3
      3705817.87     10217611.07       3705077.7      10217781.8
      3704717.83      10218211.1
#Sta/Elev= 30
  4405.1  363.51  4548.8  357.87  4569.3  358.84  4605.3  355.45  4610.4  355.98
  4690.8  352.45  4716.1  352.18  4754.1  348.69  4764.3  348.94  4818.4  346.11
  4846.4  344.49  4856.7  345.15  4872.2  343.62    4915  343.94  4928.5  342.58
  4979.8   344.2  4988.3  341.14  4991.8  341.14  5002.7344.2353  5010.8  344.99
  5113.2  343.63  5192.9  345.92  5242.1  348.15  5255.9  347.37  5419.8  351.91
  5426.3     353  5440.6   352.4  5497.8  353.89  5604.5  357.86  5724.9  360.84
#Mann= 6 ,-1 , 0
  4405.1     .17       0  4716.1     .11       0  4818.4     .15       0
  4979.8     .09       0  5002.7     .15       0  5192.9     .17       0
Bank Sta=4979.8,5002.7
XS Rating Curve= 0 ,0
Exp/Cntr=0.3,0.1

Type RM Length L Ch R = 1 ,10020   ,528,528,528
BEGIN DESCRIPTION:
CCLC 097 16.0
END DESCRIPTION:
XS GIS Cut Line= 3
      3705617.89     10217111.05      3704996.71     10217409.37
      3704767.85     10217661.08
#Sta/Elev= 30
  4310.9  361.14  4421.9  356.73  4432.7  355.66  4444.1   353.3  4460.9  352.17
  4477.3  352.84  4514.1  352.23  4543.9  352.79  4603.7  349.56  4624.9  349.16
    4642  347.76    4677  347.33  4806.1  340.61  4924.9  340.56  4970.1  341.74
  4987.2  340.68  4992.8  340.07  4996.6   338.5  5002.9   338.5  5005.6  336.88
  5009.1  336.88  5021.6   340.7    5029  341.47  5056.7   340.9  5078.3  343.04
  5099.3  342.77  5115.1  343.54  5141.9  345.39  5170.2  345.06  5340.2  349.11
#Mann= 6 ,-1 , 0
  4310.9     .11       0  4514.1     .17       0  4603.7     .15       0
  4987.2     .09       0  5021.6     .15       0  5115.1     .17       0
Bank Sta=4987.2,5021.6
XS Rating Curve= 0 ,0
Exp/Cntr=0.3,0.1

Type RM Length L Ch R = 1 ,9492    ,505,505,505
BEGIN DESCRIPTION:
CCLC 097 15.0
END DESCRIPTION:
XS GIS Cut Line= 3
      3705417.88     10217011.07      3704886.73     10217113.39
      3704617.88     10217411.04
#Sta/Elev= 30
  4306.7  353.88  4389.7  350.76  4449.3  349.63  4479.9  347.99  4493.4  346.19
  4540.2   342.7  4545.3  343.98  4551.1     344  4585.8   342.8  4649.1  342.51
  4673.3  340.15  4714.1  338.85  4785.4  338.86  4795.6  339.83  4844.5  339.15
  4852.3  339.73  4873.2  338.61  4923.3  339.56  4958.4  339.19  4979.4   340.1
  4987.2  339.61  4993.6  339.04  4999.3  336.57  5002.8  336.57  5008.9339.0691
  5015.2  341.24  5029.4  342.56    5114  344.22  5170.7  346.86  5248.7  348.72
#Mann= 5 ,-1 , 0
  4306.7     .11       0  4585.8     .15       0  4987.2     .17       0
  4993.6     .09       0  5008.9     .17       0
Bank Sta=4993.6,5008.9
XS Rating Curve= 0 ,0
Exp/Cntr=0.3,0.1

Type RM Length L Ch R = 1 ,8987    ,455,455,455
BEGIN DESCRIPTION:
CCLC 097 14.0
END DESCRIPTION:
XS GIS Cut Line= 3
      3705317.85     10216761.07      3704773.88     10216818.25
      3704317.86     10217311.07
#Sta/Elev= 30
    4628   351.7  4668.2  351.84  4698.4  350.53  4758.7  346.75  4776.6   344.5
  4788.9  341.52    4809  339.16  4849.2  339.71  4929.7  338.02  4958.8  336.42
  4979.9  337.38    4990   336.2  4998.3  333.28  5010.1  334.07    5023337.3139
  5030.2  338.59  5090.9  337.91    5150  338.09  5170.5   339.1  5202.6  338.26
  5251.9  340.28  5309.5  340.45  5506.5  344.57  5662.4  350.23  5669.3  349.58
  5733.3  351.58  5747.5  353.03    5790  352.92  5825.1     355  5846.4  355.14
#Mann= 6 ,-1 , 0
    4628     .17       0  4776.6     .15       0  4979.9     .09       0
    5023     .15       0  5090.9     .11       0  5309.5     .17       0
Bank Sta=4979.9,5023
XS Rating Curve= 0 ,0
Exp/Cntr=0.3,0.1

Type RM Length L Ch R = 1 ,8532    ,477,477,477
BEGIN DESCRIPTION:
CCLC 097 13.0
END DESCRIPTION:
XS GIS Cut Line= 3
      3705267.86     10216561.07      3704688.14     10216476.85
      3704367.85     10216711.07
#Sta/Elev= 30
  4414.2  349.96  4449.3  349.69  4484.9  347.14  4513.5  346.83  4550.9  345.26
  4589.6  344.68  4626.4  341.53  4636.5  342.32  4654.7  340.04  4676.9  339.85
  4717.6  337.71  4724.8  336.82  4794.9  335.65  4808.3  334.59  4828.5  335.72
  4884.4   335.5  4919.5  335.74  4940.3  334.85    4970  335.41  4980.1  332.89
  4995.9   328.8  5011.1  329.87    5032  333.45  5038.1  334.56  5080.5  335.79
  5268.2  340.22  5324.6  342.62  5339.3   342.1  5368.6  342.97  5396.8  345.73
#Mann= 8 ,-1 , 0
  4414.2     .17       0  4513.5     .15       0  4550.9     .17       0
  4717.6     .15       0  4884.4     .17       0  4980.1     .09       0
    5032     .17       0  5080.5     .11       0
Bank Sta=4980.1,5032
XS Rating Curve= 0 ,0
Exp/Cntr=0.3,0.1

Type RM Length L Ch R = 1 ,8055    ,510,510,510
BEGIN DESCRIPTION:
CCLC 097 12.0
END DESCRIPTION:
XS GIS Cut Line= 3
       3705238.3     10216010.96      3704600.27     10216002.28
      3704217.86     10216311.06
#Sta/Elev= 30
  4286.2  347.42  4686.7  335.28  4696.7  335.65  4736.7  333.96  4756.7  332.28
  4856.7  331.29  4886.7  332.29  4916.7  332.08    4923  330.29  4927.3  330.29
  4932.1  327.96  4934.4  328.67  4946.5  331.67  4967.3  331.59  4975.2  330.26
  4981.7  328.32  4989.6  328.01  4994.3  326.83  4997.8  326.83    5004  329.11
  5011.6330.1876  5024.8   331.9  5045.6  332.99    5124  333.91  5138.4   334.9
  5167.1   334.7  5259.9  336.99  5330.3  339.63  5338.2   340.8  5415.8  344.21
#Mann= 4 ,-1 , 0
  4286.2     .17       0  4934.4     .11       0  4975.2     .06       0
  5011.6     .11       0
Bank Sta=4975.2,5011.6
XS Rating Curve= 0 ,0
Exp/Cntr=0.3,0.1

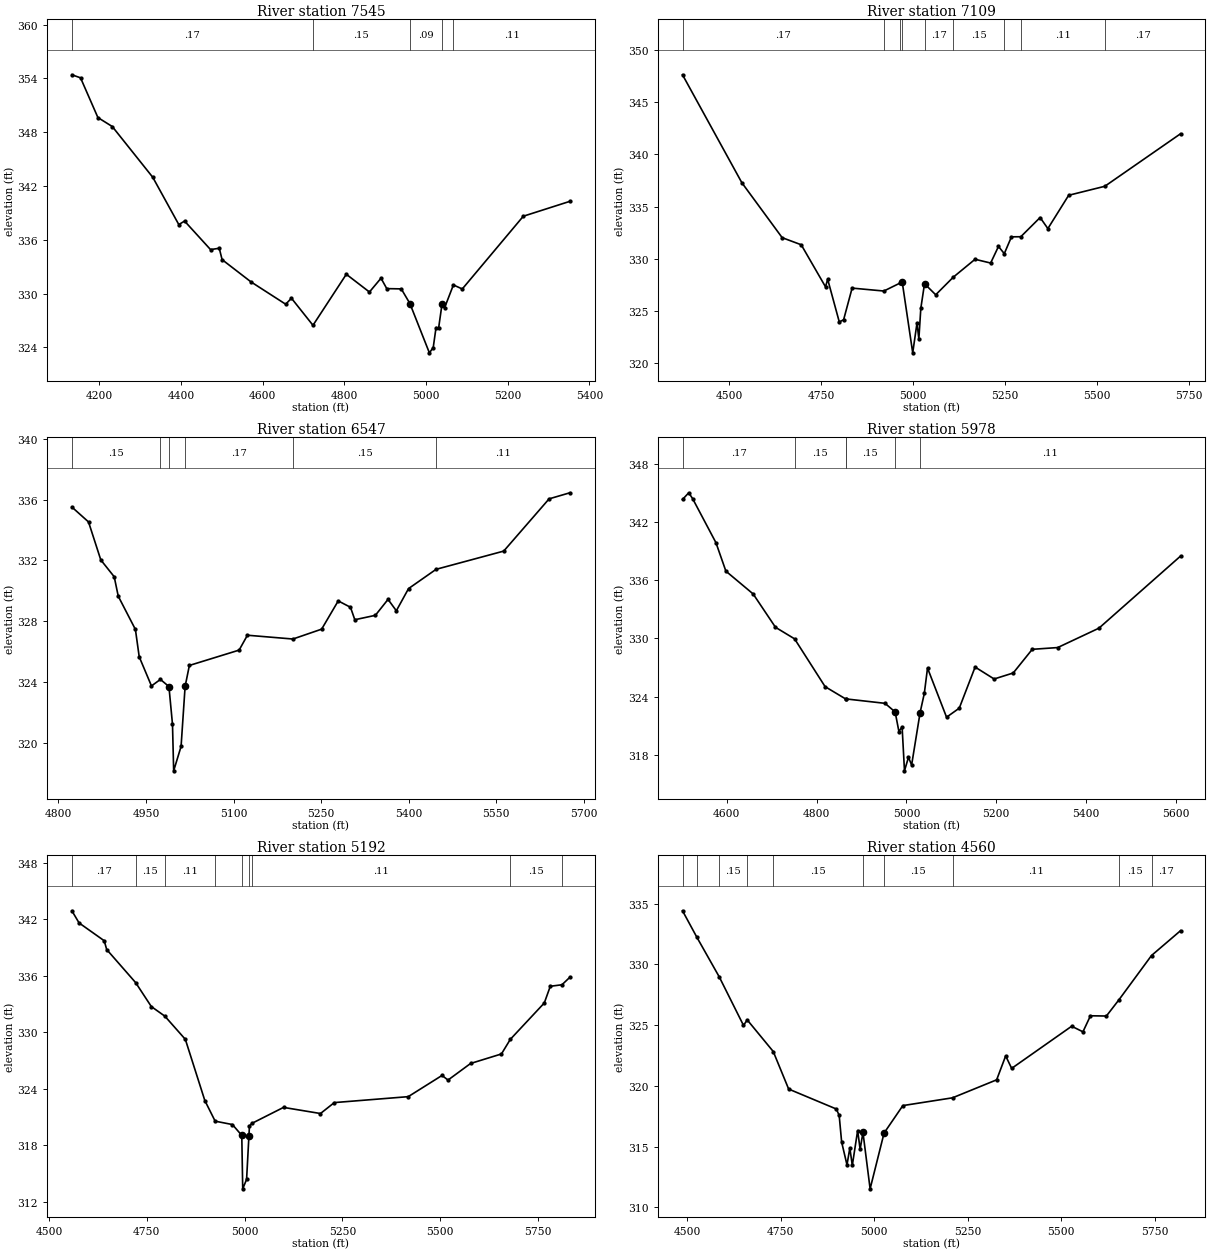
Type RM Length L Ch R = 1 ,7545    ,436,436,436
BEGIN DESCRIPTION:
CCLC 097 11.0
END DESCRIPTION:
XS GIS Cut Line= 3
      3704917.86     10215061.07      3704311.81     10215680.64
      3704033.61     10215896.63
#Sta/Elev= 30
  4133.3   354.4  4154.5  354.06    4197  349.63  4232.2  348.63  4331.3  342.97
    4395   337.7  4409.1  338.09  4472.7  334.91    4494  335.06    4501  333.79
  4571.7  331.31  4656.6  328.82  4670.7  329.49  4723.4  326.47    4805  332.16
  4861.6  330.18  4889.9  331.72    4904  330.56  4939.5  330.53  4960.6   328.9
  5008.3   323.4  5017.7  323.98  5024.6  326.22  5030.9  326.16  5039.1  328.79
  5045.4  328.41  5067.1  330.97  5088.8  330.52  5238.2  338.63  5352.2  340.29
#Mann= 5 ,-1 , 0
  4133.3     .17       0  4723.4     .15       0  4960.6     .09       0
  5039.1     .15       0  5067.1     .11       0
Bank Sta=4960.6,5039.1
XS Rating Curve= 0 ,0
Exp/Cntr=0.3,0.1

Type RM Length L Ch R = 1 ,7109    ,562,562,562
BEGIN DESCRIPTION:
CCLC 097 10.0
END DESCRIPTION:
XS GIS Cut Line= 4
      3704817.82     10215111.09      3704385.86     10215359.05
      3704148.88     10215320.86      3703717.86     10215761.07
#Sta/Elev= 30
  4372.6  347.62    4534  337.28  4643.6  332.02  4695.4  331.34  4761.5  327.31
  4767.3  328.04  4798.9  323.95  4810.7  324.16  4833.8  327.19  4920.1  326.91
  4964.6  327.68  4969.9  327.81  4998.6  320.99  5010.3  323.86  5015.3  322.31
  5020.6  325.25  5030.7  327.61  5061.1  326.55  5108.7  328.23  5168.1  329.95
  5210.5  329.59  5231.8  331.18  5247.6  330.49  5267.1   332.1  5292.5  332.11
    5345  333.95  5366.1  332.89  5422.7  336.08  5520.9  336.94  5726.8  341.97
#Mann= 9 ,-1 , 0
  4372.6     .17       0  4920.1     .15       0  4964.6     .17       0
  4969.9     .09       0  5030.7     .17       0  5108.7     .15       0
  5247.6     .17       0  5292.5     .11       0  5520.9     .17       0
Bank Sta=4969.9,5030.7
XS Rating Curve= 0 ,0
Exp/Cntr=0.3,0.1

Type RM Length L Ch R = 1 ,6547    ,569,569,569
BEGIN DESCRIPTION:
CCLC 097 9.0
END DESCRIPTION:
XS GIS Cut Line= 3
      3704417.87     10214911.05      3704318.65     10215057.38
      3703867.83      10215561.1
#Sta/Elev= 30
  4823.2  335.51  4851.7  334.53  4872.7  332.03  4895.7  330.92  4902.6  329.64
    4932  327.45  4938.5  325.65  4959.5  323.73  4974.8  324.16  4989.4  323.69
  4995.5   321.2  4997.5  318.14  5010.2  319.75  5017.1323.6967  5024.4  325.08
  5109.6  326.09  5123.8  327.07  5201.7  326.82  5250.9  327.47  5279.3  329.33
  5300.3  328.91  5307.7  328.09  5342.9  328.38  5364.6  329.43  5378.8  328.68
  5399.7  330.14  5446.9  331.41  5562.7  332.61  5640.4  336.05    5676  336.45
#Mann= 6 ,-1 , 0
  4823.2     .15       0  4974.8     .17       0  4989.4     .09       0
  5017.1     .17       0  5201.7     .15       0  5446.9     .11       0
Bank Sta=4989.4,5017.1
XS Rating Curve= 0 ,0
Exp/Cntr=0.3,0.1

Type RM Length L Ch R = 1 ,5978    ,786,786,786
BEGIN DESCRIPTION:
CCLC 097 8.0
END DESCRIPTION:
XS GIS Cut Line= 3
      3704367.87     10214661.06      3703937.94     10214885.09
      3703501.65     10215331.77
#Sta/Elev= 30
  4501.3  344.33  4515.2  345.02  4523.9  344.41  4575.8  339.87  4597.9  336.94
  4658.6  334.59  4708.4  331.15  4750.9  329.96  4818.9  325.03  4864.4  323.77
  4864.5  323.77  4952.4  323.31  4974.9  322.42  4983.3   320.4  4990.4  320.89
  4995.7  316.35  5004.6  317.75  5011.6  316.95  5030.5  322.36  5039.9  324.34
    5047  326.95  5089.4  321.88  5117.7  322.81    5153  327.05  5195.4  325.82
  5237.9  326.44  5280.3  328.88  5336.9  329.06  5428.8  331.06  5610.5  338.49
#Mann= 6 ,-1 , 0
  4501.3     .17       0  4750.9     .15       0  4864.4     .17       0
  4864.5     .15       0  4974.9     .07       0  5030.5     .11       0
Bank Sta=4974.9,5030.5
XS Rating Curve= 0 ,0
Exp/Cntr=0.3,0.1

Type RM Length L Ch R = 1 ,5192    ,632,632,632
BEGIN DESCRIPTION:
CCLC 097 7.0
END DESCRIPTION:
XS GIS Cut Line= 3
      3704057.75     10214135.08      3703713.98     10214400.72
      3703267.83      10215111.1
#Sta/Elev= 30
  4558.5  342.88  4576.9  341.59  4641.2   339.7  4647.5  338.77  4721.5  335.26
  4761.6  332.72  4796.2   331.7  4848.6  329.24  4898.4  322.75  4924.8  320.56
    4969   320.2  4992.9  319.05  4995.3  313.38  5005.2  314.38  5011.2 319.024
  5012.5  320.03  5018.5  320.32  5099.6  322.02  5194.1  321.37  5229.5  322.53
  5418.5  323.16  5504.9  325.41  5520.2  324.92  5577.9  326.68  5656.8  327.69
  5679.5  329.24  5766.4   333.1  5781.7  334.87  5811.5  335.03  5831.8  335.83
#Mann= 9 ,-1 , 0
  4558.5     .17       0  4721.5     .15       0  4796.2     .11       0
  4924.8     .17       0  4992.9     .09       0  5011.2     .17       0
  5018.5     .11       0  5679.5     .15       0  5811.5     .17       0
Bank Sta=4992.9,5011.2
XS Rating Curve= 0 ,0
Exp/Cntr=0.3,0.1

Type RM Length L Ch R = 1 ,4560    ,443,443,443
BEGIN DESCRIPTION:
CCLC 097 6.0
END DESCRIPTION:
XS GIS Cut Line= 3
      3703617.88     10213861.05      3703229.03     10214194.91
      3703167.85     10215011.12
#Sta/Elev= 30
  4487.5  334.41  4525.9  332.23  4585.7  328.97  4650.5  324.98  4660.5  325.43
    4730  322.83  4771.2  319.74  4898.5   318.1  4906.2  317.58  4912.8  315.38
  4927.1   313.5  4934.7  314.89  4941.3  313.46  4955.6  316.33  4962.2  314.78
  4969.8  316.17  4988.9  311.53  5026.2  316.12  5076.4  318.38  5209.2  319.02
  5327.1   320.5  5351.2  322.47  5367.2  321.44  5527.6  324.91  5557.7  324.45
  5577.8  325.77  5620.4  325.75  5654.3   327.1    5741  330.73  5818.5  332.77
#Mann= 10 ,-1 , 0
  4487.5     .11       0  4525.9     .17       0  4585.7     .15       0
  4660.5     .17       0    4730     .15       0  4969.8     .09       0
  5026.2     .15       0  5209.2     .11       0  5654.3     .15       0
    5741     .17       0
Bank Sta=4969.8,5026.2
XS Rating Curve= 0 ,0
Exp/Cntr=0.3,0.1

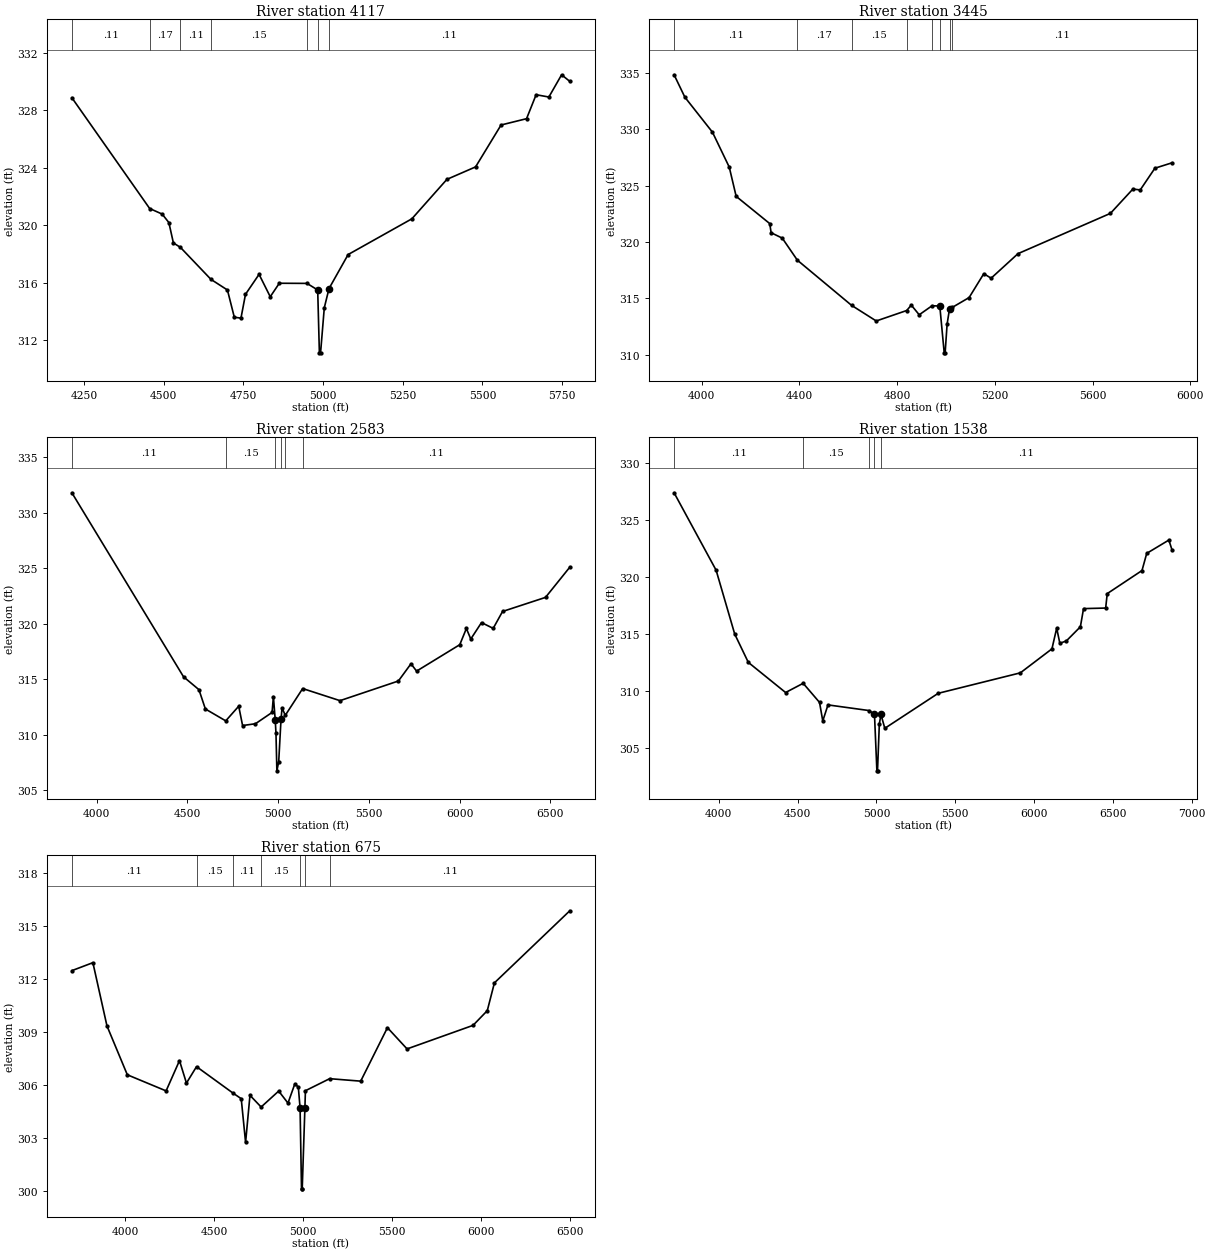
Type RM Length L Ch R = 1 ,4117    ,672,672,672
BEGIN DESCRIPTION:
CCLC 097 5.0
END DESCRIPTION:
XS GIS Cut Line= 3
      3703367.86     10213461.06      3702833.78     10214046.55
      3702833.78     10214816.76
#Sta/Elev= 30
  4211.5  328.88  4455.6  321.16  4494.9  320.77  4515.9  320.18  4530.1  318.76
  4552.2  318.45    4648  316.22  4699.7  315.48  4721.3  313.58  4742.2  313.52
  4756.4  315.18    4799  316.57  4834.1  315.01  4862.5  315.95  4949.5  315.94
    4983  315.48  4988.3   311.1    4992   311.1  5003.7  314.24  5018.5  315.58
  5078.5  317.95  5278.5  320.44  5388.5  323.19  5478.5  324.06  5558.5  326.98
  5638.5  327.42  5668.5  329.09  5708.5  328.93  5748.5  330.48  5774.2  330.02
#Mann= 7 ,-1 , 0
  4211.5     .11       0  4455.6     .17       0  4552.2     .11       0
    4648     .15       0  4949.5     .11       0    4983     .06       0
  5018.5     .11       0
Bank Sta=4983,5018.5
XS Rating Curve= 0 ,0
Exp/Cntr=0.3,0.1

Type RM Length L Ch R = 1 ,3445    ,862,862,862
BEGIN DESCRIPTION:
CCLC 097 4.0
END DESCRIPTION:
XS GIS Cut Line= 3
      3703467.83     10213311.08      3702547.32     10213739.26
      3702567.85     10214761.03
#Sta/Elev= 30
  3887.8  334.86  3931.9  332.87  4044.8  329.76  4113.5  326.66  4141.8  324.06
  4279.2  321.64  4284.8  320.83  4330.4  320.35  4392.2  318.39  4613.9  314.38
  4714.9  312.99  4839.6  313.92  4858.3   314.4  4890.7  313.54  4943.1  314.34
  4974.9  314.32    4993  310.16  4996.8  310.16  5004.9  312.72  5014.9  314.09
  5026.3   314.2  5094.9  315.07  5154.9  317.19  5184.9  316.79  5294.9  318.97
  5673.1  322.55    5765  324.71    5795  324.63    5855  326.56    5925  327.04
#Mann= 8 ,-1 , 0
  3887.8     .11       0  4392.2     .17       0  4613.9     .15       0
  4839.6     .11       0  4943.1     .15       0  4974.9     .09       0
  5014.9     .15       0  5026.3     .11       0
Bank Sta=4974.9,5014.9
XS Rating Curve= 0 ,0
Exp/Cntr=0.3,0.1

Type RM Length L Ch R = 1 ,2583    ,1045,1045,1045
BEGIN DESCRIPTION:
CCLC 097 3.0
END DESCRIPTION:
XS GIS Cut Line= 3
      3703017.82      10212661.1      3702199.69     10213450.09
      3701817.85     10215011.07
#Sta/Elev= 30
  3863.4  331.81  4478.6  315.24  4563.5  314.08    4599  312.34  4711.2  311.27
  4782.7  312.59    4804  310.85  4874.8  311.01  4966.6  312.03  4973.8  313.46
 4983.85311.3646    4988  310.16    4993  306.77  5003.1   307.6  5015.9311.4339
  5021.6  312.43  5039.4  311.77  5135.1  314.18  5340.7  313.09  5662.5  314.86
  5731.9  316.41  5762.8  315.75  6000.8  318.13  6037.2  319.59  6061.4  318.64
  6120.5  320.12  6184.9   319.6  6236.4  321.12  6473.2  322.39    6607  325.11
#Mann= 6 ,-1 , 0
  3863.4     .11       0  4711.2     .15       0 4983.85     .06       0
  5015.9     .15       0  5039.4     .15       0  5135.1     .11       0
Bank Sta=4983.85,5015.9
XS Rating Curve= 0 ,0
Exp/Cntr=0.3,0.1

Type RM Length L Ch R = 1 ,1538    ,863,863,863
BEGIN DESCRIPTION:
CCLC 097 2.0
END DESCRIPTION:
XS GIS Cut Line= 3
      3702867.88     10212711.07      3701547.32     10213010.09
      3701667.85     10214811.07
#Sta/Elev= 30
  3716.3  327.42  3982.9  320.61    4101  314.99  4187.3   312.5  4423.8  309.85
  4535.3  310.66  4639.1  308.98  4659.6  307.35  4692.7  308.76  4954.9  308.26
  4987.7  307.93    5003  302.96  5006.9  302.96  5018.5  307.08  5028.7  307.92
  5053.2   306.7    5392  309.78  5913.2  311.58  6113.6  313.69  6143.7  315.51
  6163.7  314.18  6205.1  314.39    6294  315.63    6314  317.23  6454.4  317.28
  6464.4  318.55  6684.9  320.58  6714.9  322.09  6855.3  323.26  6875.3   322.4
#Mann= 5 ,-1 , 0
  3716.3     .11       0  4535.3     .15       0  4954.9     .11       0
  4987.7     .06       0  5028.7     .11       0
Bank Sta=4987.7,5028.7
XS Rating Curve= 0 ,0
Exp/Cntr=0.3,0.1

Type RM Length L Ch R = 1 ,675     ,0,0,0
BEGIN DESCRIPTION:
CCLC 097 1.0
END DESCRIPTION:
XS GIS Cut Line= 3
      3702411.93       10212083.      3701281.69     10212520.51
      3701385.86     10214103.83
#Sta/Elev= 30
  3701.4  312.46  3819.5  312.91  3898.6  309.34    4013  306.58    4231  305.67
  4306.3  307.38  4345.4  306.11    4402  307.04  4606.5  305.55  4653.3  305.23
  4677.8  302.76  4702.4  305.42  4765.1  304.76  4863.9  305.66  4916.1  304.98
    4954  306.05  4974.1   305.9  4984.1   304.7  4992.1  300.14  4996.1  300.14
  5011.1 304.678  5014.1  305.68  5150.4  306.36  5324.8  306.22  5475.1  309.24
  5585.4  308.04  5956.2  309.37  6036.3   310.2  6076.4  311.77  6500.1  315.84
#Mann= 7 ,-1 , 0
  3701.4     .11       0    4402     .15       0  4606.5     .11       0
  4765.1     .15       0  4984.1     .09       0  5011.1     .15       0
  5150.4     .11       0
Bank Sta=4984.1,5011.1
XS Rating Curve= 0 ,0
Exp/Cntr=0.3,0.1

Chan Stop Cuts=-1
Use User Specified Reach Order=0
Composite Channel Slope=5