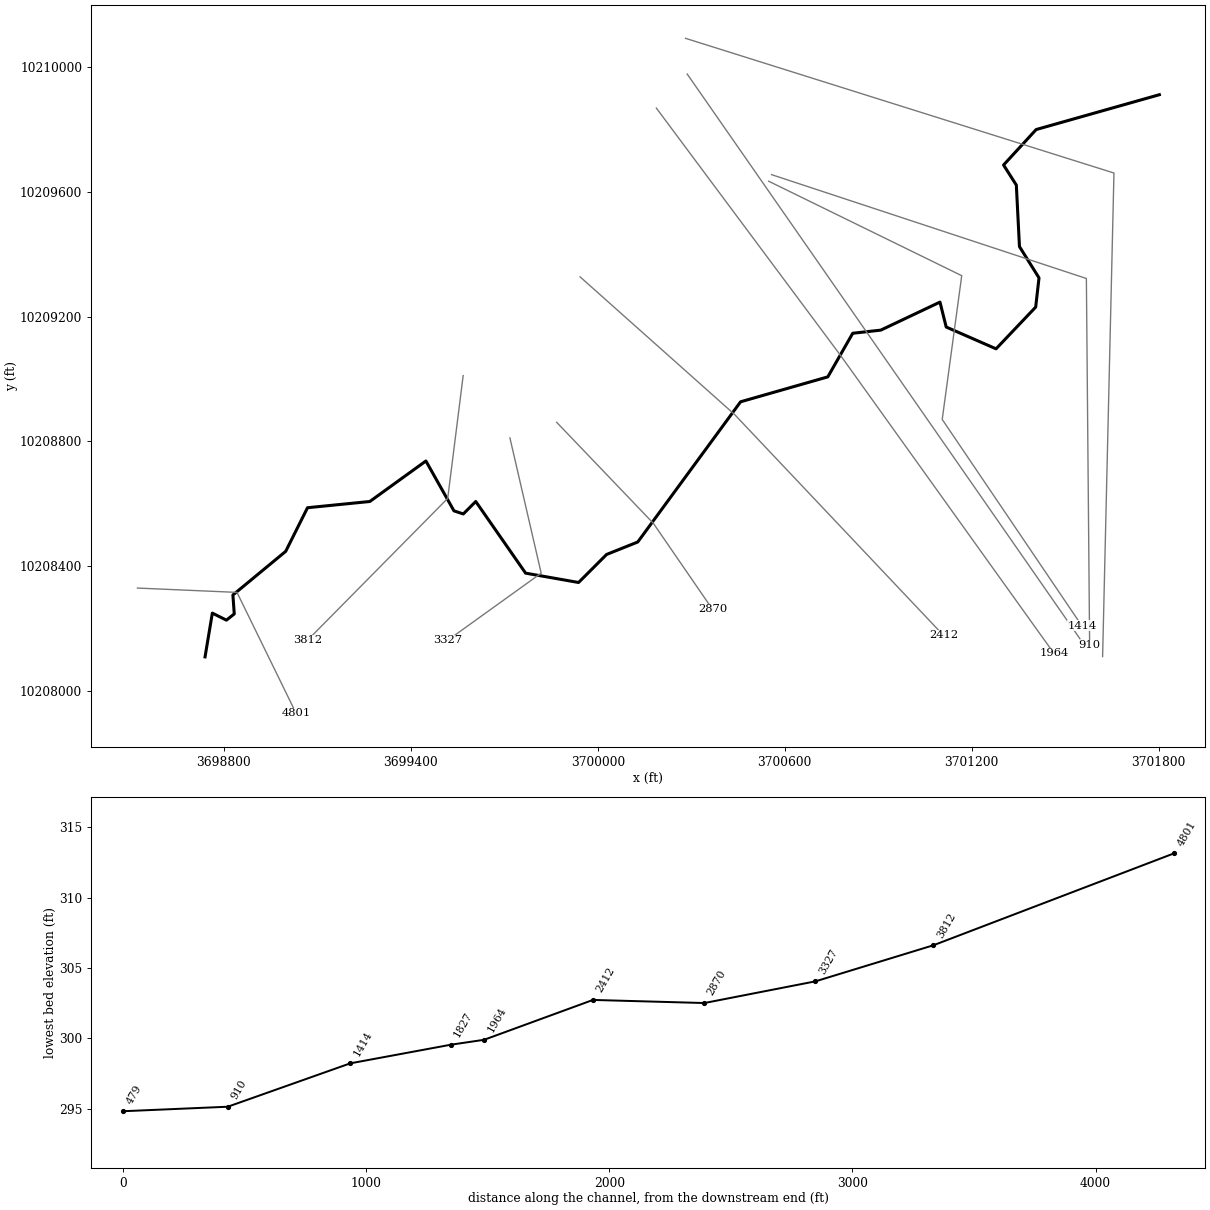
--- CCLC 098.prj (project) ---

Proj Title=CCLC 098 Base Level Engineering
Current Plan=p01
Default Exp/Contr=0.3,0.1
English Units
Geom File=g01
Flow File=f01
Flow File=f02
Plan File=p01
Y Axis Title=Elevation
X Axis Title(PF)=Main Channel Distance
X Axis Title(XS)=Station
BEGIN DESCRIPTION:
CCLC 098
END DESCRIPTION:
DSS Export Rating Curves= 0
DSS Export Rating Curve Sorted= 0
DSS Export Volume Flow Curves= 0
DXF OffsetX= 0
DXF OffsetY= 0
DXF ScaleX= 1
DXF ScaleY= 10

--- CCLC 098.p01 (plan) ---

Plan Title=Multiple Run
Short Identifier=Multiple
Geom File=g01
Flow File=f01
Subcritical Flow
K Sum by GR= 0
Std Step Tol= 0.01
Critical Tol= 0.01
Num of Std Step Trials= 20
Max Error Tol= 0.3
Flow Tol Ratio= 0.001
Split Flow NTrial= 30
Split Flow Tol= 0.02
Split Flow Ratio= 0.02
Log Output Level= 0
Friction Slope Method= 1
Unsteady Friction Slope Method= 2
Unsteady Bridges Friction Slope Method= 1
Parabolic Critical Depth
Global Vel Dist=  1 , 1 , 1
Global Log Level= 0
CheckData=True
Encroach Param= -1, 0, 0, 0
BEGIN DESCRIPTION:
Multiple Run
END DESCRIPTION:

--- CCLC 098.f01 (steady flow) ---

Flow Title=Multiple
Program Version=4.10
Number of Profiles= 7
Profile Names=10-year,25-year,50-year,1pct_min,100-year,1pct_plu,500-year
River Rch & RM=CCLC 098,Reach-1         ,4801
     483     650     874     388    1171    3536    2171
River Rch & RM=CCLC 098,Reach-1         ,3812
     755    1041    1425     641    1936    5847    3695
Boundary for River Rch & Prof#=CCLC 098,Reach-1         , 1
Up Type= 0
Dn Type= 3
Dn Slope=0.005
Boundary for River Rch & Prof#=CCLC 098,Reach-1         , 2
Up Type= 0
Dn Type= 3
Dn Slope=0.005
Boundary for River Rch & Prof#=CCLC 098,Reach-1         , 3
Up Type= 0
Dn Type= 3
Dn Slope=0.005
Boundary for River Rch & Prof#=CCLC 098,Reach-1         , 4
Up Type= 0
Dn Type= 3
Dn Slope=0.005
Boundary for River Rch & Prof#=CCLC 098,Reach-1         , 5
Up Type= 0
Dn Type= 3
Dn Slope=0.005
Boundary for River Rch & Prof#=CCLC 098,Reach-1         , 6
Up Type= 0
Dn Type= 3
Dn Slope=0.005
Boundary for River Rch & Prof#=CCLC 098,Reach-1         , 7
Up Type= 0
Dn Type= 3
Dn Slope=0.005
DSS Import GetInterval= 0
DSS Import GetPeak= 0
DSS Import FillOption= 0

--- CCLC 098.f02 (steady flow) ---

Flow Title=Orig_BLE_Flows
Program Version=4.10
Number of Profiles= 7
Profile Names=10-year,25-year,50-year,1pct_min,100-year,1pct_plu,500-year
River Rch & RM=CCLC 098,Reach-1         ,4801
     483     637     760     298     901    2720    1262
River Rch & RM=CCLC 098,Reach-1         ,3812
     755    1021    1239     493    1489    4496    2148
Boundary for River Rch & Prof#=CCLC 098,Reach-1         , 1
Up Type= 0
Dn Type= 3
Dn Slope=0.005
Boundary for River Rch & Prof#=CCLC 098,Reach-1         , 2
Up Type= 0
Dn Type= 3
Dn Slope=0.005
Boundary for River Rch & Prof#=CCLC 098,Reach-1         , 3
Up Type= 0
Dn Type= 3
Dn Slope=0.005
Boundary for River Rch & Prof#=CCLC 098,Reach-1         , 4
Up Type= 0
Dn Type= 3
Dn Slope=0.005
Boundary for River Rch & Prof#=CCLC 098,Reach-1         , 5
Up Type= 0
Dn Type= 3
Dn Slope=0.005
Boundary for River Rch & Prof#=CCLC 098,Reach-1         , 6
Up Type= 0
Dn Type= 3
Dn Slope=0.005
Boundary for River Rch & Prof#=CCLC 098,Reach-1         , 7
Up Type= 0
Dn Type= 3
Dn Slope=0.005
DSS Import GetInterval= 0
DSS Import GetPeak= 0
DSS Import FillOption= 0

--- CCLC 098.g01 (geometry) ---

Geom Title=Existing Conditions
Program Version=4.10

River Reach=CCLC 098        ,Reach-1
Reach XY= 30
      3698739.34      10208108.1      3698762.77     10208248.56
      3698807.91     10208225.99      3698833.09     10208245.95
      3698828.75     10208306.72      3698998.23     10208446.84
      3699068.23     10208586.84      3699268.23     10208606.84
      3699448.23     10208736.84      3699538.23     10208576.84
      3699568.23     10208566.84      3699608.23     10208606.84
      3699768.23     10208376.84      3699938.23     10208346.84
      3700028.23     10208436.84      3700128.23     10208476.84
      3700458.23     10208926.84      3700738.23     10209006.84
      3700818.23     10209146.84      3700908.23     10209156.84
      3701098.23     10209246.84      3701118.23     10209166.84
      3701278.23     10209096.84      3701405.42     10209230.73
       3701416.1     10209324.61      3701353.36       10209425.
      3701343.32     10209622.45      3701302.32     10209686.87
       3701406.9     10209800.65      3701802.43      10209912.5

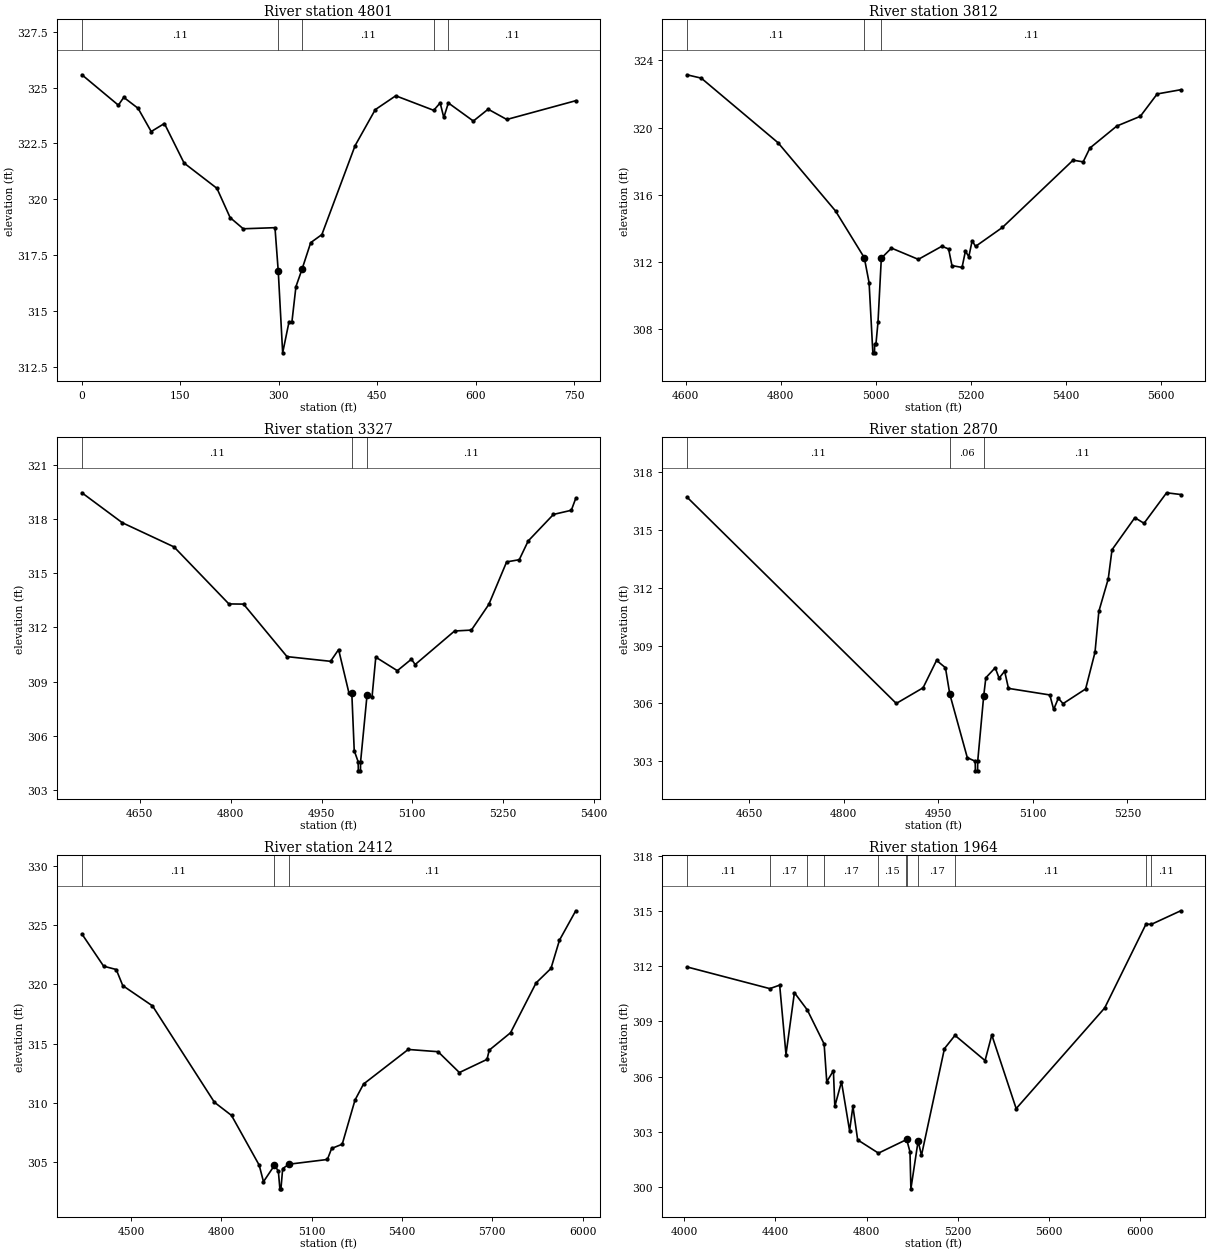
Type RM Length L Ch R = 1 ,4801    ,989,989,989
BEGIN DESCRIPTION:
CCLC 098 8.0
END DESCRIPTION:
XS GIS Cut Line= 3
      3698522.41     10208328.98      3698841.86     10208315.09
      3699031.69     10207926.76
#Sta/Elev= 30
       0  325.57    55.5  324.21    63.7  324.56    85.5  324.07   105.5  323.03
   125.6  323.39   155.6  321.62   205.6  320.49   225.7  319.18   245.7  318.68
     294  318.73     299  316.77   305.7  313.13   315.2  314.49   319.7  314.49
   325.9  316.09   335.4  316.89   348.4  318.06   365.4  318.42     416   322.4
   446.7  324.01   477.9  324.63   535.7  323.98   545.5  324.31   551.1  323.66
     558  324.31   596.1   323.5   618.6  324.03     647  323.57     752  324.41
#Mann= 5 ,-1 , 0
       0     .11       0     299     .07       0   335.4     .11       0
   535.7     .11       0     558     .11       0
Bank Sta=299,335.4
XS Rating Curve= 0 ,0
Exp/Cntr=0.3,0.1

Type RM Length L Ch R = 1 ,3812    ,485,485,485
BEGIN DESCRIPTION:
CCLC 098 7.0
END DESCRIPTION:
XS GIS Cut Line= 3
      3699567.85     10209011.03      3699518.23     10208616.84
      3699067.82     10208161.04
#Sta/Elev= 30
  4602.7  323.15  4632.9  322.95  4794.2  319.11  4915.1  315.05  4975.6  312.27
  4985.7  310.78  4993.6  306.61  4997.1  306.61  4997.3  307.11    5000  307.11
  5004.4  308.43  5011.4  312.24  5032.7  312.84  5089.2  312.17  5138.7  312.95
  5152.8  312.79  5159.9   311.8  5181.1  311.69  5188.2  312.66  5195.3  312.33
  5202.4  313.28  5209.4  312.94    5266  314.07  5414.5  318.07  5435.7  317.97
  5449.8  318.79  5506.4   320.1  5555.9  320.68  5591.3  322.01  5640.8  322.26
#Mann= 3 ,-1 , 0
  4602.7     .11       0  4975.6     .07       0  5011.4     .11       0
Bank Sta=4975.6,5011.4
XS Rating Curve= 0 ,0
Exp/Cntr=0.3,0.1

Type RM Length L Ch R = 1 ,3327    ,457,457,457
BEGIN DESCRIPTION:
CCLC 098 6.0
END DESCRIPTION:
XS GIS Cut Line= 3
      3699717.85     10208811.09      3699818.23     10208376.84
      3699517.89      10208161.1
#Sta/Elev= 30
  4554.3  319.46    4621   317.8  4706.4  316.46    4797   313.3  4821.2  313.29
    4893  310.38  4964.9  310.12  4978.2  310.77  4995.3  308.36    5000  308.36
    5004  305.17  5010.5  304.55  5010.8  304.05  5014.3  304.05  5014.5  304.55
  5025.1  308.23  5033.4  308.14  5039.6  310.35  5075.2   309.6  5098.5  310.24
  5104.6  309.94  5169.7   311.8  5197.5  311.85  5226.2  313.27  5255.7  315.63
  5276.5  315.75  5291.3  316.79    5333  318.26  5362.5  318.49  5369.8  319.15
#Mann= 3 ,-1 , 0
  4554.3     .11       0    5000     .07       0  5025.1     .11       0
Bank Sta=5000,5025.1
XS Rating Curve= 0 ,0
Exp/Cntr=0.3,0.1

Type RM Length L Ch R = 1 ,2870    ,458,458,458
BEGIN DESCRIPTION:
CCLC 098 5.0
END DESCRIPTION:
XS GIS Cut Line= 3
      3699867.88     10208861.04      3700178.23     10208536.84
      3700367.87     10208261.05
#Sta/Elev= 30
  4551.2  316.69  4883.4     306  4925.9  306.81  4947.3  308.23  4961.4  307.85
  4968.3  306.48  4996.1  303.19  5008.6  303.01  5008.9  302.51  5012.4  302.51
  5012.6  303.01 5022.06306.3786  5025.5  307.33  5040.4  307.85  5046.5  307.31
  5055.3  307.67  5061.4  306.78    5127  306.44  5133.1  305.69  5140.5  306.27
    5148  305.99  5183.8  306.75  5198.7  308.65  5204.8  310.77  5219.7  312.45
  5225.7  313.96  5261.9  315.62  5276.5  315.33  5312.3  316.91  5334.7  316.82
#Mann= 3 ,-1 , 0
  4551.2     .11       0  4968.3     .06       0 5022.06     .11       0
Bank Sta=4968.3,5022.06
XS Rating Curve= 0 ,0
Exp/Cntr=0.3,0.1

Type RM Length L Ch R = 1 ,2412    ,448,448,448
BEGIN DESCRIPTION:
CCLC 098 4.0
END DESCRIPTION:
XS GIS Cut Line= 3
      3699943.14     10209327.81      3700438.23     10208886.84
      3701109.84     10208176.74
#Sta/Elev= 30
    4337  324.25  4409.2  321.53    4451  321.25  4472.7  319.89  4571.4  318.18
  4777.1  310.04  4833.9  308.93  4925.9  304.73  4940.1  303.33  4976.7304.7201
  4989.5  304.23  4994.6  302.73  4998.1  302.73  5003.9  304.44  5024.9  304.81
  5152.4  305.21  5166.5  306.14  5201.7   306.5  5244.2  310.23  5272.5  311.58
    5421   314.5  5520.1  314.31  5590.9  312.55  5682.7  313.66    5690  314.44
  5760.8  315.91  5845.7  320.12  5895.1  321.34  5923.4  323.73  5977.4  326.21
#Mann= 3 ,-1 , 0
    4337     .11       0  4976.7     .07       0  5024.9     .11       0
Bank Sta=4976.7,5024.9
XS Rating Curve= 0 ,0
Exp/Cntr=0.3,0.1

Type RM Length L Ch R = 1 ,1964    ,137,137,137
BEGIN DESCRIPTION:
CCLC 098 3.0
END DESCRIPTION:
XS GIS Cut Line= 3
      3700187.93     10209869.49      3700778.23     10209076.84
      3701463.44     10208120.23
#Sta/Elev= 30
  4011.7  311.96  4375.2  310.78  4418.4  310.97  4446.1   307.2    4483  310.56
  4539.6  309.62  4613.3  307.77  4624.8  305.72    4654  306.32  4660.2  304.38
  4689.4  305.72  4724.9  303.06  4739.5  304.38  4760.3  302.56  4851.5  301.84
  4973.4  302.57  4975.1  302.59  4989.7  301.91  4993.7   299.9  5025.3   302.5
  5040.1  301.72  5140.8  307.52    5187  308.24  5318.9  306.87  5348.4  308.26
  5455.3  304.26  5843.4  309.73  6024.6  314.29  6047.4  314.27  6176.7  315.01
#Mann= 11 ,-1 , 0
  4011.7     .11       0  4375.2     .17       0  4539.6     .11       0
  4613.3     .17       0  4851.5     .15       0  4973.4     .17       0
  4975.1     .09       0  5025.3     .17       0    5187     .11       0
  6024.6     .17       0  6047.4     .11       0
Bank Sta=4975.1,5025.3
XS Rating Curve= 0 ,0
Exp/Cntr=0.3,0.1

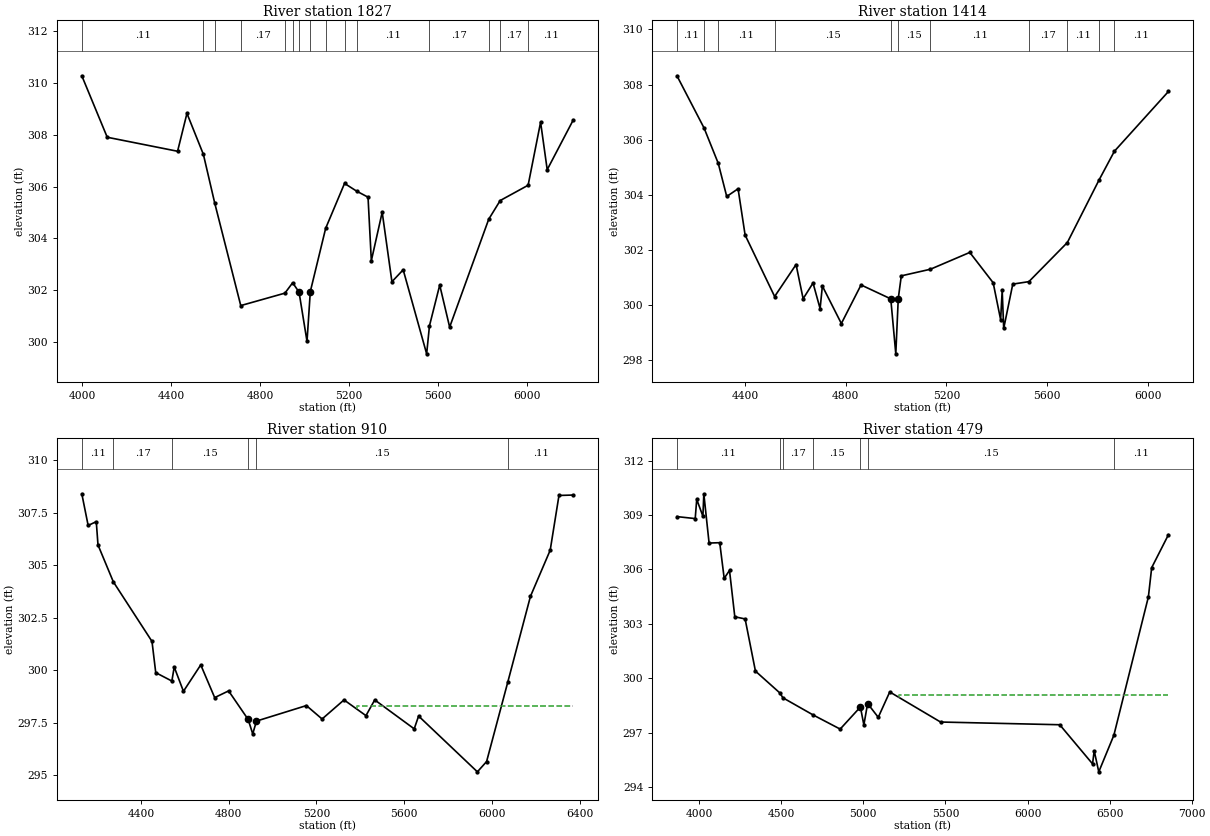
Type RM Length L Ch R = 1 ,1827    ,413,413,413
BEGIN DESCRIPTION:
Mapping XS b648216e
END DESCRIPTION:
XS GIS Cut Line= 2
      3700286.91     10209978.83      3701547.34     10208166.31
#Sta/Elev= 30
  3998.8  310.27    4113   307.9    4429  307.36  4471.1  308.82  4544.9  307.24
  4596.2  305.35  4712.8  301.41  4911.1  301.89  4945.9  302.29  4974.6  301.93
  5010.4  300.03  5025.2  301.95  5094.2  304.39    5179  306.12  5233.8  305.82
  5284.5  305.59  5299.3  303.14  5348.1  305.01  5391.8  302.33  5442.4  302.79
  5547.8  299.55  5560.4  300.63  5606.5   302.2  5651.1  300.58  5826.6  304.74
  5878.2  305.46  6003.6  306.05  6059.6  308.48  6089.3  306.65  6206.5  308.57
#Mann= 15 ,-1 , 0
  3998.8     .11       0  4544.9     .17       0  4596.2     .11       0
  4712.8     .17       0  4911.1     .15       0  4945.9     .17       0
  4974.6     .09       0  5025.2     .17       0  5094.2     .11       0
    5179     .17       0  5233.8     .11       0  5560.4     .17       0
  5826.6     .11       0  5878.2     .17       0  6003.6     .11       0
Bank Sta=4974.6,5025.2
XS Rating Curve= 0 ,0
Exp/Cntr=0.3,0.1

Type RM Length L Ch R = 1 ,1414    ,504,504,504
BEGIN DESCRIPTION:
Mapping XS 5a31fd21
END DESCRIPTION:
XS GIS Cut Line= 4
      3700548.45     10209634.82      3701168.05     10209331.61
      3701105.43     10208870.24      3701553.24     10208208.41
#Sta/Elev= 30
  4128.4  308.32  4236.5  306.42  4292.8  305.14  4326.4  303.94  4371.5  304.22
  4399.5  302.54  4516.9  300.31  4602.1  301.47  4630.2  300.23  4669.6   300.8
  4697.7  299.87  4706.7  300.69  4782.2  299.33  4860.5  300.73  4978.7300.2254
  4998.7  298.23  5008.5300.2347  5020.6  301.06  5136.4   301.3  5292.9  301.91
  5385.9  300.81  5415.6  299.47  5421.8  300.53  5427.8  299.15  5463.9  300.76
    5528  300.85    5681  302.27  5806.5  304.53  5867.9  305.58  6082.9  307.75
#Mann= 11 ,-1 , 0
  4128.4     .11       0  4236.5     .17       0  4292.8     .11       0
  4516.9     .15       0  4978.7     .09       0  5008.5     .15       0
  5136.4     .11       0    5528     .17       0    5681     .11       0
  5806.5     .17       0  5867.9     .11       0
Bank Sta=4978.7,5008.5
XS Rating Curve= 0 ,0
Exp/Cntr=0.3,0.1

Type RM Length L Ch R = 1 ,910     ,431,431,431
BEGIN DESCRIPTION:
CCLC 098 2.0
END DESCRIPTION:
XS GIS Cut Line= 3
      3700557.74     10209655.93      3701568.15     10209322.59
      3701578.57     10208145.81
#Sta/Elev= 30
  4130.6  308.41  4159.5   306.9  4196.6  307.08  4204.4  305.97  4274.4  304.21
  4450.6  301.37  4467.7  299.88  4541.2  299.48  4551.9  300.15    4594  298.99
  4672.9  300.25  4736.4  298.69  4799.9  299.01  4888.9  297.65  4909.9  296.96
  4926.9  297.57  5154.5  298.31  5226.1  297.67  5326.1  298.58  5426.1  297.83
  5466.1  298.58  5646.1   297.2  5666.1  297.81  5934.1  295.15  5976.1  295.64
    6073  299.44  6176.1  303.52  6266.1  305.72  6306.1  308.33  6371.4  308.35
#Mann= 6 ,-1 , 0
  4130.6     .11       0  4274.4     .17       0  4541.2     .15       0
  4888.9     .09       0  4926.9     .15       0    6073     .11       0
#XS Ineff= 2 , 0
                         5384.89          298.29
Permanent Ineff=
       F       F
Bank Sta=4888.9,4926.9
XS Rating Curve= 0 ,0
Exp/Cntr=0.3,0.1

Type RM Length L Ch R = 1 ,479     ,0,0,0
BEGIN DESCRIPTION:
CCLC 098 1.0
END DESCRIPTION:
XS GIS Cut Line= 3
      3700281.69     10210093.43      3701656.69     10209661.14
      3701620.23     10208109.02
#Sta/Elev= 30
  3864.6  308.92  3975.9  308.81  3985.1  309.87  4022.8  308.94  4028.3  310.18
  4060.4  307.46  4125.2  307.48  4152.4  305.51  4184.8  305.95    4217  303.39
  4279.9  303.27  4342.8  300.39  4492.1  299.18  4509.6  298.92  4694.2  297.97
  4858.9  297.19  4982.2  298.41  5003.2  297.42  5026.1   298.6  5090.9  297.84
  5160.9  299.24  5470.3  297.58  6196.3  297.43  6396.3  295.27  6406.3  295.99
  6434.2  294.83  6526.1  296.85  6736.4  304.49  6756.4   306.1  6858.5  307.92
#Mann= 7 ,-1 , 0
  3864.6     .11       0  4492.1     .15       0  4509.6     .17       0
  4694.2     .15       0  4982.2     .09       0  5026.1     .15       0
  6526.1     .11       0
#XS Ineff= 2 , 0
                         5218.75          299.07
Permanent Ineff=
       F       F
Bank Sta=4982.2,5026.1
XS Rating Curve= 0 ,0
Exp/Cntr=0.3,0.1

Chan Stop Cuts=-1
Use User Specified Reach Order=0
Composite Channel Slope=5