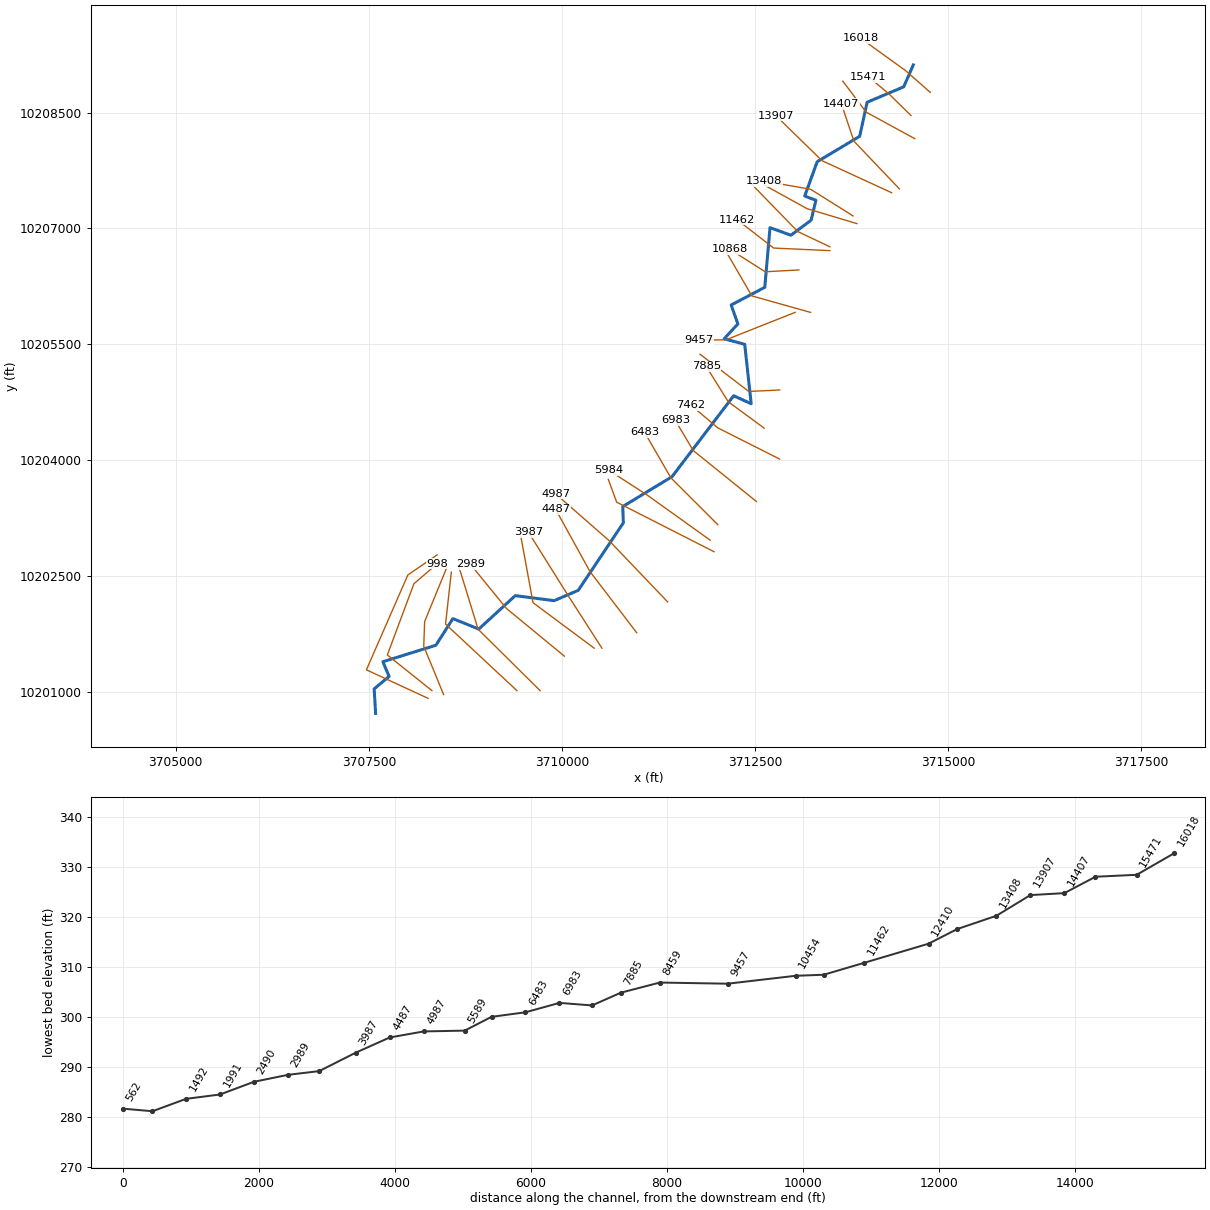
--- CCLC 099.prj (project) ---

Proj Title=CCLC 099 Base Level Engineering
Current Plan=p01
Default Exp/Contr=0.3,0.1
English Units
Geom File=g01
Flow File=f01
Flow File=f02
Plan File=p01
Y Axis Title=Elevation
X Axis Title(PF)=Main Channel Distance
X Axis Title(XS)=Station
BEGIN DESCRIPTION:
CCLC 099
END DESCRIPTION:
DSS Export Rating Curves= 0
DSS Export Rating Curve Sorted= 0
DSS Export Volume Flow Curves= 0
DXF OffsetX= 0
DXF OffsetY= 0
DXF ScaleX= 1
DXF ScaleY= 10

--- CCLC 099.p01 (plan) ---

Plan Title=Multiple Run
Short Identifier=Multiple
Geom File=g01
Flow File=f01
Subcritical Flow
K Sum by GR= 0
Std Step Tol= 0.01
Critical Tol= 0.01
Num of Std Step Trials= 20
Max Error Tol= 0.3
Flow Tol Ratio= 0.001
Split Flow NTrial= 30
Split Flow Tol= 0.02
Split Flow Ratio= 0.02
Log Output Level= 0
Friction Slope Method= 1
Unsteady Friction Slope Method= 2
Unsteady Bridges Friction Slope Method= 1
Parabolic Critical Depth
Global Vel Dist=  1 , 1 , 1
Global Log Level= 0
CheckData=True
Encroach Param= -1, 0, 0, 0
BEGIN DESCRIPTION:
Multiple Run
END DESCRIPTION:

--- CCLC 099.f01 (steady flow) ---

Flow Title=Multiple
Program Version=4.10
Number of Profiles= 7
Profile Names=10-year,25-year,50-year,1pct_min,100-year,1pct_plu,500-year
River Rch & RM=CCLC 099,Reach-1         ,16018
     682     928    1258     561    1694    5116    3175
River Rch & RM=CCLC 099,Reach-1         ,12410
    1066    1480    2033     917    2768    8359    5310
River Rch & RM=CCLC 099,Reach-1         ,1991
    1048    1448    1984     891    2691    8127    5126
Boundary for River Rch & Prof#=CCLC 099,Reach-1         , 1
Up Type= 0
Dn Type= 3
Dn Slope=0.005
Boundary for River Rch & Prof#=CCLC 099,Reach-1         , 2
Up Type= 0
Dn Type= 3
Dn Slope=0.005
Boundary for River Rch & Prof#=CCLC 099,Reach-1         , 3
Up Type= 0
Dn Type= 3
Dn Slope=0.005
Boundary for River Rch & Prof#=CCLC 099,Reach-1         , 4
Up Type= 0
Dn Type= 3
Dn Slope=0.005
Boundary for River Rch & Prof#=CCLC 099,Reach-1         , 5
Up Type= 0
Dn Type= 3
Dn Slope=0.005
Boundary for River Rch & Prof#=CCLC 099,Reach-1         , 6
Up Type= 0
Dn Type= 3
Dn Slope=0.005
Boundary for River Rch & Prof#=CCLC 099,Reach-1         , 7
Up Type= 0
Dn Type= 3
Dn Slope=0.005
DSS Import GetInterval= 0
DSS Import GetPeak= 0
DSS Import FillOption= 0

--- CCLC 099.f02 (steady flow) ---

Flow Title=Orig_BLE_Flows
Program Version=4.10
Number of Profiles= 7
Profile Names=10-year,25-year,50-year,1pct_min,100-year,1pct_plu,500-year
River Rch & RM=CCLC 099,Reach-1         ,16018
     682     910    1094     431    1303    3935    1846
River Rch & RM=CCLC 099,Reach-1         ,12410
    1066    1451    1768     705    2129    6430    3087
River Rch & RM=CCLC 099,Reach-1         ,1991
    1048    1420    1725     685    2070    6251    2980
Boundary for River Rch & Prof#=CCLC 099,Reach-1         , 1
Up Type= 0
Dn Type= 3
Dn Slope=0.005
Boundary for River Rch & Prof#=CCLC 099,Reach-1         , 2
Up Type= 0
Dn Type= 3
Dn Slope=0.005
Boundary for River Rch & Prof#=CCLC 099,Reach-1         , 3
Up Type= 0
Dn Type= 3
Dn Slope=0.005
Boundary for River Rch & Prof#=CCLC 099,Reach-1         , 4
Up Type= 0
Dn Type= 3
Dn Slope=0.005
Boundary for River Rch & Prof#=CCLC 099,Reach-1         , 5
Up Type= 0
Dn Type= 3
Dn Slope=0.005
Boundary for River Rch & Prof#=CCLC 099,Reach-1         , 6
Up Type= 0
Dn Type= 3
Dn Slope=0.005
Boundary for River Rch & Prof#=CCLC 099,Reach-1         , 7
Up Type= 0
Dn Type= 3
Dn Slope=0.005
DSS Import GetInterval= 0
DSS Import GetPeak= 0
DSS Import FillOption= 0

--- CCLC 099.g01 (geometry) ---

Geom Title=Existing Conditions
Program Version=4.10

River Reach=CCLC 099        ,Reach-1
Reach XY= 30
      3714548.23     10209116.84      3714423.71      10208832.6
      3713950.76     10208633.57      3713853.58     10208192.04
       3713303.8     10207862.47      3713142.32     10207418.14
      3713287.54     10207363.69      3713225.29     10207105.32
      3712964.41     10206910.65       3712693.3     10207008.38
      3712625.57     10206236.04       3712190.5     10206006.86
      3712277.34     10205761.05      3712099.64     10205569.17
      3712365.78     10205497.27      3712449.63     10204727.94
      3712222.74     10204831.38      3711425.27      10203783.4
      3710786.88     10203395.57      3710794.94     10203184.35
      3710210.62      10202310.4      3709899.19     10202176.93
      3709395.96     10202241.82      3708922.92     10201808.52
      3708588.29     10201944.62      3708368.95     10201599.66
      3707682.39     10201385.88      3707762.78     10201195.15
      3707569.55     10201034.29      3707588.23     10200716.84

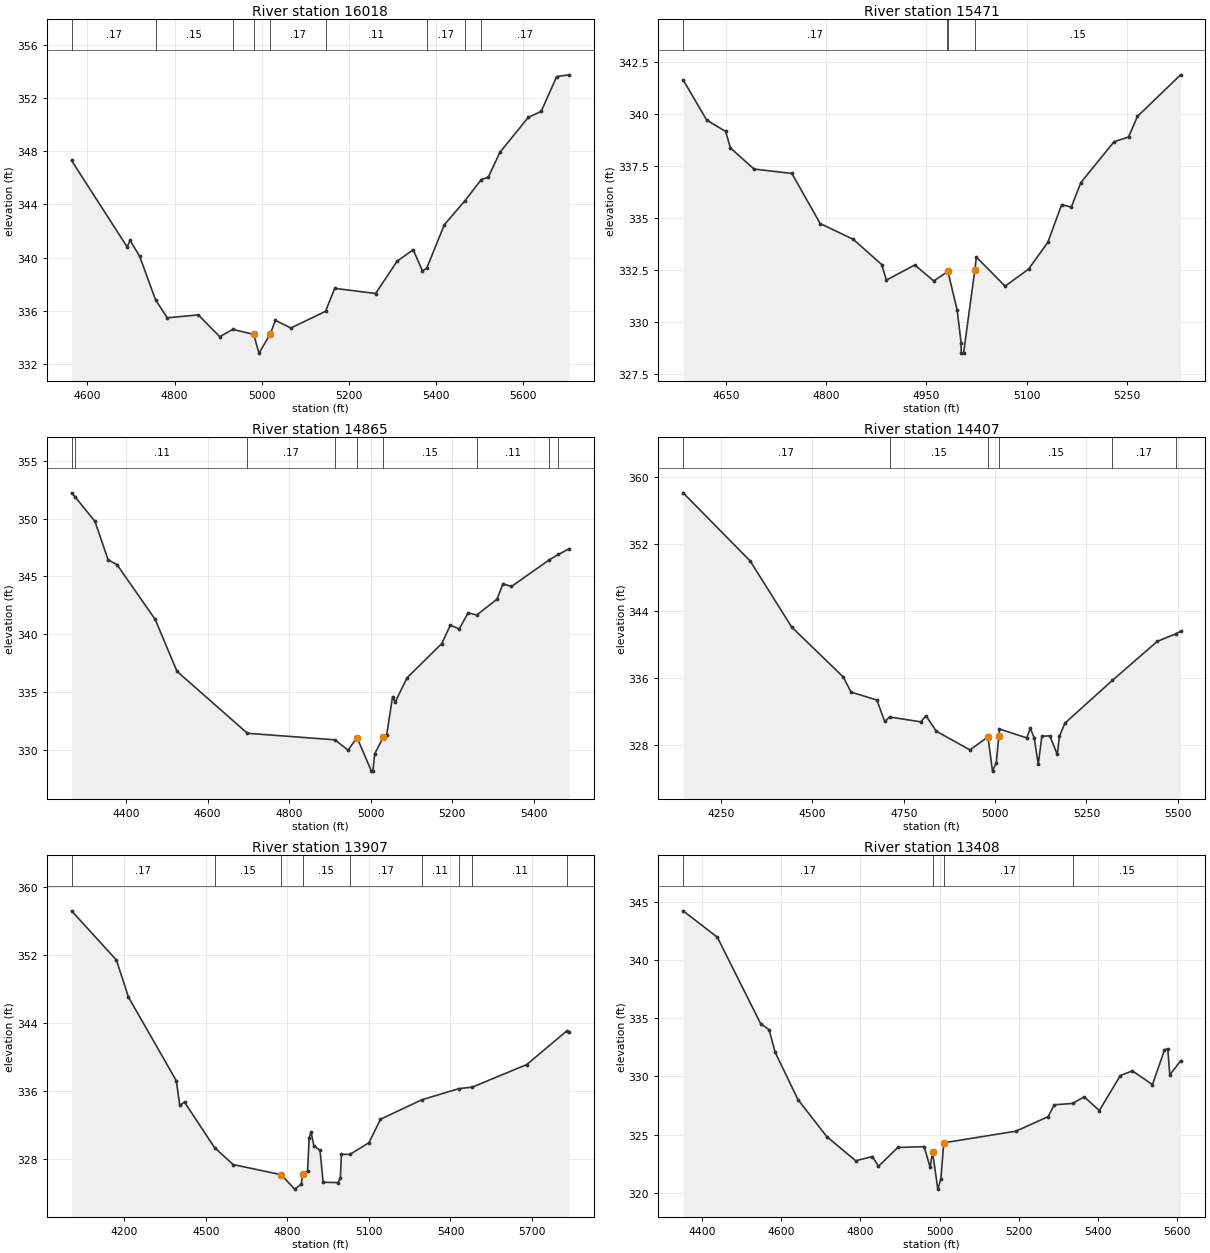
Type RM Length L Ch R = 1 ,16018   ,547,547,547
BEGIN DESCRIPTION:
CCLC 099 29.0
END DESCRIPTION:
XS GIS Cut Line= 3
      3714767.85     10208761.07      3714443.15     10209046.55
      3713867.88     10209461.05
#Sta/Elev= 30
  4563.7  347.31  4691.3   340.8    4698  341.29  4719.8  340.11  4756.4  336.82
  4783.4  335.46  4854.5  335.68  4903.8  334.04  4933.7  334.59  4981.7  334.21
  4993.9   332.8  5020.2334.2673  5031.4  335.27    5067  334.69  5146.5  335.95
  5167.6  337.68  5261.4  337.29  5310.7  339.72  5347.7  340.59  5368.9  338.99
  5378.8   339.2  5419.2  342.47  5465.6  344.25  5503.9  345.87  5519.8  346.04
  5546.8  347.93  5611.9  350.56  5641.3     351  5676.9  353.63  5705.1  353.76
#Mann= 9 ,-1 , 0
  4563.7     .17       0  4756.4     .15       0  4933.7     .17       0
  4981.7     .09       0  5020.2     .17       0  5146.5     .11       0
  5378.8     .17       0  5465.6     .11       0  5503.9     .17       0
Bank Sta=4981.7,5020.2
XS Rating Curve= 0 ,0
Exp/Cntr=0.3,0.1

Type RM Length L Ch R = 1 ,15471   ,606,606,606
BEGIN DESCRIPTION:
CCLC 099 28.0
END DESCRIPTION:
XS GIS Cut Line= 3
      3714517.82      10208461.1      3714229.61     10208744.47
      3713967.88     10208961.05
#Sta/Elev= 30
  4586.3  341.66  4621.6  339.72  4649.9  339.18  4656.9  338.39  4692.3  337.37
  4748.9  337.16  4791.3  334.75  4840.8  333.99  4883.2  332.78  4890.3  332.03
  4932.8  332.76  4961.1  331.99  4981.5  332.43  4982.2  332.46  4996.1  330.59
    5002  329.02  5002.2  328.52  5005.7  328.52 5022.61332.5302  5024.8  333.14
  5067.8  331.74  5102.9  332.56  5131.6  333.84  5152.4  335.66  5166.8  335.54
  5181.1  336.72  5230.6  338.68  5252.4  338.91  5265.7   339.9  5330.2   341.9
#Mann= 4 ,-1 , 0
  4586.3     .17       0  4981.5     .15       0  4982.2     .09       0
 5022.61     .15       0
Bank Sta=4982.2,5022.61
XS Rating Curve= 0 ,0
Exp/Cntr=0.3,0.1

Type RM Length L Ch R = 1 ,14865   ,458,458,458
BEGIN DESCRIPTION:
CCLC 099 27.0
END DESCRIPTION:
XS GIS Cut Line= 3
      3714567.86     10208161.07      3713937.94     10208504.89
      3713635.88     10208905.91
#Sta/Elev= 30
  4266.6  352.23  4276.3  351.84    4324  349.76  4356.3  346.43  4378.1  346.01
  4471.7  341.27  4525.2  336.77  4697.8  331.41  4912.5  330.84  4944.7  329.95
  4966.6  331.04    5002  328.13  5005.5  328.13    5010  329.63  5030.9  331.07
  5039.2  331.23  5053.8  334.58    5060  334.09  5089.2  336.21  5174.5  339.18
  5195.4  340.77  5217.3  340.44  5239.1  341.84  5260.1  341.65  5309.9  343.02
  5324.4  344.35  5345.3  344.12  5438.2  346.43  5460.3  346.89  5486.3  347.38
#Mann= 9 ,-1 , 0
  4266.6     .17       0  4276.3     .11       0  4697.8     .17       0
  4912.5     .15       0  4966.6     .09       0  5030.9     .15       0
  5260.1     .11       0  5438.2     .17       0  5460.3     .11       0
Bank Sta=4966.6,5030.9
XS Rating Curve= 0 ,0
Exp/Cntr=0.3,0.1

Type RM Length L Ch R = 1 ,14407   ,500,500,500
BEGIN DESCRIPTION:
CCLC 099 26.0
END DESCRIPTION:
XS GIS Cut Line= 3
      3714367.85     10207511.07      3713778.96     10208129.55
      3713617.84     10208611.11
#Sta/Elev= 30
    4146  358.16  4329.8  349.99  4443.1   342.1  4584.6  336.11  4605.7  334.31
  4676.5  333.36  4697.9  330.79    4711  331.33  4796.6  330.75  4810.8  331.48
  4839.1  329.63  4931.3  327.39  4980.6  328.95    4993  324.85  5003.4  325.86
 5010.34329.0746  5012.1  329.89  5086.8  328.83  5096.5  330.01  5107.1  328.83
  5118.3  325.67  5128.1  329.02  5149.9  329.08  5170.3  326.85  5176.2  329.03
  5191.4   330.6  5320.8   335.7  5444.5  340.39  5494.3  341.28  5507.8  341.57
#Mann= 6 ,-1 , 0
    4146     .17       0    4711     .15       0  4980.6     .09       0
 5010.34     .15       0  5320.8     .17       0  5494.3     .11       0
Bank Sta=4980.6,5010.34
XS Rating Curve= 0 ,0
Exp/Cntr=0.3,0.1

Type RM Length L Ch R = 1 ,13907   ,499,499,499
BEGIN DESCRIPTION:
CCLC 099 25.0
END DESCRIPTION:
XS GIS Cut Line= 3
      3714267.89     10207461.06      3713365.46     10207876.82
      3712767.82     10208461.11
#Sta/Elev= 30
  4006.4  357.23  4171.6  351.43  4215.6  347.08  4391.8  337.22  4404.5  334.31
    4422   334.7  4532.3  329.35    4601  327.35  4777.2  326.16  4827.1  324.46
  4851.8  325.04 4855.97326.2532  4874.7  326.59  4880.2  330.45  4887.3   331.2
  4897.7  329.56  4920.3  329.03  4931.7  325.27  4986.4  325.23    4995  325.79
  4999.1  328.56  5030.2  328.55  5100.3  329.93  5142.7  332.69  5294.3  334.98
  5431.8   336.3  5480.2  336.47  5680.2  339.12  5827.5  343.08  5835.8  342.98
#Mann= 9 ,-1 , 0
  4006.4     .17       0  4532.3     .15       0  4777.2     .09       0
 4855.97     .15       0  5030.2     .17       0  5294.3     .11       0
  5431.8     .17       0  5480.2     .11       0  5827.5     .15       0
Bank Sta=4777.2,4855.97
XS Rating Curve= 0 ,0
Exp/Cntr=0.3,0.1

Type RM Length L Ch R = 1 ,13408   ,575,575,575
BEGIN DESCRIPTION:
CCLC 099 24.0
END DESCRIPTION:
XS GIS Cut Line= 3
      3713767.86     10207161.06      3713218.53      10207505.9
      3712617.86     10207611.07
#Sta/Elev= 30
  4351.4  344.23    4438  341.96  4547.6  334.53  4568.8  334.02  4584.1  332.09
  4641.8  328.02  4714.9  324.83  4787.9  322.76  4830.3  323.12  4845.6  322.28
  4894.5   323.9  4961.1  323.97  4976.4  322.18  4982.3  323.55  4995.7  320.32
  5003.4  321.17  5010.8   324.3  5193.6   325.3  5274.8  326.55  5290.5  327.57
  5336.7  327.68  5366.2  328.25  5404.3  327.07  5457.5  330.08    5488  330.48
  5538.7   329.3  5569.2  332.28  5577.5  332.39  5582.6  330.14  5609.8  331.33
#Mann= 4 ,-1 , 0
  4351.4     .17       0  4982.3     .09       0  5010.8     .17       0
  5336.7     .15       0
Bank Sta=4982.3,5010.8
XS Rating Curve= 0 ,0
Exp/Cntr=0.3,0.1

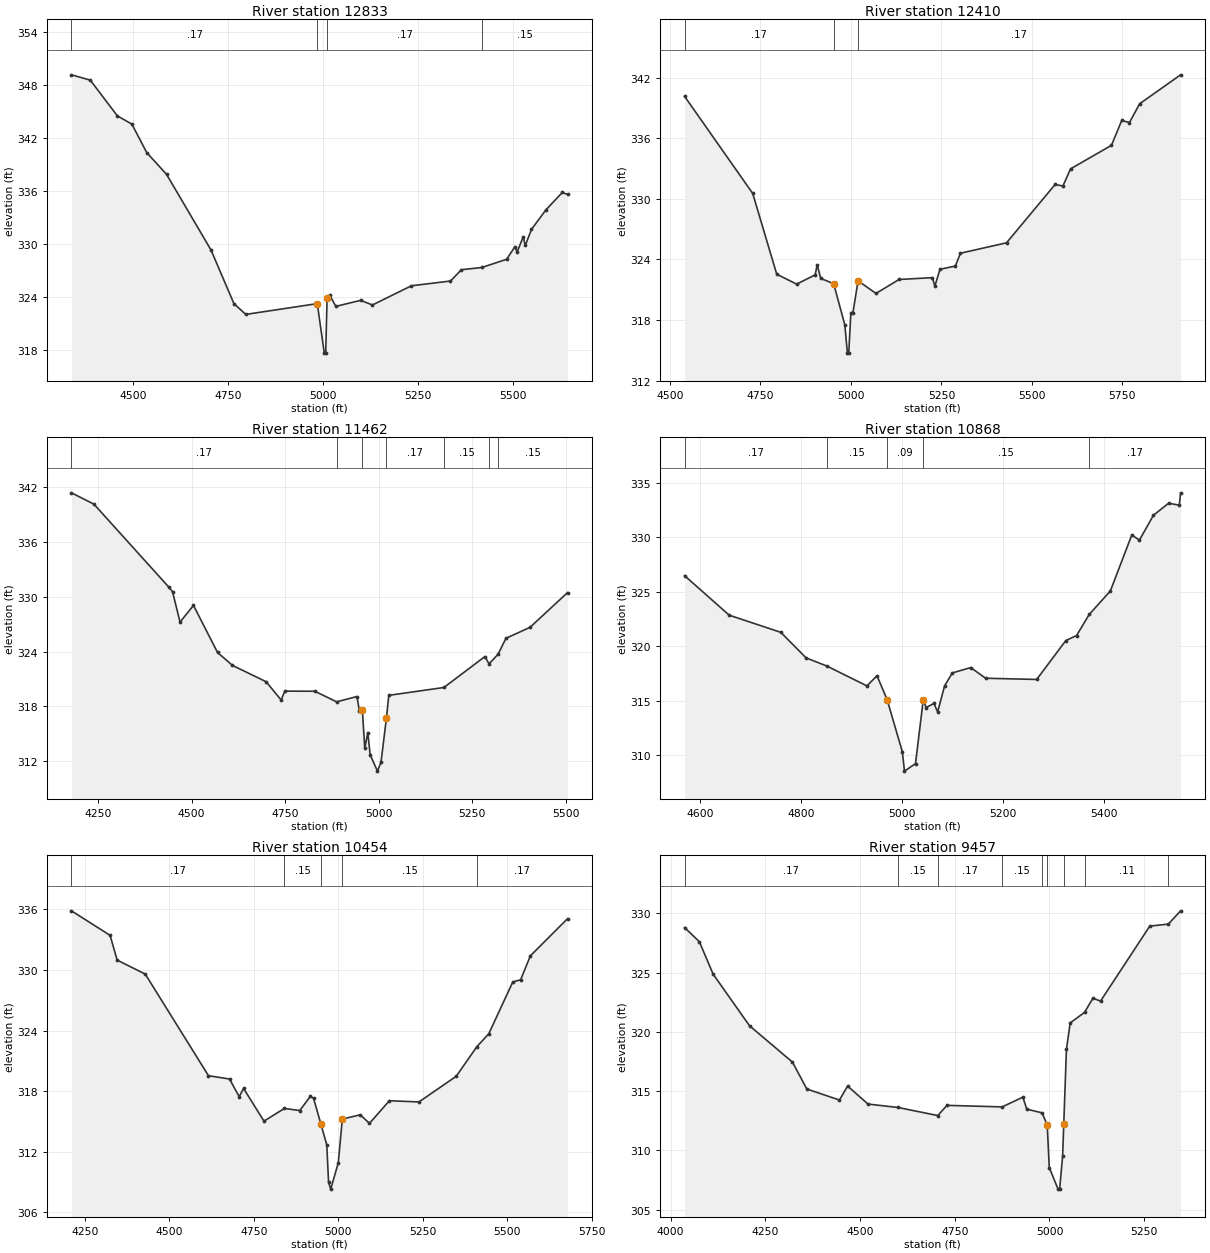
Type RM Length L Ch R = 1 ,12833   ,423,423,423
BEGIN DESCRIPTION:
CCLC 099 23.0
END DESCRIPTION:
XS GIS Cut Line= 3
      3713817.84     10207061.07      3713172.32     10207254.89
      3712617.84     10207561.08
#Sta/Elev= 30
    4337  349.16  4386.6  348.56  4457.9  344.52  4496.2  343.58  4535.4  340.36
  4587.6   337.9  4704.9  329.33  4765.1  323.28  4796.4  322.05  4984.9  323.27
  5003.4  317.67  5007.1  317.67  5010.7  323.88  5017.6  324.25  5033.7  322.96
    5099  323.64  5130.3  323.12  5233.1  325.29    5336  325.83  5364.8  327.11
  5418.6  327.36    5484  328.29  5505.8  329.71  5511.5  329.09  5527.5  330.81
  5533.2  329.85  5549.3  331.66  5587.1  333.86  5630.6  335.85  5644.4  335.63
#Mann= 4 ,-1 , 0
    4337     .17       0  4984.9     .09       0  5010.7     .17       0
  5418.6     .15       0
Bank Sta=4984.9,5010.7
XS Rating Curve= 0 ,0
Exp/Cntr=0.3,0.1

Type RM Length L Ch R = 1 ,12410   ,948,948,948
BEGIN DESCRIPTION:
CCLC 099 22.0
END DESCRIPTION:
XS GIS Cut Line= 3
      3713467.87     10206761.06      3713052.68     10206957.94
      3712417.87     10207611.05
#Sta/Elev= 30
  4540.5  340.15  4728.7  330.54  4795.1  322.54  4850.2  321.56  4901.3  322.48
  4906.8  323.47  4916.8  322.12  4952.3  321.61  4983.2  317.52  4990.3  314.73
    4994  314.73  4999.9  318.74  5005.7  318.74  5019.7  321.89  5069.3  320.64
  5132.9  322.02  5224.9   322.2  5231.9  321.36    5246  323.03  5288.5  323.35
  5302.6  324.62  5429.9  325.65  5564.2  331.43  5585.6  331.27  5606.7  332.97
  5719.8   335.3  5748.1  337.76  5769.5  337.56  5797.8  339.42  5910.8  342.28
#Mann= 3 , 0 , 0
  4540.5     .17       0  4952.3     .09       0  5019.7     .17       0
Bank Sta=4952.3,5019.7
XS Rating Curve= 0 ,0
Exp/Cntr=0.3,0.1

Type RM Length L Ch R = 1 ,11462   ,594,594,594
BEGIN DESCRIPTION:
CCLC 099 21.0
END DESCRIPTION:
XS GIS Cut Line= 3
      3713467.89     10206711.07      3712740.03     10206744.47
      3712267.87     10207111.06
#Sta/Elev= 30
  4178.7  341.38  4238.8  340.14    4439  331.05    4449  330.55    4469  327.22
    4505  329.05  4569.2   323.9  4609.2  322.48  4699.3  320.69  4739.3  318.69
  4749.3  319.66  4829.4  319.65  4887.7  318.49  4942.1  319.07  4948.5  317.52
  4956.6  317.58    4963  313.39  4971.1  315.13  4977.4  312.69  4996.9   310.9
  5006.4  311.87  5020.9  316.71  5027.2   319.2  5174.6  320.06  5284.3  323.45
  5295.3  322.65  5319.3  323.69  5340.5  325.45  5404.6  326.64  5505.1  330.45
#Mann= 7 ,-1 , 0
  4178.7     .17       0  4887.7     .15       0  4956.6     .09       0
  5020.9     .17       0  5174.6     .15       0  5295.3     .17       0
  5319.3     .15       0
Bank Sta=4956.6,5020.9
XS Rating Curve= 0 ,0
Exp/Cntr=0.3,0.1

Type RM Length L Ch R = 1 ,10868   ,414,414,414
BEGIN DESCRIPTION:
CCLC 099 20.0
END DESCRIPTION:
XS GIS Cut Line= 3
      3713067.81     10206461.07      3712630.65     10206437.18
      3712172.55      10206728.7
#Sta/Elev= 30
    4570  326.47  4658.3  322.84  4760.2  321.27  4810.3  318.92  4850.9  318.18
  4930.5  316.35  4950.5  317.28  4970.6  315.07  5000.6  310.29  5004.8  308.52
  5026.6  309.21  5041.9  315.05  5047.8  314.36    5063  314.74  5070.4  313.96
  5084.2  316.36  5099.5  317.54  5135.9  318.03  5165.2  317.05  5266.2  316.94
  5323.8  320.51    5345  320.97  5370.1  322.91  5411.9  325.07  5454.2   330.2
  5469.4  329.74  5497.1  332.02    5527  333.12  5548.2  332.95  5550.8  334.08
#Mann= 5 ,-1 , 0
    4570     .17       0  4850.9     .15       0  4970.6     .09       0
  5041.9     .15       0  5370.1     .17       0
Bank Sta=4970.6,5041.9
XS Rating Curve= 0 ,0
Exp/Cntr=0.3,0.1

Type RM Length L Ch R = 1 ,10454   ,997,997,997
BEGIN DESCRIPTION:
CCLC 099 19.0
END DESCRIPTION:
XS GIS Cut Line= 3
      3713217.88     10205911.06      3712458.25     10206124.68
      3712117.87     10206711.05
#Sta/Elev= 30
  4210.9  335.86  4325.2  333.43    4346  330.98  4429.1   329.6  4616.1  319.54
  4678.4  319.21    4707  317.46  4719.9  318.28  4780.3  315.04  4840.7   316.3
  4886.1  316.09  4917.3  317.49  4926.9   317.3  4948.5  314.77  4966.1  312.68
  4971.3     309  4977.6  308.31    5000  310.91    5012  315.24    5065  315.67
  5092.3  314.82  5151.1  317.06  5238.6  316.94  5348.9  319.48  5410.1  322.42
    5445  323.68  5516.2  328.82  5539.3  329.03  5568.3  331.41    5678  335.08
#Mann= 5 ,-1 , 0
  4210.9     .17       0  4840.7     .15       0  4948.5     .09       0
    5012     .15       0  5410.1     .17       0
Bank Sta=4948.5,5012
XS Rating Curve= 0 ,0
Exp/Cntr=0.3,0.1

Type RM Length L Ch R = 1 ,9457    ,998,998,998
BEGIN DESCRIPTION:
CCLC 099 18.0
END DESCRIPTION:
XS GIS Cut Line= 3
      3713017.81     10205911.05      3712122.62      10205555.8
      3711776.45     10205551.76
#Sta/Elev= 30
  4036.9  328.81    4076  327.61  4112.2  324.88  4208.3  320.52  4321.7  317.45
  4359.6  315.18  4445.7  314.25  4467.2  315.43    4521  313.91  4600.6  313.62
  4705.2  312.94  4729.5   313.8  4875.1  313.67  4929.8  314.49  4940.1  313.48
  4980.5  313.17  4994.1  312.14  4999.5  308.55  5022.7  306.73  5026.9  306.73
  5034.8  309.54 5037.75312.1893  5044.8  318.52  5054.8  320.76  5092.7  321.65
  5114.8  322.85  5134.8   322.6  5264.8  328.93  5313.9   329.1  5346.2  330.22
#Mann= 9 ,-1 , 0
  4036.9     .17       0  4600.6     .15       0  4705.2     .17       0
  4875.1     .15       0  4980.5     .17       0  4994.1     .09       0
 5037.75     .17       0  5092.7     .11       0  5313.9     .17       0
Bank Sta=4994.1,5037.75
XS Rating Curve= 0 ,0
Exp/Cntr=0.3,0.1

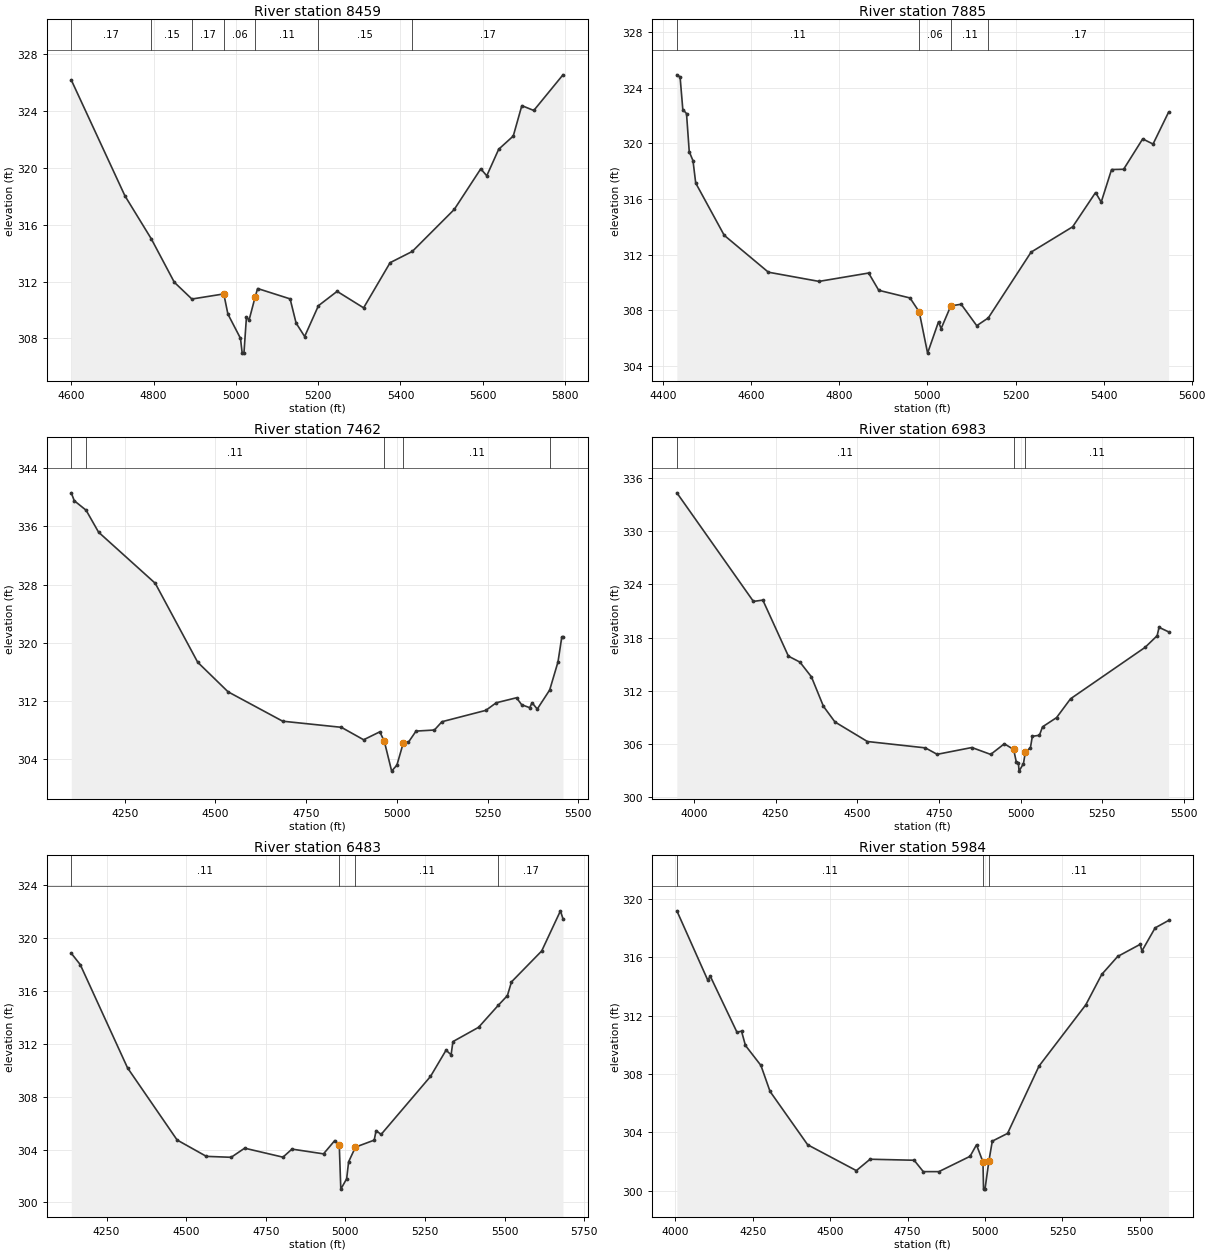
Type RM Length L Ch R = 1 ,8459    ,574,574,574
BEGIN DESCRIPTION:
CCLC 099 17.0
END DESCRIPTION:
XS GIS Cut Line= 3
       3712818.1     10204905.93      3712418.46     10204886.78
       3711786.9     10205369.47
#Sta/Elev= 30
  4599.9   326.2  4730.3  318.04  4794.4  315.01  4850.4  311.95  4893.1  310.77
  4970.6  311.13  4980.6  309.71  5011.2     308  5015.3  306.96  5019.6  306.96
  5025.7  309.51    5032  309.28  5046.5  310.88  5052.8  311.51  5131.8  310.78
  5146.3  309.08  5167.1  308.13  5200.6   310.3    5246  311.31  5310.4  310.15
  5374.8  313.33  5428.6  314.12  5530.7  317.08  5595.1  319.94  5609.7  319.45
  5638.7  321.32  5674.1  322.25  5694.9  324.39    5724  324.05  5794.9  326.56
#Mann= 7 ,-1 , 0
  4599.9     .17       0  4794.4     .15       0  4893.1     .17       0
  4970.6     .06       0  5046.5     .11       0  5200.6     .15       0
  5428.6     .17       0
Bank Sta=4970.6,5046.5
XS Rating Curve= 0 ,0
Exp/Cntr=0.3,0.1

Type RM Length L Ch R = 1 ,7885    ,423,423,423
BEGIN DESCRIPTION:
CCLC 099 16.0
END DESCRIPTION:
XS GIS Cut Line= 3
      3712617.83     10204411.09      3712151.48     10204754.89
      3711867.88     10205211.03
#Sta/Elev= 30
  4431.1  324.91  4438.4  324.76  4444.6  322.42    4453  322.13  4459.2  319.39
  4467.7  318.75  4473.9  317.14  4538.6  313.39  4638.9  310.74  4753.8  310.08
  4866.5  310.68  4889.5  309.44  4960.5  308.89  4981.4  307.89  5000.4  304.93
  5025.2  307.18  5031.1  306.69  5053.1  308.32  5076.6  308.44    5112   306.9
  5138.3  307.46  5235.4  312.18  5329.8     314  5381.8  316.46  5394.6  315.77
  5418.1  318.11  5445.5  318.13  5488.8  320.31  5512.3  319.94  5547.6  322.23
#Mann= 4 ,-1 , 0
  4431.1     .11       0  4981.4     .06       0  5053.1     .11       0
  5138.3     .17       0
Bank Sta=4981.4,5053.1
XS Rating Curve= 0 ,0
Exp/Cntr=0.3,0.1

Type RM Length L Ch R = 1 ,7462    ,479,479,479
BEGIN DESCRIPTION:
CCLC 099 15.0
END DESCRIPTION:
XS GIS Cut Line= 3
      3712817.87     10204011.06      3712016.91     10204415.32
      3711667.86     10204711.07
#Sta/Elev= 30
  4102.8  340.62  4111.2  339.53  4143.7  338.23  4178.1  335.21  4334.2  328.19
  4451.2  317.34  4534.8  313.28  4685.3  309.24    4847   308.4  4908.3  306.69
  4952.9  307.78  4965.3  306.48  4985.5  302.38    5000  303.21  5017.5  306.24
  5031.8  306.36  5052.7  307.88  5103.3  308.03  5124.1  309.17    5245  310.73
  5273.5  311.77  5329.5  312.46  5343.8   311.5  5365.8   311.1  5372.4  311.77
  5386.7  310.91  5420.9  313.53  5443.8  317.39  5454.2  320.79  5457.5  320.79
#Mann= 5 ,-1 , 0
  4102.8     .17       0  4143.7     .11       0  4965.3     .06       0
  5017.5     .11       0  5420.9     .17       0
Bank Sta=4965.3,5017.5
XS Rating Curve= 0 ,0
Exp/Cntr=0.3,0.1

Type RM Length L Ch R = 1 ,6983    ,500,500,500
BEGIN DESCRIPTION:
CCLC 099 14.0
END DESCRIPTION:
XS GIS Cut Line= 3
      3712517.85     10203461.07      3711699.18     10204121.58
      3711467.86     10204511.06
#Sta/Elev= 30
  3948.1  334.36  4182.4  322.08  4211.2  322.23  4289.5  315.89  4324.7  315.22
  4359.9  313.55  4396.7  310.22  4431.9  308.45  4531.1  306.24  4708.6  305.52
  4744.7  304.79  4850.9  305.56  4908.5  304.78  4950.3  305.98  4978.9  305.34
  4986.8  303.94  4993.3  303.83  4995.4  302.89  5008.8  303.74  5014.6  305.03
  5030.2  305.54    5036  306.83  5057.6  306.94  5067.3   307.9  5110.1  308.94
  5152.9  311.07  5380.9  316.88    5418   318.2  5423.8  319.15    5453  318.64
#Mann= 3 , 0 , 0
  3948.1     .11       0  4978.9     .06       0  5014.6     .11       0
Bank Sta=4978.9,5014.6
XS Rating Curve= 0 ,0
Exp/Cntr=0.3,0.1

Type RM Length L Ch R = 1 ,6483    ,499,499,499
BEGIN DESCRIPTION:
CCLC 099 13.0
END DESCRIPTION:
XS GIS Cut Line= 3
      3712017.82      10203161.1      3711409.03     10203769.53
      3711067.84     10204361.09
#Sta/Elev= 30
  4139.3  318.87  4167.5  318.01    4316  310.19  4471.6  304.73  4563.5  303.49
  4641.3  303.42  4683.7  304.11  4803.9  303.43  4832.2  304.04  4931.2  303.68
  4966.6  304.69  4980.7  304.33  4985.5  301.01  5003.8  301.79    5010  303.08
  5031.5  304.19  5090.4  304.72  5096.2  305.44    5112  305.15    5267  309.54
  5315.9  311.53  5331.7  311.18  5337.5  312.18  5417.9  313.26  5479.9  314.93
  5508.4  315.66  5521.3   316.7  5616.1  319.04    5675  322.08  5682.9  321.48
#Mann= 4 ,-1 , 0
  4139.3     .11       0  4980.7     .06       0  5031.5     .11       0
  5479.9     .17       0
Bank Sta=4980.7,5031.5
XS Rating Curve= 0 ,0
Exp/Cntr=0.3,0.1

Type RM Length L Ch R = 1 ,5984    ,395,395,395
BEGIN DESCRIPTION:
CCLC 099 12.0
END DESCRIPTION:
XS GIS Cut Line= 3
      3711917.88     10202961.05      3711108.95     10203540.93
      3710611.33     10203863.28
#Sta/Elev= 30
  4004.7  319.18  4104.2  314.44  4112.8  314.69  4198.8  310.86  4213.5  310.93
  4226.2  309.95  4276.2  308.58  4305.6   306.8  4427.2  303.14  4584.4  301.37
  4628.7  302.15  4771.1  302.08  4800.6   301.3    4851   301.3  4951.7  302.35
  4972.5  303.14  4993.4  301.96  4995.2   300.1  4999.9   300.1  5012.3301.9993
  5023.5  303.39  5072.8  303.92  5174.5  308.54  5325.6  312.74    5377  314.82
  5428.4  316.05  5500.9  316.88  5506.9  316.43  5549.4  318.01  5592.9  318.52
#Mann= 3 , 0 , 0
  4004.7     .11       0  4993.4     .06       0  5012.3     .11       0
Bank Sta=4993.4,5012.3
XS Rating Curve= 0 ,0
Exp/Cntr=0.3,0.1

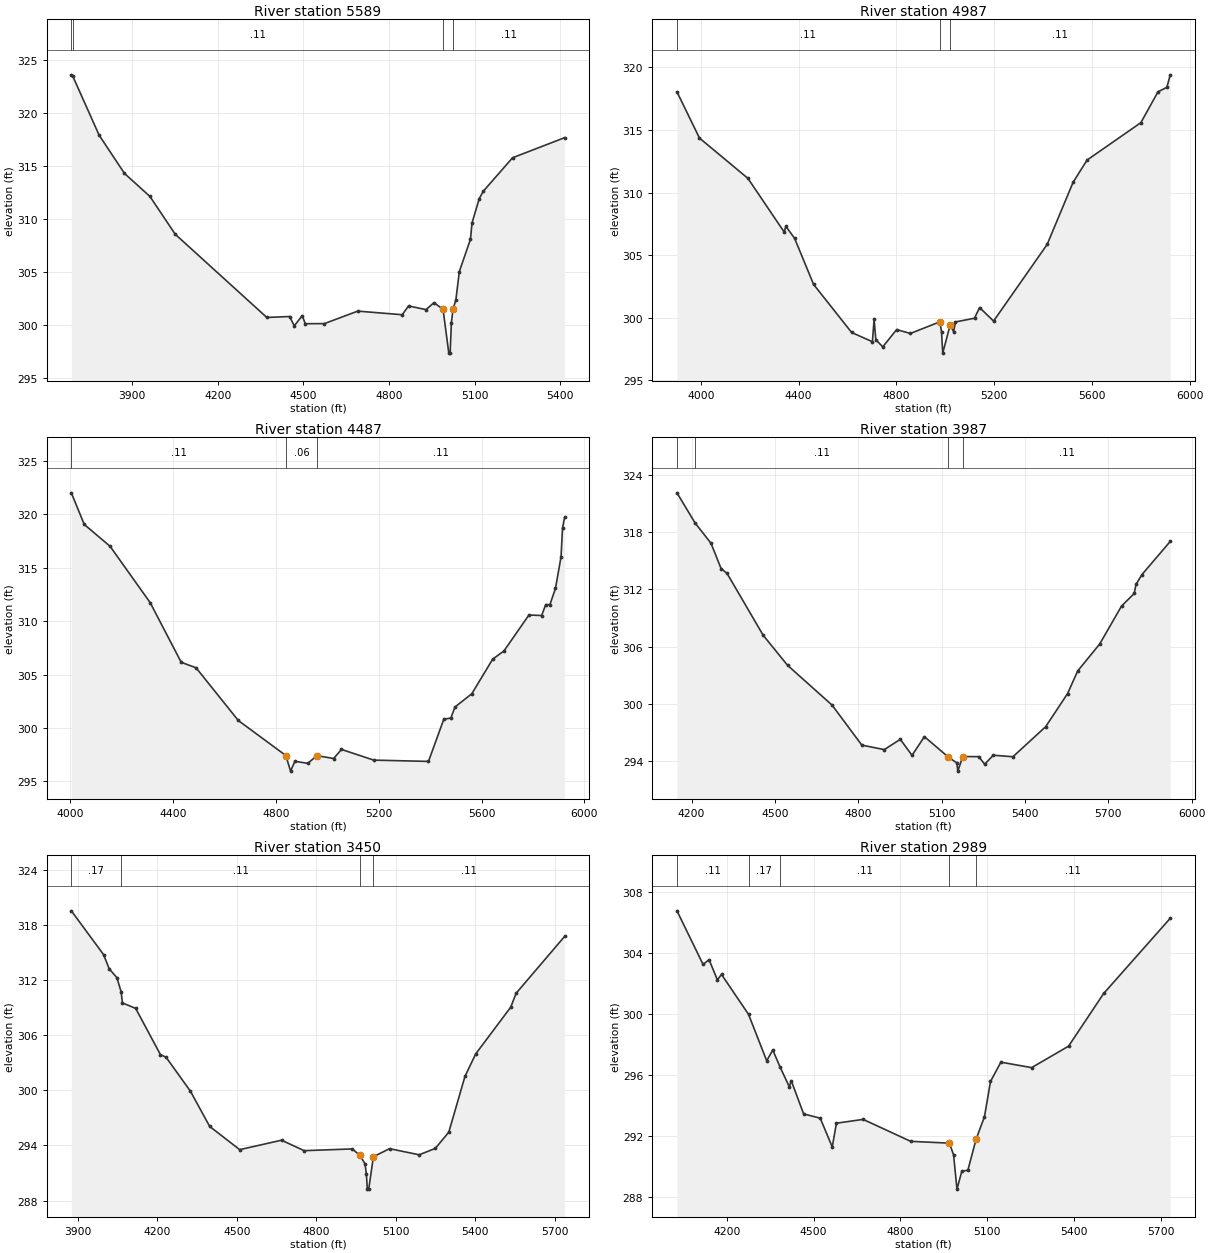
Type RM Length L Ch R = 1 ,5589    ,602,602,602
BEGIN DESCRIPTION:
CCLC 099 11.0
END DESCRIPTION:
XS GIS Cut Line= 3
      3711967.87     10202811.06      3710708.78      10203452.8
      3710600.06      10203747.9
#Sta/Elev= 30
  3687.2  323.64  3691.5  323.56  3784.5  317.94  3873.4  314.32  3962.4  312.15
  4051.3  308.57  4371.9  300.71  4451.5   300.8  4468.1  299.92    4496  300.88
  4506.6  300.12  4573.7  300.13  4690.5  301.31  4846.1  300.97  4868.4   301.8
  4929.5  301.45  4957.3  302.11  4989.2  301.48  5009.3  297.34    5014  297.34
  5018.4  300.23    5024  301.47  5034.1  302.38  5046.2  305.05  5085.1  308.09
  5090.7  309.65    5116  311.95  5130.5  312.65  5232.5   315.8  5414.9   317.7
#Mann= 4 ,-1 , 0
  3687.2     .17       0  3691.5     .11       0  4989.2     .06       0
    5024     .11       0
Bank Sta=4989.2,5024
XS Rating Curve= 0 ,0
Exp/Cntr=0.3,0.1

Type RM Length L Ch R = 1 ,4987    ,500,500,500
BEGIN DESCRIPTION:
CCLC 099 10.0
END DESCRIPTION:
XS GIS Cut Line= 3
      3711367.86     10202161.06      3710609.95     10202954.98
      3709917.83     10203561.09
#Sta/Elev= 30
  3902.4  318.05  3994.4  314.36  4192.6  311.14    4341  306.85  4347.9  307.31
  4383.5  306.35  4461.2  302.67  4616.8  298.83  4701.8  298.09  4708.7  299.87
  4715.9  298.25  4744.2  297.68  4800.8  299.06  4857.1  298.75  4977.6  299.68
  4984.5  298.89  4989.4  297.18  5019.8  299.43    5034  298.89  5041.6  299.67
  5119.4  299.97  5140.3  300.82  5197.3  299.74  5416.5  305.86  5522.8  310.83
  5579.7   312.6  5799.9  315.59  5870.1  318.06  5906.2  318.41    5920  319.41
#Mann= 3 , 0 , 0
  3902.4     .11       0  4977.6     .06       0  5019.8     .11       0
Bank Sta=4977.6,5019.8
XS Rating Curve= 0 ,0
Exp/Cntr=0.3,0.1

Type RM Length L Ch R = 1 ,4487    ,500,500,500
BEGIN DESCRIPTION:
CCLC 099 9.0
END DESCRIPTION:
XS GIS Cut Line= 3
      3710967.84     10201761.08      3710363.76     10202552.85
      3709917.84      10203361.1
#Sta/Elev= 30
  4004.1  322.01  4054.4  319.05  4154.7  317.01  4310.7  311.74  4431.7  306.15
  4489.4  305.64  4653.6  300.71  4838.6  297.43    4857  295.97  4873.9  296.89
  4923.8   296.7    4960  297.42  5024.5  297.15  5055.1     298  5180.7     297
  5393.6  296.88  5453.2  300.83  5480.7  300.94  5496.7  301.97  5562.1  303.21
  5643.4  306.45    5687  307.21  5784.4  310.58  5833.7  310.53  5849.7  311.55
  5865.8  311.54  5887.6  313.07  5909.3  316.03    5915  318.71  5923.1  319.71
#Mann= 3 , 0 , 0
  4004.1     .11       0  4838.6     .06       0    4960     .11       0
Bank Sta=4838.6,4960
XS Rating Curve= 0 ,0
Exp/Cntr=0.3,0.1

Type RM Length L Ch R = 1 ,3987    ,537,537,537
BEGIN DESCRIPTION:
CCLC 099 8.0
END DESCRIPTION:
XS GIS Cut Line= 3
      3710517.86     10201561.05      3710057.41     10202278.74
      3709567.84     10203061.09
#Sta/Elev= 30
  4147.3  322.15  4212.4  318.99  4269.9  316.85  4306.2  314.19  4327.4   313.7
  4457.5   307.2  4545.4  304.04  4705.7  299.86  4812.7  295.66  4893.6  295.19
  4951.1  296.27  4993.4  294.59  5038.1  296.55  5124.2   294.4  5154.8  293.79
  5158.3  292.93    5176  294.46  5233.8  294.45    5255  293.65  5285.7   294.6
  5356.6  294.44  5474.3  297.59  5553.3  301.07  5589.8  303.45  5668.8  306.27
  5747.8  310.27  5793.1  311.58  5799.7  312.53  5820.9  313.56  5922.9  317.05
#Mann= 4 ,-1 , 0
  4147.3     .17       0  4212.4     .11       0  5124.2     .06       0
    5176     .11       0
Bank Sta=5124.2,5176
XS Rating Curve= 0 ,0
Exp/Cntr=0.3,0.1

Type RM Length L Ch R = 1 ,3450    ,461,461,461
BEGIN DESCRIPTION:
CCLC 099 7.0
END DESCRIPTION:
XS GIS Cut Line= 3
      3710417.82     10201561.09      3709625.44     10202150.72
      3709467.84     10203011.12
#Sta/Elev= 30
  3875.5  319.56  3997.5  314.78  4018.3  313.25  4047.5  312.28  4063.4  310.75
  4068.4  309.53  4118.4  308.93    4212  303.89  4233.2  303.61  4324.9  299.92
  4397.9  296.07  4511.2  293.54  4669.1  294.57  4754.6  293.43  4936.4  293.62
  4965.2  292.91  4984.5  291.99  4989.6  290.84  4993.1  289.24  4998.3  289.24
    5016  292.77    5077  293.65  5188.9  292.98  5249.9  293.68  5300.7  295.45
  5361.7  301.52  5402.4  303.98  5534.5  309.06  5554.9  310.58  5737.9  316.77
#Mann= 4 ,-1 , 0
  3875.5     .17       0  4063.4     .11       0  4965.2     .06       0
    5016     .11       0
Bank Sta=4965.2,5016
XS Rating Curve= 0 ,0
Exp/Cntr=0.3,0.1

Type RM Length L Ch R = 1 ,2989    ,499,499,499
BEGIN DESCRIPTION:
CCLC 099 6.0
END DESCRIPTION:
XS GIS Cut Line= 3
      3710031.67     10201458.03      3709280.91     10202076.66
      3708818.16      10202645.5
#Sta/Elev= 30
  4027.2  306.77  4117.4  303.25  4138.2  303.56  4166.9  302.24  4181.3  302.59
  4274.7  299.97  4337.6  296.92  4358.5  297.63  4383.6  296.52  4415.8  295.21
  4422.3  295.62  4465.3  293.43  4522.7  293.15  4564.3  291.26  4578.7  292.82
  4671.2  293.07  4835.4  291.63  4969.6  291.51  4983.9  290.74  4995.7  288.49
  5012.5  289.67  5033.3  289.73    5062  291.78  5090.7  293.24  5111.6  295.56
  5147.5  296.83  5253.8  296.47  5381.6  297.88    5503  301.34  5733.3  306.28
#Mann= 5 ,-1 , 0
  4027.2     .11       0  4274.7     .17       0  4383.6     .11       0
  4969.6     .06       0    5062     .11       0
Bank Sta=4969.6,5062
XS Rating Curve= 0 ,0
Exp/Cntr=0.3,0.1

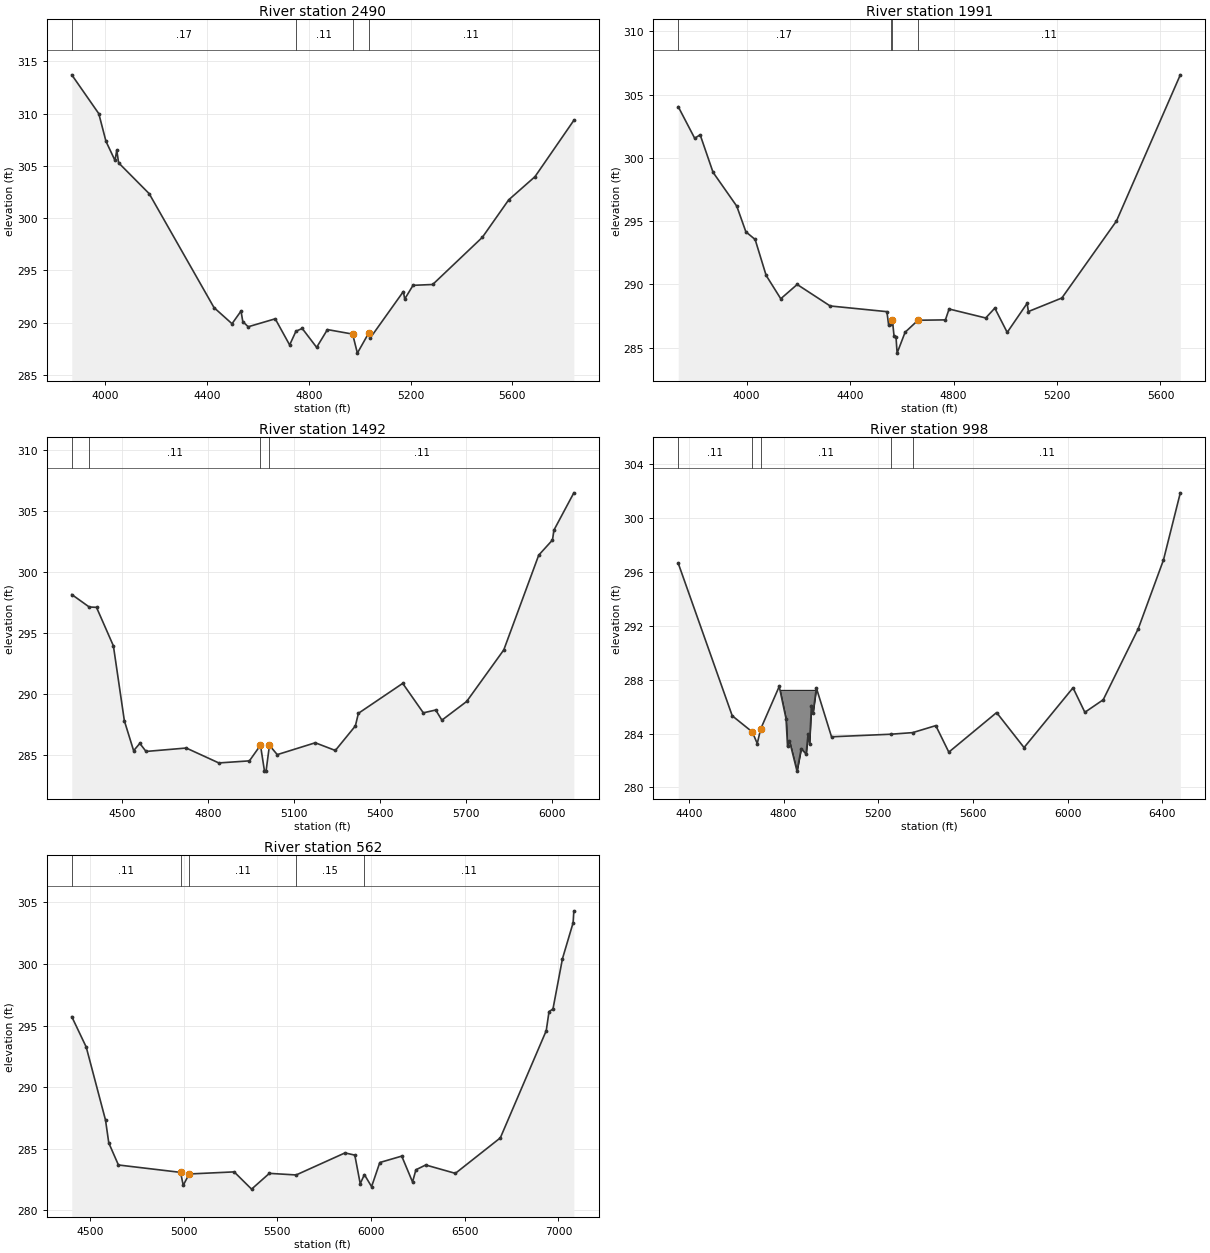
Type RM Length L Ch R = 1 ,2490    ,499,499,499
BEGIN DESCRIPTION:
CCLC 099 5.0
END DESCRIPTION:
XS GIS Cut Line= 3
      3709717.87     10201011.05      3708914.83     10201806.76
      3708667.84     10202611.09
#Sta/Elev= 30
  3869.5   313.7  3975.6  309.99  4003.9  307.34  4039.2  305.52  4046.3  306.49
  4053.4  305.29  4173.6  302.34  4428.2  291.45  4498.9  289.91  4534.2  291.12
  4541.3  290.11  4562.5  289.62  4668.6  290.38  4725.2  287.88  4749.9  289.19
  4774.6  289.46  4831.2  287.65  4873.6  289.35  4972.6  288.92  4991.2   287.1
  5035.7  289.02    5041  288.52  5171.9  292.99  5177.1  292.27  5209.8  293.58
    5287  293.66  5482.1  298.17  5585.5  301.75  5688.9  303.97  5841.4  309.35
#Mann= 4 ,-1 , 0
  3869.5     .17       0  4749.9     .11       0  4972.6     .06       0
  5035.7     .11       0
Bank Sta=4972.6,5035.7
XS Rating Curve= 0 ,0
Exp/Cntr=0.3,0.1

Type RM Length L Ch R = 1 ,1991    ,499,499,499
BEGIN DESCRIPTION:
CCLC 099 4.0
END DESCRIPTION:
XS GIS Cut Line= 3
      3709417.84     10201011.09      3708493.35     10201873.66
      3708568.12     10202546.31
#Sta/Elev= 30
  3735.6  304.05  3799.3  301.55  3820.3  301.83  3870.2  298.86    3962  296.18
  3997.2  294.15  4032.9  293.55  4075.4  290.71    4132  288.86  4195.5  289.99
    4323  288.29  4542.4  287.84  4549.2  286.76  4556.3  286.88  4563.4  287.21
  4570.2  285.88  4577.6  285.83  4581.8  284.56  4612.7  286.21  4662.6  287.16
  4768.6  287.19  4782.8  288.05  4924.4  287.34  4959.6  288.12  5007.5   286.2
  5084.5   288.5  5089.5  287.85  5218.8  288.92    5430  295.01  5676.8  306.57
#Mann= 4 ,-1 , 0
  3735.6     .17       0  4556.3     .11       0  4563.4     .06       0
  4662.6     .11       0
Bank Sta=4563.4,4662.6
XS Rating Curve= 0 ,0
Exp/Cntr=0.3,0.1

Type RM Length L Ch R = 1 ,1492    ,494,494,494
BEGIN DESCRIPTION:
CCLC 099 3.0
END DESCRIPTION:
XS GIS Cut Line= 4
      3708467.84     10200961.09      3708211.28     10201586.94
      3708222.75     10201905.99      3708510.23     10202607.52
#Sta/Elev= 30
  4323.6  298.14  4384.5  297.12    4410  297.09    4469  293.94  4507.3  287.81
  4539.7  285.36  4561.3  285.96    4583   285.3  4723.5  285.58  4837.3  284.36
  4944.1  284.53  4982.8  285.81  4996.8  283.69  5002.3  283.69  5014.1   285.8
  5041.4  285.04  5174.2  286.01  5244.3  285.38  5314.3  287.39  5324.8  288.42
  5479.6  290.87  5551.6  288.46  5594.9  288.69  5616.5  287.86    5703  289.39
  5832.7  293.61  5954.7  301.36  6002.7   302.6  6008.1  303.42  6077.4  306.46
#Mann= 4 ,-1 , 0
  4323.6     .17       0  4384.5     .11       0  4982.8     .06       0
  5014.1     .11       0
Bank Sta=4982.8,5014.1
XS Rating Curve= 0 ,0
Exp/Cntr=0.3,0.1

Type RM Length L Ch R = 1 ,998     ,436,436,436
BEGIN DESCRIPTION:
CCLC 099 2.0
END DESCRIPTION:
XS GIS Cut Line= 4
      3708317.86     10201011.06      3707740.03     10201473.64
      3708083.78     10202395.51      3708384.35     10202654.62
#Sta/Elev= 30
  4355.3  296.65  4583.4  285.32  4668.2  284.12  4689.1  283.26  4703.5  284.34
  4781.9   287.5  4810.7   285.1  4817.1  283.04  4825.1  283.47    4857  281.21
  4874.7  282.88  4895.5  282.48  4903.5  283.94  4909.9  283.19  4917.9  286.08
  4924.4   285.5  4938.8  287.39  5002.8  283.76  5252.3  283.95  5345.6  284.07
  5443.3  284.59  5498.3  282.62  5700.2  285.56  5816.1  282.96    6023   287.4
    6073  285.58  6150.5  286.51  6298.6  291.79    6405  296.89  6476.2  301.88
#Mann= 5 ,-1 , 0
  4355.3     .11       0  4668.2     .06       0  4703.5     .11       0
  5252.3     .15       0  5345.6     .11       0
#Block Obstruct= 1 ,-1
 4780.28 4939.44  287.25
Bank Sta=4668.2,4703.5
XS Rating Curve= 0 ,0
Exp/Cntr=0.3,0.1

Type RM Length L Ch R = 1 ,562     ,0,0,0
BEGIN DESCRIPTION:
CCLC 099 1.0
END DESCRIPTION:
XS GIS Cut Line= 4
      3708267.89     10200911.06      3707469.19     10201280.93
      3708005.65     10202510.09      3708384.33     10202769.46
#Sta/Elev= 30
  4402.1  295.73  4479.3  293.26  4582.3  287.33  4599.7  285.48  4651.1  283.69
  4982.9  283.09  4997.2  282.04  5028.8  282.96    5269  283.13    5362  281.73
    5457  283.01  5599.9  282.88  5860.7  284.67  5913.1  284.49    5942  282.17
  5964.3  282.91  6002.6  281.93  6046.5  283.89  6163.6  284.41  6221.3  282.31
  6239.3   283.3  6291.6  283.69  6449.9  283.01  6689.9  285.89    6935  294.59
  6949.9  296.14  6970.9  296.35  7021.7  300.44  7078.5  303.35  7082.4  304.32
#Mann= 5 ,-1 , 0
  4402.1     .11       0  4982.9     .06       0  5028.8     .11       0
  5599.9     .15       0  5964.3     .11       0
Bank Sta=4982.9,5028.8
XS Rating Curve= 0 ,0
Exp/Cntr=0.3,0.1

Chan Stop Cuts=-1
Use User Specified Reach Order=0
Composite Channel Slope=5