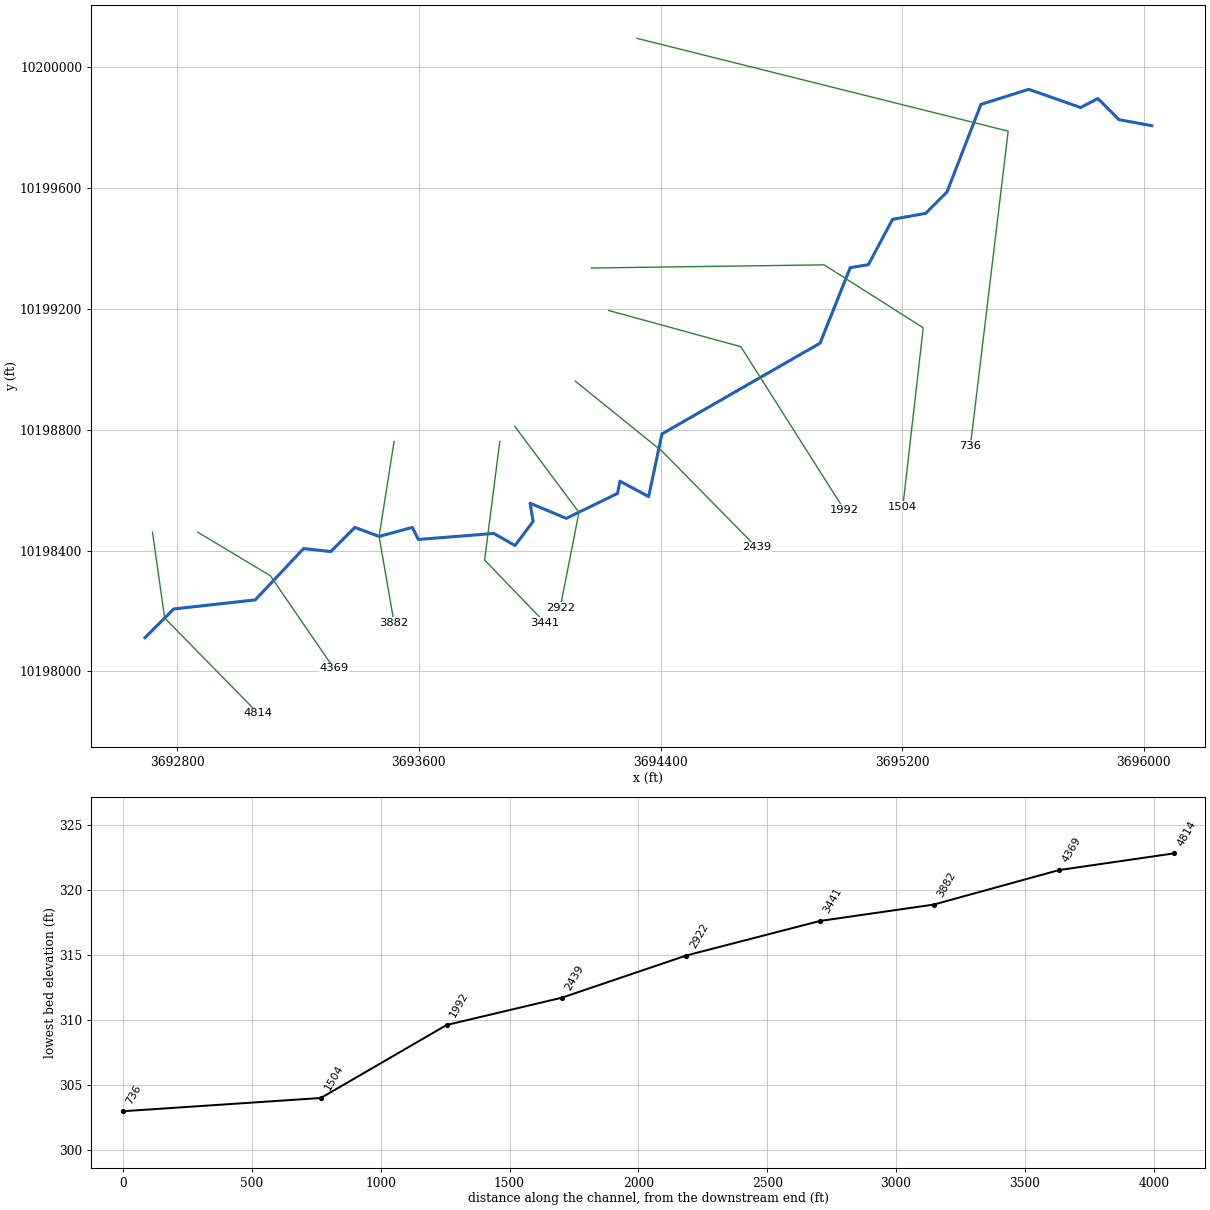
--- CCLC 100.prj (project) ---

Proj Title=CCLC 100 Base Level Engineering
Current Plan=p01
Default Exp/Contr=0.3,0.1
English Units
Geom File=g01
Flow File=f01
Flow File=f02
Plan File=p01
Y Axis Title=Elevation
X Axis Title(PF)=Main Channel Distance
X Axis Title(XS)=Station
BEGIN DESCRIPTION:
CCLC 100
END DESCRIPTION:
DSS Export Rating Curves= 0
DSS Export Rating Curve Sorted= 0
DSS Export Volume Flow Curves= 0
DXF OffsetX= 0
DXF OffsetY= 0
DXF ScaleX= 1
DXF ScaleY= 10

--- CCLC 100.p01 (plan) ---

Plan Title=Multiple Run
Short Identifier=Multiple
Geom File=g01
Flow File=f01
Subcritical Flow
K Sum by GR= 0
Std Step Tol= 0.01
Critical Tol= 0.01
Num of Std Step Trials= 20
Max Error Tol= 0.3
Flow Tol Ratio= 0.001
Split Flow NTrial= 30
Split Flow Tol= 0.02
Split Flow Ratio= 0.02
Log Output Level= 0
Friction Slope Method= 1
Unsteady Friction Slope Method= 2
Unsteady Bridges Friction Slope Method= 1
Parabolic Critical Depth
Global Vel Dist=  1 , 1 , 1
Global Log Level= 0
CheckData=True
Encroach Param= -1, 0, 0, 0
BEGIN DESCRIPTION:
Multiple Run
END DESCRIPTION:

--- CCLC 100.f01 (steady flow) ---

Flow Title=Multiple
Program Version=4.10
Number of Profiles= 7
Profile Names=10-year,25-year,50-year,1pct_min,100-year,1pct_plu,500-year
River Rch & RM=CCLC 100,Reach-1         ,4814
     570     771    1042     463    1399    4225    2608
Boundary for River Rch & Prof#=CCLC 100,Reach-1         , 1
Up Type= 0
Dn Type= 3
Dn Slope=0.005
Boundary for River Rch & Prof#=CCLC 100,Reach-1         , 2
Up Type= 0
Dn Type= 3
Dn Slope=0.005
Boundary for River Rch & Prof#=CCLC 100,Reach-1         , 3
Up Type= 0
Dn Type= 3
Dn Slope=0.005
Boundary for River Rch & Prof#=CCLC 100,Reach-1         , 4
Up Type= 0
Dn Type= 3
Dn Slope=0.005
Boundary for River Rch & Prof#=CCLC 100,Reach-1         , 5
Up Type= 0
Dn Type= 3
Dn Slope=0.005
Boundary for River Rch & Prof#=CCLC 100,Reach-1         , 6
Up Type= 0
Dn Type= 3
Dn Slope=0.005
Boundary for River Rch & Prof#=CCLC 100,Reach-1         , 7
Up Type= 0
Dn Type= 3
Dn Slope=0.005
DSS Import GetInterval= 0
DSS Import GetPeak= 0
DSS Import FillOption= 0

--- CCLC 100.f02 (steady flow) ---

Flow Title=Orig_BLE_Flows
Program Version=4.10
Number of Profiles= 7
Profile Names=10-year,25-year,50-year,1pct_min,100-year,1pct_plu,500-year
River Rch & RM=CCLC 100,Reach-1         ,4814
     570     756     906     356    1076    3250    1516
Boundary for River Rch & Prof#=CCLC 100,Reach-1         , 1
Up Type= 0
Dn Type= 3
Dn Slope=0.005
Boundary for River Rch & Prof#=CCLC 100,Reach-1         , 2
Up Type= 0
Dn Type= 3
Dn Slope=0.005
Boundary for River Rch & Prof#=CCLC 100,Reach-1         , 3
Up Type= 0
Dn Type= 3
Dn Slope=0.005
Boundary for River Rch & Prof#=CCLC 100,Reach-1         , 4
Up Type= 0
Dn Type= 3
Dn Slope=0.005
Boundary for River Rch & Prof#=CCLC 100,Reach-1         , 5
Up Type= 0
Dn Type= 3
Dn Slope=0.005
Boundary for River Rch & Prof#=CCLC 100,Reach-1         , 6
Up Type= 0
Dn Type= 3
Dn Slope=0.005
Boundary for River Rch & Prof#=CCLC 100,Reach-1         , 7
Up Type= 0
Dn Type= 3
Dn Slope=0.005
DSS Import GetInterval= 0
DSS Import GetPeak= 0
DSS Import FillOption= 0

--- CCLC 100.g01 (geometry) ---

Geom Title=Existing Conditions
Program Version=4.10

River Reach=CCLC 100        ,Reach-1
Reach XY= 30
      3692693.23     10198111.84      3692788.23     10198206.84
      3693058.23     10198236.84      3693218.23     10198406.84
      3693308.23     10198396.84      3693388.23     10198476.84
      3693468.23     10198446.84      3693578.23     10198476.84
      3693598.23     10198436.84      3693848.23     10198456.84
      3693918.23     10198416.84      3693978.23     10198496.84
      3693968.23     10198556.84      3694088.23     10198506.84
      3694257.57     10198589.28      3694265.69     10198629.85
      3694360.72     10198578.85      3694404.76      10198786.3
      3694928.23     10199086.84      3695028.23     10199336.84
      3695088.23     10199346.84      3695168.23     10199496.84
      3695278.23     10199516.84      3695348.23     10199586.84
      3695460.93     10199877.43      3695619.16     10199927.37
      3695791.02     10199867.06      3695848.23     10199896.84
      3695918.23     10199826.84      3696026.69     10199806.84

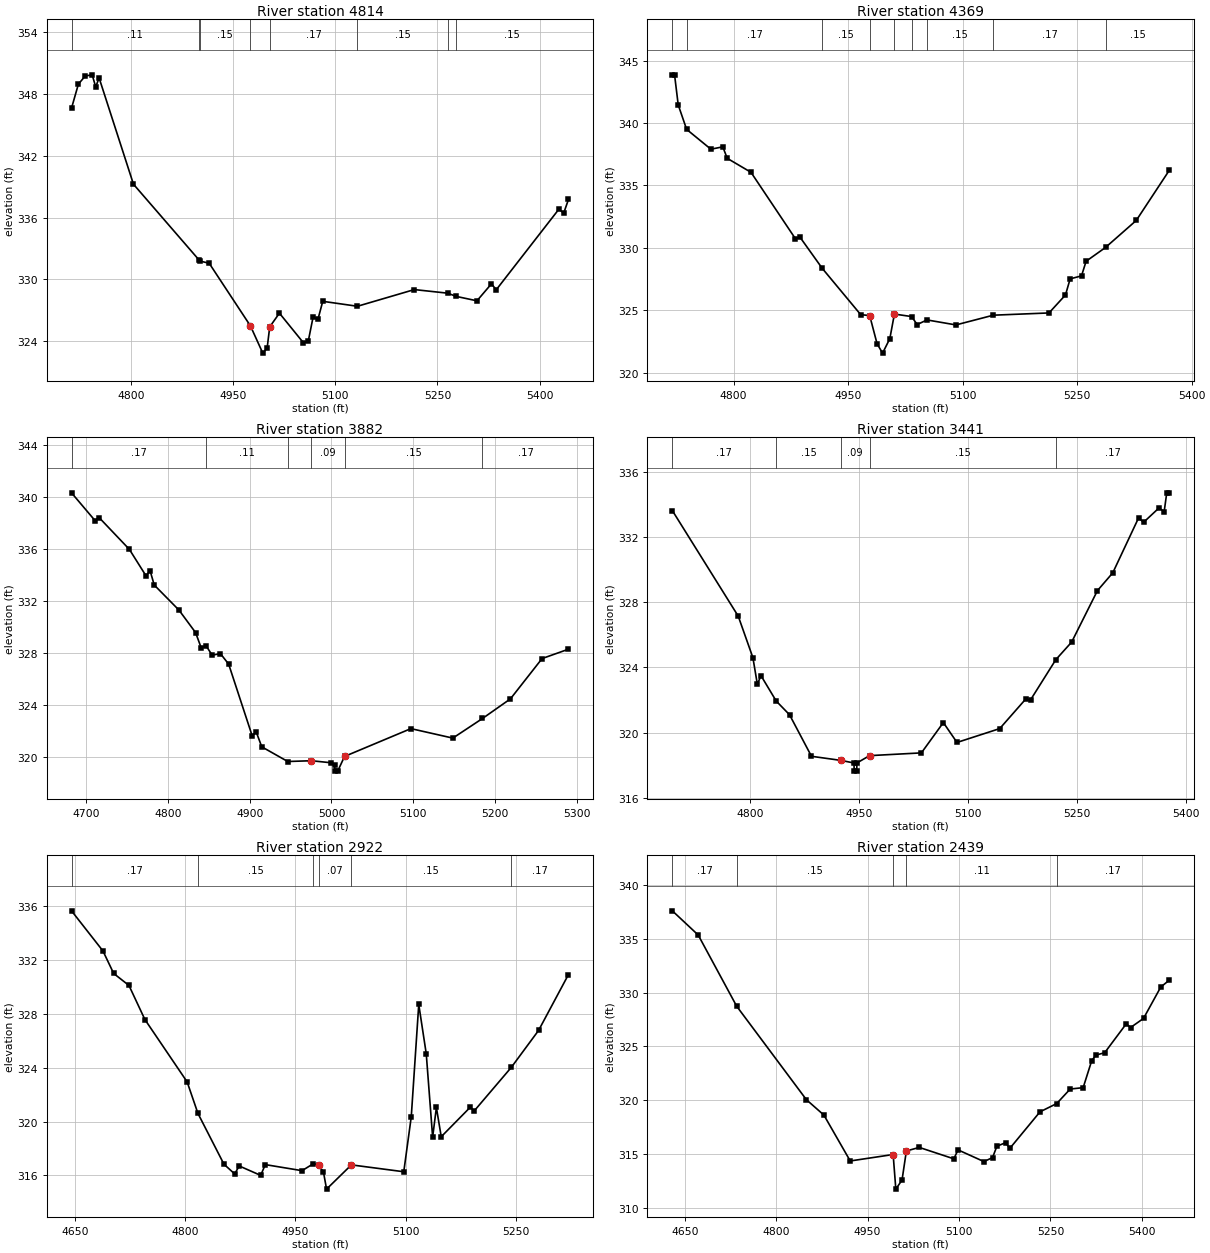
Type RM Length L Ch R = 1 ,4814    ,445,445,445
BEGIN DESCRIPTION:
CCLC 100 7.0
END DESCRIPTION:
XS GIS Cut Line= 3
      3692717.85     10198461.09      3692758.23     10198176.84
      3693067.82      10197861.1
#Sta/Elev= 30
  4712.9  346.62    4723  348.96  4733.1  349.75  4743.2  349.86  4748.4  348.69
  4753.4  349.56  4803.8  339.24  4899.7  331.91  4901.2  331.78  4914.9  331.57
  4975.5  325.48  4993.6  322.84    5000  323.34  5003.8  325.39    5018  326.72
  5053.3  323.84  5060.4  324.02  5067.4  326.33  5074.6  326.13  5081.6  327.87
  5132.5  327.39    5216  329.01    5265  328.66  5277.3  328.35  5307.9  327.92
  5329.2  329.57  5336.2  328.99  5428.2  336.82  5435.2  336.43  5442.2  337.76
#Mann= 8 ,-1 , 0
  4712.9     .11       0  4899.7     .17       0  4901.2     .15       0
  4975.5     .09       0  5003.8     .17       0  5132.5     .15       0
    5265     .17       0  5277.3     .15       0
Bank Sta=4975.5,5003.8
XS Rating Curve= 0 ,0
Exp/Cntr=0.3,0.1

Type RM Length L Ch R = 1 ,4369    ,487,487,487
BEGIN DESCRIPTION:
CCLC 100 6.0
END DESCRIPTION:
XS GIS Cut Line= 3
      3692867.87     10198461.06      3693108.23     10198316.84
      3693317.84     10198011.09
#Sta/Elev= 30
  4719.7  343.86  4722.6  343.86  4727.4  341.45  4738.4  339.49  4770.2   337.9
  4785.8  338.09  4791.6  337.17  4822.7  336.05    4881  330.72  4886.8  330.86
  4916.1  328.35  4966.5  324.64  4978.2324.5733  4987.9  322.31  4995.1  321.56
  5004.6  322.72  5010.6  324.69  5033.1  324.49  5040.4  323.85  5053.3  324.22
  5091.2  323.82  5140.2   324.6  5213.1  324.78  5234.7  326.22  5240.8  327.51
  5255.7  327.75  5261.7  328.92  5287.2  330.03  5327.4  332.19  5370.7  336.21
#Mann= 9 ,-1 , 0
  4719.7     .11       0  4738.4     .17       0  4916.1     .15       0
  4978.2     .09       0  5010.6     .15       0  5033.1     .17       0
  5053.3     .15       0  5140.2     .17       0  5287.2     .15       0
Bank Sta=4978.2,5010.6
XS Rating Curve= 0 ,0
Exp/Cntr=0.3,0.1

Type RM Length L Ch R = 1 ,3882    ,441,441,441
BEGIN DESCRIPTION:
CCLC 100 5.0
END DESCRIPTION:
XS GIS Cut Line= 3
      3693517.85     10198761.05      3693468.23     10198446.84
      3693517.84     10198161.12
#Sta/Elev= 30
  4681.9  340.31  4710.6  338.18  4715.6  338.41  4752.7  335.96    4773  333.93
  4778.1  334.31  4783.1  333.22  4813.5  331.28  4833.7  329.56  4840.5   328.4
  4846.4  328.56    4854  327.82  4864.1  327.94  4874.2  327.13  4902.9  321.63
    4908   321.9  4914.7  320.77  4946.5  319.64  4975.5   319.7    5000  319.54
  5003.9   319.4  5004.1   318.9  5007.6   318.9    5016  320.03  5097.2  322.17
  5148.5  321.44  5184.8  322.95    5219  324.46  5257.7  327.56    5290  328.28
#Mann= 6 ,-1 , 0
  4681.9     .17       0  4846.4     .11       0  4946.5     .15       0
  4975.5     .09       0    5016     .15       0  5184.8     .17       0
Bank Sta=4975.5,5016
XS Rating Curve= 0 ,0
Exp/Cntr=0.3,0.1

Type RM Length L Ch R = 1 ,3441    ,519,519,519
BEGIN DESCRIPTION:
CCLC 100 4.0
END DESCRIPTION:
XS GIS Cut Line= 3
      3693867.85     10198761.06      3693817.61     10198368.71
      3694017.84     10198161.08
#Sta/Elev= 30
  4693.3  333.63    4784  327.15  4804.2   324.6  4810.3  322.97  4815.3   323.5
  4836.3  321.94  4854.6   321.1  4884.8  318.55  4925.2   318.3  4943.3  318.14
  4943.6  317.64  4947.1  317.64  4947.3  318.14  4964.7  318.59  5036.1  318.76
  5066.3  320.62  5085.1   319.4  5143.9  320.25  5179.4  322.05  5186.3  322.01
  5221.1  324.48  5242.9  325.56  5278.4  328.72  5299.5  329.81    5335  333.18
  5341.9  332.91  5363.3   333.8  5370.2  333.55  5373.8  334.72  5377.3  334.72
#Mann= 5 ,-1 , 0
  4693.3     .17       0  4836.3     .15       0  4925.2     .09       0
  4964.7     .15       0  5221.1     .17       0
Bank Sta=4925.2,4964.7
XS Rating Curve= 0 ,0
Exp/Cntr=0.3,0.1

Type RM Length L Ch R = 1 ,2922    ,483,483,483
BEGIN DESCRIPTION:
CCLC 100 3.0
END DESCRIPTION:
XS GIS Cut Line= 3
      3693917.83      10198811.1      3694129.98     10198526.84
      3694067.86      10198211.1
#Sta/Elev= 30
  4645.3  335.64  4688.1  332.66  4702.7  330.99  4723.5   330.1  4745.2  327.57
  4802.7  322.94  4817.4   320.6  4852.8  316.83  4867.4  316.11  4873.6   316.7
  4902.8     316  4909.1   316.8  4959.1  316.35  4974.6  316.87    4982  316.76
  4988.3  316.24  4992.5  314.98  5026.3  316.78  5097.6  316.27  5107.8  320.35
    5118  328.69  5128.2  325.03  5136.9  318.84    5142  321.04  5148.6  318.87
  5188.3  321.07  5193.4  320.78    5244  324.02  5281.1  326.76  5321.8  330.91
#Mann= 6 ,-1 , 0
  4645.3     .17       0  4817.4     .15       0  4974.6     .11       0
    4982     .07       0  5026.3     .15       0    5244     .17       0
Bank Sta=4982,5026.3
XS Rating Curve= 0 ,0
Exp/Cntr=0.3,0.1

Type RM Length L Ch R = 1 ,2439    ,447,447,447
BEGIN DESCRIPTION:
CCLC 100 2.0
END DESCRIPTION:
XS GIS Cut Line= 3
      3694117.87     10198961.06      3694405.91     10198728.35
      3694717.82      10198411.1
#Sta/Elev= 30
  4629.7  337.62  4672.1  335.37  4735.3  328.74  4849.6  320.05  4878.3  318.62
  4921.5  314.35  4991.9  314.95  4996.3  311.73  5006.5  312.58  5013.6  315.28
  5034.8  315.61  5091.4  314.55  5098.4  315.38  5140.9  314.29    5155  314.67
  5162.1  315.72  5176.3  316.05  5183.3  315.52  5232.8  318.92  5260.2  319.69
  5282.3  321.04  5303.6  321.17  5317.7  323.69  5324.7   324.2  5338.9  324.42
  5374.3  327.11  5381.3  326.76  5402.6  327.61  5430.9  330.53  5444.9  331.17
#Mann= 5 ,-1 , 0
  4629.7     .17       0  4735.3     .15       0  4991.9     .06       0
  5013.6     .11       0  5260.2     .17       0
Bank Sta=4991.9,5013.6
XS Rating Curve= 0 ,0
Exp/Cntr=0.3,0.1

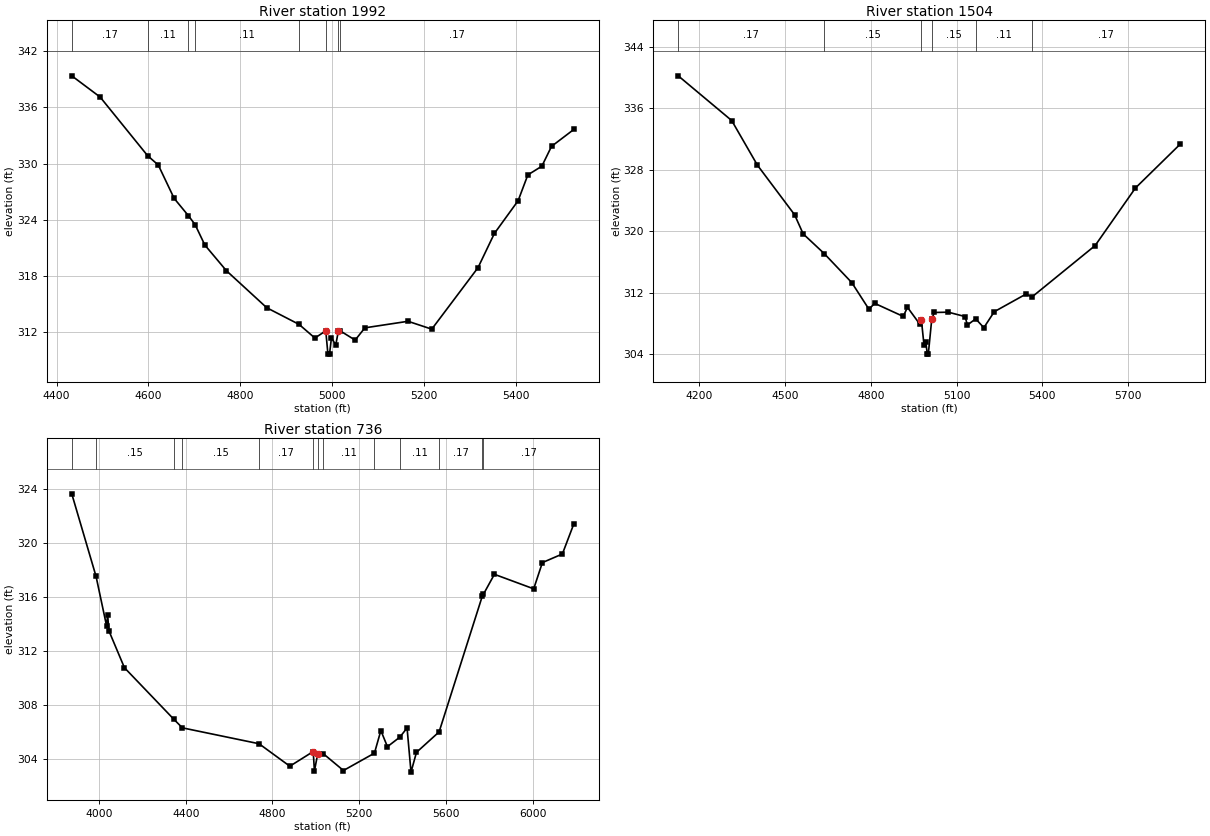
Type RM Length L Ch R = 1 ,1992    ,488,488,488
BEGIN DESCRIPTION:
Mapping XS 77e59040
END DESCRIPTION:
XS GIS Cut Line= 3
      3694228.24     10199195.09       3694665.7     10199075.31
       3695008.7     10198534.82
#Sta/Elev= 30
  4433.2  339.38    4495  337.11  4598.3  330.85  4621.7  329.84  4656.2  326.28
  4687.4  324.42  4701.8  323.48  4723.1  321.29    4770  318.55  4857.9  314.59
  4928.3  312.81  4962.8  311.35  4986.5  312.12  4991.2  309.63  4994.7  309.63
  4998.9  311.39  5008.2   310.6  5014.1  312.13  5018.5   312.1  5050.5  311.13
  5071.7  312.44  5165.7  313.14  5217.4   312.3  5318.1  318.87  5353.8  322.53
  5405.5  326.03  5426.7  328.79  5457.2  329.72  5478.3  331.84  5526.9  333.65
#Mann= 8 ,-1 , 0
  4433.2     .17       0  4598.3     .11       0  4687.4     .17       0
  4701.8     .11       0  4928.3     .15       0  4986.5     .09       0
  5014.1     .15       0  5018.5     .17       0
Bank Sta=4986.5,5014.1
XS Rating Curve= 0 ,0
Exp/Cntr=0.3,0.1

Type RM Length L Ch R = 1 ,1504    ,768,768,768
BEGIN DESCRIPTION:
Mapping XS b120b6da
END DESCRIPTION:
XS GIS Cut Line= 4
      3694170.86     10199335.72      3694941.74     10199346.14
      3695269.87     10199137.81      3695202.27     10198545.07
#Sta/Elev= 30
  4126.6  340.23  4313.6  334.41  4403.6   328.6  4533.6  322.15  4563.6  319.66
  4637.1   317.1  4733.6  313.32  4793.7  309.85  4813.7  310.62  4913.5  308.92
  4928.5   310.1  4971.1  307.93    4977   308.5  4986.4  305.14  4992.3  305.65
  4997.8  304.01  5001.3  304.01  5013.5  308.61  5022.8  309.43  5071.1  309.47
  5129.9   308.9    5138   307.8  5167.1   308.6  5195.6  307.45    5232  309.53
  5343.2  311.83  5364.3  311.46  5584.9  318.14  5725.8  325.63  5882.8  331.35
#Mann= 6 ,-1 , 0
  4126.6     .17       0  4637.1     .15       0    4977     .09       0
  5013.5     .15       0  5167.1     .11       0  5364.3     .17       0
Bank Sta=4977,5013.5
XS Rating Curve= 0 ,0
Exp/Cntr=0.3,0.1

Type RM Length L Ch R = 1 ,736     ,0,0,0
BEGIN DESCRIPTION:
CCLC 100 1.0
END DESCRIPTION:
XS GIS Cut Line= 3
      3694321.91     10200096.15      3695551.12     10199788.85
      3695426.11     10198747.16
#Sta/Elev= 30
  3874.3  323.67  3986.4  317.53  4034.7  313.87  4039.9  314.67  4045.4   313.5
  4117.2  310.75    4345  306.92  4384.7  306.28  4738.2   305.1  4880.3  303.43
  4988.2  304.52  4993.7  303.08 5008.84  304.34  5034.6  304.36  5127.7  303.11
  5270.6   304.4  5300.2  306.08  5330.5  304.88  5387.7  305.59  5421.1  306.27
  5439.3  302.99  5464.5  304.46  5568.9  305.98  5767.8  316.05  5773.5  316.21
    5824  317.69  6005.3  316.61  6045.3  318.56  6137.6   319.2  6190.5  321.44
#Mann= 13 ,-1 , 0
  3874.3     .17       0  3986.4     .15       0    4345     .17       0
  4384.7     .15       0  4738.2     .17       0  4988.2     .09       0
 5008.84     .17       0  5034.6     .11       0  5270.6     .15       0
  5387.7     .11       0  5568.9     .17       0  5767.8     .11       0
  5773.5     .17       0
Bank Sta=4988.2,5008.84
XS Rating Curve= 0 ,0
Exp/Cntr=0.3,0.1

Chan Stop Cuts=-1
Use User Specified Reach Order=0
Composite Channel Slope=5