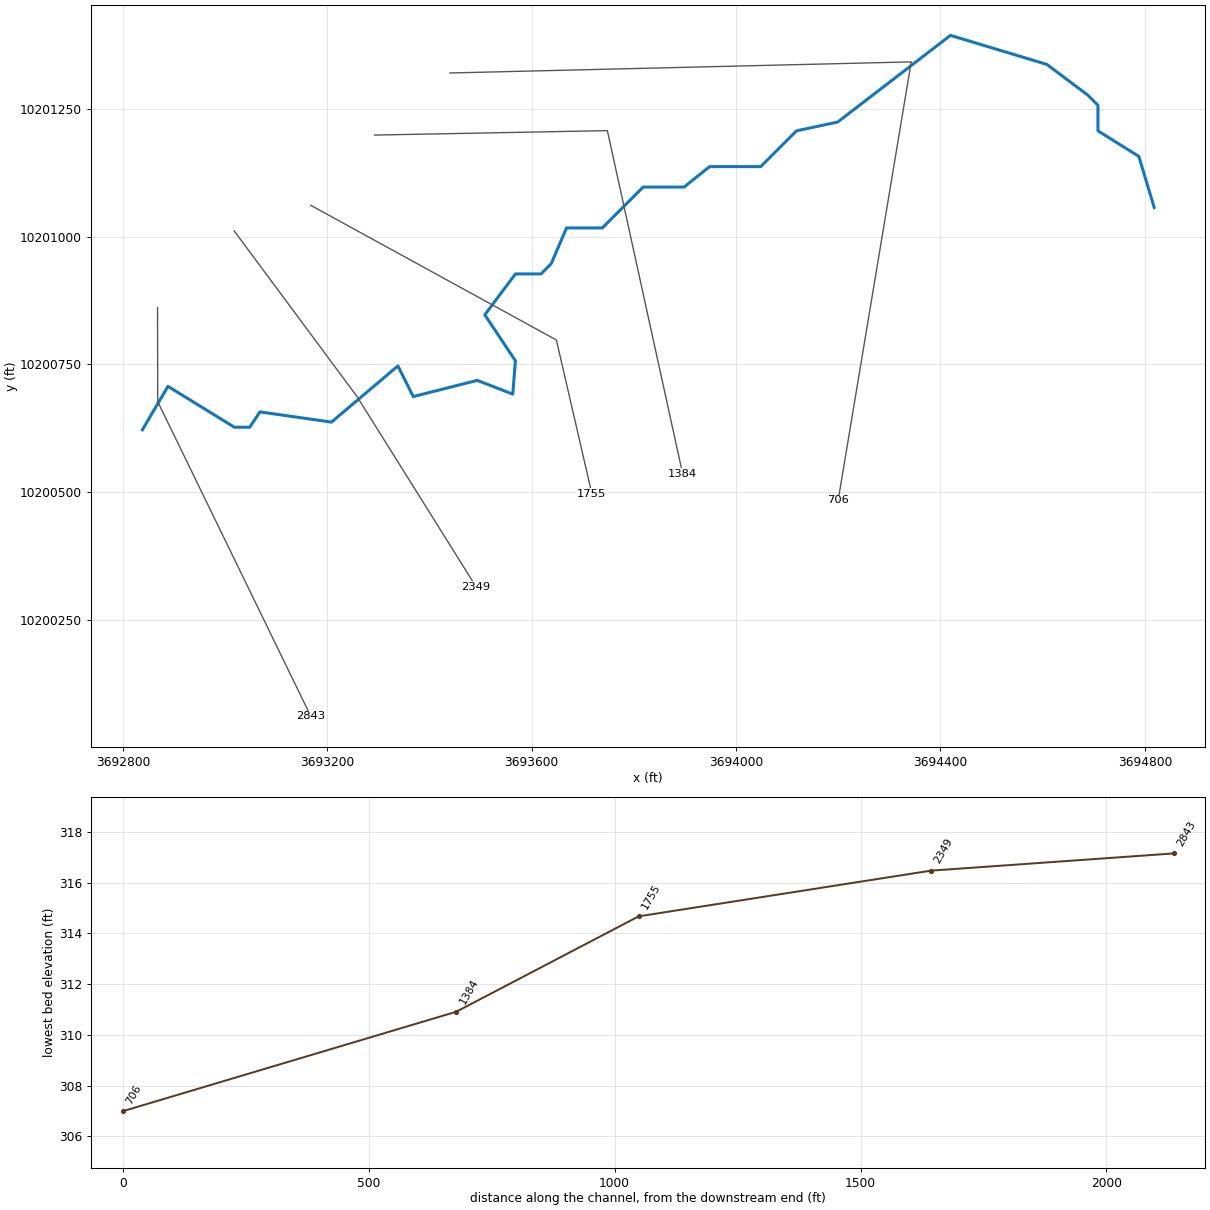
--- CCLC 101.prj (project) ---

Proj Title=CCLC 101 Base Level Engineering
Current Plan=p02
Default Exp/Contr=0.3,0.1
English Units
Geom File=g01
Flow File=f01
Flow File=f02
Plan File=p01
Plan File=p02
Y Axis Title=Elevation
X Axis Title(PF)=Main Channel Distance
X Axis Title(XS)=Station
BEGIN DESCRIPTION:
CCLC 101
END DESCRIPTION:
DSS Export Rating Curves= 0
DSS Export Rating Curve Sorted= 0
DSS Export Volume Flow Curves= 0
DXF OffsetX= 0
DXF OffsetY= 0
DXF ScaleX= 1
DXF ScaleY= 10

--- CCLC 101.p02 (plan) ---

Plan Title=Plan 02
Program Version=4.10
Short Identifier=Plan 02
Geom File=g01
Flow File=f02
Subcritical Flow
K Sum by GR= 0
Std Step Tol= 0.01
Critical Tol= 0.01
Num of Std Step Trials= 20
Max Error Tol= 0.3
Flow Tol Ratio= 0.001
Split Flow NTrial= 30
Split Flow Tol= 0.02
Split Flow Ratio= 0.02
Log Output Level= 0
Friction Slope Method= 1
Unsteady Friction Slope Method= 2
Unsteady Bridges Friction Slope Method= 1
Parabolic Critical Depth
Global Vel Dist= 1 , 1 , 1
Global Log Level= 0
CheckData=True
Encroach Param=-1 ,0,0, 0
BEGIN DESCRIPTION:
Multiple Run
END DESCRIPTION:
Computation Interval=1HOUR
Output Interval=1HOUR
Run HTab= 0
Run UNet= 0
Run PostProcess= 0
Run WQNet= 0
UNET Theta= 1
UNET Theta Warmup= 1
UNET ZTol= 0.02
UNET ZSATol= 0.05
UNET MxIter= 20
UNET MaxInSteps= 0
UNET DtIC= 0
UNET DtMin= 0
UNET MaxCRTS= 20
UNET WFStab= 2
UNET SFStab= 1
UNET WFX= 1
UNET SFX= 1
UNET DSS MLevel= 4
UNET DZMax Abort= 100
UNET Convert EG Bridges= 0
UNET Use Existing IB Tables=-1
UNET Froude Reduction=False
UNET Froude Limit= 1
UNET Froude Power= 10
UNET Time Slicing=0,0, 5
UNET Junction Losses=0
Instantaneous Interval=1HOUR
Write IC File= 0
Write IC File at Sim End=0
Echo Input=False
Echo Parameters=False
Echo Output=False
Write Detailed= 0
WQ AD Non Conservative
WQ ULTIMATE=-1
WQ Max Comp Step=1HOUR
WQ Output Interval=15MIN
WQ Output Selected Increments= 0
WQ Output face flow=0
WQ Output face velocity=0
WQ Output face area=0
WQ Output face dispersion=0
WQ Output cell volume=0
WQ Output cell surface area=0
WQ Output cell continuity=0
WQ Output cumulative cell continuity=0
WQ Output face conc=0
WQ Output face dconc_dx=0
WQ Output face courant=0
WQ Output face peclet=0
WQ Output face adv mass=0
WQ Output face disp mass=0
WQ Output cell mass=0
WQ Output cell source sink temp=0
WQ Output cell source sink nsm=0
WQ Output MaxMinRange=-1
WQ Daily Max Min Mean=-1
WQ Daily Range=0
WQ Daily Time=0
WQ Create Restart=0
WQ Fixed Restart=0
WQ System Summary=0
WQ Use Fixed Temperature=0
Sorting and Armoring Iterations= 10
XS Update Threshold= 0.02
Hydraulics Update Threshold= 0.02
Energy Slope Method= 1
Volume Change Method= 0
XS Weighting Method= 0
Number of US Weighted Cross Sections= 1
Number of DS Weighted Cross Sections= 1
Upstream XS Weight=0.25
Main XS Weight=0.5
Downstream XS Weight=0.25
Number of DS XS's Weighted with US Boundary= 1
Upstream Boundary Weight= 1
Weight of XSs Associated with US Boundary= 0
Number of US XS's Weighted with DS Boundary= 1
Downstream Boundary Weight= 0.5
Weight of XSs Associated with DS Boundary= 0.5
Sediment Output Level= 4
Mass or Volume Output= 0
Output Increment Type= 1
Profile and TS Output Increment= 10
XS Output Flag= 0
XS Output Increment= 10
Disregard all LS=0
Disregard all Conn=0
Disregard all Breaches=0
Disregard all Pumps=0

--- CCLC 101.p01 (plan) ---

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Plan Title=Multiple Run
Short Identifier=Multiple
Geom File=g01
Flow File=f01
Global Vel Dist=  1 , 1 , 1
Encroach Param= -1, 0, 0, 0

--- CCLC 101.f02 (steady flow) ---

Flow Title=Orig_BLE_Flows
Program Version=4.10
Number of Profiles= 7
Profile Names=10-year,25-year,50-year,1pct_min,100-year,1pct_plu,500-year
River Rch & RM=CCLC 101,Reach-1         ,2843
     489     657     881     390    1177    3554    2169
Boundary for River Rch & Prof#=CCLC 101,Reach-1         , 1
Up Type= 0
Dn Type= 3
Dn Slope=0.005
Boundary for River Rch & Prof#=CCLC 101,Reach-1         , 2
Up Type= 0
Dn Type= 3
Dn Slope=0.005
Boundary for River Rch & Prof#=CCLC 101,Reach-1         , 3
Up Type= 0
Dn Type= 3
Dn Slope=0.005
Boundary for River Rch & Prof#=CCLC 101,Reach-1         , 4
Up Type= 0
Dn Type= 3
Dn Slope=0.005
Boundary for River Rch & Prof#=CCLC 101,Reach-1         , 5
Up Type= 0
Dn Type= 3
Dn Slope=0.005
Boundary for River Rch & Prof#=CCLC 101,Reach-1         , 6
Up Type= 0
Dn Type= 3
Dn Slope=0.005
Boundary for River Rch & Prof#=CCLC 101,Reach-1         , 7
Up Type= 0
Dn Type= 3
Dn Slope=0.005
DSS Import GetInterval= 0
DSS Import GetPeak= 0
DSS Import FillOption= 0

--- CCLC 101.f01 (steady flow) ---

Flow Title=Multiple
Number of Profiles=7
Profile Names=10-year,25-year,50-year,1pct_min,100-year,1pct_plu,500-year
River Rch & RM= CCLC 101,Reach-1,2843
     489     644     766     300     905    2733    1261
Boundary for River Rch & Prof#=CCLC 101,Reach-1,1
Up Type=0
Dn Type=3
Dn Slope=0.005
Boundary for River Rch & Prof#=CCLC 101,Reach-1,2
Up Type=0
Dn Type=3
Dn Slope=0.005
Boundary for River Rch & Prof#=CCLC 101,Reach-1,3
Up Type=0
Dn Type=3
Dn Slope=0.005
Boundary for River Rch & Prof#=CCLC 101,Reach-1,4
Up Type=0
Dn Type=3
Dn Slope=0.005
Boundary for River Rch & Prof#=CCLC 101,Reach-1,5
Up Type=0
Dn Type=3
Dn Slope=0.005
Boundary for River Rch & Prof#=CCLC 101,Reach-1,6
Up Type=0
Dn Type=3
Dn Slope=0.005
Boundary for River Rch & Prof#=CCLC 101,Reach-1,7
Up Type=0
Dn Type=3
Dn Slope=0.005

--- CCLC 101.g01 (geometry) ---

Geom Title=Existing Conditions
Program Version=4.10

River Reach=CCLC 101        ,Reach-1
Reach XY= 30
      3692838.23     10200621.84      3692888.23     10200706.84
      3693018.23     10200626.84      3693048.23     10200626.84
      3693068.23     10200656.84      3693208.23     10200636.84
      3693338.23     10200746.84      3693368.23     10200686.84
       3693493.5     10200718.52      3693562.99     10200691.61
      3693568.23     10200756.84      3693508.23     10200846.84
      3693568.23     10200926.84      3693618.23     10200926.84
      3693638.23     10200946.84      3693668.23     10201016.84
      3693738.23     10201016.84      3693818.23     10201096.84
      3693898.23     10201096.84      3693948.23     10201136.84
      3694048.23     10201136.84      3694118.23     10201206.84
       3694198.8     10201224.07      3694419.57     10201393.68
      3694608.23     10201336.84      3694688.23     10201276.84
      3694708.23     10201256.84      3694708.23     10201206.84
      3694788.23     10201156.84      3694818.23     10201056.84

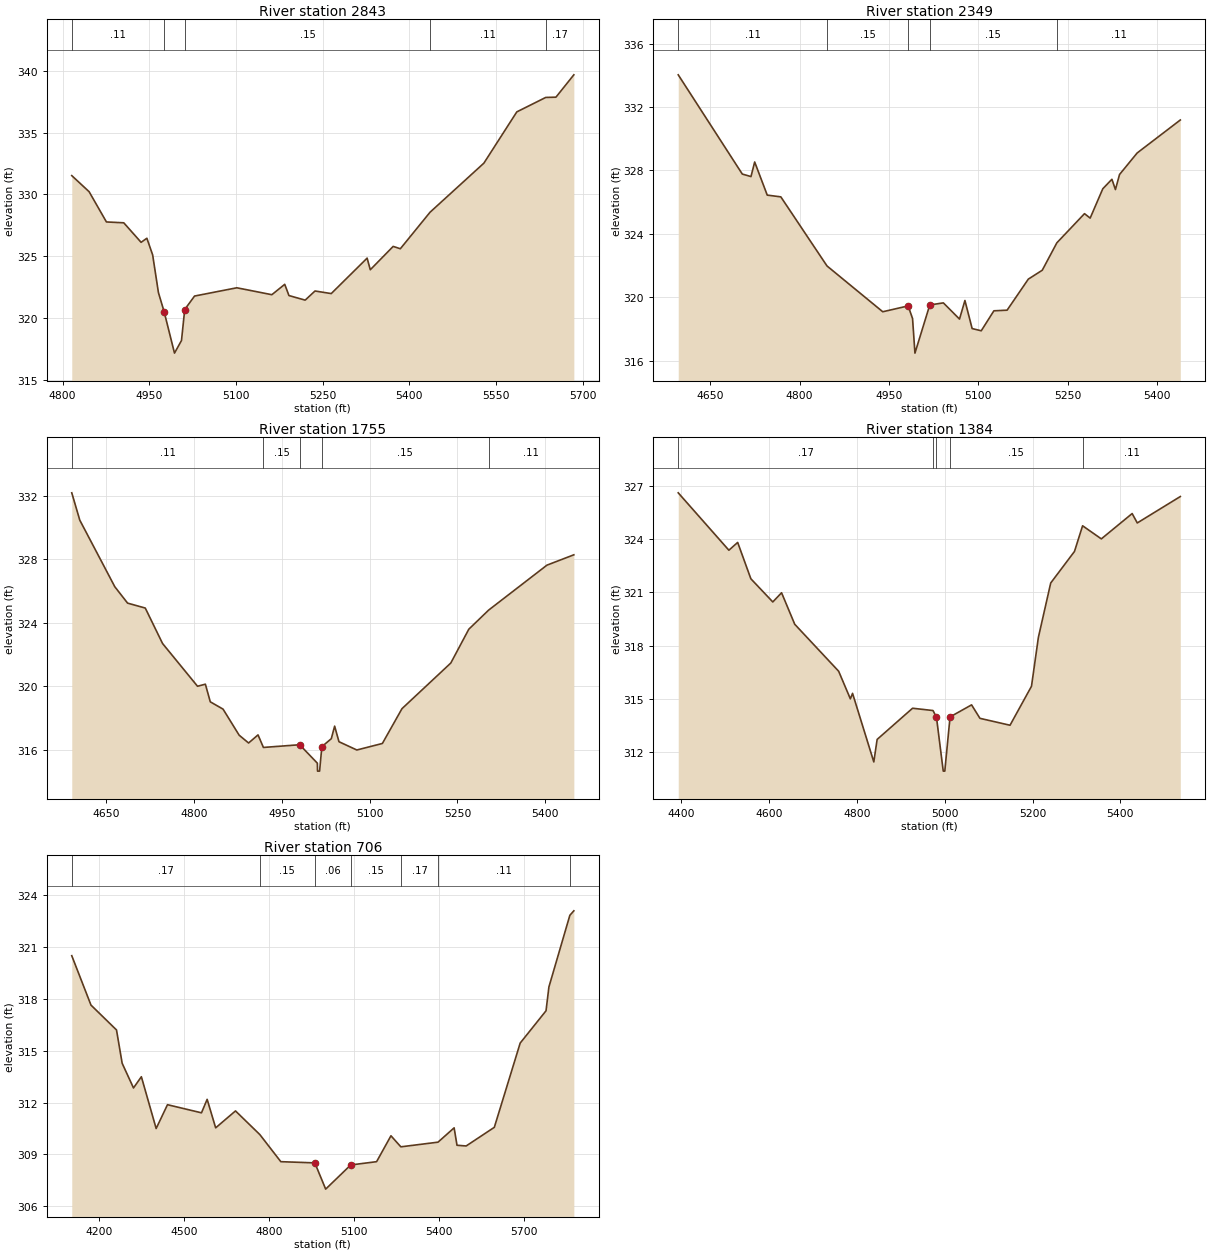
Type RM Length L Ch R = 1 ,2843    ,494,494,494
BEGIN DESCRIPTION:
CCLC 101 4.0
END DESCRIPTION:
XS GIS Cut Line= 3
      3692867.85     10200861.04      3692868.23     10200676.84
      3693167.85     10200061.07
#Sta/Elev= 30
  4815.8  331.52  4845.8  330.22  4875.8  327.77  4905.8   327.7  4935.8  326.12
  4945.8  326.45  4955.8   325.1  4965.8  322.05  4975.8  320.48  4993.6  317.15
  5005.7  318.17  5011.3  320.68  5028.3  321.77  5101.5  322.44  5162.1  321.88
  5184.4  322.72  5191.7  321.81  5219.8  321.44  5236.8  322.18  5264.9  321.97
    5327  324.84  5332.5   323.9  5372.1  325.79  5384.5   325.6    5436  328.56
  5529.1  332.53  5586.1  336.68  5636.2  337.85  5653.8  337.87  5684.8  339.68
#Mann= 5 ,-1 , 0
  4815.8     .11       0  4975.8     .09       0  5011.3     .15       0
    5436     .11       0  5636.2     .17       0
Bank Sta=4975.8,5011.3
XS Rating Curve= 0 ,0
Exp/Cntr=0.3,0.1

Type RM Length L Ch R = 1 ,2349    ,594,594,594
BEGIN DESCRIPTION:
CCLC 101 3.0
END DESCRIPTION:
XS GIS Cut Line= 3
      3693017.86     10201011.06      3693258.23     10200686.84
      3693491.17     10200314.62
#Sta/Elev= 30
  4596.4  334.03  4703.9  327.77  4718.5  327.61  4724.7  328.53  4745.8  326.44
  4768.6  326.33  4846.1  321.97  4939.7  319.08  4982.3  319.45  4989.7  318.65
  4993.7  316.47  5018.6  319.51  5041.4  319.64  5068.5  318.62  5077.6  319.79
  5089.7  318.02    5105  317.88  5126.2  319.14  5148.4  319.18    5184  321.14
  5207.4   321.7  5231.9  323.43  5278.3  325.27  5287.8  324.99    5309  326.84
  5324.3  327.44  5330.2  326.79  5337.1  327.74  5366.7   329.1  5439.1  331.18
#Mann= 5 ,-1 , 0
  4596.4     .11       0  4846.1     .15       0  4982.3     .09       0
  5018.6     .15       0  5231.9     .11       0
Bank Sta=4982.3,5018.6
XS Rating Curve= 0 ,0
Exp/Cntr=0.3,0.1

Type RM Length L Ch R = 1 ,1755    ,371,371,371
BEGIN DESCRIPTION:
CCLC 101 2.0
END DESCRIPTION:
XS GIS Cut Line= 3
      3693167.85     10201061.07      3693648.41     10200797.53
      3693717.92     10200496.32
#Sta/Elev= 30
  4591.5  332.18  4605.2  330.46    4665  326.27  4686.8  325.24    4717  324.93
  4746.5   322.7  4806.2  320.01  4819.6  320.14    4828  319.03  4849.8  318.57
  4877.3  316.93  4893.4  316.44  4909.5  316.95  4918.7  316.16  4980.6  316.33
  5010.8  315.17  5011.1  314.67  5014.6  314.67  5018.5  316.21  5034.6  316.71
  5040.3   317.5  5047.7  316.52  5078.2     316  5121.8  316.41  5155.3   318.6
  5238.6  321.47  5269.4   323.6  5303.2   324.8  5402.8  327.63  5448.7  328.28
#Mann= 5 ,-1 , 0
  4591.5     .11       0  4918.7     .15       0  4980.6     .09       0
  5018.5     .15       0  5303.2     .11       0
Bank Sta=4980.6,5018.5
XS Rating Curve= 0 ,0
Exp/Cntr=0.3,0.1

Type RM Length L Ch R = 1 ,1384    ,678,678,678
BEGIN DESCRIPTION:
Mapping XS 5970e551
END DESCRIPTION:
XS GIS Cut Line= 3
      3693292.47     10201198.57      3693748.16     10201207.25
      3693895.56      10200535.3
#Sta/Elev= 30
  4392.7  326.62  4508.1  323.38  4528.1  323.82  4558.1  321.77  4608.1  320.46
  4628.1  320.98  4658.1   319.2  4758.1  316.55  4784.8  314.99  4789.8   315.3
  4838.2  311.43  4845.8   312.7  4926.5  314.46  4973.1  314.33 4980.97313.9461
  4996.4  310.91  4999.9  310.91  5011.9  313.97  5060.9  314.65    5080  313.89
  5148.5   313.5  5197.4   315.7  5213.1  318.46  5241.2  321.53  5295.3  323.31
  5313.8  324.76  5356.5  324.02  5426.7  325.45  5438.4  324.92  5536.4  326.41
#Mann= 5 ,-1 , 0
  4392.7     .17       0  4973.1     .15       0 4980.97     .09       0
  5011.9     .15       0  5313.8     .11       0
Bank Sta=4980.97,5011.9
XS Rating Curve= 0 ,0
Exp/Cntr=0.3,0.1

Type RM Length L Ch R = 1 ,706     ,0,0,0
BEGIN DESCRIPTION:
CCLC 101 1.0
END DESCRIPTION:
XS GIS Cut Line= 3
      3693440.05      10201320.1      3694342.78      10201341.8
      3694199.85     10200484.23
#Sta/Elev= 30
  4103.4  320.51  4171.2  317.65  4261.3  316.21  4281.3  314.28  4321.3  312.85
  4349.1   313.5  4401.3   310.5  4441.3  311.88  4561.3  311.41  4581.3  312.19
  4611.4  310.54  4681.4  311.52  4767.3  310.15  4841.4  308.58  4961.5  308.51
  4999.7  306.99  5088.2  308.39  5179.5  308.58  5230.2  310.08  5265.1  309.44
  5396.3  309.71  5453.2  310.54  5463.3  309.53  5495.7  309.49  5595.1  310.57
  5686.4  315.45  5777.6  317.32  5787.8   318.7  5861.7  322.85  5875.8  323.11
#Mann= 7 ,-1 , 0
  4103.4     .17       0  4767.3     .15       0  4961.5     .06       0
  5088.2     .15       0  5265.1     .17       0  5396.3     .11       0
  5861.7     .17       0
Bank Sta=4961.5,5088.2
XS Rating Curve= 0 ,0
Exp/Cntr=0.3,0.1

Chan Stop Cuts=-1
Use User Specified Reach Order=0
Composite Channel Slope=5