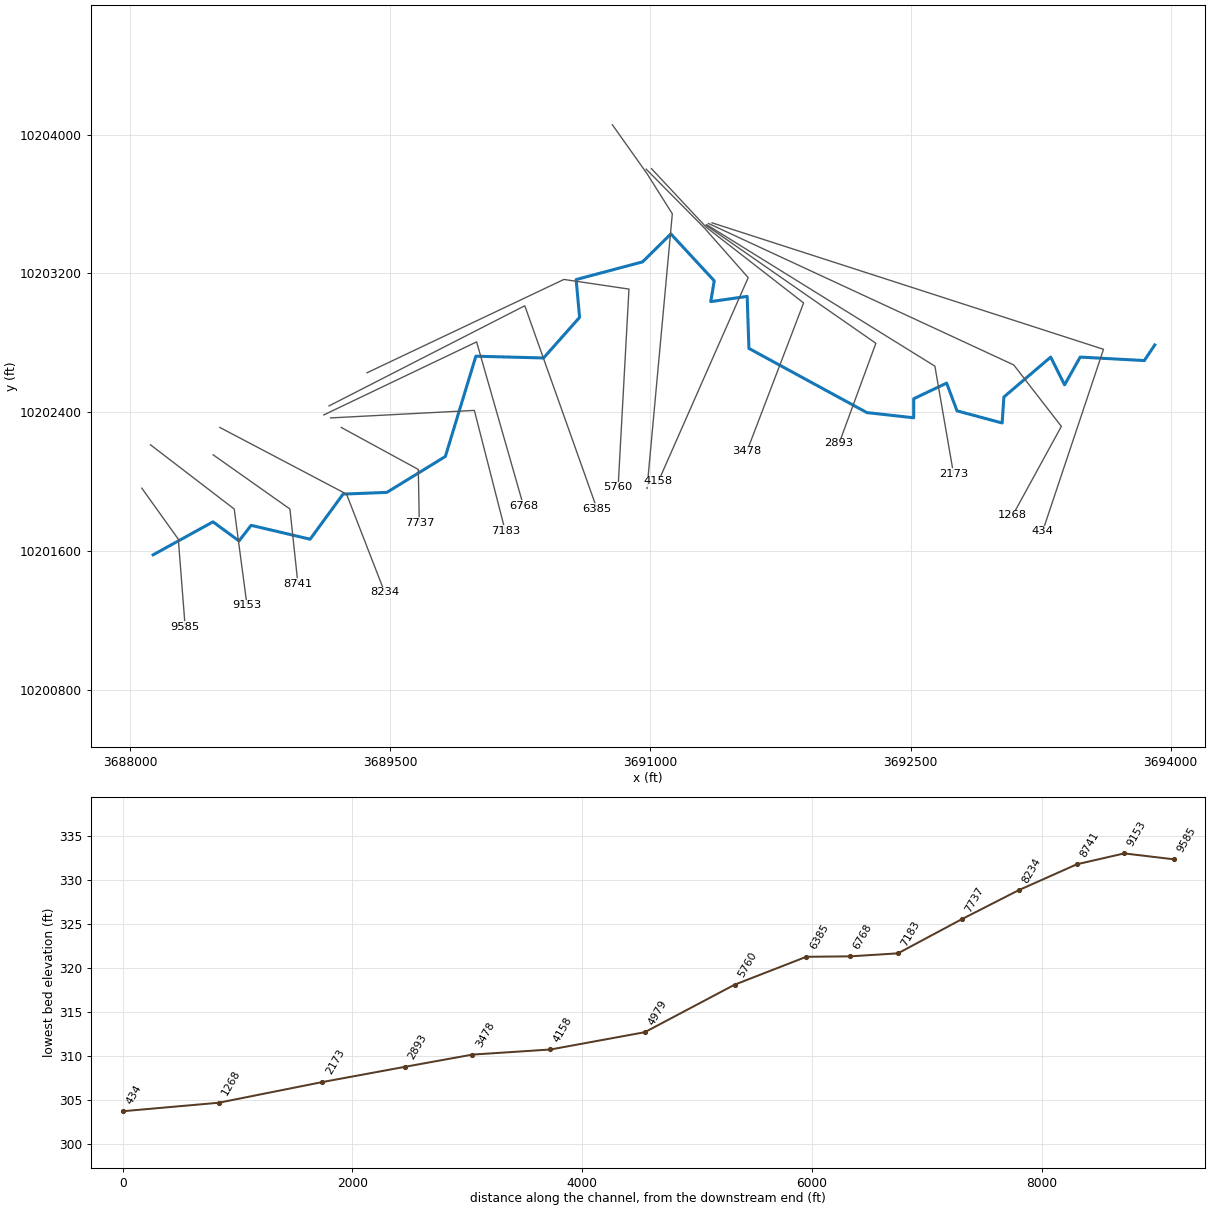
--- CCLC 105.prj (project) ---

Proj Title=CCLC 105 Base Level Engineering
Current Plan=p01
Default Exp/Contr=0.3,0.1
English Units
Geom File=g01
Flow File=f01
Flow File=f02
Plan File=p01
Y Axis Title=Elevation
X Axis Title(PF)=Main Channel Distance
X Axis Title(XS)=Station
BEGIN DESCRIPTION:
CCLC 105
END DESCRIPTION:
DSS Export Rating Curves= 0
DSS Export Rating Curve Sorted= 0
DSS Export Volume Flow Curves= 0
DXF OffsetX= 0
DXF OffsetY= 0
DXF ScaleX= 1
DXF ScaleY= 10

--- CCLC 105.p01 (plan) ---

Plan Title=Multiple Run
Short Identifier=Multiple
Geom File=g01
Flow File=f01
Subcritical Flow
K Sum by GR= 0
Std Step Tol= 0.01
Critical Tol= 0.01
Num of Std Step Trials= 20
Max Error Tol= 0.3
Flow Tol Ratio= 0.001
Split Flow NTrial= 30
Split Flow Tol= 0.02
Split Flow Ratio= 0.02
Log Output Level= 0
Friction Slope Method= 1
Unsteady Friction Slope Method= 2
Unsteady Bridges Friction Slope Method= 1
Parabolic Critical Depth
Global Vel Dist=  1 , 1 , 1
Global Log Level= 0
CheckData=True
Encroach Param= -1, 0, 0, 0
BEGIN DESCRIPTION:
Multiple Run
END DESCRIPTION:

--- CCLC 105.f01 (steady flow) ---

Flow Title=Multiple
Program Version=4.10
Number of Profiles= 7
Profile Names=10-year,25-year,50-year,1pct_min,100-year,1pct_plu,500-year
River Rch & RM=CCLC 105,Reach-1         ,9585
     458     610     815     359    1083    3271    1973
River Rch & RM=CCLC 105,Reach-1         ,4979
    1129    1546    2102     935    2825    8531    5284
Boundary for River Rch & Prof#=CCLC 105,Reach-1         , 1
Up Type= 0
Dn Type= 3
Dn Slope=0.005
Boundary for River Rch & Prof#=CCLC 105,Reach-1         , 2
Up Type= 0
Dn Type= 3
Dn Slope=0.005
Boundary for River Rch & Prof#=CCLC 105,Reach-1         , 3
Up Type= 0
Dn Type= 3
Dn Slope=0.005
Boundary for River Rch & Prof#=CCLC 105,Reach-1         , 4
Up Type= 0
Dn Type= 3
Dn Slope=0.005
Boundary for River Rch & Prof#=CCLC 105,Reach-1         , 5
Up Type= 0
Dn Type= 3
Dn Slope=0.005
Boundary for River Rch & Prof#=CCLC 105,Reach-1         , 6
Up Type= 0
Dn Type= 3
Dn Slope=0.005
Boundary for River Rch & Prof#=CCLC 105,Reach-1         , 7
Up Type= 0
Dn Type= 3
Dn Slope=0.005
DSS Import GetInterval= 0
DSS Import GetPeak= 0
DSS Import FillOption= 0

--- CCLC 105.f02 (steady flow) ---

Flow Title=Orig_BLE_Flows
Program Version=4.10
Number of Profiles= 7
Profile Names=10-year,25-year,50-year,1pct_min,100-year,1pct_plu,500-year
River Rch & RM=CCLC 105,Reach-1         ,9585
     458     598     709     276     833    2514    1147
River Rch & RM=CCLC 105,Reach-1         ,4979
    1129    1516    1828     719    2173    6562    3072
Boundary for River Rch & Prof#=CCLC 105,Reach-1         , 1
Up Type= 0
Dn Type= 3
Dn Slope=0.005
Boundary for River Rch & Prof#=CCLC 105,Reach-1         , 2
Up Type= 0
Dn Type= 3
Dn Slope=0.005
Boundary for River Rch & Prof#=CCLC 105,Reach-1         , 3
Up Type= 0
Dn Type= 3
Dn Slope=0.005
Boundary for River Rch & Prof#=CCLC 105,Reach-1         , 4
Up Type= 0
Dn Type= 3
Dn Slope=0.005
Boundary for River Rch & Prof#=CCLC 105,Reach-1         , 5
Up Type= 0
Dn Type= 3
Dn Slope=0.005
Boundary for River Rch & Prof#=CCLC 105,Reach-1         , 6
Up Type= 0
Dn Type= 3
Dn Slope=0.005
Boundary for River Rch & Prof#=CCLC 105,Reach-1         , 7
Up Type= 0
Dn Type= 3
Dn Slope=0.005
DSS Import GetInterval= 0
DSS Import GetPeak= 0
DSS Import FillOption= 0

--- CCLC 105.g01 (geometry) ---

Geom Title=Existing Conditions
Program Version=4.10

River Reach=CCLC 105        ,Reach-1
Reach XY= 30
      3688133.23     10201576.84      3688478.23     10201766.84
      3688628.23     10201656.84      3688698.23     10201746.84
      3689038.23     10201666.84      3689228.23     10201926.84
      3689480.77     10201936.84      3689818.03      10202143.8
      3689993.93     10202721.96      3690384.17     10202711.75
       3690591.9      10202945.9      3690572.09     10203163.83
      3690955.13     10203265.89      3691118.23     10203426.84
      3691368.23     10203156.84      3691348.23     10203036.84
      3691558.23     10203066.84      3691568.23     10202766.84
      3692248.23     10202396.84      3692518.23     10202366.84
      3692518.23     10202476.84      3692708.23     10202566.84
      3692768.23     10202406.84      3693028.23     10202336.84
      3693038.23     10202486.84      3693308.23     10202716.84
      3693388.23     10202556.84      3693478.23     10202716.84
      3693848.23     10202696.84      3693908.23     10202786.84

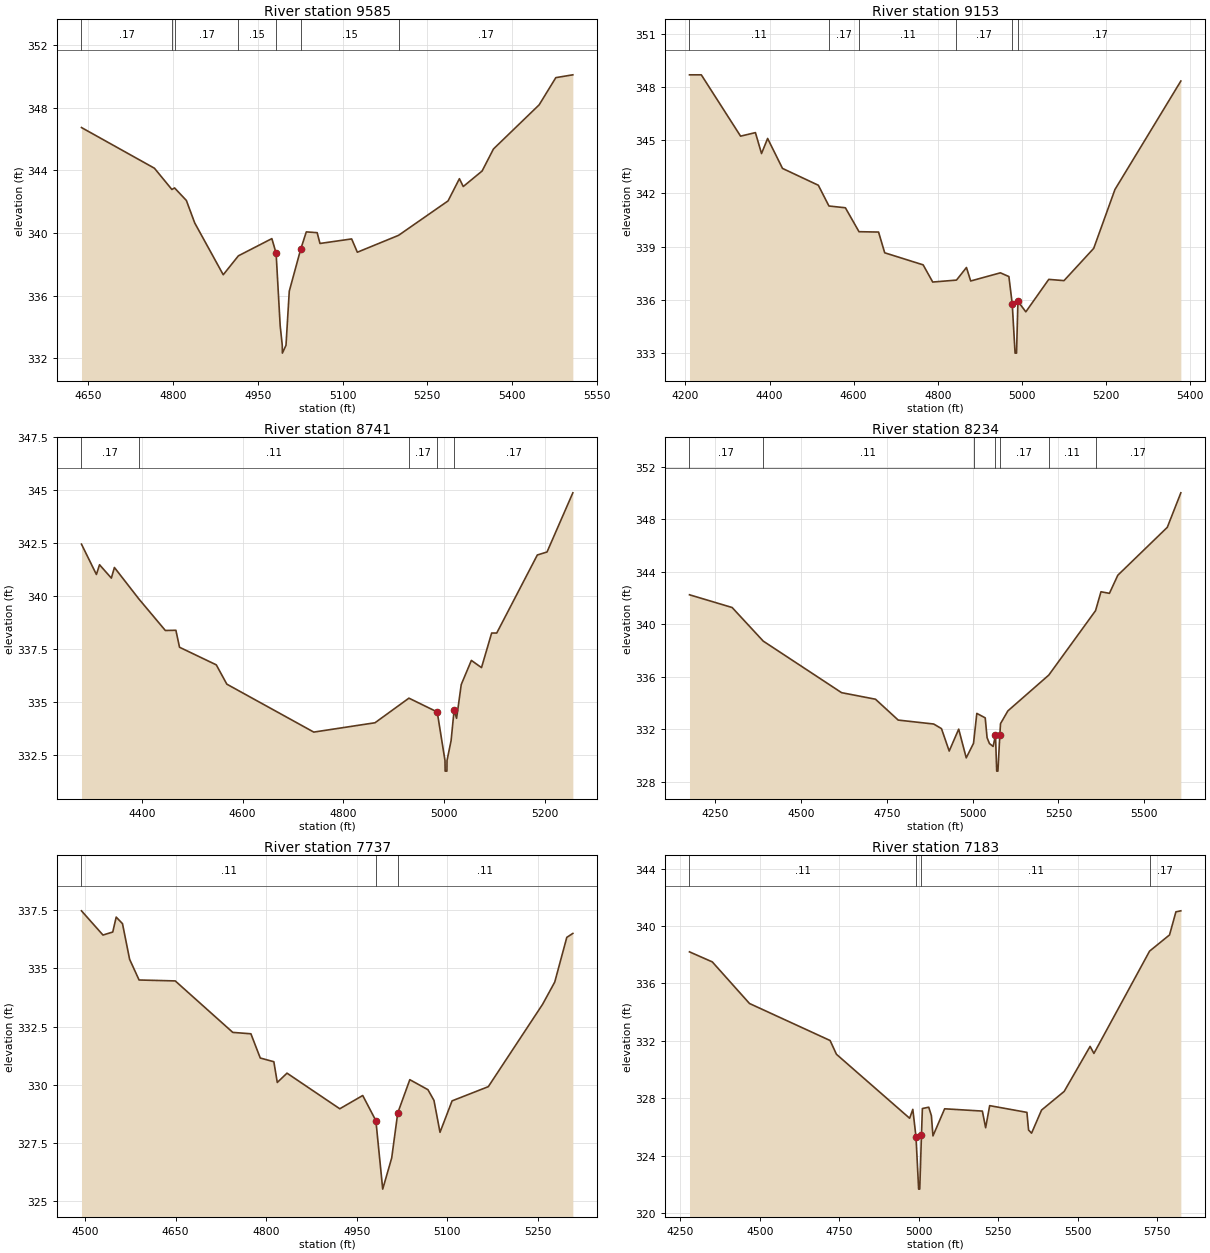
Type RM Length L Ch R = 1 ,9585    ,432,432,432
BEGIN DESCRIPTION:
CCLC 105 8.0
END DESCRIPTION:
XS GIS Cut Line= 3
      3688067.85     10201961.07      3688278.23     10201666.84
      3688317.85     10201161.09
#Sta/Elev= 30
  4638.3  346.74  4767.3  344.14  4798.2  342.78  4802.9  342.88  4823.8  342.08
  4838.6  340.64    4889  337.33  4915.8  338.54    4975  339.64  4982.5  338.71
  4989.7  334.08  4993.4  332.82  4993.6  332.32    5000  332.82  5005.8  336.28
  5025.9  338.95  5035.9  340.07  5055.1  340.02  5060.1  339.33  5116.1  339.62
  5126.2  338.77  5199.1  339.85  5286.6  342.05  5306.7  343.47  5313.5  342.97
  5346.8  343.96  5366.9  345.37  5447.7  348.19  5477.2  349.93  5507.3  350.11
#Mann= 7 ,-1 , 0
  4638.3     .17       0  4798.2     .15       0  4802.9     .17       0
  4915.8     .15       0  4982.5     .09       0  5025.9     .15       0
  5199.1     .17       0
Bank Sta=4982.5,5025.9
XS Rating Curve= 0 ,0
Exp/Cntr=0.3,0.1

Type RM Length L Ch R = 1 ,9153    ,412,412,412
BEGIN DESCRIPTION:
CCLC 105 7.0
END DESCRIPTION:
XS GIS Cut Line= 3
      3688117.86     10202211.07      3688600.59     10201840.93
      3688674.34     10201285.71
#Sta/Elev= 30
  4209.7  348.69  4237.8  348.69  4331.2  345.23  4366.5  345.43    4381  344.25
  4395.5   345.1  4430.9  343.41  4516.1  342.46  4541.3  341.29  4580.4  341.19
  4612.8  339.84  4659.3  339.82  4673.9  338.65  4765.3  337.97  4788.1     337
  4844.6  337.11  4868.3  337.82  4878.4  337.06    4949  337.52  4969.2  337.31
 4977.13 335.779  4983.9  332.99  4987.4  332.99  4990.7  335.91  5009.5  335.32
    5064  337.15  5100.3  337.08  5170.9   338.9  5221.4  342.22  5378.1  348.34
#Mann= 6 ,-1 , 0
  4209.7     .11       0  4541.3     .17       0  4612.8     .11       0
  4844.6     .17       0 4977.13     .09       0  4990.7     .17       0
Bank Sta=4977.13,4990.7
XS Rating Curve= 0 ,0
Exp/Cntr=0.3,0.1

Type RM Length L Ch R = 1 ,8741    ,507,507,507
BEGIN DESCRIPTION:
CCLC 105 6.0
END DESCRIPTION:
XS GIS Cut Line= 3
      3688479.04     10202153.45      3688921.78     10201840.93
      3688967.86     10201411.03
#Sta/Elev= 30
  4280.5  342.46  4310.1  341.03  4316.3  341.49  4339.7  340.86  4345.8  341.36
  4394.2  339.88  4446.8  338.39  4467.7   338.4  4474.9   337.6  4547.8  336.77
  4568.7  335.86  4741.1   333.6  4862.5  334.04  4929.8   335.2  4985.9334.5483
  5001.3  332.26  5001.6  331.76  5005.1  331.76  5005.3  332.26  5013.4   333.2
  5019.3  334.62  5024.3  334.25  5033.5  335.84  5053.6  336.98  5073.7  336.64
  5093.8  338.27  5103.9  338.27  5184.4  341.95  5203.6  342.09  5254.8  344.88
#Mann= 5 ,-1 , 0
  4280.5     .17       0  4394.2     .11       0  4929.8     .17       0
  4985.9     .09       0  5019.3     .17       0
Bank Sta=4985.9,5019.3
XS Rating Curve= 0 ,0
Exp/Cntr=0.3,0.1

Type RM Length L Ch R = 1 ,8234    ,497,497,497
BEGIN DESCRIPTION:
CCLC 105 5.0
END DESCRIPTION:
XS GIS Cut Line= 3
      3688517.83     10202311.08      3689248.23     10201926.84
      3689467.85     10201361.08
#Sta/Elev= 30
  4174.7  342.26    4299  341.29  4389.6  338.73    4618   334.8  4716.9   334.3
  4783.1  332.71  4886.6  332.41  4909.2  332.06  4931.7  330.35  4959.4  332.02
  4981.4  329.83  5002.6  330.94  5012.2  333.22  5036.7  332.88  5042.1  331.37
  5049.1  330.92  5059.8   330.7  5066.6  331.57  5070.2  328.82  5073.7  328.82
  5079.3331.5852  5081.3  332.44  5102.7  333.41    5222  336.14  5358.3  341.05
  5374.1  342.49  5398.7  342.37  5423.2  343.75  5567.4   347.4  5606.9  350.03
#Mann= 7 ,-1 , 0
  4174.7     .17       0  4389.6     .11       0  5002.6     .17       0
  5066.6    .065       0  5079.3     .17       0    5222     .11       0
  5358.3     .17       0
Bank Sta=5066.6,5079.3
XS Rating Curve= 0 ,0
Exp/Cntr=0.3,0.1

Type RM Length L Ch R = 1 ,7737    ,554,554,554
BEGIN DESCRIPTION:
CCLC 105 4.0
END DESCRIPTION:
XS GIS Cut Line= 3
      3689217.83     10202311.08      3689661.97     10202069.06
      3689667.85     10201761.12
#Sta/Elev= 30
  4494.2  337.47  4529.8  336.43    4546  336.56  4551.7   337.2  4562.1  336.92
  4573.9  335.39  4589.6   334.5  4649.5  334.46  4744.8  332.25  4774.8  332.19
  4790.3  331.15  4812.8  330.99  4818.5   330.1  4834.6   330.5    4922  328.97
    4960  329.54  4981.8  328.46  4993.1  325.52    5008  326.86    5018  328.79
    5038  330.22    5068  329.79    5078  329.33    5088  327.96    5108  329.31
    5168  329.92    5258  333.46    5278  334.41    5298  336.33    5308   336.5
#Mann= 3 , 0 , 0
  4494.2     .11       0  4981.8    .065       0    5018     .11       0
Bank Sta=4981.8,5018
XS Rating Curve= 0 ,0
Exp/Cntr=0.3,0.1

Type RM Length L Ch R = 1 ,7183    ,415,415,415
BEGIN DESCRIPTION:
Mapping XS 7f39f3ac
END DESCRIPTION:
XS GIS Cut Line= 3
       3689156.1      10202366.1      3689985.14     10202409.51
      3690162.83     10201716.09
#Sta/Elev= 30
    4279   338.2  4350.8   337.5  4467.8   334.6  4721.4  332.02  4741.4  331.06
  4971.7   326.6  4981.7  327.22  4991.7   325.3    5000  321.66  5003.5  321.66
  5008.9325.4469  5011.8  327.28  5031.8  327.37  5040.1  326.78  5045.1  325.37
  5081.8  327.26  5200.5   327.1  5210.8  325.94  5223.5  327.48  5340.7  327.01
  5345.9  325.78  5355.3  325.56  5386.7  327.17  5457.9  328.47  5539.5  331.61
  5551.5  331.12  5726.6  338.25  5789.4  339.38  5809.5  340.99    5825  341.06
#Mann= 4 ,-1 , 0
    4279     .11       0  4991.7    .065       0  5008.9     .11       0
  5726.6     .17       0
Bank Sta=4991.7,5008.9
XS Rating Curve= 0 ,0
Exp/Cntr=0.3,0.1

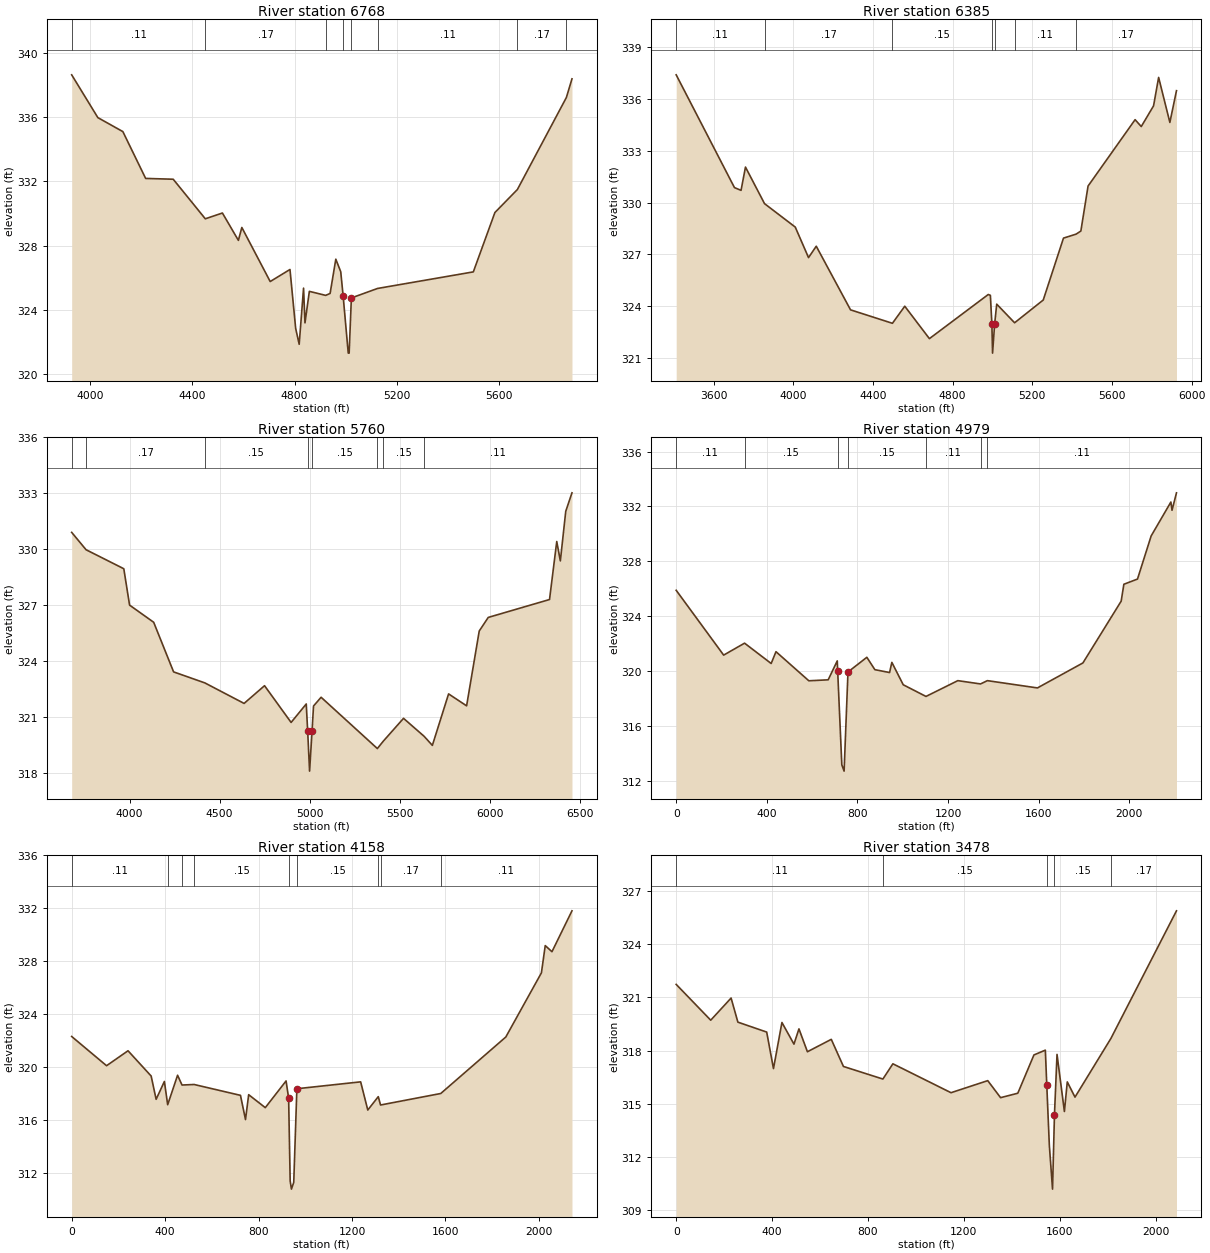
Type RM Length L Ch R = 1 ,6768    ,383,383,383
BEGIN DESCRIPTION:
CCLC 105 3.0
END DESCRIPTION:
XS GIS Cut Line= 3
      3689117.13     10202383.49      3689998.16     10202804.47
      3690267.84     10201861.11
#Sta/Elev= 30
  3927.7  338.62  4030.1  335.96    4128  335.09  4217.1  332.18    4325  332.13
  4450.6  329.67  4517.5  330.03    4580  328.33  4593.5  329.13  4704.5  325.77
  4781.9  326.52  4804.1  322.86  4817.9  321.87    4835  325.36  4840.6   323.2
  4857.7  325.16  4921.5  324.91  4938.9  325.03  4961.2  327.16  4980.5  326.38
  4989.8  324.89  5009.9  321.32  5013.4  321.32  5022.1  324.75  5124.5  325.34
  5499.3  326.37  5583.7  330.06  5671.7  331.49  5863.4  337.21  5885.3  338.37
#Mann= 8 ,-1 , 0
  3927.7     .11       0  4450.6     .17       0  4921.5     .15       0
  4989.8     .09       0  5022.1     .15       0  5124.5     .11       0
  5671.7     .17       0  5863.4     .11       0
Bank Sta=4989.8,5022.1
XS Rating Curve= 0 ,0
Exp/Cntr=0.3,0.1

Type RM Length L Ch R = 1 ,6385    ,625,625,625
BEGIN DESCRIPTION:
CCLC 105 2.0
END DESCRIPTION:
XS GIS Cut Line= 3
      3689147.46     10202435.54      3690275.94     10203012.81
      3690692.61     10201840.94
#Sta/Elev= 30
  3412.6  337.41  3705.1  330.87  3738.2  330.71  3760.4  332.06    3856  329.94
  4010.3  328.58  4076.9  326.81  4115.7  327.47  4287.8  323.78  4498.1     323
    4560  323.99  4683.7  322.11  4979.2  324.67  4989.8  324.62  4997.2  322.97
  5000.7  321.27    5011  322.95  5021.6  324.11  5111.3  323.03  5255.1  324.35
  5356.7  327.94  5419.9  328.17  5443.9  328.35  5480.1  330.96  5716.2  334.81
  5747.1  334.41  5808.8  335.61  5834.3  337.26  5890.7  334.65  5923.9  336.49
#Mann= 7 ,-1 , 0
  3412.6     .11       0    3856     .17       0  4498.1     .15       0
  4997.2     .09       0    5011     .15       0  5111.3     .11       0
  5419.9     .17       0
Bank Sta=4997.2,5011
XS Rating Curve= 0 ,0
Exp/Cntr=0.3,0.1

Type RM Length L Ch R = 1 ,5760    ,781,781,781
BEGIN DESCRIPTION:
Mapping XS e37a9e55
END DESCRIPTION:
XS GIS Cut Line= 4
      3689366.17     10202626.34      3690501.57     10203164.53
      3690876.57     10203108.97      3690814.07     10201966.57
#Sta/Elev= 30
    3678   330.9  3757.8  329.97  3967.6  328.95  3999.7     327  4133.6  326.08
  4244.3  323.42  4417.9  322.83  4635.9  321.73  4749.6  322.68  4897.2  320.71
  4981.3   321.7  4989.3  320.23  4999.8   318.1 5013.49320.2412  5021.7  321.59
  5063.8  322.06  5376.4  319.31  5408.9   319.7  5521.8  320.93  5635.9  319.97
    5682  319.48  5772.2  322.24  5872.3   321.6  5942.4  325.61  5992.5  326.34
    6333   327.3  6373.1  330.41  6393.1  329.37  6423.1  332.03  6457.7  333.02
#Mann= 8 ,-1 , 0
    3678     .11       0  3757.8     .17       0  4417.9     .15       0
  4989.3     .09       0 5013.49     .15       0  5376.4     .11       0
  5408.9     .15       0  5635.9     .11       0
Bank Sta=4989.3,5013.49
XS Rating Curve= 0 ,0
Exp/Cntr=0.3,0.1

Type RM Length L Ch R = 1 ,4979    ,821,821,821
BEGIN DESCRIPTION:
Mapping XS 1fd35e3b
END DESCRIPTION:
XS GIS Cut Line= 4
      3690781.01     10204056.19      3690981.08      10203773.9
      3691126.57       10203543.      3690980.74     10201959.67
#Sta/Elev= 30
       0  325.89   209.6  321.17   301.9  322.04   419.4  320.56   440.6  321.42
   585.7   319.3   671.1  319.37   711.2  320.75  713.07     320   731.3  313.18
   741.4  312.72  758.52  319.94   841.8  321.01   877.2  320.11   942.2   319.9
   952.2  320.64  1002.5  319.01  1102.9  318.16  1243.5  319.31  1343.9  319.07
    1374  319.31    1595  318.78  1795.8   320.6  1964.7   325.1  1976.6  326.33
  2036.8  326.71  2097.1  329.85  2184.2  332.32  2189.2  331.72  2208.9  332.99
#Mann= 7 ,-1 , 0
       0     .11       0   301.9     .15       0  713.07     .09       0
  758.52     .15       0  1102.9     .11       0  1343.9     .17       0
    1374     .11       0
Bank Sta=713.07,758.52
XS Rating Curve= 0 ,0
Exp/Cntr=0.3,0.1

Type RM Length L Ch R = 1 ,4158    ,680,680,680
BEGIN DESCRIPTION:
Mapping XS 39f34499
END DESCRIPTION:
XS GIS Cut Line= 4
       3690975.9     10203800.27      3691309.61     10203463.33
      3691564.07     10203174.95      3691046.71     10202001.33
#Sta/Elev= 30
       0   322.3   149.3  320.09   241.2  321.22   340.2  319.31   361.5  317.55
   396.8   318.9   410.9  317.14   453.3  319.37   472.3  318.63   524.2  318.67
   722.5  317.85     744  316.02   757.6   317.9   828.7  316.92   917.7  318.94
   928.6  317.64   935.2  311.38   940.6  310.76   950.5  311.27   963.9  318.35
  1236.9  318.87  1267.4  316.74  1312.3  317.75  1322.1  317.12  1579.8  317.99
  1858.2  322.26  2010.6  327.11    2027  329.17  2055.8  328.71  2141.4   331.8
#Mann= 9 ,-1 , 0
       0     .11       0   410.9     .15       0   472.3     .12       0
   524.2     .15       0   928.6     .07       0   963.9     .15       0
  1312.3     .11       0  1322.1     .17       0  1579.8     .11       0
Bank Sta=928.6,963.9
XS Rating Curve= 0 ,0
Exp/Cntr=0.3,0.1

Type RM Length L Ch R = 1 ,3478    ,585,585,585
BEGIN DESCRIPTION:
Mapping XS 9b2ecedf
END DESCRIPTION:
XS GIS Cut Line= 4
       3691006.4     10203803.42      3691322.81     10203464.84
      3691883.52     10203029.11      3691557.13     10202174.95
#Sta/Elev= 30
       0  321.73   144.1  319.71   229.1  320.96   257.4   319.6   377.6  319.04
   405.9  316.98   441.2  319.58   491.4  318.36   512.2  319.22   547.5  317.93
   647.1  318.63   697.8   317.1   862.4  316.39   904.1  317.25  1146.6  315.62
  1299.9   316.3  1353.4  315.34  1425.3  315.59  1492.6  317.75  1540.2  318.02
  1546.1  316.07  1556.8  312.66  1570.2  310.18  1578.2  314.36  1588.9  317.78
  1619.7  314.56  1631.7  316.23  1663.9  315.37  1813.7  318.68  2087.3  325.88
#Mann= 5 ,-1 , 0
       0     .11       0   862.4     .15       0  1546.1     .09       0
  1578.2     .15       0  1813.7     .17       0
Bank Sta=1546.1,1578.2
XS Rating Curve= 0 ,0
Exp/Cntr=0.3,0.1

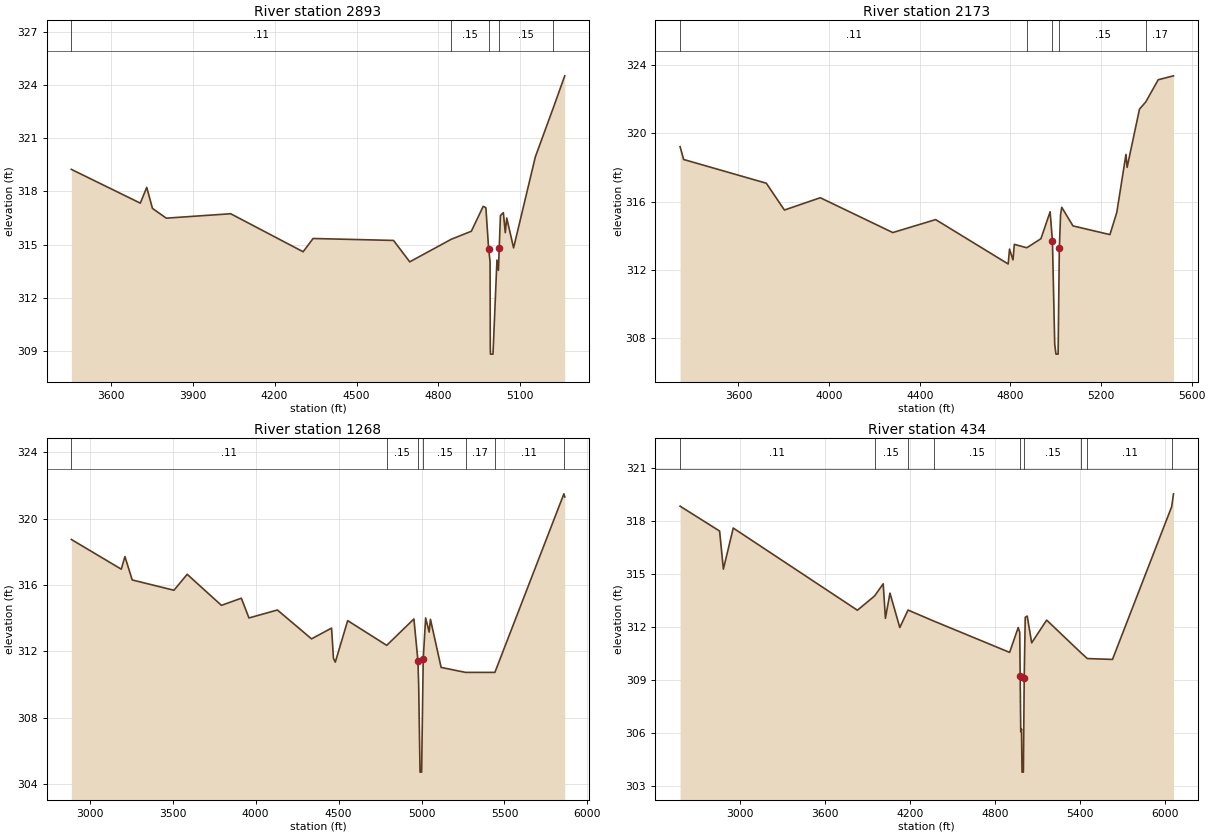
Type RM Length L Ch R = 1 ,2893    ,720,720,720
BEGIN DESCRIPTION:
Mapping XS 64e7480d
END DESCRIPTION:
XS GIS Cut Line= 3
      3691320.99     10203477.05      3692300.18     10202796.47
      3692088.36     10202220.04
#Sta/Elev= 30
  3455.7  319.25  3708.2  317.34  3731.8  318.23  3752.8  317.04  3803.4  316.49
  4039.1  316.74  4304.4  314.59  4340.9  315.34  4635.3  315.23  4694.8  314.02
  4847.2   315.3  4920.3  315.75  4963.8  317.16  4973.5  317.08  4983.6  314.77
  4988.9  314.03  4989.7   309.3  4990.2   308.8  4999.6   308.8  5014.1  314.12
  5019.4  313.54 5022.46314.8219  5026.8  316.64  5037.5   316.8  5044.6  315.67
  5049.9   316.5    5075  314.81  5154.7  319.96  5220.6  322.74  5262.3  324.54
#Mann= 5 ,-1 , 0
  3455.7     .11       0  4847.2     .15       0  4983.6     .09       0
 5022.46     .15       0  5220.6     .17       0
Bank Sta=4983.6,5022.46
XS Rating Curve= 0 ,0
Exp/Cntr=0.3,0.1

Type RM Length L Ch R = 1 ,2173    ,905,905,905
BEGIN DESCRIPTION:
Mapping XS 93ae08fc
END DESCRIPTION:
XS GIS Cut Line= 3
      3691324.49      10203480.5      3692640.46     10202664.53
      3692747.83     10202044.57
#Sta/Elev= 30
  3342.3  319.22    3358  318.47  3722.8  317.08  3802.7  315.51    3961  316.23
  4281.1  314.19  4470.1  314.95  4790.3  312.35  4796.1  313.22  4811.5  312.59
  4817.4   313.5  4872.5   313.3  4934.8  313.83  4975.4  315.41  4985.6  313.69
  4995.7  307.64  5001.2  307.07  5010.6  307.07    5016  313.26  5021.5  315.23
  5026.6  315.67  5076.2  314.58  5239.3  314.07  5269.7  315.37  5310.1  318.77
  5315.2  318.01  5369.8  321.42  5397.4  321.84  5452.4  323.14  5519.9  323.37
#Mann= 5 ,-1 , 0
  3342.3     .11       0  4872.5     .15       0  4985.6     .09       0
    5016     .15       0  5397.4     .17       0
Bank Sta=4985.6,5016
XS Rating Curve= 0 ,0
Exp/Cntr=0.3,0.1

Type RM Length L Ch R = 1 ,1268    ,834,834,834
BEGIN DESCRIPTION:
Mapping XS d07a19f7
END DESCRIPTION:
XS GIS Cut Line= 4
      3691334.94     10203487.43      3693095.32     10202671.47
      3693369.63     10202317.31      3693089.08     10201804.71
#Sta/Elev= 30
  2890.4  318.74  3191.2  316.95  3213.2  317.71  3257.3   316.3  3508.6  315.68
  3588.4  316.64  3794.6  314.77  3914.6   315.2  3960.5  314.01  4131.9  314.49
  4337.5  312.75  4458.1   313.4  4469.7  311.57  4480.8  311.35  4555.3  313.85
  4790.5  312.36  4954.3  313.95 4978.56311.4313    4983  309.97  4991.2  304.72
  5000.7  304.72  5010.4  311.53  5024.9  314.01  5046.2  313.16  5053.9  313.93
  5118.2  311.03  5265.5  310.73  5442.1  310.73  5857.9  321.49    5863   321.3
#Mann= 7 ,-1 , 0
  2890.4     .11       0  4790.5     .15       0 4978.56     .09       0
  5010.4     .15       0  5265.5     .17       0  5442.1     .11       0
  5857.9     .17       0
Bank Sta=4978.56,5010.4
XS Rating Curve= 0 ,0
Exp/Cntr=0.3,0.1

Type RM Length L Ch R = 1 ,434     ,0,0,0
BEGIN DESCRIPTION:
CCLC 105 1.0
END DESCRIPTION:
XS GIS Cut Line= 3
       3691355.7     10203490.93      3693612.68     10202761.75
        3693262.     10201713.19
#Sta/Elev= 30
  2580.8  318.84  2859.2  317.43    2886  315.27  2955.3   317.6  3830.5  312.94
  3951.8  313.75  4012.3  314.44  4027.9  312.48    4060  313.91  4129.3  311.96
  4187.2  312.95  4367.5  312.33  4903.2  310.55  4963.9  311.96  4974.5  311.69
 4977.68309.1989  4981.7  306.05    4987  306.21  4990.8  303.76  5000.3  303.76
  5006.1  309.12  5013.3  312.54  5027.2  312.61  5058.8  311.09  5164.3  312.38
  5405.9  310.53  5450.9   310.2  5628.2  310.15  6045.4  318.81  6058.3  319.54
#Mann= 9 ,-1 , 0
  2580.8     .11       0  3951.8     .15       0  4187.2     .11       0
  4367.5     .15       0 4977.68     .09       0  5006.1     .15       0
  5405.9     .17       0  5450.9     .11       0  6045.4     .17       0
Bank Sta=4977.68,5006.1
XS Rating Curve= 0 ,0
Exp/Cntr=0.3,0.1

Chan Stop Cuts=-1
Use User Specified Reach Order=0
Composite Channel Slope=5