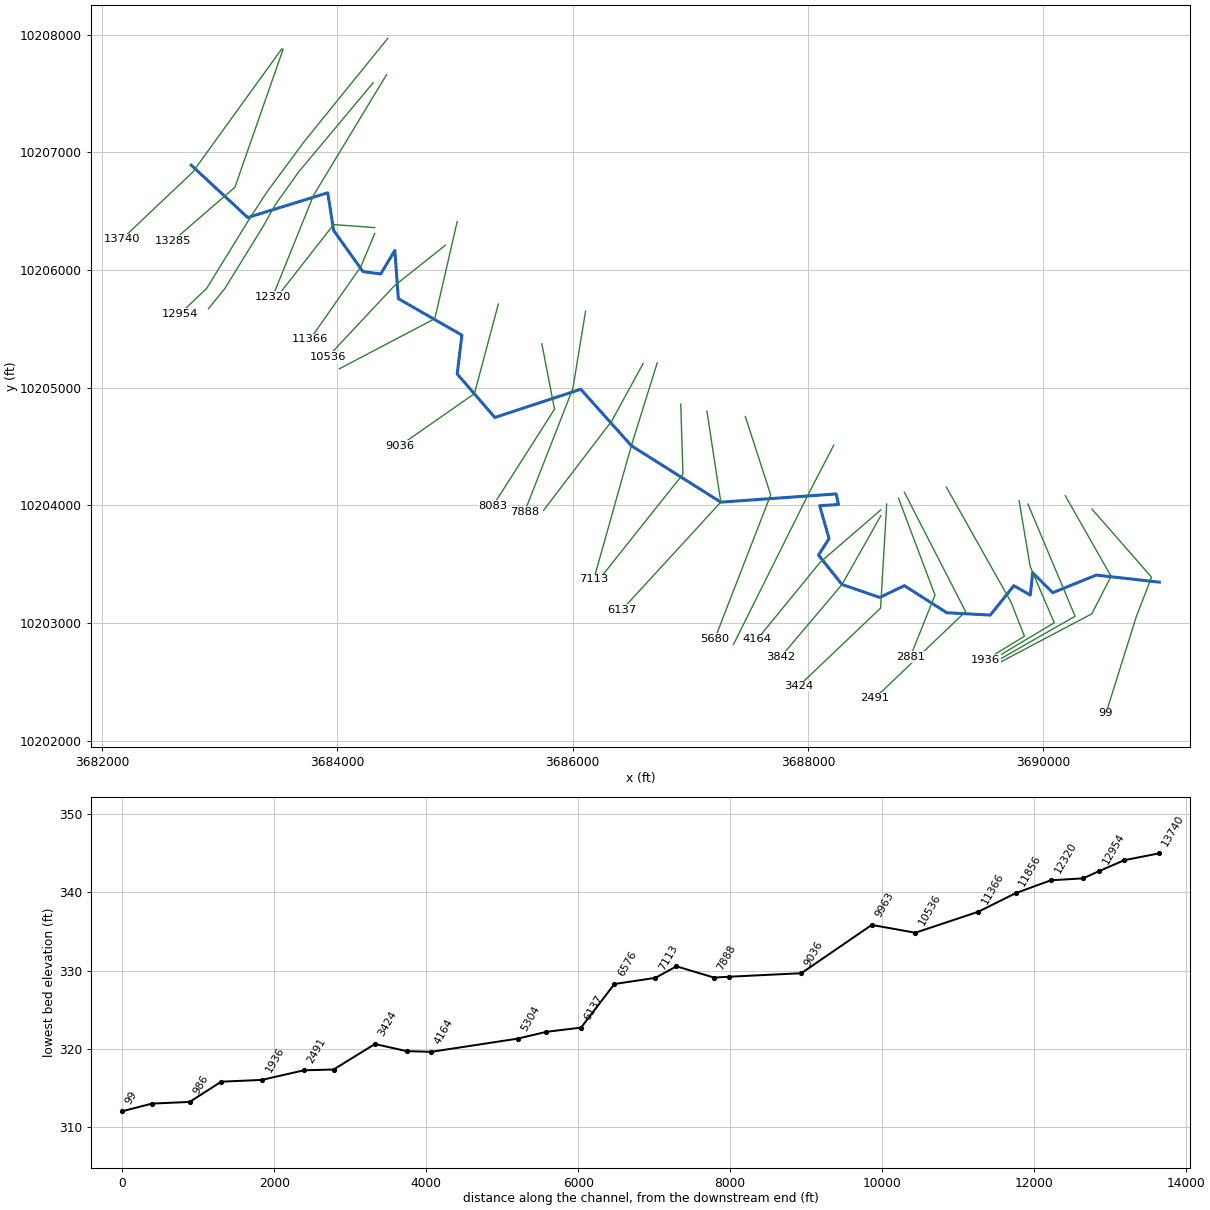
--- CCLC 106.prj (project) ---

Proj Title=CCLC 106 Base Level Engineering
Current Plan=p01
Default Exp/Contr=0.3,0.1
English Units
Geom File=g01
Flow File=f01
Flow File=f02
Plan File=p01
Y Axis Title=Elevation
X Axis Title(PF)=Main Channel Distance
X Axis Title(XS)=Station
BEGIN DESCRIPTION:
CCLC 106
END DESCRIPTION:
DSS Export Rating Curves= 0
DSS Export Rating Curve Sorted= 0
DSS Export Volume Flow Curves= 0
DXF OffsetX= 0
DXF OffsetY= 0
DXF ScaleX= 1
DXF ScaleY= 10

--- CCLC 106.p01 (plan) ---

Plan Title=Multiple Run
Short Identifier=Multiple
Geom File=g01
Flow File=f01
Subcritical Flow
K Sum by GR= 0
Std Step Tol= 0.01
Critical Tol= 0.01
Num of Std Step Trials= 20
Max Error Tol= 0.3
Flow Tol Ratio= 0.001
Split Flow NTrial= 30
Split Flow Tol= 0.02
Split Flow Ratio= 0.02
Log Output Level= 0
Friction Slope Method= 1
Unsteady Friction Slope Method= 2
Unsteady Bridges Friction Slope Method= 1
Parabolic Critical Depth
Global Vel Dist=  1 , 1 , 1
Global Log Level= 0
CheckData=True
Encroach Param= -1, 0, 0, 0
BEGIN DESCRIPTION:
Multiple Run
END DESCRIPTION:

--- CCLC 106.f01 (steady flow) ---

Flow Title=Multiple
Program Version=4.10
Number of Profiles= 7
Profile Names=10-year,25-year,50-year,1pct_min,100-year,1pct_plu,500-year
River Rch & RM=CCLC 106,Reach-1         ,13740
     800    1104    1510     679    2050    6191    3913
River Rch & RM=CCLC 106,Reach-1         ,11856
    1040    1443    1981     893    2696    8142    5165
River Rch & RM=CCLC 106,Reach-1         ,6576
     938    1274    1722     762    2302    6952    4267
River Rch & RM=CCLC 106,Reach-1         ,99
    1129    1546    2102     935    2825    8531    5284
Boundary for River Rch & Prof#=CCLC 106,Reach-1         , 1
Up Type= 0
Dn Type= 3
Dn Slope=0.01
Boundary for River Rch & Prof#=CCLC 106,Reach-1         , 2
Up Type= 0
Dn Type= 3
Dn Slope=0.01
Boundary for River Rch & Prof#=CCLC 106,Reach-1         , 3
Up Type= 0
Dn Type= 3
Dn Slope=0.01
Boundary for River Rch & Prof#=CCLC 106,Reach-1         , 4
Up Type= 0
Dn Type= 3
Dn Slope=0.01
Boundary for River Rch & Prof#=CCLC 106,Reach-1         , 5
Up Type= 0
Dn Type= 3
Dn Slope=0.01
Boundary for River Rch & Prof#=CCLC 106,Reach-1         , 6
Up Type= 0
Dn Type= 3
Dn Slope=0.01
Boundary for River Rch & Prof#=CCLC 106,Reach-1         , 7
Up Type= 0
Dn Type= 3
Dn Slope=0.01
DSS Import GetInterval= 0
DSS Import GetPeak= 0
DSS Import FillOption= 0

--- CCLC 106.f02 (steady flow) ---

Flow Title=Orig_BLE_Flows
Program Version=4.10
Number of Profiles= 7
Profile Names=10-year,25-year,50-year,1pct_min,100-year,1pct_plu,500-year
River Rch & RM=CCLC 106,Reach-1         ,13740
     800    1082    1313     522    1577    4762    2275
River Rch & RM=CCLC 106,Reach-1         ,11856
    1040    1415    1723     687    2074    6262    3003
River Rch & RM=CCLC 106,Reach-1         ,6576
     938    1249    1497     587    1771    5349    2481
River Rch & RM=CCLC 106,Reach-1         ,99
    1129    1516    1828     719    2173    6562    3072
Boundary for River Rch & Prof#=CCLC 106,Reach-1         , 1
Up Type= 0
Dn Type= 3
Dn Slope=0.005
Boundary for River Rch & Prof#=CCLC 106,Reach-1         , 2
Up Type= 0
Dn Type= 3
Dn Slope=0.005
Boundary for River Rch & Prof#=CCLC 106,Reach-1         , 3
Up Type= 0
Dn Type= 3
Dn Slope=0.005
Boundary for River Rch & Prof#=CCLC 106,Reach-1         , 4
Up Type= 0
Dn Type= 3
Dn Slope=0.005
Boundary for River Rch & Prof#=CCLC 106,Reach-1         , 5
Up Type= 0
Dn Type= 3
Dn Slope=0.005
Boundary for River Rch & Prof#=CCLC 106,Reach-1         , 6
Up Type= 0
Dn Type= 3
Dn Slope=0.005
Boundary for River Rch & Prof#=CCLC 106,Reach-1         , 7
Up Type= 0
Dn Type= 3
Dn Slope=0.005
DSS Import GetInterval= 0
DSS Import GetPeak= 0
DSS Import FillOption= 0

--- CCLC 106.g01 (geometry) ---

Geom Title=Existing Conditions
Program Version=4.10

River Reach=CCLC 106        ,Reach-1
Reach XY= 30
      3682758.23     10206891.84      3683238.23     10206446.84
      3683918.23     10206656.84      3683968.23     10206336.84
      3684218.23     10205986.84      3684368.23     10205966.84
      3684488.23     10206166.84      3684518.23     10205756.84
      3685058.23     10205446.84      3685018.23     10205116.84
      3685338.23     10204746.84      3686068.23     10204986.84
      3686498.23     10204506.84      3687258.23     10204026.84
      3688238.23     10204096.84      3688258.23     10204006.84
      3688098.23     10203996.84      3688178.23     10203716.84
      3688088.23     10203576.84      3688288.23     10203326.84
      3688608.23     10203216.84      3688818.23     10203316.84
      3689178.23     10203086.84      3689548.23     10203066.84
      3689748.23     10203316.84      3689888.23     10203236.84
      3689908.23     10203426.84      3690078.23     10203256.84
      3690448.23     10203406.84      3690984.09     10203346.84

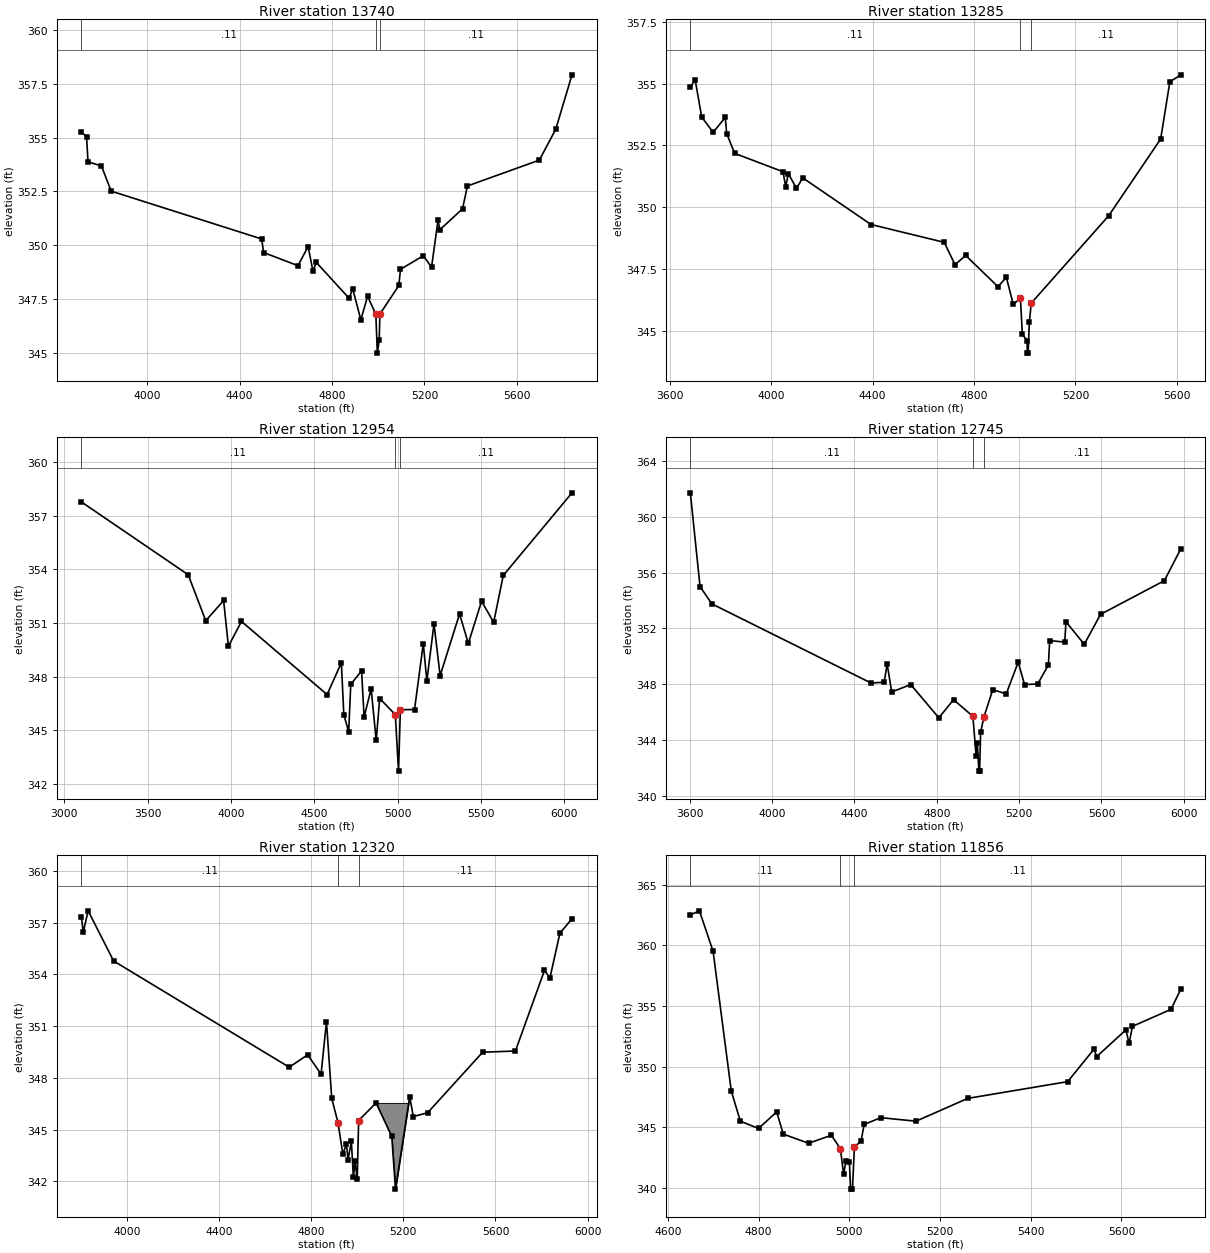
Type RM Length L Ch R = 1 ,13740   ,455,455,455
BEGIN DESCRIPTION:
CCLC 106 22.0
END DESCRIPTION:
XS GIS Cut Line= 3
      3683527.94     10207881.18      3682770.13     10206831.69
      3682167.82     10206261.04
#Sta/Elev= 30
    3715  355.26  3737.2  355.03  3743.4  353.87  3801.5  353.68    3844  352.51
  4495.4  350.29  4503.9  349.66  4652.6  349.05  4696.5  349.94  4717.4   348.8
  4732.1   349.2  4874.6  347.53  4889.2  347.99  4924.8  346.54  4954.2  347.63
  4989.8  346.79  4996.2  344.99  5004.5   345.6  5007.2   346.8  5089.4  348.13
  5096.3  348.88  5195.4  349.51    5231  348.98  5259.3  351.18  5266.2  350.71
  5365.3  351.69  5386.3  352.75  5697.8  353.95  5768.6  355.38  5839.2  357.91
#Mann= 3 , 0 , 0
    3715     .11       0  4989.8     .06       0  5007.2     .11       0
Bank Sta=4989.8,5007.2
XS Rating Curve= 0 ,0
Exp/Cntr=0.3,0.1

Type RM Length L Ch R = 1 ,13285   ,331,331,331
BEGIN DESCRIPTION:
CCLC 106 21.0
END DESCRIPTION:
XS GIS Cut Line= 3
      3683538.36     10207875.98       3683129.5     10206704.09
      3682606.06     10206250.96
#Sta/Elev= 30
  3681.9  354.84  3700.8  355.16  3726.6  353.65  3771.8  353.03  3819.8  353.63
  3825.1  352.98  3856.6  352.18  4047.2  351.44  4057.7  350.84  4068.4  351.36
  4100.2  350.77  4125.1  351.19  4394.1  349.31  4682.7  348.59    4725  347.69
  4767.4  348.06  4894.5   346.8  4927.5  347.18  4954.5  346.09    4983  346.33
  4990.6  344.88  5009.5  344.62  5009.7  344.12  5013.2  344.12  5018.1  345.37
  5025.7  346.14  5330.6  349.66  5535.7  352.76  5571.9  355.07  5615.4  355.35
#Mann= 3 , 0 , 0
  3681.9     .11       0    4983     .06       0  5025.7     .11       0
Bank Sta=4983,5025.7
XS Rating Curve= 0 ,0
Exp/Cntr=0.3,0.1

Type RM Length L Ch R = 1 ,12954   ,209,209,209
BEGIN DESCRIPTION:
CCLC 106 20.0
END DESCRIPTION:
XS GIS Cut Line= 6
      3684428.52     10207970.12      3683719.34     10207093.85
      3683400.33     10206661.99      3683244.08      10206421.1
      3682890.35     10205845.15      3682662.05     10205627.24
#Sta/Elev= 30
  3103.2  357.77  3743.4   353.7    3849  351.13  3956.1  352.26  3984.8   349.7
  4063.2  351.09  4576.9     347  4662.5  348.78  4677.2  345.87  4706.4  344.93
  4718.8  347.57  4783.8  348.33  4798.9  345.74  4841.1  347.32  4871.4  344.44
  4892.5  346.78  4986.1  345.88  5005.5  342.72  5016.4  346.16  5101.4  346.16
  5153.9  349.85  5175.3  347.76  5218.1  350.95    5255  348.06  5371.6  351.51
  5424.1  349.86  5503.5  352.22  5576.2  351.04  5633.7  353.66  6046.1  358.28
#Mann= 3 , 0 , 0
  3103.2     .11       0  4986.1     .06       0  5016.4     .11       0
Bank Sta=4986.1,5016.4
XS Rating Curve= 0 ,0
Exp/Cntr=0.3,0.1

Type RM Length L Ch R = 1 ,12745   ,425,425,425
BEGIN DESCRIPTION:
Mapping XS d093cda2
END DESCRIPTION:
XS GIS Cut Line= 6
      3684303.52     10207591.65       3683671.6     10206834.73
      3683473.68     10206556.95      3683366.05     10206365.98
      3683043.13     10205841.68      3682904.25     10205671.55
#Sta/Elev= 30
  3603.9   361.7    3651     355  3708.3  353.76  4481.4   348.1  4545.1  348.16
  4559.4  349.46  4581.6  347.46  4674.1  347.99  4810.5  345.61  4881.9  346.91
  4975.7  345.72  4991.6  342.88  4997.3  343.83  5004.9   341.8  5008.4   341.8
  5013.3  344.57  5029.2  345.67  5072.5  347.63  5137.5  347.32  5195.8  349.59
  5226.5  347.99  5290.4  348.03  5342.5   349.4  5348.4  351.13  5421.8  351.03
  5427.6  352.48  5516.4  350.87  5595.6  353.01  5905.5  355.42  5985.6  357.71
#Mann= 3 , 0 , 0
  3603.9     .11       0  4975.7     .06       0  5029.2     .11       0
Bank Sta=4975.7,5029.2
XS Rating Curve= 0 ,0
Exp/Cntr=0.3,0.1

Type RM Length L Ch R = 1 ,12320   ,464,464,464
BEGIN DESCRIPTION:
CCLC 106 19.0
END DESCRIPTION:
XS GIS Cut Line= 3
      3684417.87      10207661.1      3683798.23     10206636.84
      3683449.39     10205772.27
#Sta/Elev= 30
  3802.9  357.31  3810.7  356.46    3832  357.69  3942.6  354.78    4705  348.62
  4784.7  349.34  4843.1  348.22  4866.5  351.27  4889.3  346.82  4916.4  345.41
  4937.8  343.57  4953.3  344.18    4960  343.25  4974.6  344.32  4983.4  342.23
  4990.1  343.19    5000  342.14  5006.2  345.53  5081.7  346.55  5149.9  344.61
    5166  341.55  5227.7  346.91  5243.5  345.76  5305.6  345.98  5544.4  349.49
  5686.7  349.56  5812.9  354.24  5836.5   353.8  5879.7  356.39  5932.3  357.23
#Mann= 3 , 0 , 0
  3802.9     .11       0  4916.4     .06       0  5006.2     .11       0
#Block Obstruct= 1 ,-1
 5083.85 5227.48  346.55
Bank Sta=4916.4,5006.2
XS Rating Curve= 0 ,0
Exp/Cntr=0.3,0.1

Type RM Length L Ch R = 1 ,11856   ,490,490,490
BEGIN DESCRIPTION:
CCLC 106 18.0
END DESCRIPTION:
XS GIS Cut Line= 3
      3684317.88     10206361.07      3683968.23     10206386.84
      3683517.85     10205811.07
#Sta/Elev= 30
  4649.4   362.5  4669.5  362.84  4699.6   359.5  4739.7  347.98  4759.7   345.5
  4799.8   344.9  4839.9  346.27  4854.2  344.44  4910.1  343.68  4960.3  344.34
  4980.3  343.24  4987.4  341.11  4992.4  342.24    5000  342.17  5002.9   339.9
  5006.9   339.9  5011.2  343.39  5025.7  343.84  5032.7  345.23  5069.1  345.79
    5147   345.5  5261.2  347.38  5481.4  348.76  5539.3  351.43  5545.6  350.83
  5609.8  353.03  5616.7  351.91  5624.3  353.32  5709.3  354.72    5731   356.4
#Mann= 3 , 0 , 0
  4649.4     .11       0  4980.3     .06       0  5011.2     .11       0
Bank Sta=4980.3,5011.2
XS Rating Curve= 0 ,0
Exp/Cntr=0.3,0.1

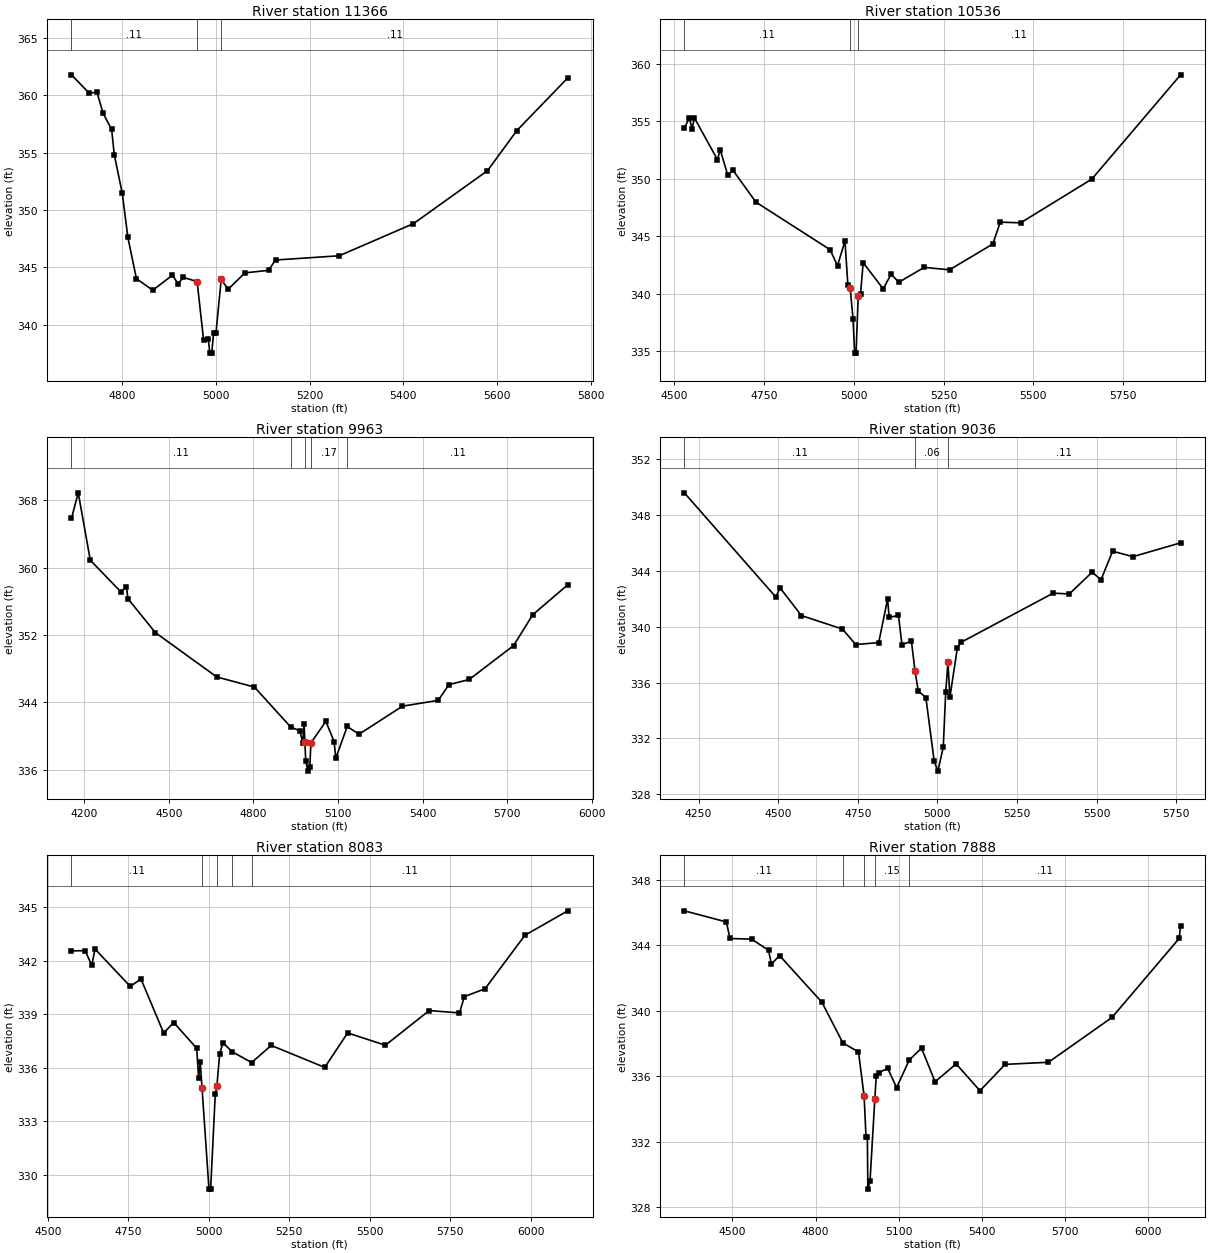
Type RM Length L Ch R = 1 ,11366   ,830,830,830
BEGIN DESCRIPTION:
CCLC 106 17.0
END DESCRIPTION:
XS GIS Cut Line= 3
      3684317.86      10206311.1      3684198.23     10206026.84
      3683767.83     10205411.04
#Sta/Elev= 30
  4691.6  361.77  4729.9  360.15  4745.9  360.28  4759.1  358.42  4777.4  357.01
  4782.9  354.83  4800.1  351.44    4812  347.61  4830.3  344.01  4865.2  343.01
    4907  344.31  4919.5  343.57  4930.3  344.13  4959.9  343.76  4973.7  338.67
  4983.6  338.79    4987  337.53    4991  337.53    4995  339.24    5000  339.24
  5011.3  343.95  5026.1  343.09  5061.9  344.52  5112.4  344.74  5127.3  345.64
  5263.3  346.01  5421.9  348.81  5579.9  353.42  5642.7  356.92  5751.3   361.5
#Mann= 3 ,-1 , 0
  4691.6     .11       0  4959.9     .06       0  5011.3     .11       0
Bank Sta=4959.9,5011.3
XS Rating Curve= 0 ,0
Exp/Cntr=0.3,0.1

Type RM Length L Ch R = 1 ,10536   ,573,573,573
BEGIN DESCRIPTION:
CCLC 106 16.0
END DESCRIPTION:
XS GIS Cut Line= 3
      3684917.83     10206211.05       3684484.1     10205865.98
      3683917.88      10205261.1
#Sta/Elev= 30
  4527.7  354.37  4541.3  355.28  4549.3  354.35  4555.7  355.28  4619.8  351.66
  4627.8   352.5  4648.6  350.31    4663  350.74  4727.1  347.96  4933.7  343.83
  4954.5  342.44  4975.3  344.58  4983.4  340.76  4989.8   340.5  4997.8  337.79
  5002.2  334.84  5006.2  334.84  5012.2  339.84  5018.6  339.94    5026   342.7
  5081.9  340.42  5103.8   341.7  5125.3     341  5196.1  342.29  5266.7  342.08
  5387.1  344.32  5408.1  346.22  5464.8  346.16  5663.1  349.96  5910.5  359.02
#Mann= 3 , 0 , 0
  4527.7     .11       0  4989.8     .06       0  5012.2     .11       0
Bank Sta=4989.8,5012.2
XS Rating Curve= 0 ,0
Exp/Cntr=0.3,0.1

Type RM Length L Ch R = 1 ,9963    ,927,927,927
BEGIN DESCRIPTION:
CCLC 106 15.0
END DESCRIPTION:
XS GIS Cut Line= 3
      3685017.86     10206411.11      3684828.23     10205586.84
      3684017.87     10205161.08
#Sta/Elev= 30
  4154.2  365.84  4178.2  368.88    4221  360.88  4328.7  357.15  4349.2  357.69
  4354.6  356.31  4451.8  352.29  4669.8  347.02  4803.4  345.82  4932.1  341.08
  4964.9  340.62  4974.7  339.22  4979.8  341.42 4982.55339.2937  4985.4  337.09
  4993.2  335.84    5000  336.34  5003.9  339.18  5056.9  341.75  5086.4  339.34
  5092.1  337.36  5132.8  341.14  5174.6  340.22  5328.9  343.55  5455.5  344.24
    5494  346.11  5565.8  346.72  5723.4  350.75  5791.2  354.41  5915.4  357.96
#Mann= 5 ,-1 , 0
  4154.2     .11       0  4932.1     .17       0 4982.55     .09       0
  5003.9     .17       0  5132.8     .11       0
Bank Sta=4982.55,5003.9
XS Rating Curve= 0 ,0
Exp/Cntr=0.3,0.1

Type RM Length L Ch R = 1 ,9036    ,953,953,953
BEGIN DESCRIPTION:
CCLC 106 14.0
END DESCRIPTION:
XS GIS Cut Line= 3
      3685367.86     10205711.09      3685164.66     10204949.32
      3684532.79      10204508.4
#Sta/Elev= 30
  4205.2  349.58    4493  342.11  4505.4  342.79  4573.2  340.79    4702  339.83
  4743.4  338.72  4815.8  338.86  4843.6  341.97  4848.7  340.67  4877.9   340.8
  4888.8  338.71  4918.6  338.96  4929.7  336.85    4940   335.4  4963.9  334.93
  4990.1  330.36  5001.5  329.66  5018.5  331.36  5026.3  335.33  5033.3  337.45
  5039.4  334.95  5062.9  338.49  5075.2  338.89  5363.9   342.4  5414.5  342.34
  5486.1   343.9  5514.1  343.36  5550.6   345.4  5614.3  345.01  5764.1     346
#Mann= 3 ,-1 , 0
  4205.2     .11       0  4929.7     .06       0  5033.3     .11       0
Bank Sta=4929.7,5033.3
XS Rating Curve= 0 ,0
Exp/Cntr=0.3,0.1

Type RM Length L Ch R = 1 ,8083    ,195,195,195
BEGIN DESCRIPTION:
CCLC 106 13.0
END DESCRIPTION:
XS GIS Cut Line= 3
      3685737.57     10205372.94      3685845.21     10204817.37
      3685320.88     10203994.41
#Sta/Elev= 30
  4573.7  342.54  4616.3  342.55  4636.7  341.73  4646.9  342.64  4756.5  340.55
  4789.5  340.97    4860  337.95  4891.4  338.53  4962.7  337.09  4968.6  335.44
  4973.7  336.31 4979.27334.8726  5000.8  329.21    5006  329.21  5020.4  334.52
  5025.5  334.99    5034  336.76  5044.2   337.4  5072.7   336.9  5133.3  336.29
  5194.2  337.25  5360.5  336.02  5431.6  337.95  5548.9  337.26  5685.1   339.2
  5779.1  339.07  5794.3  339.98  5858.5  340.42  5982.2  343.41  6115.4  344.78
#Mann= 5 ,-1 , 0
  4573.7     .11       0 4979.27     .06       0  5025.5     .11       0
  5072.7     .15       0  5133.3     .11       0
Bank Sta=4979.27,5025.5
XS Rating Curve= 0 ,0
Exp/Cntr=0.3,0.1

Type RM Length L Ch R = 1 ,7888    ,495,495,495
BEGIN DESCRIPTION:
CCLC 106 12.0
END DESCRIPTION:
XS GIS Cut Line= 3
       3686109.1     10205650.72      3686001.46     10204994.45
      3685592.34     10203947.37
#Sta/Elev= 30
  4326.8   346.1  4478.4  345.42  4491.3  344.41  4569.6  344.37  4630.4  343.69
  4640.6  342.85  4670.1  343.37    4823  340.51  4898.3  338.03  4954.7  337.48
    4975  334.78  4981.7  332.31  4986.7  332.29  4988.4   329.1  4996.3   329.6
  5013.5  334.59  5018.9  336.03  5027.7  336.21  5059.9  336.48  5092.1   335.3
  5137.7  336.99  5181.9  337.71  5230.8  335.66  5306.8  336.75  5392.7  335.11
  5483.3  336.72  5639.6  336.85  5868.9  339.59  6110.6  344.41    6116   345.2
#Mann= 5 ,-1 , 0
  4326.8     .11       0  4898.3     .15       0    4975     .09       0
  5013.5     .15       0  5137.7     .11       0
Bank Sta=4975,5013.5
XS Rating Curve= 0 ,0
Exp/Cntr=0.3,0.1

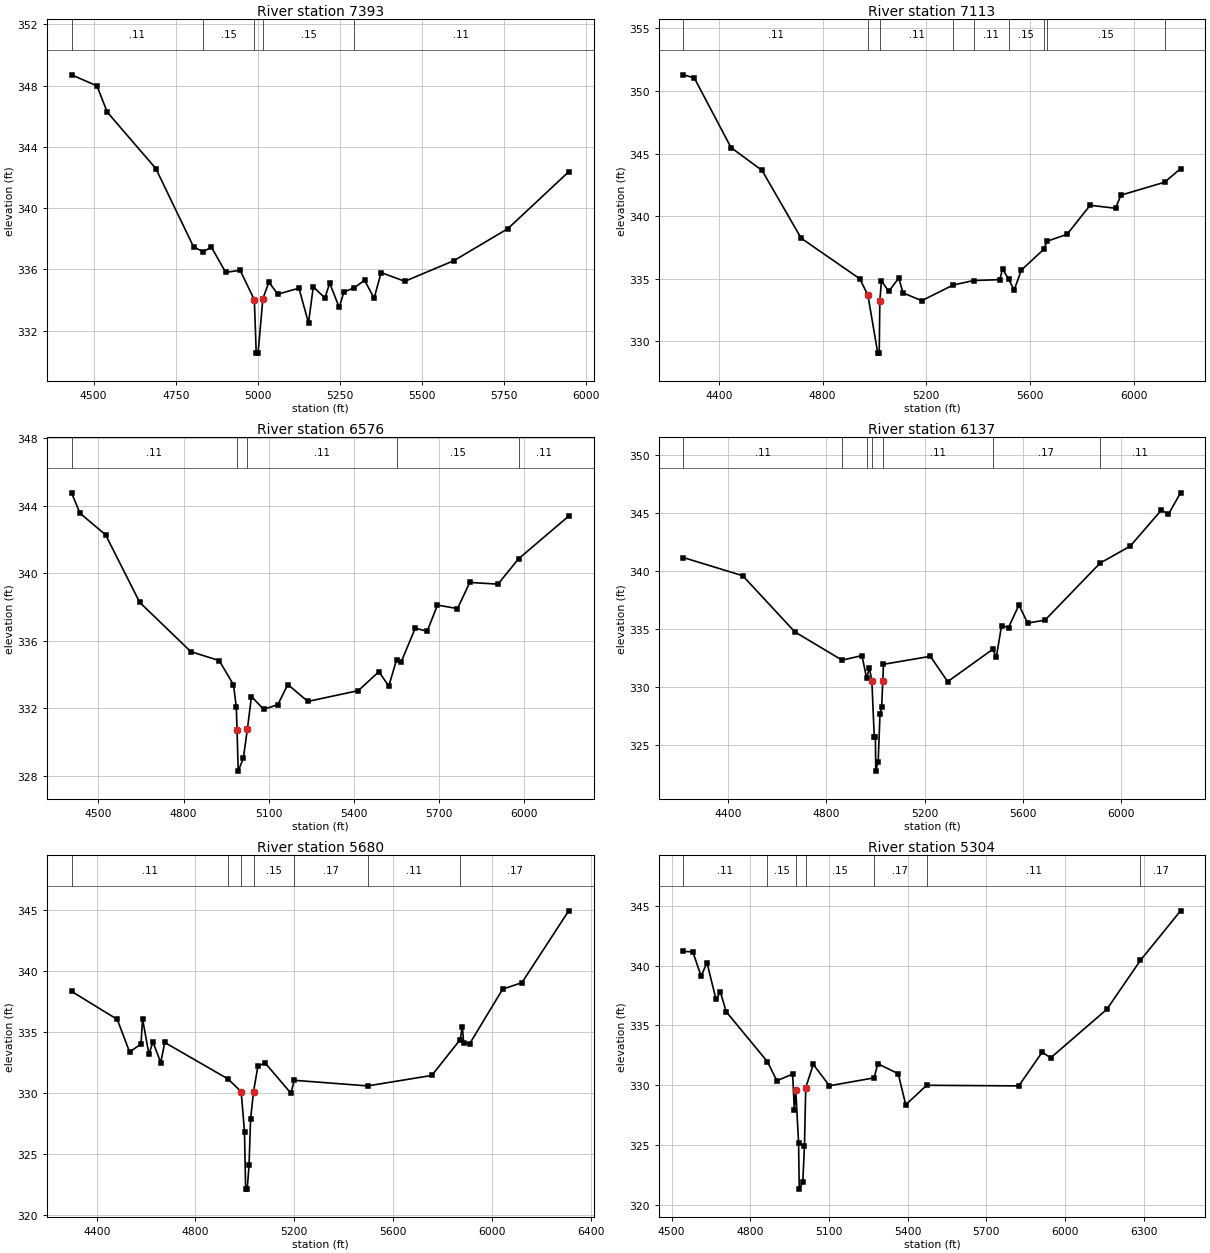
Type RM Length L Ch R = 1 ,7393    ,280,280,280
BEGIN DESCRIPTION:
CCLC 106 11.0
END DESCRIPTION:
XS GIS Cut Line= 3
      3686598.71      10205206.3      3686331.32     10204716.68
      3685752.16     10203957.18
#Sta/Elev= 30
  4432.9  348.71  4510.3  347.99  4541.4  346.28  4689.5  342.59  4804.5  337.47
  4833.1  337.17  4858.6  337.45  4902.2  335.81  4945.9  335.95  4989.2  334.03
    4995  330.54  5000.6  330.54  5015.2334.1009  5033.5  335.17  5060.7  334.39
    5125  334.78  5154.1  332.51  5168.6  334.87    5204  334.14  5218.5  335.11
  5247.6  333.52  5261.9  334.54    5293   334.8  5324.8   335.3  5353.7  334.12
  5375.1   335.8  5447.1  335.23  5596.8  336.58    5761  338.67  5945.9  342.38
#Mann= 5 ,-1 , 0
  4432.9     .11       0  4833.1     .15       0  4989.2     .09       0
  5015.2     .15       0    5293     .11       0
Bank Sta=4989.2,5015.2
XS Rating Curve= 0 ,0
Exp/Cntr=0.3,0.1

Type RM Length L Ch R = 1 ,7113    ,537,537,537
BEGIN DESCRIPTION:
CCLC 106 10.0
END DESCRIPTION:
XS GIS Cut Line= 3
      3686717.86     10205211.09      3686498.23     10204506.84
      3686178.54     10203369.42
#Sta/Elev= 30
  4262.3  351.29  4304.2  351.05  4446.3  345.48  4566.1  343.65  4716.9  338.24
  4943.2     335  4974.6  333.69  5012.7  329.06  5018.3  329.06  5020.7  333.23
  5026.8  334.84  5054.8  333.99    5094  335.06  5109.9  333.87  5182.6  333.25
  5303.8   334.5  5383.2  334.86  5483.8  334.93  5494.2  335.79    5518  334.96
  5539.1   334.1  5566.9  335.69  5653.7  337.36  5666.3     338  5743.5  338.55
  5832.4  340.87  5930.5  340.63  5951.3  341.68  6119.7  342.71  6181.5  343.79
#Mann= 9 ,-1 , 0
  4262.3     .11       0  4974.6     .06       0  5020.7     .11       0
  5303.8     .15       0  5383.2     .11       0    5518     .15       0
  5653.7     .17       0  5666.3     .15       0  6119.7     .11       0
Bank Sta=4974.6,5020.7
XS Rating Curve= 0 ,0
Exp/Cntr=0.3,0.1

Type RM Length L Ch R = 1 ,6576    ,439,439,439
BEGIN DESCRIPTION:
CCLC 106 9.0
END DESCRIPTION:
XS GIS Cut Line= 3
      3686917.85     10204861.06      3686936.43     10204265.15
      3686217.83     10203361.04
#Sta/Elev= 30
  4405.5  344.77  4435.5  343.56  4525.5  342.28  4645.6  338.28  4825.7  335.36
  4925.7  334.83  4975.8   333.4  4985.8   332.1 4988.38330.7404  4992.6  328.28
  5010.4  329.03  5024.8  330.75  5039.2   332.7  5082.5  331.94  5132.1  332.22
  5167.4  333.41  5237.8  332.41  5415.7  333.05  5487.8  334.17    5523  333.32
  5550.2  334.87  5566.3  334.74  5615.9  336.74  5658.4  336.58  5694.4  338.12
  5764.9  337.91  5808.2  339.46  5907.5  339.36  5979.9  340.86  6156.6  343.39
#Mann= 5 ,-1 , 0
  4405.5     .11       0 4988.38     .06       0  5024.8     .11       0
  5550.2     .15       0  5979.9     .11       0
Bank Sta=4988.38,5024.8
XS Rating Curve= 0 ,0
Exp/Cntr=0.3,0.1

Type RM Length L Ch R = 1 ,6137    ,457,457,457
BEGIN DESCRIPTION:
CCLC 106 8.0
END DESCRIPTION:
XS GIS Cut Line= 3
      3687140.35     10204800.01      3687258.23     10204026.84
      3686417.87     10203111.09
#Sta/Elev= 30
  4217.9  341.17  4459.6   339.6    4672  334.74  4864.2   332.3  4945.1  332.69
  4964.5  330.73  4975.5  331.64  4985.6  330.49  4995.3  325.69    5000  325.69
  5001.4   322.7  5011.3  323.53  5018.7  327.61  5025.5  328.22  5030.1330.5325
  5032.9  331.94    5224  332.63  5294.3  330.44  5477.5  333.23  5492.8  332.59
  5513.8  335.28  5542.2  335.12  5584.7  337.07  5619.9   335.5  5690.8  335.76
  5915.1  340.69  6037.9  342.16  6164.9  345.28  6193.3  344.91  6242.9  346.77
#Mann= 7 ,-1 , 0
  4217.9     .11       0  4864.2     .15       0  4964.5     .11       0
  4985.6     .06       0  5030.1     .11       0  5477.5     .17       0
  5915.1     .11       0
Bank Sta=4985.6,5030.1
XS Rating Curve= 0 ,0
Exp/Cntr=0.3,0.1

Type RM Length L Ch R = 1 ,5680    ,376,376,376
BEGIN DESCRIPTION:
CCLC 106 7.0
END DESCRIPTION:
XS GIS Cut Line= 3
      3687466.75     10204754.85      3687682.02      10204088.2
      3687207.01     10202864.29
#Sta/Elev= 30
    4298  338.37  4483.2  336.07  4533.2   333.4  4579.3  334.05  4585.7  336.11
  4611.4  333.22  4627.7  334.22  4659.3  332.53  4675.4  334.18  4931.6  331.19
    4985  330.15  4998.5  326.87    5003  322.16  5009.4  322.16  5016.9  324.12
  5023.1   327.9 5035.14330.1541    5053  332.27  5082.9  332.48  5186.4  330.02
  5199.8  331.08  5497.3  330.62  5757.1  331.48  5871.8  334.41  5880.6  335.48
  5885.9  334.13  5910.5  334.08  6043.9  338.55  6121.8  339.08  6311.4  344.97
#Mann= 7 ,-1 , 0
    4298     .11       0  4931.6     .15       0    4985     .09       0
 5035.14     .15       0  5199.8     .17       0  5497.3     .11       0
  5871.8     .17       0
Bank Sta=4985,5035.14
XS Rating Curve= 0 ,0
Exp/Cntr=0.3,0.1

Type RM Length L Ch R = 1 ,5304    ,1140,1140,1140
BEGIN DESCRIPTION:
CCLC 106 6.0
END DESCRIPTION:
XS GIS Cut Line= 3
      3688217.83     10204511.03      3688008.23     10204106.84
      3687366.06      10202817.4
#Sta/Elev= 30
  4544.7  341.18  4580.7  341.15  4612.2  339.12  4634.8  340.24  4669.2  337.16
  4685.7   337.8  4707.8  336.14    4865  331.96  4901.3  330.36  4961.4  330.92
  4967.7  327.92  4973.3  329.58    4984  325.15  4986.5  321.29    5000  321.86
  5006.4  324.92 5011.25329.7784    5040  331.73  5101.6  329.94  5271.8   330.6
  5286.3  331.78  5363.9  330.95  5392.6  328.35  5472.4  329.98  5823.6  329.93
  5913.1  332.76  5944.9  332.27  6159.4  336.34  6287.3  340.43  6440.5  344.58
#Mann= 7 ,-1 , 0
  4544.7     .11       0    4865     .15       0  4973.3     .09       0
 5011.25     .15       0  5271.8     .17       0  5472.4     .11       0
  6287.3     .17       0
Bank Sta=4973.3,5011.25
XS Rating Curve= 0 ,0
Exp/Cntr=0.3,0.1

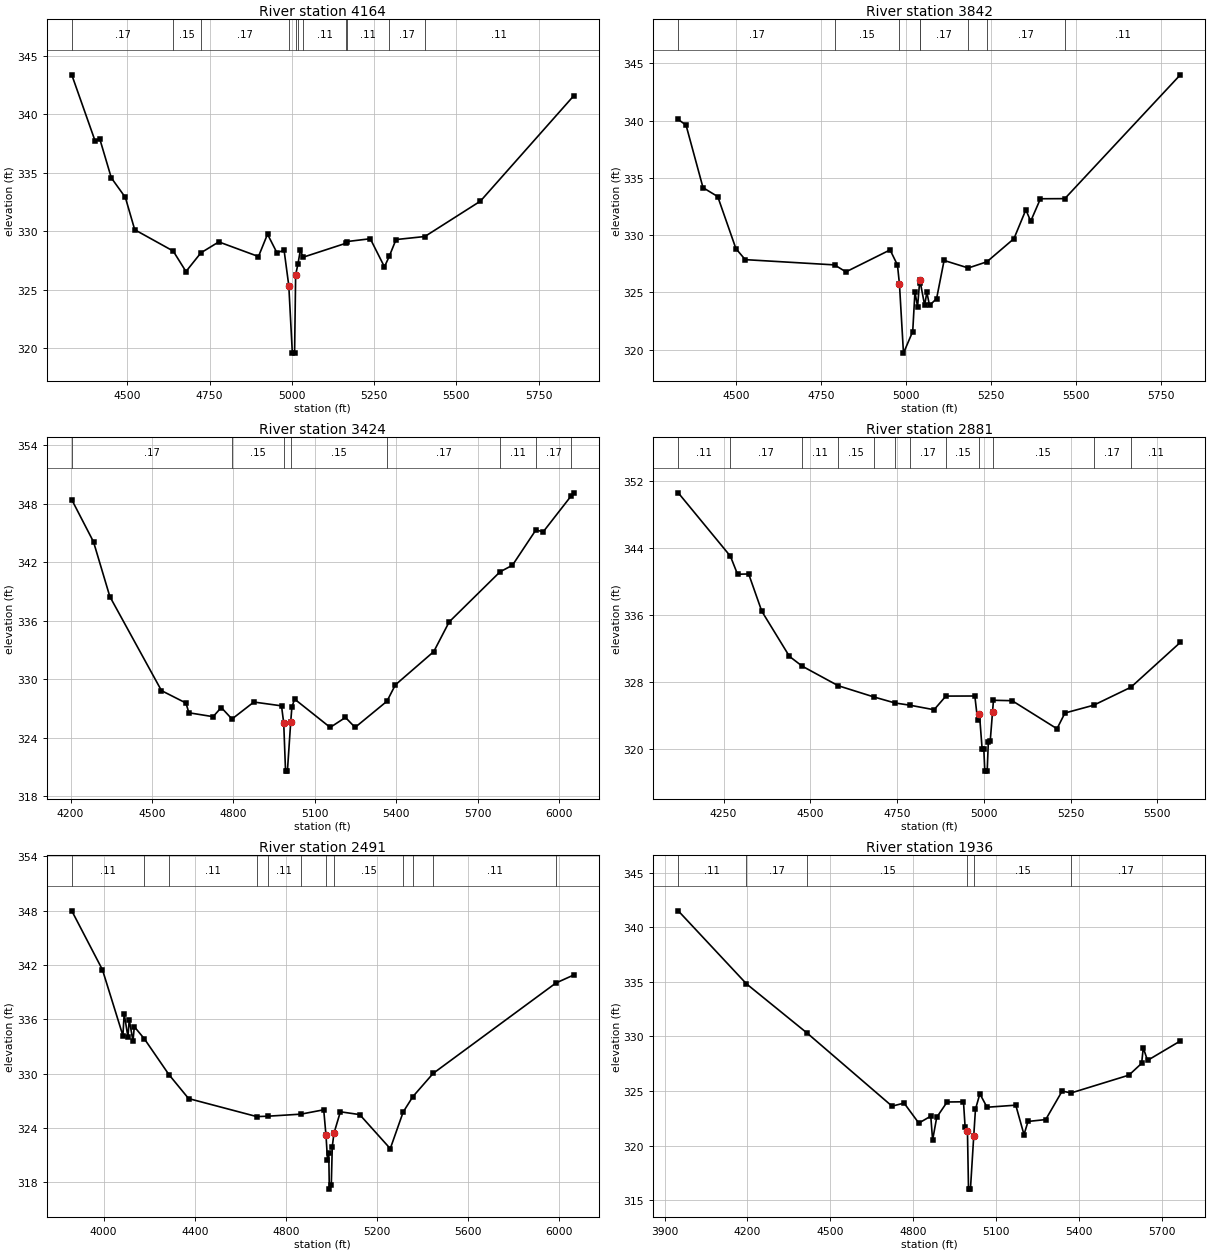
Type RM Length L Ch R = 1 ,4164    ,322,322,322
BEGIN DESCRIPTION:
CCLC 106 5.0
END DESCRIPTION:
XS GIS Cut Line= 3
      3688617.88      10203961.1      3688102.16     10203515.29
      3687567.84     10202861.05
#Sta/Elev= 30
  4330.8  343.37  4401.6  337.73  4415.8  337.91    4451  334.57  4493.7   332.9
  4522.2  330.14  4639.1  328.32    4678  326.57  4723.5  328.17  4777.8   329.1
  4898.4  327.85  4925.9  329.76  4954.4  328.18  4976.3  328.38  4990.6  325.36
  5001.4   319.6  5008.2   319.6  5011.4  326.28  5018.7  327.25  5025.8  328.41
  5033.9  327.79  5164.9  328.99  5167.7  329.13  5238.3  329.37  5281.4  326.97
  5295.9  327.86  5316.6   329.3  5404.2  329.56  5573.1  332.58  5857.2  341.59
#Mann= 11 ,-1 , 0
  4330.8     .17       0  4639.1     .15       0  4723.5     .17       0
  4990.6     .09       0  5011.4     .17       0  5018.7     .15       0
  5033.9     .11       0  5164.9     .17       0  5167.7     .11       0
  5295.9     .17       0  5404.2     .11       0
Bank Sta=4990.6,5011.4
XS Rating Curve= 0 ,0
Exp/Cntr=0.3,0.1

Type RM Length L Ch R = 1 ,3842    ,418,418,418
BEGIN DESCRIPTION:
CCLC 106 4.4
END DESCRIPTION:
XS GIS Cut Line= 3
      3688617.85     10203911.07      3688288.23     10203326.84
      3687767.86     10202711.08
#Sta/Elev= 30
  4329.2  340.11  4352.2  339.61  4402.1  334.15  4445.4  333.37  4498.9  328.82
  4526.3  327.86  4789.1   327.4  4822.5  326.79  4952.4  328.71  4974.1  327.39
 4979.91325.7438  4991.8  319.69    5019  321.58  5025.5  325.02  5033.3  323.76
  5039.8  326.09  5041.5  325.84  5054.1  323.87  5060.6  325.01  5068.4  323.86
  5089.2  324.45  5111.3  327.79  5182.5  327.13  5237.1  327.67  5316.7  329.69
  5351.8  332.21  5366.1  331.22  5394.7  333.18  5466.4  333.19  5806.2  344.01
#Mann= 8 ,-1 , 0
  4329.2     .17       0  4789.1     .15       0 4979.91     .09       0
  5039.8     .15       0  5041.5     .17       0  5182.5     .15       0
  5237.1     .17       0  5466.4     .11       0
Bank Sta=4979.91,5039.8
XS Rating Curve= 0 ,0
Exp/Cntr=0.3,0.1

Type RM Length L Ch R = 1 ,3424    ,543,543,543
BEGIN DESCRIPTION:
CCLC 106 4.3
END DESCRIPTION:
XS GIS Cut Line= 3
      3688667.85     10204011.08      3688616.05      10203126.4
      3687917.88      10202461.1
#Sta/Elev= 30
  4204.4  348.41  4284.5   344.1  4344.7  338.49    4535  328.85  4625.1  327.58
  4636.1  326.58  4725.3  326.18  4755.4  327.12  4794.9  325.94  4875.6  327.68
  4977.5  327.29  4985.7   325.5  4992.3   320.6  4999.2   320.6  5011.3 325.587
  5015.8  327.18  5025.8  327.98  5156.9  325.08  5213.2   326.1  5248.7  325.08
    5366  327.76  5397.2  329.44  5538.7  332.85  5595.4  335.89  5782.8  341.02
  5828.7   341.7  5915.2  345.32    5942  345.12  6045.6  348.82    6055  349.12
#Mann= 8 ,-1 , 0
  4204.4     .17       0  4794.9     .15       0  4985.7     .09       0
  5011.3     .15       0    5366     .17       0  5782.8     .11       0
  5915.2     .17       0  6045.6     .11       0
Bank Sta=4985.7,5011.3
XS Rating Curve= 0 ,0
Exp/Cntr=0.3,0.1

Type RM Length L Ch R = 1 ,2881    ,390,390,390
BEGIN DESCRIPTION:
CCLC 106 4.2
END DESCRIPTION:
XS GIS Cut Line= 3
      3688767.86     10204061.04      3689078.23     10203236.84
      3688867.85     10202711.07
#Sta/Elev= 30
  4119.3  350.57  4269.7     343  4290.2  340.85  4322.3  340.88  4360.1  336.43
  4439.8  331.04  4476.7  329.87  4580.2  327.54  4683.7  326.19  4743.8  325.48
  4787.2  325.21  4856.6  324.67  4890.7   326.3  4974.1  326.31  4982.1  323.45
  4987.4  324.16  4995.1     320    5000     320  5002.8  317.34  5009.7  317.34
    5013  320.81  5018.4   320.9  5025.1324.3927  5027.8   325.8  5081.6  325.75
  5210.9   322.4  5233.8  324.28  5316.5  325.21    5424  327.36  5566.3  332.71
#Mann= 12 ,-1 , 0
  4119.3     .11       0  4269.7     .17       0  4476.7     .11       0
  4580.2     .15       0  4683.7     .17       0  4743.8     .11       0
  4787.2     .17       0  4890.7     .15       0  4987.4     .09       0
  5025.1     .15       0  5316.5     .17       0    5424     .11       0
Bank Sta=4987.4,5025.1
XS Rating Curve= 0 ,0
Exp/Cntr=0.3,0.1

Type RM Length L Ch R = 1 ,2491    ,555,555,555
BEGIN DESCRIPTION:
CCLC 106 4.1
END DESCRIPTION:
XS GIS Cut Line= 3
      3688817.87     10204111.04      3689338.23     10203096.84
      3688567.85     10202361.07
#Sta/Elev= 30
  3860.1  347.97  3994.9  341.46  4084.7  334.19  4090.3  336.63  4106.8  334.02
  4112.5  335.95    4129  333.58  4134.7  335.18  4178.8  333.84    4287  329.88
  4373.2  327.24  4672.7  325.25  4720.2  325.29  4866.7  325.52  4966.7     326
  4976.7 323.175  4983.3  320.51  4988.9  321.24  4991.3  317.24    5000  317.74
  5004.3  321.93  5011.5  323.39  5039.8  325.78  5124.7  325.47    5259  321.71
  5315.8  325.76  5358.4  327.46  5447.4  330.02  5986.6     340  6065.3  340.89
#Mann= 12 ,-1 , 0
  3860.1     .11       0  4178.8     .17       0    4287     .11       0
  4672.7     .15       0  4720.2     .11       0  4866.7     .15       0
  4976.7     .09       0  5011.5     .15       0  5315.8     .17       0
  5358.4     .15       0  5447.4     .11       0  5986.6     .17       0
Bank Sta=4976.7,5011.5
XS Rating Curve= 0 ,0
Exp/Cntr=0.3,0.1

Type RM Length L Ch R = 1 ,1936    ,535,535,535
BEGIN DESCRIPTION:
CCLC 106 4.0
END DESCRIPTION:
XS GIS Cut Line= 4
      3689175.05     10204154.21      3689723.68     10203178.48
      3689838.27     10202886.82      3689508.95     10202685.76
#Sta/Elev= 30
  3949.5   341.5  4196.7  334.81  4417.4  330.28  4723.9  323.61  4767.6  323.89
  4820.8  322.06  4864.2  322.69  4870.9   320.5  4885.8  322.59  4923.4  323.99
  4982.7  324.01  4988.5  321.73  4997.1   321.3  5000.9  316.01  5007.9  316.01
    5020  320.92  5026.1  323.32    5042  324.74    5068  323.51  5172.1   323.7
  5201.9     321  5216.5  322.21  5280.5  322.38  5340.1  324.99  5372.6  324.82
  5581.9  326.45    5628  327.53  5633.9  328.95  5649.4   327.8  5768.1  329.58
#Mann= 6 ,-1 , 0
  3949.5     .11       0  4196.7     .17       0  4417.4     .15       0
  4997.1     .09       0    5020     .15       0  5372.6     .17       0
Bank Sta=4997.1,5020
XS Rating Curve= 0 ,0
Exp/Cntr=0.3,0.1

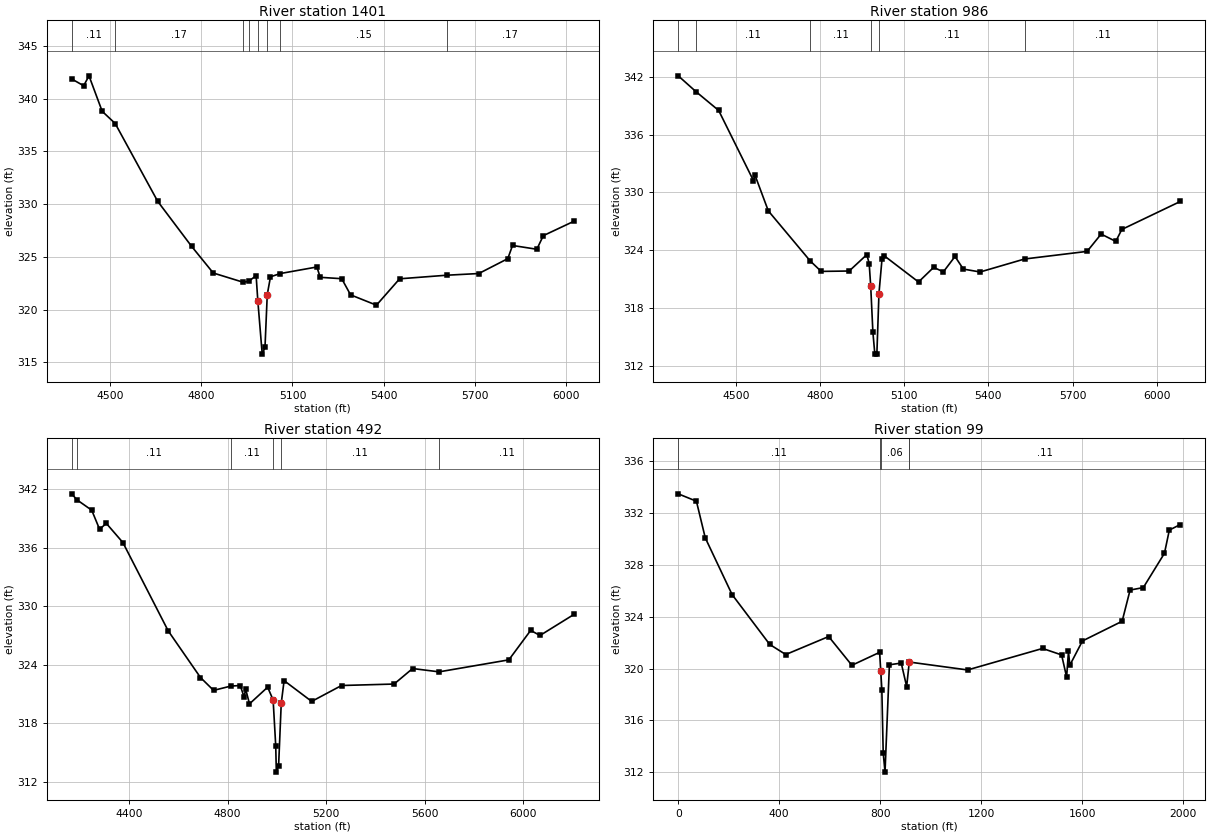
Type RM Length L Ch R = 1 ,1401    ,415,415,415
BEGIN DESCRIPTION:
CCLC 106 3.0
END DESCRIPTION:
XS GIS Cut Line= 4
      3689793.12     10204039.63      3689886.88     10203480.57
      3690091.74      10203001.4      3689609.13     10202713.22
#Sta/Elev= 30
  4374.7  341.86  4413.8  341.22  4431.3  342.16  4474.6   338.8  4517.4  337.64
  4657.2  330.26  4768.7  325.99  4839.7  323.47  4938.5  322.59  4957.4   322.7
  4980.6  323.23  4986.1  320.85  5000.6  315.78  5009.7  316.41  5017.2  321.43
  5027.8  323.11  5060.2  323.42  5180.3  324.04  5191.2  323.06  5261.9  322.93
    5291   321.4    5376  320.42  5452.2  322.92  5607.2  323.26  5712.4  323.42
  5807.7  324.83  5823.3  326.08  5903.1  325.72  5924.5  327.01  6024.8  328.37
#Mann= 8 ,-1 , 0
  4374.7     .11       0  4517.4     .17       0  4938.5     .15       0
  4957.4     .17       0  4986.1     .09       0  5017.2     .17       0
  5060.2     .15       0  5607.2     .17       0
Bank Sta=4986.1,5017.2
XS Rating Curve= 0 ,0
Exp/Cntr=0.3,0.1

Type RM Length L Ch R = 1 ,986     ,494,494,494
BEGIN DESCRIPTION:
CCLC 106 2.0
END DESCRIPTION:
XS GIS Cut Line= 3
      3689867.84      10204011.1      3690268.82     10203056.95
      3689612.68     10202682.01
#Sta/Elev= 30
  4293.8  342.12  4356.9  340.48    4438  338.52  4562.2  331.22  4567.6  331.79
  4615.1  328.08    4765  322.86  4803.7  321.79  4903.5  321.83  4966.4  323.53
  4974.8  322.61  4980.2   320.3  4988.1  315.45    4995  313.19  5002.2  313.19
  5009.7  319.49  5020.6  323.09  5027.7  323.43  5150.8  320.69  5204.8  322.21
  5239.4  321.74  5280.9  323.34  5310.7  322.03  5370.5  321.73  5529.2  323.08
  5752.1  323.87  5802.1  325.67  5854.3  324.91  5875.9  326.15  6084.5  329.06
#Mann= 6 ,-1 , 0
  4293.8     .11       0  4356.9     .11       0    4765     .11       0
  4980.2     .06       0  5009.7     .11       0  5529.2     .11       0
Bank Sta=4980.2,5009.7
XS Rating Curve= 0 ,0
Exp/Cntr=0.3,0.1

Type RM Length L Ch R = 1 ,492     ,393,393,393
BEGIN DESCRIPTION:
CCLC 106 1.0
END DESCRIPTION:
XS GIS Cut Line= 4
      3690185.49     10204081.26      3690574.38     10203397.23
      3690411.18     10203077.79        3689623.     10202661.13
#Sta/Elev= 30
  4167.8  341.51    4188  340.91  4248.8  339.83  4280.6  337.88    4308  338.48
  4375.1  336.52  4559.1  327.46    4690  322.68  4743.2  321.36  4812.9   321.8
  4851.4  321.86  4867.3  320.66    4873  321.51  4888.9  319.98  4962.6  321.69
  4984.8  320.37  4995.3  315.69  4997.8  312.98    5007  313.64  5017.7  320.04
  5029.3  322.36  5141.2  320.23  5262.4  321.86  5475.5  322.01  5550.7   323.6
  5658.1  323.26  5941.2  324.49  6029.7  327.51  6067.6  326.99  6204.9  329.14
#Mann= 6 ,-1 , 0
  4167.8     .11       0    4188     .11       0  4812.9     .11       0
  4984.8     .06       0  5017.7     .11       0  5658.1     .11       0
Bank Sta=4984.8,5017.7
XS Rating Curve= 0 ,0
Exp/Cntr=0.3,0.1

Type RM Length L Ch R = 1 ,99      ,0,0,0
BEGIN DESCRIPTION:
CCLC 106 1.0
END DESCRIPTION:
XS GIS Cut Line= 4
      3690412.88     10203967.31      3690918.09     10203389.19
      3690787.88     10203050.65      3690530.94      10202231.2
#Sta/Elev= 30
       0  333.49      72  332.92   107.1  330.09   213.4  325.71   362.5  321.86
     426  321.08     596  322.47     688  320.25   797.9  321.25   802.4   319.8
   806.7  318.38   812.1   313.5   819.3     312   836.7  320.29   883.6  320.42
     905  318.61  915.46   320.5  1146.5  319.89  1443.6  321.55    1519  321.05
  1538.8  319.34  1546.2  321.32  1551.4  320.25  1601.6  322.13  1758.8  323.65
  1790.3  326.06  1842.7  326.25  1926.5   328.9  1945.8  330.69  1989.3  331.12
#Mann= 5 ,-1 , 0
       0     .11       0   797.9     .08       0   802.4     .06       0
  915.46     .08       0   915.7     .11       0
Bank Sta=802.4,915.46
XS Rating Curve= 0 ,0
Exp/Cntr=0.3,0.1

Chan Stop Cuts=-1
Use User Specified Reach Order=0
Composite Channel Slope=5