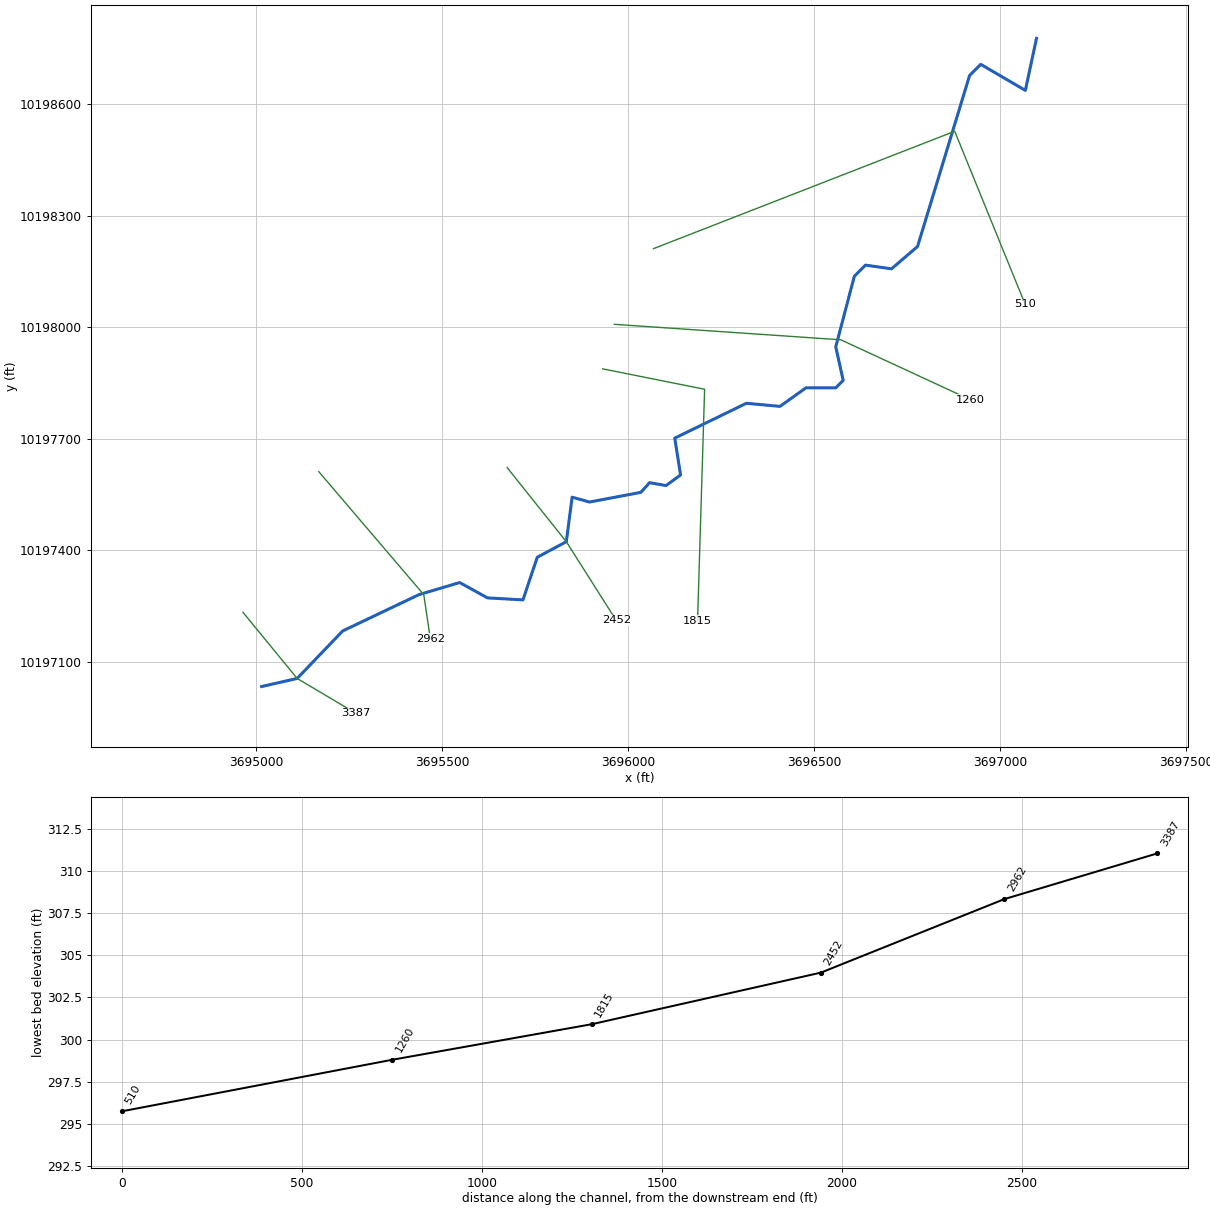
--- CCLC 107.prj (project) ---

Proj Title=CCLC 107 Base Level Engineering
Current Plan=p01
Default Exp/Contr=0.3,0.1
English Units
Geom File=g01
Flow File=f01
Flow File=f02
Plan File=p01
Y Axis Title=Elevation
X Axis Title(PF)=Main Channel Distance
X Axis Title(XS)=Station
BEGIN DESCRIPTION:
CCLC 107
END DESCRIPTION:
DSS Export Rating Curves= 0
DSS Export Rating Curve Sorted= 0
DSS Export Volume Flow Curves= 0
DXF OffsetX= 0
DXF OffsetY= 0
DXF ScaleX= 1
DXF ScaleY= 10

--- CCLC 107.p01 (plan) ---

Plan Title=Multiple Run
Short Identifier=Multiple
Geom File=g01
Flow File=f01
Subcritical Flow
K Sum by GR= 0
Std Step Tol= 0.01
Critical Tol= 0.01
Num of Std Step Trials= 20
Max Error Tol= 0.3
Flow Tol Ratio= 0.001
Split Flow NTrial= 30
Split Flow Tol= 0.02
Split Flow Ratio= 0.02
Log Output Level= 0
Friction Slope Method= 1
Unsteady Friction Slope Method= 2
Unsteady Bridges Friction Slope Method= 1
Parabolic Critical Depth
Global Vel Dist=  1 , 1 , 1
Global Log Level= 0
CheckData=True
Encroach Param= -1, 0, 0, 0
BEGIN DESCRIPTION:
Multiple Run
END DESCRIPTION:

--- CCLC 107.f01 (steady flow) ---

Flow Title=Multiple
Program Version=4.10
Number of Profiles= 7
Profile Names=10-year,25-year,50-year,1pct_min,100-year,1pct_plu,500-year
River Rch & RM=CCLC 107,Reach-1         ,3387
     595     809    1096     488    1474    4451    2764
Boundary for River Rch & Prof#=CCLC 107,Reach-1         , 1
Up Type= 0
Dn Type= 3
Dn Slope=0.005
Boundary for River Rch & Prof#=CCLC 107,Reach-1         , 2
Up Type= 0
Dn Type= 3
Dn Slope=0.005
Boundary for River Rch & Prof#=CCLC 107,Reach-1         , 3
Up Type= 0
Dn Type= 3
Dn Slope=0.005
Boundary for River Rch & Prof#=CCLC 107,Reach-1         , 4
Up Type= 0
Dn Type= 3
Dn Slope=0.005
Boundary for River Rch & Prof#=CCLC 107,Reach-1         , 5
Up Type= 0
Dn Type= 3
Dn Slope=0.005
Boundary for River Rch & Prof#=CCLC 107,Reach-1         , 6
Up Type= 0
Dn Type= 3
Dn Slope=0.005
Boundary for River Rch & Prof#=CCLC 107,Reach-1         , 7
Up Type= 0
Dn Type= 3
Dn Slope=0.005
DSS Import GetInterval= 0
DSS Import GetPeak= 0
DSS Import FillOption= 0

--- CCLC 107.f02 (steady flow) ---

Flow Title=Orig_BLE_Flows
Program Version=4.10
Number of Profiles= 7
Profile Names=10-year,25-year,50-year,1pct_min,100-year,1pct_plu,500-year
River Rch & RM=CCLC 107,Reach-1         ,3387
     595     793     953     376    1134    3426    1607
Boundary for River Rch & Prof#=CCLC 107,Reach-1         , 1
Up Type= 0
Dn Type= 3
Dn Slope=0.005
Boundary for River Rch & Prof#=CCLC 107,Reach-1         , 2
Up Type= 0
Dn Type= 3
Dn Slope=0.005
Boundary for River Rch & Prof#=CCLC 107,Reach-1         , 3
Up Type= 0
Dn Type= 3
Dn Slope=0.005
Boundary for River Rch & Prof#=CCLC 107,Reach-1         , 4
Up Type= 0
Dn Type= 3
Dn Slope=0.005
Boundary for River Rch & Prof#=CCLC 107,Reach-1         , 5
Up Type= 0
Dn Type= 3
Dn Slope=0.005
Boundary for River Rch & Prof#=CCLC 107,Reach-1         , 6
Up Type= 0
Dn Type= 3
Dn Slope=0.005
Boundary for River Rch & Prof#=CCLC 107,Reach-1         , 7
Up Type= 0
Dn Type= 3
Dn Slope=0.005
DSS Import GetInterval= 0
DSS Import GetPeak= 0
DSS Import FillOption= 0

--- CCLC 107.g01 (geometry) ---

Geom Title=Existing Conditions
Program Version=4.10

River Reach=CCLC 107        ,Reach-1
Reach XY= 30
      3695014.02      10197033.3       3695109.5     10197055.01
      3695231.94     10197182.77      3695437.01     10197280.43
      3695546.61     10197312.98      3695621.48     10197271.75
      3695716.96     10197266.32      3695755.37     10197381.12
       3695833.5     10197422.79      3695849.12     10197542.58
        3695896.     10197529.56      3696034.02      10197555.6
      3696057.46     10197581.64      3696101.73     10197573.83
      3696140.79     10197602.48      3696125.17     10197701.44
      3696317.87     10197795.19      3696408.23     10197786.84
      3696478.23     10197836.84      3696558.23     10197836.84
      3696578.23     10197856.84      3696558.23     10197946.84
      3696608.23     10198136.84      3696638.23     10198166.84
      3696708.23     10198156.84      3696778.23     10198216.84
      3696918.23     10198676.84      3696948.23     10198706.84
      3697068.23     10198636.84      3697098.23     10198776.84

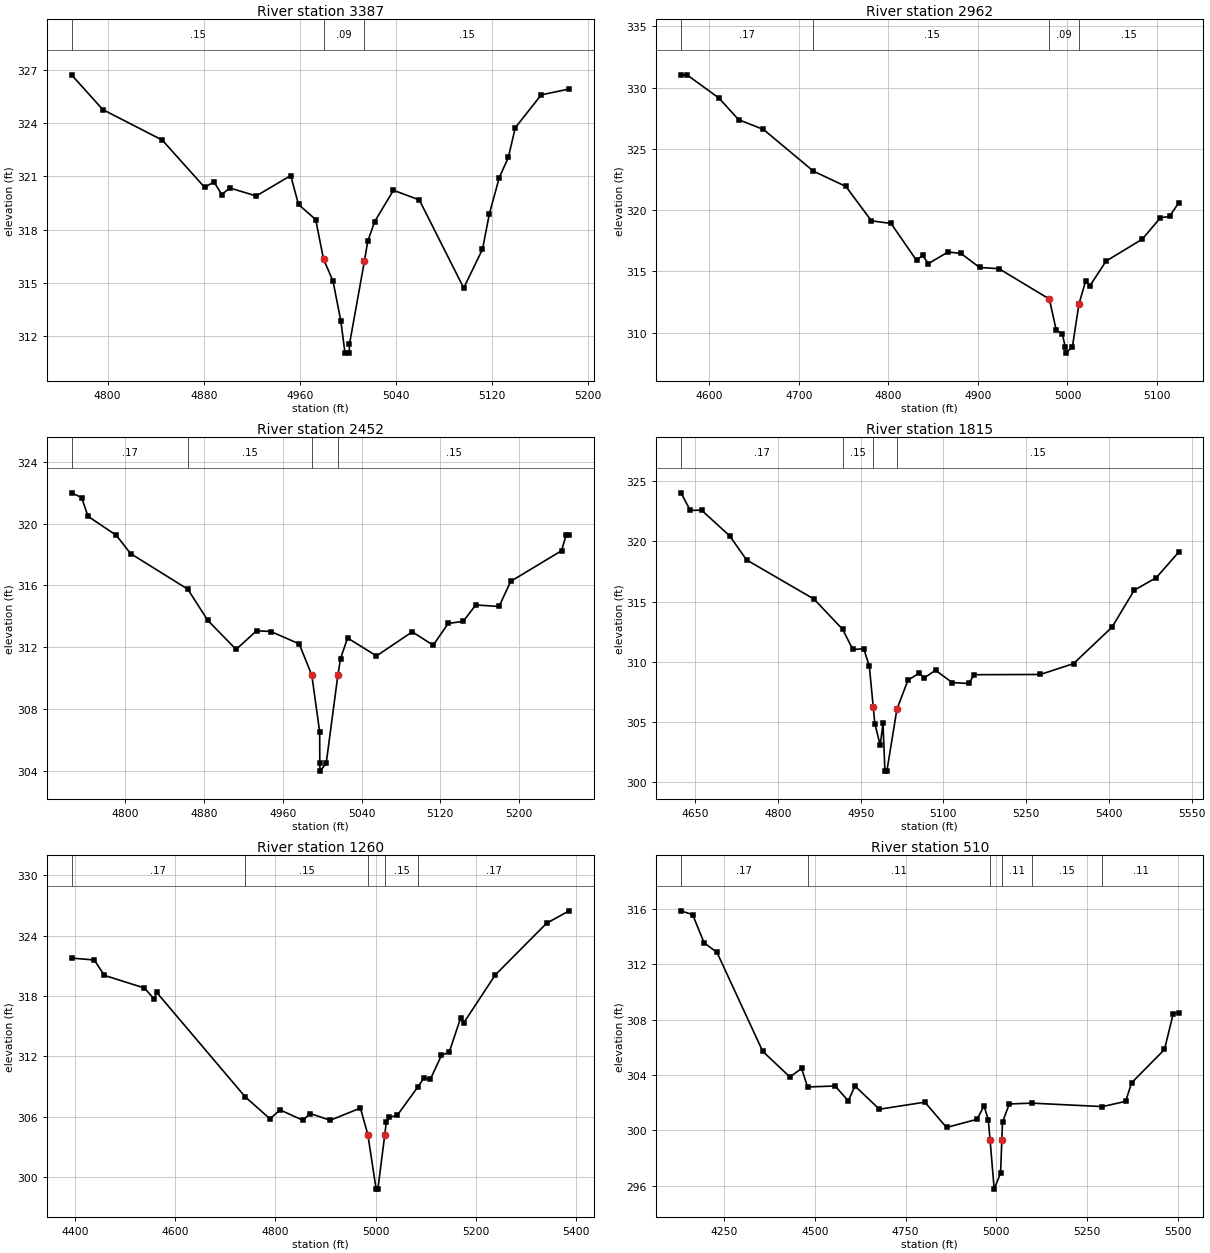
Type RM Length L Ch R = 1 ,3387    ,425,425,425
BEGIN DESCRIPTION:
CCLC 107 6.0
END DESCRIPTION:
XS GIS Cut Line= 3
      3694963.73     10197232.91       3695109.5     10197055.01
      3695267.84     10196961.08
#Sta/Elev= 30
    4770  326.73    4796  324.77  4845.5  323.05  4880.7  320.39  4888.6  320.69
    4895  319.98  4901.7  320.35  4923.7   319.9  4952.4  321.05  4958.9  319.42
  4973.2  318.57  4979.7  316.34  4987.6   315.1  4994.1  312.86  4997.6  311.04
  5001.1  311.04  5001.3  311.54  5013.8 316.248  5016.5  317.34  5022.3  318.46
  5037.9  320.22  5059.4  319.68  5096.4  314.71    5112   316.9  5117.8  318.91
    5126  320.94  5133.5  322.07  5139.3  323.75  5160.9   325.6  5184.1  325.93
#Mann= 3 , 0 , 0
    4770     .15       0  4979.7     .09       0  5013.8     .15       0
Bank Sta=4979.7,5013.8
XS Rating Curve= 0 ,0
Exp/Cntr=0.3,0.1

Type RM Length L Ch R = 1 ,2962    ,510,510,510
BEGIN DESCRIPTION:
CCLC 107 5.0
END DESCRIPTION:
XS GIS Cut Line= 3
      3695167.83      10197611.1      3695450.01     10197280.39
      3695467.85     10197161.05
#Sta/Elev= 30
  4568.6  331.04  4575.8  331.01  4610.9  329.15  4632.9  327.38  4660.7  326.58
  4716.4  323.18  4752.7  321.93  4781.1  319.13  4803.1  318.91  4831.5   315.9
  4838.2   316.3  4844.8  315.64  4866.7  316.58    4881  316.47  4901.9  315.32
  4923.6  315.22  4979.8  312.74  4987.5  310.19  4994.1  309.92  4997.6  308.83
  4997.9  308.33  5005.5  308.83  5012.8  312.33  5020.2  314.19  5025.2  313.84
  5043.1  315.84  5083.5  317.63  5103.8  319.38  5113.9  319.48    5124  320.58
#Mann= 4 ,-1 , 0
  4568.6     .17       0  4716.4     .15       0  4979.8     .09       0
  5012.8     .15       0
Bank Sta=4979.8,5012.8
XS Rating Curve= 0 ,0
Exp/Cntr=0.3,0.1

Type RM Length L Ch R = 1 ,2452    ,637,637,637
BEGIN DESCRIPTION:
CCLC 107 4.0
END DESCRIPTION:
XS GIS Cut Line= 3
      3695674.61     10197621.86       3695833.5     10197422.79
      3695967.88     10197211.03
#Sta/Elev= 30
  4745.3  321.99  4755.6  321.68    4762  320.47  4790.8  319.24  4805.2  318.06
  4863.4  315.75  4883.7  313.73  4912.5  311.85  4933.3  313.06  4947.7  313.01
  4976.6  312.21  4989.4  310.18  4997.4   306.5  4997.5  304.47  4997.7  303.97
    5004  304.47  5015.9310.1982  5018.6  311.26  5025.7  312.59  5055.1  311.43
  5091.5  312.99  5112.7  312.12  5127.9  313.53  5143.2  313.67    5156  314.73
  5179.6  314.63  5191.5  316.26  5243.1  318.24  5247.8  319.25  5250.8  319.25
#Mann= 4 ,-1 , 0
  4745.3     .17       0  4863.4     .15       0  4989.4     .09       0
  5015.9     .15       0
Bank Sta=4989.4,5015.9
XS Rating Curve= 0 ,0
Exp/Cntr=0.3,0.1

Type RM Length L Ch R = 1 ,1815    ,555,555,555
BEGIN DESCRIPTION:
CCLC 107 3.0
END DESCRIPTION:
XS GIS Cut Line= 3
      3695931.36      10197887.8      3696205.48     10197832.87
      3696186.53     10197210.73
#Sta/Elev= 30
  4624.3  324.03  4641.1  322.57  4661.5  322.59  4712.5  320.46  4743.1  318.46
  4865.5   315.2  4917.4  312.69  4935.7  311.02  4955.7  311.07  4965.7  309.63
 4972.85306.2195  4975.7  304.86  4985.5  303.06  4990.5  304.89    4994  300.91
  4997.5  300.91  5015.7  306.04  5035.7  308.46  5055.7  309.04  5065.7  308.67
  5085.8  309.29  5115.8  308.27  5145.8  308.19  5155.8  308.92  5275.8  308.94
  5335.9  309.84  5405.9  312.88  5445.9  315.94  5485.9  316.98  5526.3  319.09
#Mann= 4 ,-1 , 0
  4624.3     .17       0  4917.4     .15       0 4972.85     .09       0
  5015.7     .15       0
Bank Sta=4972.85,5015.7
XS Rating Curve= 0 ,0
Exp/Cntr=0.3,0.1

Type RM Length L Ch R = 1 ,1260    ,750,750,750
BEGIN DESCRIPTION:
CCLC 107 2.0
END DESCRIPTION:
XS GIS Cut Line= 3
      3695962.54      10198007.6      3696571.95     10197965.93
      3696919.16     10197805.28
#Sta/Elev= 30
  4392.9  321.78  4438.3  321.59  4458.4  320.06  4538.5   318.8  4557.7  317.71
  4562.8  318.37  4739.4  307.99  4789.1  305.79  4809.2  306.68  4854.7  305.65
  4869.3  306.32  4909.4  305.65  4969.6  306.86 4984.41304.2269    5001   298.8
  5004.5   298.8  5018.3 304.225  5021.2  305.43    5027  305.93  5043.3  306.15
  5084.7  308.99  5095.8  309.82  5109.4  309.74  5131.4   312.1  5147.1  312.45
    5170  315.86  5175.6  315.31  5238.8   320.1  5341.5  325.25  5386.3  326.48
#Mann= 5 ,-1 , 0
  4392.9     .17       0  4739.4     .15       0 4984.41     .09       0
  5018.3     .15       0  5084.7     .17       0
Bank Sta=4984.41,5018.3
XS Rating Curve= 0 ,0
Exp/Cntr=0.3,0.1

Type RM Length L Ch R = 1 ,510     ,0,0,0
BEGIN DESCRIPTION:
CCLC 107 1.0
END DESCRIPTION:
XS GIS Cut Line= 3
      3696067.88     10198211.08      3696878.23     10198526.84
      3697067.85     10198061.06
#Sta/Elev= 30
  4130.3  315.88  4162.5   315.6  4194.2  313.56  4229.5  312.88  4355.7  305.72
  4430.8  303.86    4463  304.48  4479.5  303.14  4555.7  303.21  4591.8  302.13
  4610.1  303.21  4677.6  301.53  4803.1  302.04  4862.8  300.21    4947   300.8
  4966.2  301.77  4978.1  300.77  4982.9299.3211  4994.3  295.75  5011.9  296.91
  5015.4299.3017  5017.3   300.6    5036  301.91  5097.5  301.97    5293  301.72
  5357.1   302.1  5373.3  303.44  5464.1  305.85  5488.2  308.44  5502.9   308.5
#Mann= 6 ,-1 , 0
  4130.3     .17       0  4479.5     .11       0  4982.9     .06       0
  5015.4     .11       0  5097.5     .15       0    5293     .11       0
Bank Sta=4982.9,5015.4
XS Rating Curve= 0 ,0
Exp/Cntr=0.3,0.1

Chan Stop Cuts=-1
Use User Specified Reach Order=0
Composite Channel Slope=5