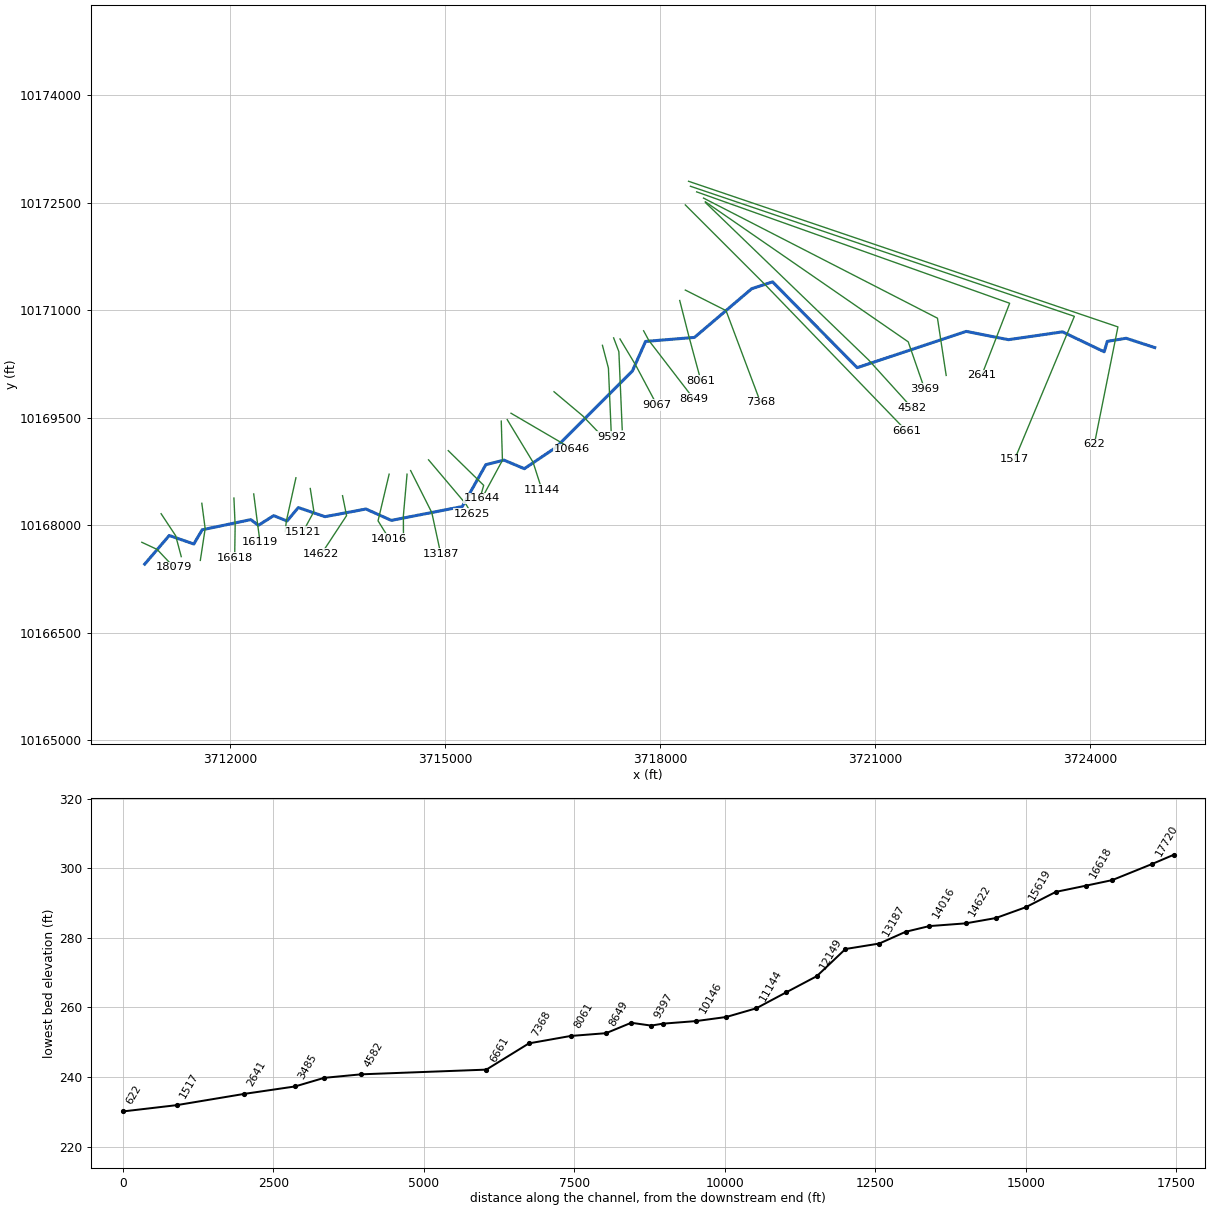
--- CCLC 110.prj (project) ---

Proj Title=CCLC 110 Base Level Engineering
Current Plan=p01
Default Exp/Contr=0.3,0.1
English Units
Geom File=g01
Flow File=f01
Flow File=f02
Plan File=p01
Y Axis Title=Elevation
X Axis Title(PF)=Main Channel Distance
X Axis Title(XS)=Station
BEGIN DESCRIPTION:
CCLC 110
END DESCRIPTION:
DSS Export Rating Curves= 0
DSS Export Rating Curve Sorted= 0
DSS Export Volume Flow Curves= 0
DXF OffsetX= 0
DXF OffsetY= 0
DXF ScaleX= 1
DXF ScaleY= 10

--- CCLC 110.p01 (plan) ---

Plan Title=Multiple Run
Short Identifier=Multiple
Geom File=g01
Flow File=f01
Subcritical Flow
K Sum by GR= 0
Std Step Tol= 0.01
Critical Tol= 0.01
Num of Std Step Trials= 20
Max Error Tol= 0.3
Flow Tol Ratio= 0.001
Split Flow NTrial= 30
Split Flow Tol= 0.02
Split Flow Ratio= 0.02
Log Output Level= 0
Friction Slope Method= 1
Unsteady Friction Slope Method= 2
Unsteady Bridges Friction Slope Method= 1
Parabolic Critical Depth
Global Vel Dist=  1 , 1 , 1
Global Log Level= 0
CheckData=True
Encroach Param= -1, 0, 0, 0
BEGIN DESCRIPTION:
Multiple Run
END DESCRIPTION:

--- CCLC 110.f01 (steady flow) ---

Flow Title=Multiple
Program Version=4.10
Number of Profiles= 7
Profile Names=10-year,25-year,50-year,1pct_min,100-year,1pct_plu,500-year
River Rch & RM=CCLC 110,Reach-1         ,18079
     677     922    1251     558    1685    5089    3160
River Rch & RM=CCLC 110,Reach-1         ,11644
     981    1357    1858     835    2522    7616    4814
River Rch & RM=CCLC 110,Reach-1         ,4582
    1300    1821    2515    1139    3440   10389    6665
River Rch & RM=CCLC 110,Reach-1         ,1517
    1394    1959    2713    1231    3718   11228    7233
Boundary for River Rch & Prof#=CCLC 110,Reach-1         , 1
Up Type= 0
Dn Type= 3
Dn Slope=0.005
Boundary for River Rch & Prof#=CCLC 110,Reach-1         , 2
Up Type= 0
Dn Type= 3
Dn Slope=0.005
Boundary for River Rch & Prof#=CCLC 110,Reach-1         , 3
Up Type= 0
Dn Type= 3
Dn Slope=0.005
Boundary for River Rch & Prof#=CCLC 110,Reach-1         , 4
Up Type= 0
Dn Type= 3
Dn Slope=0.005
Boundary for River Rch & Prof#=CCLC 110,Reach-1         , 5
Up Type= 0
Dn Type= 3
Dn Slope=0.005
Boundary for River Rch & Prof#=CCLC 110,Reach-1         , 6
Up Type= 0
Dn Type= 3
Dn Slope=0.005
Boundary for River Rch & Prof#=CCLC 110,Reach-1         , 7
Up Type= 0
Dn Type= 3
Dn Slope=0.005
DSS Import GetInterval= 0
DSS Import GetPeak= 0
DSS Import FillOption= 0

--- CCLC 110.f02 (steady flow) ---

Flow Title=Orig_BLE_Flows
Program Version=4.10
Number of Profiles= 7
Profile Names=10-year,25-year,50-year,1pct_min,100-year,1pct_plu,500-year
River Rch & RM=CCLC 110,Reach-1         ,18079
     677     904    1088     429    1296    3913    1837
River Rch & RM=CCLC 110,Reach-1         ,11644
     981    1330    1616     643    1940    5860    2799
River Rch & RM=CCLC 110,Reach-1         ,4582
    1300    1785    2187     876    2646    7991    3875
River Rch & RM=CCLC 110,Reach-1         ,1517
    1394    1921    2359     947    2860    8637    4205
Boundary for River Rch & Prof#=CCLC 110,Reach-1         , 1
Up Type= 0
Dn Type= 3
Dn Slope=0.005
Boundary for River Rch & Prof#=CCLC 110,Reach-1         , 2
Up Type= 0
Dn Type= 3
Dn Slope=0.005
Boundary for River Rch & Prof#=CCLC 110,Reach-1         , 3
Up Type= 0
Dn Type= 3
Dn Slope=0.005
Boundary for River Rch & Prof#=CCLC 110,Reach-1         , 4
Up Type= 0
Dn Type= 3
Dn Slope=0.005
Boundary for River Rch & Prof#=CCLC 110,Reach-1         , 5
Up Type= 0
Dn Type= 3
Dn Slope=0.005
Boundary for River Rch & Prof#=CCLC 110,Reach-1         , 6
Up Type= 0
Dn Type= 3
Dn Slope=0.005
Boundary for River Rch & Prof#=CCLC 110,Reach-1         , 7
Up Type= 0
Dn Type= 3
Dn Slope=0.005
DSS Import GetInterval= 0
DSS Import GetPeak= 0
DSS Import FillOption= 0

--- CCLC 110.g01 (geometry) ---

Geom Title=Existing Conditions
Program Version=4.10

River Reach=CCLC 110        ,Reach-1
Reach XY= 30
      3710808.17     10167456.62       3711150.6     10167855.73
      3711493.55     10167737.24      3711610.28     10167935.41
      3712288.31     10168077.09      3712393.17     10167997.35
      3712607.11     10168132.49      3712794.11     10168057.54
      3712950.62     10168245.28      3713323.27     10168118.18
      3713894.87     10168225.15      3714248.22     10168066.47
      3715238.19     10168259.26      3715566.79     10168843.71
      3715820.14     10168906.91      3716104.03     10168787.69
      3716547.39     10169086.02      3717610.98     10170149.72
      3717795.07     10170562.76      3718477.42     10170618.74
       3719275.4     10171297.76      3719566.92     10171393.35
      3720746.82     10170196.57      3722267.66      10170702.6
      3722857.21     10170587.06      3723611.14     10170696.42
      3724192.45     10170418.15      3724235.87     10170563.25
      3724498.53     10170606.78      3724898.23     10170476.84

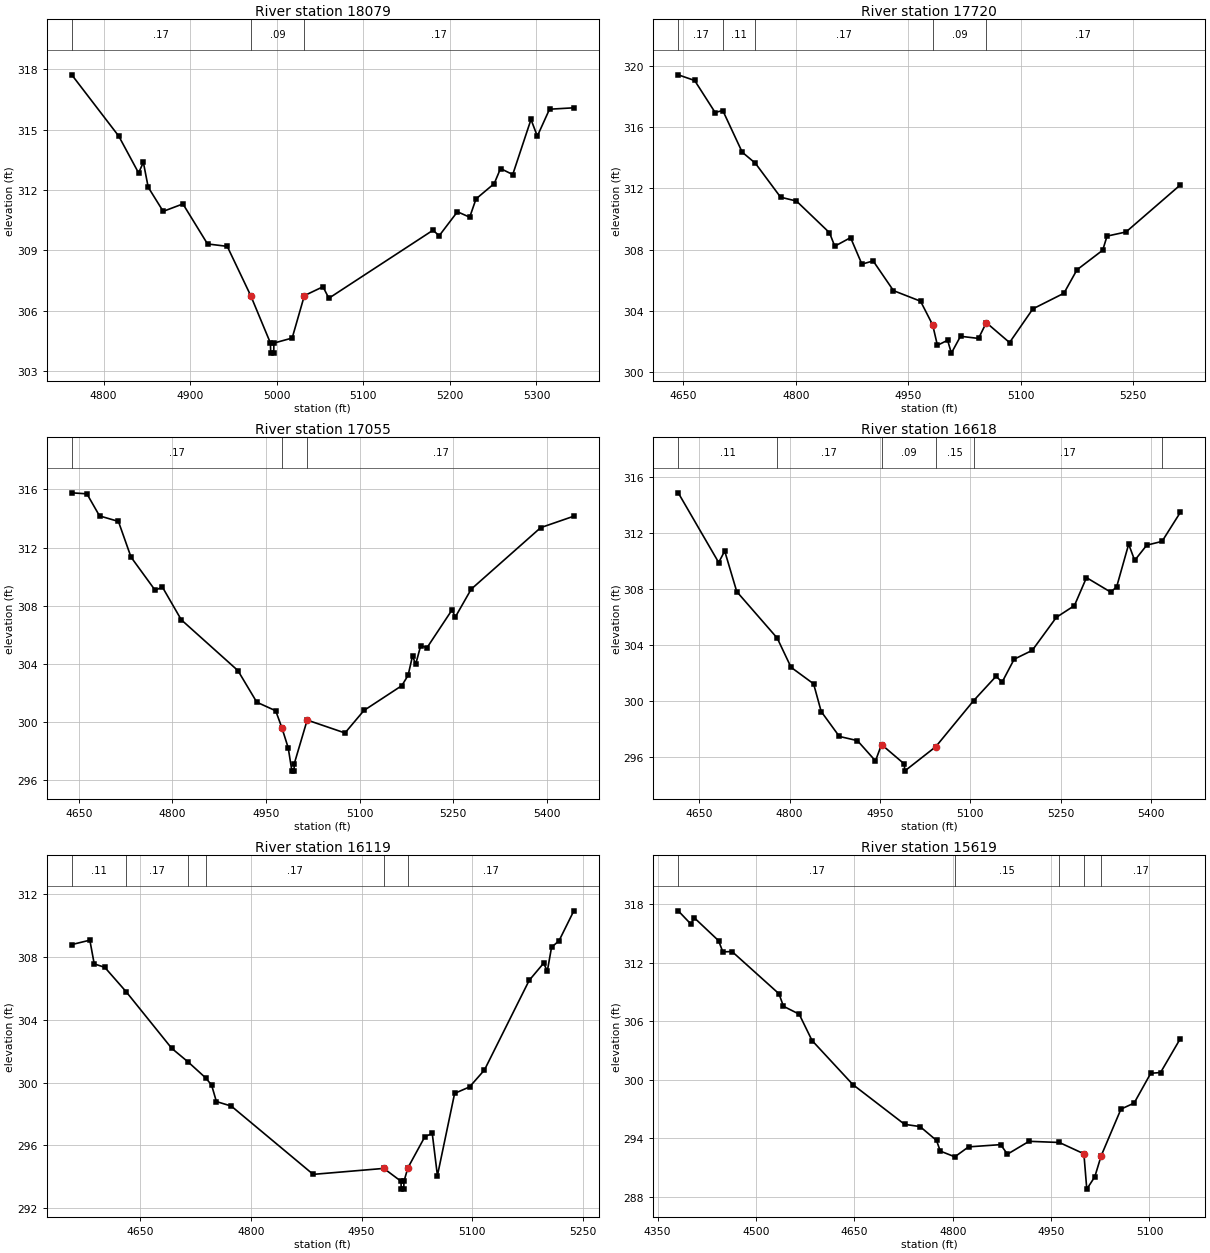
Type RM Length L Ch R = 1 ,18079   ,359,359,359
BEGIN DESCRIPTION:
CCLC 110 32.0
END DESCRIPTION:
XS GIS Cut Line= 3
      3710767.88     10167761.06      3710982.45     10167660.87
      3711217.82      10167411.1
#Sta/Elev= 30
  4763.2  317.73  4817.5  314.68  4840.4  312.85  4845.9  313.38  4851.5  312.14
  4868.8  310.94  4891.6  311.31    4920  309.32  4942.8   309.2    4970306.7407
  4992.7  304.39    4993  303.89  4996.5  303.89  4996.7  304.39  5017.8  304.64
  5031.9  306.75  5053.4  307.19  5060.2  306.62  5180.4     310  5187.7  309.73
  5208.7  310.92  5222.9  310.65  5230.2  311.56  5251.2  312.32  5258.5  313.07
  5272.6  312.77  5293.7  315.51    5301  314.68  5315.1  316.02  5343.2  316.09
#Mann= 3 , 0 , 0
  4763.2     .17       0    4970     .09       0  5031.9     .17       0
Bank Sta=4970,5031.9
XS Rating Curve= 0 ,0
Exp/Cntr=0.3,0.1

Type RM Length L Ch R = 1 ,17720   ,665,665,665
BEGIN DESCRIPTION:
CCLC 110 31.0
END DESCRIPTION:
XS GIS Cut Line= 3
      3711037.17     10168159.35       3711240.3     10167852.05
      3711317.85     10167561.08
#Sta/Elev= 30
  4643.2  319.41  4665.1  319.04  4692.4  316.95  4702.6  317.08  4728.5  314.36
    4746  313.64  4779.7  311.42  4800.8  311.17  4844.9   309.1  4851.9  308.22
    4873  308.78  4888.1  307.05  4903.1  307.26  4930.2  305.32  4966.3  304.63
 4982.47303.0834  4988.8  301.75  5002.4  302.08  5007.4  301.24  5019.6  302.34
  5043.6   302.2    5054  303.23    5085  301.93  5116.1  304.13  5157.5  305.15
  5174.9  306.68  5209.2  307.96    5215  308.88  5240.3  309.15  5312.7  312.22
#Mann= 5 ,-1 , 0
  4643.2     .17       0  4702.6     .11       0    4746     .17       0
 4982.47     .09       0    5054     .17       0
Bank Sta=4982.47,5054
XS Rating Curve= 0 ,0
Exp/Cntr=0.3,0.1

Type RM Length L Ch R = 1 ,17055   ,437,437,437
BEGIN DESCRIPTION:
CCLC 110 30.0
END DESCRIPTION:
XS GIS Cut Line= 3
      3711604.88      10168305.2      3711651.76     10167951.01
      3711584.06     10167508.34
#Sta/Elev= 30
  4638.5  315.77  4662.8   315.7    4683  314.18  4713.3   313.8  4733.5  311.34
  4772.1  309.06  4783.9  309.27  4814.1  307.02  4904.9  303.52  4935.2  301.34
  4965.5  300.75  4975.5  299.57  4985.6  298.19  4991.5  296.59    4995  296.59
  4995.2  297.09    5016  300.11  5076.6  299.22    5107  300.77  5167.7  302.48
  5177.8  303.19  5184.9  304.53    5190  303.96    5198  305.23  5208.2   305.1
  5248.4  307.71  5253.4   307.2    5279  309.13  5390.4  313.37  5443.6  314.16
#Mann= 3 , 0 , 0
  4638.5     .17       0  4975.5     .09       0    5016     .17       0
Bank Sta=4975.5,5016
XS Rating Curve= 0 ,0
Exp/Cntr=0.3,0.1

Type RM Length L Ch R = 1 ,16618   ,499,499,499
BEGIN DESCRIPTION:
CCLC 110 29.0
END DESCRIPTION:
XS GIS Cut Line= 3
       3712052.8     10168378.07      3712069.83     10167993.75
      3712063.23      10167545.4
#Sta/Elev= 30
  4615.3  314.88  4682.4   309.9  4692.4  310.72  4712.4  307.82  4779.5   304.5
  4802.5  302.41  4839.9  301.23  4852.5  299.25  4882.6  297.47  4912.6  297.17
  4942.6  295.72  4952.6  296.89  4990.7  295.49  4990.9  294.99  5042.7  296.74
  5105.3  300.02  5142.7  301.77  5152.7  301.35  5172.7  302.99  5202.7  303.62
  5242.7  305.98  5272.7  306.82  5292.7  308.82  5332.7  307.79  5342.7  308.15
  5362.7  311.21  5372.7  310.05  5392.7  311.14  5418.1  311.41  5448.4  313.48
#Mann= 6 ,-1 , 0
  4615.3     .11       0  4779.5     .17       0  4952.6     .09       0
  5042.7     .15       0  5105.3     .17       0  5418.1     .11       0
Bank Sta=4952.6,5042.7
XS Rating Curve= 0 ,0
Exp/Cntr=0.3,0.1

Type RM Length L Ch R = 1 ,16119   ,500,500,500
BEGIN DESCRIPTION:
CCLC 110 28.0
END DESCRIPTION:
XS GIS Cut Line= 3
      3712328.85     10168435.36      3712385.39     10167996.49
      3712417.85     10167761.11
#Sta/Elev= 30
  4557.5  308.79    4582  309.07  4587.9  307.56  4602.2  307.34  4630.9   305.8
  4692.9  302.18  4715.4   301.3  4738.8   300.3  4746.9  299.84  4753.4  298.79
  4773.6   298.5  4884.5  294.15  4980.2  294.53  5003.5  293.71  5003.7  293.21
  5007.2  293.21  5007.5  293.71  5012.8294.5671  5035.8  296.55  5045.8  296.76
  5052.8  294.07  5076.1  299.31  5096.3  299.72  5116.5   300.8  5177.1  306.51
  5196.6   307.6  5201.7  307.11  5207.4  308.62  5217.5  309.03  5237.6  310.94
#Mann= 6 ,-1 , 0
  4557.5     .11       0  4630.9     .17       0  4715.4     .11       0
  4738.8     .17       0  4980.2     .09       0  5012.8     .17       0
Bank Sta=4980.2,5012.8
XS Rating Curve= 0 ,0
Exp/Cntr=0.3,0.1

Type RM Length L Ch R = 1 ,15619   ,498,498,498
BEGIN DESCRIPTION:
CCLC 110 27.0
END DESCRIPTION:
XS GIS Cut Line= 3
      3712917.85     10168661.09      3712784.18      10168057.2
      3712767.86     10167911.11
#Sta/Elev= 30
  4381.5  317.32  4400.8  315.96  4405.9  316.61    4443  314.26  4449.5  313.11
  4463.5  313.15  4535.1  308.82  4541.9  307.54  4565.9  306.73  4585.5  304.03
  4647.8  299.51  4726.6  295.44  4750.2  295.21  4775.3  293.79    4781   292.7
  4803.2  292.11  4824.1  293.13  4873.1  293.36  4883.4  292.38  4916.4   293.7
  4962.6  293.58    5000  292.42  5004.4   288.8  5016.6  290.06  5026.3  292.21
  5056.5     297  5076.6  297.62  5101.9  300.67  5116.9  300.75    5147  304.22
#Mann= 5 ,-1 , 0
  4381.5     .17       0  4803.2     .15       0  4962.6     .17       0
    5000     .09       0  5026.3     .17       0
Bank Sta=5000,5026.3
XS Rating Curve= 0 ,0
Exp/Cntr=0.3,0.1

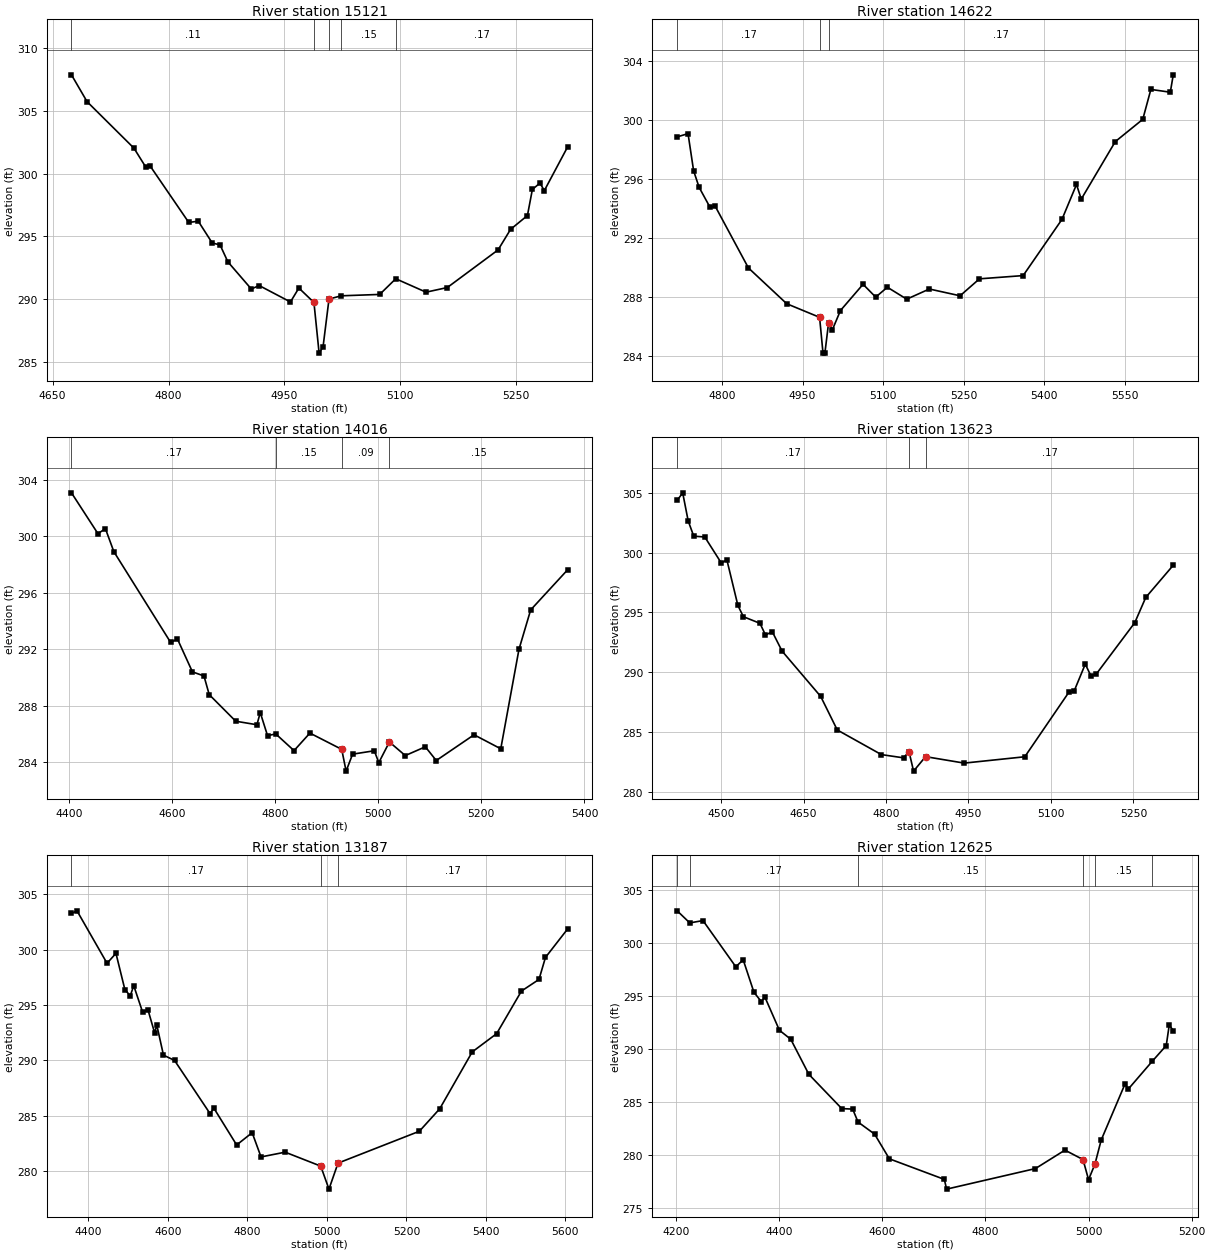
Type RM Length L Ch R = 1 ,15121   ,499,499,499
BEGIN DESCRIPTION:
CCLC 110 26.0
END DESCRIPTION:
XS GIS Cut Line= 3
      3713117.86     10168511.04      3713168.36     10168189.38
      3713017.85     10167911.07
#Sta/Elev= 30
  4674.4  307.88  4694.6  305.74  4755.3  302.03  4770.8   300.5  4775.9  300.64
  4826.2  296.11  4838.5  296.21  4856.6  294.47  4866.7  294.32  4876.8  292.97
  4907.2   290.8  4917.3  291.08  4957.8  289.77  4968.7  290.88  4988.2  289.73
  4994.9  285.69    5000  286.19  5007.7     290  5023.4  290.26  5073.3  290.37
  5094.1  291.62  5133.3  290.55  5160.8  290.92  5226.5  293.92  5242.7  295.56
  5264.5  296.66  5270.9  298.74  5280.7  299.25  5286.4  298.65  5316.4  302.12
#Mann= 5 ,-1 , 0
  4674.4     .11       0  4988.2     .07       0  5007.7     .11       0
  5023.4     .15       0  5094.1     .17       0
Bank Sta=4988.2,5007.7
XS Rating Curve= 0 ,0
Exp/Cntr=0.3,0.1

Type RM Length L Ch R = 1 ,14622   ,606,606,606
BEGIN DESCRIPTION:
CCLC 110 25.0
END DESCRIPTION:
XS GIS Cut Line= 3
      3713567.85     10168411.08      3713624.27     10168133.25
       3713272.2     10167597.83
#Sta/Elev= 30
  4716.5  298.84  4736.7  299.06  4747.1  296.54  4757.3  295.42  4777.7  294.06
  4787.4  294.13  4849.2  289.95  4920.6  287.52  4981.8   286.6  4988.2  284.17
  4991.7  284.17  4998.6  286.23  5005.6  285.75  5020.7  287.06  5062.8  288.84
  5086.4  287.97  5108.1  288.64  5144.2  287.83  5186.3  288.52  5243.6  288.06
  5279.7  289.21  5361.1  289.43  5433.4  293.24  5460.5  295.61  5469.4  294.62
  5532.8  298.52    5584  300.03  5599.1  302.06  5635.3  301.87  5640.8  303.05
#Mann= 3 , 0 , 0
  4716.5     .17       0  4981.8     .09       0  4998.6     .17       0
Bank Sta=4981.8,4998.6
XS Rating Curve= 0 ,0
Exp/Cntr=0.3,0.1

Type RM Length L Ch R = 1 ,14016   ,393,393,393
BEGIN DESCRIPTION:
CCLC 110 24.0
END DESCRIPTION:
XS GIS Cut Line= 3
      3714217.85     10168711.06      3714063.22     10168060.38
      3714217.87     10167811.05
#Sta/Elev= 30
    4405  303.06  4456.4  300.17  4470.8  300.53  4487.2   298.9  4597.4  292.48
  4610.6  292.72  4639.6   290.4    4662  290.11  4672.2  288.79  4723.6  286.91
  4764.7  286.66  4771.2  287.52  4785.3  285.89  4801.3  286.01  4836.7  284.83
  4867.5  286.07  4929.2  284.92  4937.7  283.38  4950.3  284.58  4992.4  284.82
  5001.1  283.98  5021.7  285.44  5052.5  284.48  5091.4   285.1  5112.6  284.13
  5185.9  285.95  5237.7  284.96    5273  291.99  5295.7  294.78  5367.2  297.61
#Mann= 4 ,-1 , 0
    4405     .17       0  4801.3     .15       0  4929.2     .09       0
  5021.7     .15       0
Bank Sta=4929.2,5021.7
XS Rating Curve= 0 ,0
Exp/Cntr=0.3,0.1

Type RM Length L Ch R = 1 ,13623   ,436,436,436
BEGIN DESCRIPTION:
CCLC 110 23.0
END DESCRIPTION:
XS GIS Cut Line= 3
      3714467.85     10168711.03      3714416.72     10168133.49
      3714417.85     10167811.09
#Sta/Elev= 30
  4420.2  304.36  4430.2  304.99  4440.2  302.64  4450.3  301.37  4470.4   301.3
  4500.5  299.12  4510.5   299.4  4530.6  295.58  4540.6  294.64  4570.7  294.09
  4580.8  293.11  4593.1  293.39  4610.9  291.77  4681.2  287.98  4711.3  285.18
  4791.6  283.12  4831.8  282.85  4841.8  283.37  4850.1  281.74  4871.9  282.95
  4942.2  282.41  5052.4  282.94  5132.4  288.32  5142.4  288.46  5162.4  290.68
  5172.4  289.72  5182.4  289.85  5252.4  294.14  5272.4  296.25  5322.4  298.94
#Mann= 3 , 0 , 0
  4420.2     .17       0  4841.8     .09       0  4871.9     .17       0
Bank Sta=4841.8,4871.9
XS Rating Curve= 0 ,0
Exp/Cntr=0.3,0.1

Type RM Length L Ch R = 1 ,13187   ,562,562,562
BEGIN DESCRIPTION:
CCLC 110 22.0
END DESCRIPTION:
XS GIS Cut Line= 3
      3714517.87     10168761.03      3714813.22     10168174.97
      3714938.23      10167596.8
#Sta/Elev= 30
  4357.5  303.28  4371.4  303.52    4447  298.78  4469.4  299.68  4491.8  296.41
  4505.3  295.84  4514.2  296.75  4536.6  294.35  4549.9  294.58  4566.6   292.5
  4572.2  293.19  4588.9  290.48  4616.8     290    4706   285.2  4715.8  285.68
    4773  282.36    4812  283.47  4834.3  281.28    4895  281.71  4984.5  280.45
  5005.2  278.37    5028  280.72  5232.6   283.6  5283.8  285.63  5365.6  290.77
    5427  292.42  5489.4  296.27  5533.5  297.32  5549.8  299.31  5605.3  301.87
#Mann= 3 , 0 , 0
  4357.5     .17       0  4984.5     .09       0    5028     .17       0
Bank Sta=4984.5,5028
XS Rating Curve= 0 ,0
Exp/Cntr=0.3,0.1

Type RM Length L Ch R = 1 ,12625   ,476,476,476
BEGIN DESCRIPTION:
CCLC 110 21.0
END DESCRIPTION:
XS GIS Cut Line= 3
      3714767.86     10168911.06      3715283.03     10168301.62
      3715367.87     10168161.04
#Sta/Elev= 30
    4202  303.06  4226.4  301.92    4252  302.14  4315.7  297.78    4330  298.44
  4350.9  295.37  4365.1   294.5  4372.2  294.91  4400.3  291.79  4422.3  290.94
  4457.4  287.63  4521.2   284.4  4542.4  284.35  4552.8  283.13  4584.9  281.99
  4613.5  279.66  4720.1  277.72  4724.6   276.8  4896.9  278.74  4954.1  280.48
  4989.2  279.59  4999.9  277.69  5012.3  279.16  5024.4  281.43  5070.7  286.73
  5076.8  286.23  5123.2  288.85  5150.6  290.35  5156.4  292.28  5164.2  291.76
#Mann= 6 ,-1 , 0
    4202     .11       0  4226.4     .17       0  4552.8     .15       0
  4989.2     .09       0  5012.3     .15       0  5123.2     .17       0
Bank Sta=4989.2,5012.3
XS Rating Curve= 0 ,0
Exp/Cntr=0.3,0.1

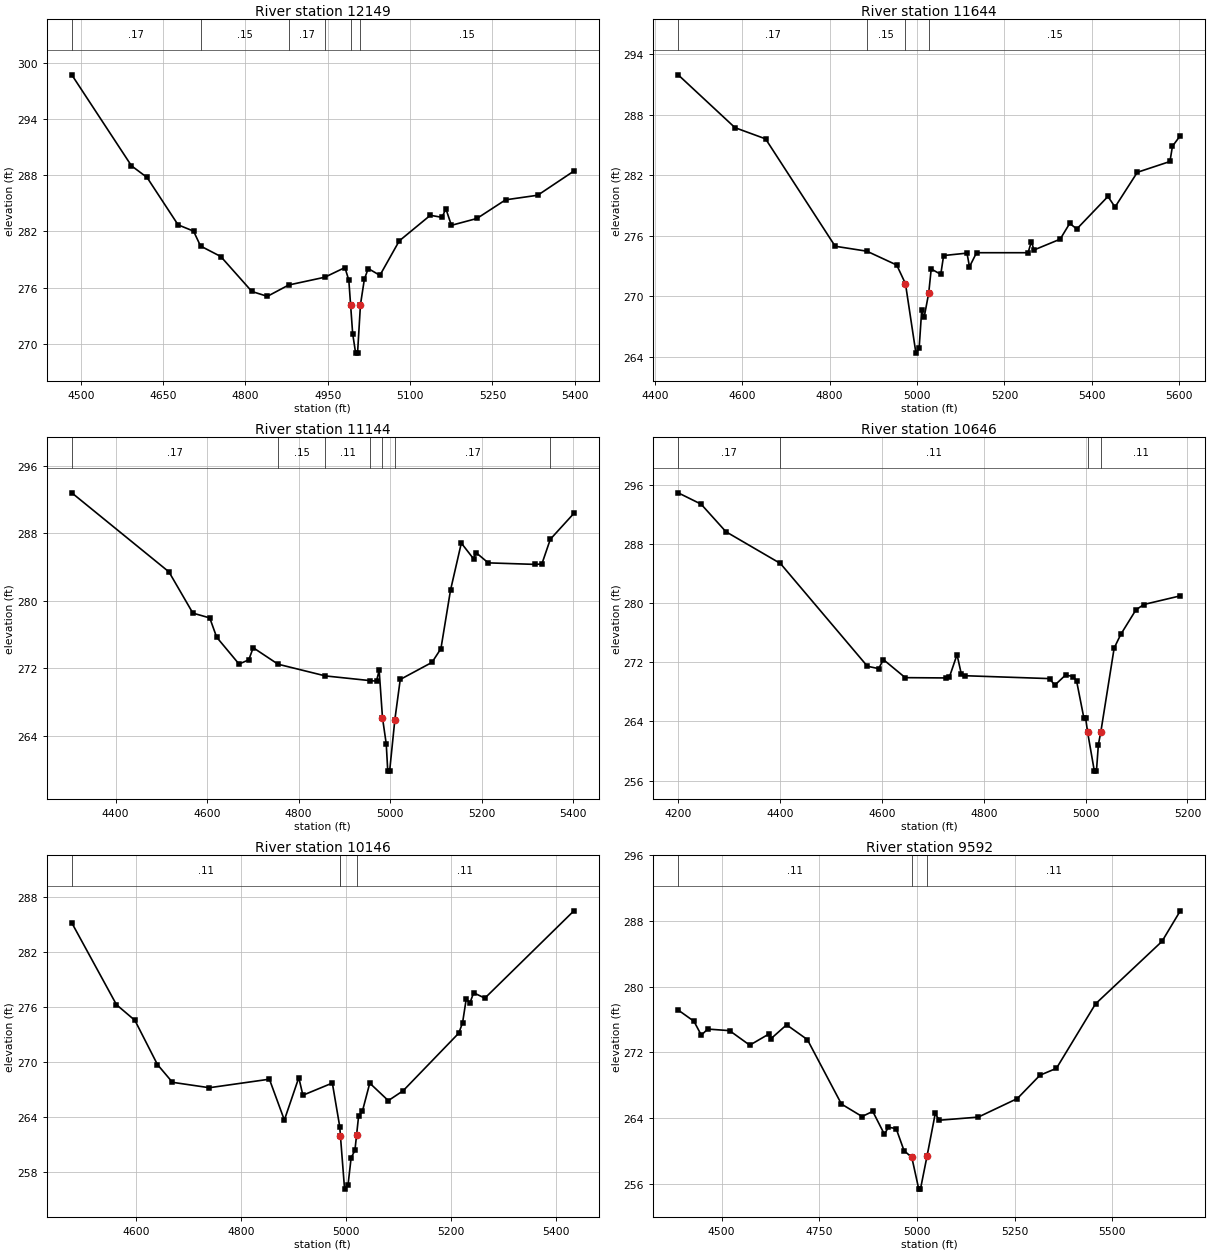
Type RM Length L Ch R = 1 ,12149   ,505,505,505
BEGIN DESCRIPTION:
CCLC 110 20.0
END DESCRIPTION:
XS GIS Cut Line= 3
      3715042.41     10169039.52      3715537.18     10168555.18
      3715474.67     10168341.61
#Sta/Elev= 30
  4483.5   298.7  4592.3  288.99  4620.6  287.75  4677.2  282.69  4705.4  282.02
  4718.1  280.43    4755  279.31  4811.6  275.58  4839.9  275.06  4878.7  276.27
  4944.5   277.1  4981.2  278.13  4988.3  276.78 4991.56274.1252  4995.3  271.08
  5000.7     269  5004.2     269  5009.5  274.17  5016.6  276.88  5023.6  278.03
  5044.9   277.3  5080.2  280.98  5136.8  283.71  5158.1  283.49  5165.1  284.41
  5175.2  282.64  5221.7  283.37  5273.9  285.36  5332.5  285.85  5398.4  288.43
#Mann= 6 ,-1 , 0
  4483.5     .17       0  4718.1     .15       0  4878.7     .17       0
  4944.5     .15       0 4991.56     .09       0  5009.5     .15       0
Bank Sta=4991.56,5009.5
XS Rating Curve= 0 ,0
Exp/Cntr=0.3,0.1

Type RM Length L Ch R = 1 ,11644   ,500,500,500
BEGIN DESCRIPTION:
CCLC 110 19.0
END DESCRIPTION:
XS GIS Cut Line= 3
      3715781.97     10169451.03      3715798.33     10168904.67
      3715511.98     10168374.45
#Sta/Elev= 30
  4453.4  291.93  4583.4   286.7  4653.4  285.59  4812.7  274.96  4885.3  274.47
  4953.6   273.1  4973.6  271.25  4997.5  264.38  5004.9  264.88  5010.7   268.6
  5016.3  267.92  5026.8  270.32  5032.5  272.71  5054.4  272.18  5060.9  274.04
  5114.4  274.28  5120.1  272.93  5136.3  274.32  5254.1  274.32  5261.9  275.42
  5267.6  274.59  5327.6  275.66  5349.5  277.22  5365.7  276.67    5437  279.89
  5453.2  278.84  5504.2  282.28  5578.9  283.35  5584.6  284.86  5602.6  285.91
#Mann= 4 ,-1 , 0
  4453.4     .17       0  4885.3     .15       0  4973.6     .09       0
  5026.8     .15       0
Bank Sta=4973.6,5026.8
XS Rating Curve= 0 ,0
Exp/Cntr=0.3,0.1

Type RM Length L Ch R = 1 ,11144   ,498,498,498
BEGIN DESCRIPTION:
CCLC 110 18.0
END DESCRIPTION:
XS GIS Cut Line= 3
      3715865.28     10169471.88      3716225.87     10168876.92
      3716349.12     10168494.39
#Sta/Elev= 30
  4304.3  292.83  4516.7  283.44    4569  278.54  4605.9  277.97    4621  275.68
  4669.9  272.49  4691.2  272.99  4700.9  274.43  4755.2  272.47  4858.7  271.08
  4956.8  270.52  4970.4  270.46  4976.2  271.75  4983.5   266.1  4991.7     263
    4995  259.77  4999.1  259.77 5010.55265.8988  5022.3  270.66  5091.7  272.69
  5111.2  274.32  5132.2  281.27  5155.8  286.86  5182.7  284.98  5187.9  285.73
  5214.7  284.51  5316.2  284.33  5331.8  284.37  5350.4  287.32  5401.9  290.39
#Mann= 7 ,-1 , 0
  4304.3     .17       0  4755.2     .15       0  4858.7     .11       0
  4956.8     .17       0  4983.5     .09       0 5010.55     .17       0
  5350.4     .11       0
Bank Sta=4983.5,5010.55
XS Rating Curve= 0 ,0
Exp/Cntr=0.3,0.1

Type RM Length L Ch R = 1 ,10646   ,500,500,500
BEGIN DESCRIPTION:
CCLC 110 17.0
END DESCRIPTION:
XS GIS Cut Line= 3
      3715917.88     10169561.06      3716608.82     10169157.43
      3716767.81     10169061.09
#Sta/Elev= 30
  4199.8   294.9  4244.8  293.37  4293.6  289.64  4400.5  285.35  4571.4  271.45
  4593.5  271.13  4602.8  272.35  4645.7  269.91  4725.9  269.87  4732.5     270
  4747.4  273.02  4755.7  270.44  4763.1  270.17  4929.4  269.78  4939.2  268.88
  4960.7  270.27  4975.7  270.05  4982.2  269.47  4996.5  264.46    5000  264.46
  5003.7  262.59  5017.1  257.27  5021.2  257.27    5025  260.85 5029.92262.6245
    5056  273.91    5069  275.76  5098.7  279.07  5114.2   279.8  5185.9  280.97
#Mann= 4 ,-1 , 0
  4199.8     .17       0  4400.5     .11       0  5003.7     .06       0
 5029.92     .11       0
Bank Sta=5003.7,5029.92
XS Rating Curve= 0 ,0
Exp/Cntr=0.3,0.1

Type RM Length L Ch R = 1 ,10146   ,554,554,554
BEGIN DESCRIPTION:
CCLC 110 16.0
END DESCRIPTION:
XS GIS Cut Line= 3
      3716517.87     10169861.06      3716918.28     10169524.45
      3717217.83     10169211.09
#Sta/Elev= 30
  4476.9  285.17  4562.1  276.23  4597.2  274.52  4640.1   269.7  4668.7  267.76
    4739  267.17  4853.4   268.1  4881.9  263.64  4909.4  268.27  4917.2  266.35
  4973.3  267.68  4987.4  262.92  4988.8 261.845  4996.6   256.1  5003.3   256.6
  5009.1  259.53  5016.3  260.32  5019.4261.9719  5023.3  264.05  5030.5  264.59
  5044.6  267.67  5079.9  265.76  5108.2  266.84  5214.2  273.13  5221.4  274.26
  5228.3  276.83  5235.6  276.46  5242.5  277.53  5263.9  276.95  5433.5  286.48
#Mann= 4 ,-1 , 0
  4476.9     .11       0  4987.4     .09       0  4988.8     .06       0
  5019.4     .11       0
Bank Sta=4988.8,5019.4
XS Rating Curve= 0 ,0
Exp/Cntr=0.3,0.1

Type RM Length L Ch R = 1 ,9592    ,195,195,195
BEGIN DESCRIPTION:
CCLC 110 15.0
END DESCRIPTION:
XS GIS Cut Line= 3
      3717193.42     10170508.34      3717276.76     10170190.59
      3717318.34     10169234.19
#Sta/Elev= 30
  4388.6  277.16    4429  275.79  4447.8   274.1  4464.3  274.84  4520.2  274.65
  4571.9  272.88  4620.6  274.23  4625.8  273.65  4666.2  275.36  4719.4  273.56
  4806.7  265.71  4859.6  264.19  4886.8  264.82  4916.8  262.02  4926.8  262.89
  4946.8  262.72  4966.9  260.04  4986.9  259.21  5004.7  255.35    5009  255.35
  5026.1 259.428  5046.9  264.56  5056.9  263.74    5157  264.12  5257.1  266.38
    5315  269.22  5357.2  270.06  5457.3  277.91  5627.5  285.52  5674.4  289.24
#Mann= 3 , 0 , 0
  4388.6     .11       0  4986.9     .06       0  5026.1     .11       0
Bank Sta=4986.9,5026.1
XS Rating Curve= 0 ,0
Exp/Cntr=0.3,0.1

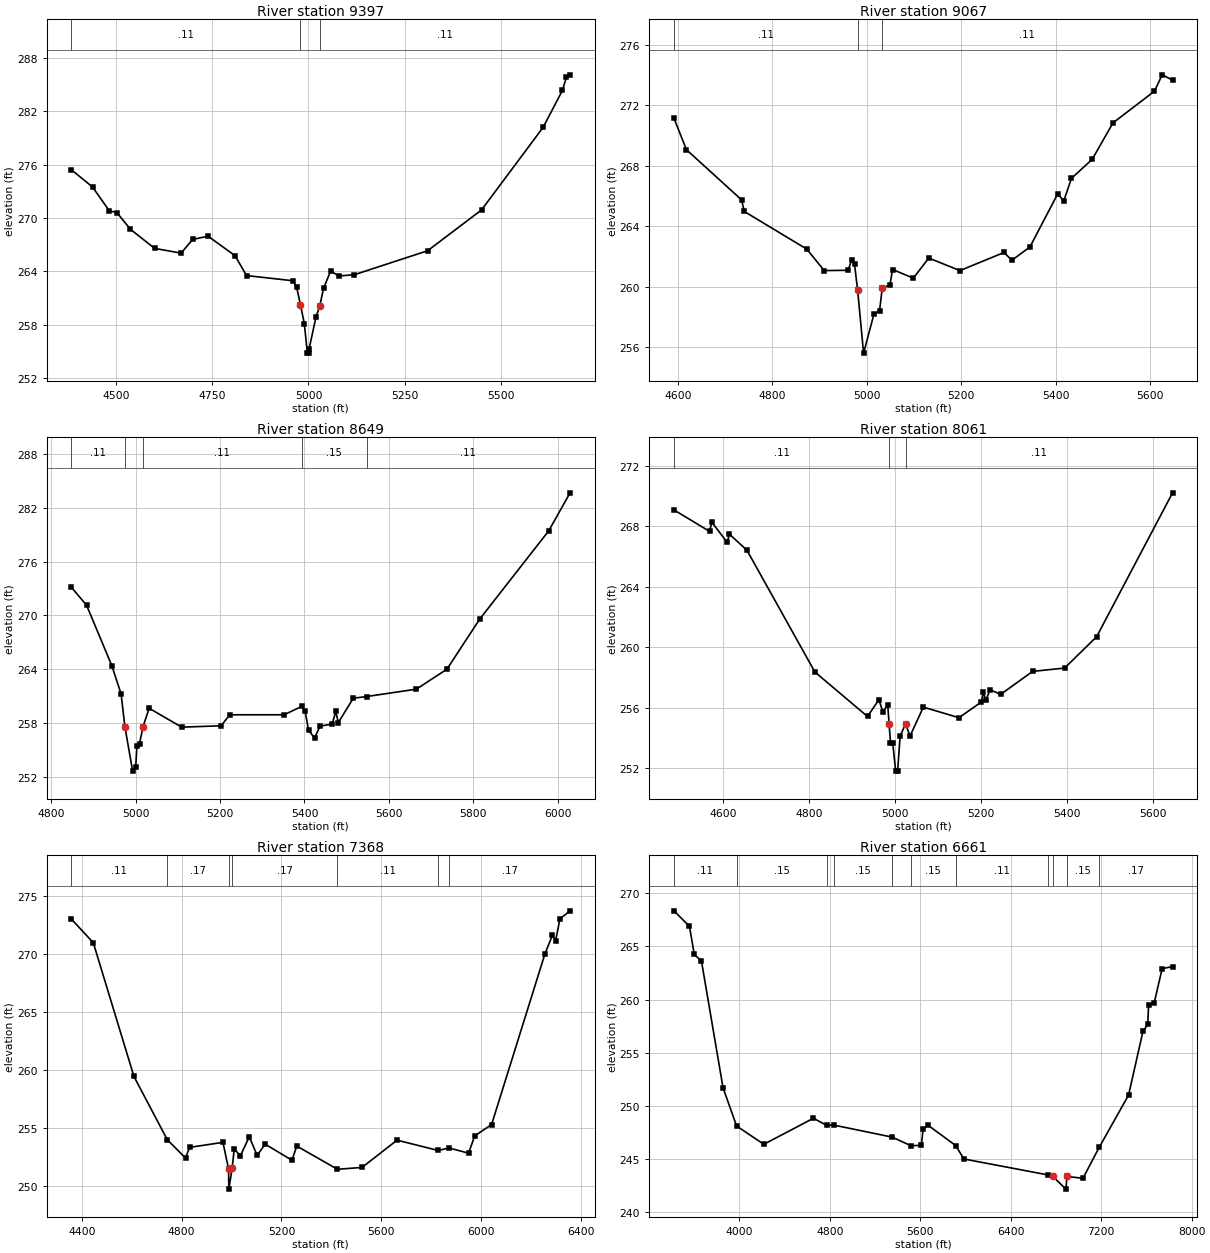
Type RM Length L Ch R = 1 ,9397    ,330,330,330
BEGIN DESCRIPTION:
Mapping XS 68823850
END DESCRIPTION:
XS GIS Cut Line= 3
      3717349.69     10170612.43      3717422.59     10170419.76
      3717469.47     10169331.27
#Sta/Elev= 30
  4384.2  275.41  4439.1  273.47  4482.6  270.79    4502  270.61  4537.5  268.72
  4600.1  266.58    4669  266.04    4699  267.58    4739  267.95  4809.1  265.76
  4839.1  263.52  4959.2  262.94  4969.2  262.23  4979.2  260.23  4989.3  258.11
  4997.1   254.8  5001.4   254.8  5001.8   255.3  5019.3  258.82  5029.3   260.1
  5039.3   262.1  5057.7  264.03  5079.3  263.47  5119.4  263.62  5309.6  266.31
  5449.7   270.9  5609.8  280.19  5659.9  284.34  5669.9  285.79  5679.7  286.09
#Mann= 3 ,-1 , 0
  4384.2     .11       0  4979.2     .07       0  5029.3     .11       0
Bank Sta=4979.2,5029.3
XS Rating Curve= 0 ,0
Exp/Cntr=0.3,0.1

Type RM Length L Ch R = 1 ,9067    ,418,418,418
BEGIN DESCRIPTION:
CCLC 110 14.0
END DESCRIPTION:
XS GIS Cut Line= 3
      3717438.21     10170596.86      3717656.97     10170232.26
      3717953.03     10169676.49
#Sta/Elev= 30
    4592  271.15  4618.3  269.07    4735  265.75  4740.8  264.98    4873  262.49
  4909.9  261.07  4960.3  261.09  4968.2  261.79    4974   261.5  4980.5259.7938
  4993.2  255.61    5015  258.18    5027  258.42  5032.6  259.89  5048.9  260.14
  5054.6  261.14  5098.5  260.57  5131.1   261.9    5197  261.07  5290.5  262.27
  5306.8  261.75  5345.1  262.63  5403.8  266.14  5416.7  265.68    5433  267.17
  5476.9  268.43  5520.8  270.84  5608.7  272.94    5625  274.02  5646.9  273.67
#Mann= 3 , 0 , 0
    4592     .11       0  4980.5     .06       0  5032.6     .11       0
Bank Sta=4980.5,5032.6
XS Rating Curve= 0 ,0
Exp/Cntr=0.3,0.1

Type RM Length L Ch R = 1 ,8649    ,588,588,588
BEGIN DESCRIPTION:
CCLC 110 13.0
END DESCRIPTION:
XS GIS Cut Line= 3
      3717767.85     10170711.08      3717840.16     10170577.05
      3718467.87     10169761.05
#Sta/Elev= 30
  4847.7  273.13  4883.4  271.15  4943.4  264.39  4965.3  261.24 4974.37257.5693
  4992.7  252.62    5000  253.12  5002.8  255.46  5009.1  255.69  5017.3  257.58
  5031.8  259.64  5108.8  257.53  5202.2  257.68    5223  258.91  5351.7  258.91
    5393  259.84  5401.5  259.32  5409.7  257.18  5423.9  256.32  5436.8  257.64
  5465.8  257.88    5474  259.28  5480.3  258.04  5515.7  260.76  5547.7  260.95
  5665.2  261.77  5737.7     264    5815  269.57    5979  279.45  6029.5  283.69
#Mann= 5 ,-1 , 0
  4847.7     .11       0 4974.37     .06       0  5017.3     .11       0
    5393     .15       0  5547.7     .11       0
Bank Sta=4974.37,5017.3
XS Rating Curve= 0 ,0
Exp/Cntr=0.3,0.1

Type RM Length L Ch R = 1 ,8061    ,693,693,693
BEGIN DESCRIPTION:
CCLC 110 12.0
END DESCRIPTION:
XS GIS Cut Line= 3
      3718271.54     10171133.35      3718396.55     10170643.72
      3718567.86     10170011.04
#Sta/Elev= 30
  4484.7  269.08  4567.7  267.66  4572.8  268.27  4608.5  266.94  4613.7  267.48
  4654.5  266.42  4812.8  258.37  4935.3  255.43  4961.8  256.54    4971  255.75
  4982.4  256.19 4985.63254.9333  4988.8   253.7    4994   253.7  5000.8  251.82
  5005.4  251.82  5011.2  254.12  5023.9  254.95  5034.2  254.13  5065.3  256.05
  5148.2  255.35    5200  256.38  5205.3  257.04  5210.5  256.49  5220.7   257.2
  5245.2  256.89  5319.7  258.41  5394.2  258.63  5468.7   260.7  5645.5  270.21
#Mann= 3 , 0 , 0
  4484.7     .11       0 4985.63     .06       0  5023.9     .11       0
Bank Sta=4985.63,5023.9
XS Rating Curve= 0 ,0
Exp/Cntr=0.3,0.1

Type RM Length L Ch R = 1 ,7368    ,707,707,707
BEGIN DESCRIPTION:
CCLC 110 11.0
END DESCRIPTION:
XS GIS Cut Line= 3
      3718349.69     10171279.12      3718917.38     10170992.68
      3719396.55     10169716.64
#Sta/Elev= 30
  4358.3  272.96  4445.8  270.93  4608.8   259.4  4742.4  253.95  4815.5  252.37
  4831.8  253.29  4965.6  253.72  4987.9  251.45  4989.3  249.69 5002.53251.5089
  5010.8  253.14  5035.7  252.57  5071.3  254.21  5102.7  252.59  5134.7  253.57
  5242.1  252.18  5261.7   253.4  5424.7   251.4  5523.2  251.56  5663.7  253.91
  5828.9  253.02  5871.6  253.24  5950.2  252.79  5975.1  254.28  6042.7  255.26
  6256.2  269.95  6286.4  271.58  6299.1  271.09  6316.7  272.99  6357.2  273.68
#Mann= 7 ,-1 , 0
  4358.3     .11       0  4742.4     .17       0  4987.9     .09       0
 5002.53     .17       0  5424.7     .11       0  5828.9     .15       0
  5871.6     .17       0
Bank Sta=4987.9,5002.53
XS Rating Curve= 0 ,0
Exp/Cntr=0.3,0.1

Type RM Length L Ch R = 1 ,6661    ,2079,2079,2079
BEGIN DESCRIPTION:
CCLC 110 10.0
END DESCRIPTION:
XS GIS Cut Line= 3
       3718349.7     10172466.61      3719465.29     10171351.84
       3721432.7     10169315.91
#Sta/Elev= 30
  3422.9  268.35  3559.9  266.89  3602.3  264.24  3665.9  263.63  3856.8  251.69
  3976.8  248.09  4217.5  246.37  4655.9  248.82  4772.7  248.16  4835.7  248.18
  5350.3  247.05  5516.1  246.25  5610.6  246.26  5624.8  247.77  5667.2  248.18
  5915.2  246.24  5985.4  244.99    6728  243.49  6770.3  243.37  6888.4  242.15
  6897.7  243.34  7039.1  243.17  7181.8  246.07  7442.2     251  7569.6  257.01
    7612  257.65    7619  259.46  7668.6  259.68  7739.4  262.91  7831.2   263.1
#Mann= 11 ,-1 , 0
  3422.9     .11       0  3976.8     .15       0  4772.7     .11       0
  4835.7     .15       0  5350.3     .11       0  5516.1     .15       0
  5915.2     .11       0    6728     .15       0  6770.3     .09       0
  6897.7     .15       0  7181.8     .17       0
Bank Sta=6770.3,6897.7
XS Rating Curve= 0 ,0
Exp/Cntr=0.3,0.1

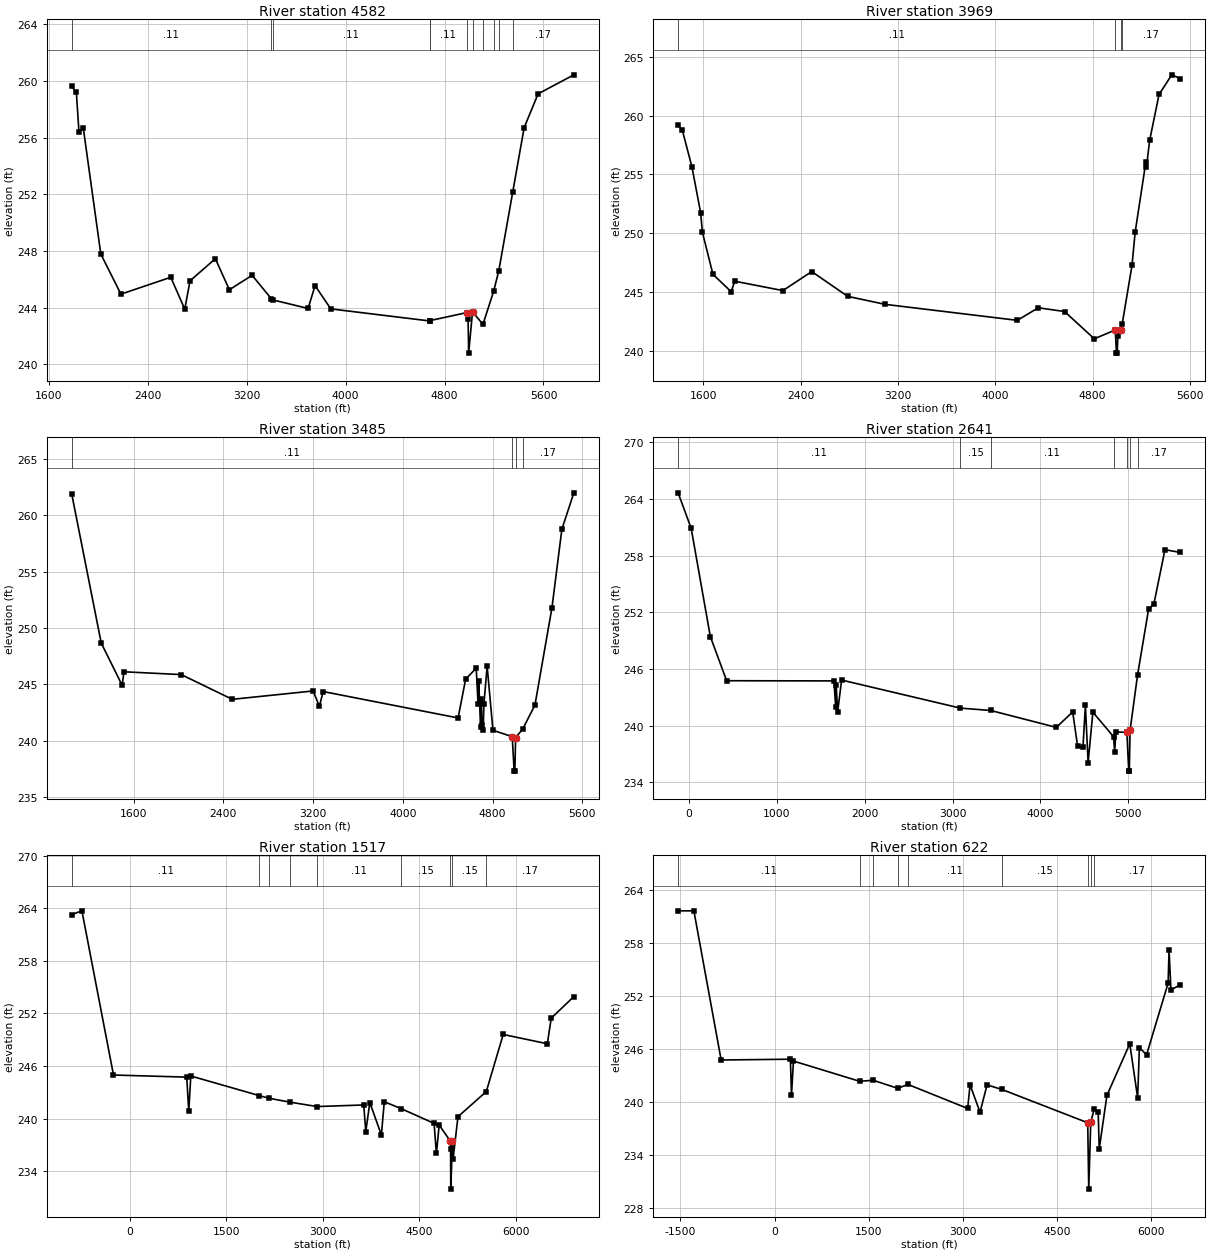
Type RM Length L Ch R = 1 ,4582    ,613,613,613
BEGIN DESCRIPTION:
CCLC 110 9.0
END DESCRIPTION:
XS GIS Cut Line= 3
      3718631.62     10172498.37      3720905.08     10170305.65
      3721511.14     10169636.77
#Sta/Elev= 30
  1784.6  259.61  1822.4  259.21  1843.7  256.42    1879  256.66  2020.4  247.79
    2183  244.96  2586.2  246.15  2699.3   243.9  2741.8   245.9  2946.8  247.46
    3060  245.27    3244  246.29  3398.4  244.65  3413.7  244.55  3696.6  243.95
  3753.1  245.56  3880.4  243.92  4679.1  243.07  4685.1   243.1 4977.78 243.654
  4990.6  243.19  4995.3   240.8  5026.4  243.71  5110.9  242.83  5197.8  245.18
  5239.1  246.62  5351.4  252.15  5444.1  256.71  5556.9  259.09  5845.8  260.43
#Mann= 11 ,-1 , 0
  1784.6     .11       0  3398.4     .15       0  3413.7     .11       0
  4679.1     .15       0  4685.1     .11       0 4977.78     .06       0
  5026.4     .11       0  5110.9     .15       0  5197.8     .11       0
  5239.1     .15       0  5351.4     .17       0
Bank Sta=4977.78,5026.4
XS Rating Curve= 0 ,0
Exp/Cntr=0.3,0.1

Type RM Length L Ch R = 1 ,3969    ,484,484,484
BEGIN DESCRIPTION:
CCLC 110 8.0
END DESCRIPTION:
XS GIS Cut Line= 3
      3718629.16     10172510.06      3721459.05     10170556.91
      3721684.71     10169905.99
#Sta/Elev= 30
  1393.7  259.19  1428.6  258.75  1506.9  255.65  1578.6  251.75  1593.5  250.07
    1680  246.49  1829.5  245.02  1859.2  245.91  2254.8  245.11    2492  246.73
  2787.4  244.62    3095  243.94  4181.5  242.58  4354.5  243.65  4569.5  243.33
  4814.3  241.01  4986.5  241.76  4996.3  239.79  5002.6  239.79  5007.7  241.25
 5033.07241.8004    5043  242.23  5124.1  247.26  5149.8  250.07    5238  256.05
  5243.2  255.65  5269.1  257.89  5346.4   261.8  5450.7  263.47  5521.1  263.15
#Mann= 4 ,-1 , 0
  1393.7     .11       0  4986.5     .06       0 5033.07     .11       0
    5043     .17       0
Bank Sta=4986.5,5033.07
XS Rating Curve= 0 ,0
Exp/Cntr=0.3,0.1

Type RM Length L Ch R = 1 ,3485    ,844,844,844
BEGIN DESCRIPTION:
CCLC 110 7.0
END DESCRIPTION:
XS GIS Cut Line= 3
      3718603.18     10172562.11      3721867.04     10170886.77
      3721988.56     10170088.19
#Sta/Elev= 30
  1047.9   261.9  1311.7  248.66  1498.1  244.92    1514  246.12  2025.1  245.87
  2479.8  243.68  3200.1  244.42  3256.4  243.06  3289.6  244.37  4492.7  242.03
  4559.7  245.46  4654.1  246.44  4670.7  243.27  4676.3   245.3  4692.8  241.24
  4698.5  243.74  4706.3  241.44  4716.6  240.96  4722.4  243.23  4751.5  246.62
  4803.3  240.94  4975.3  240.37  4992.3  237.32  4998.6  237.32  5005.6  240.29
  5068.2  241.04  5177.6  243.17  5329.3  251.79  5417.6  258.74  5524.4  261.97
#Mann= 4 ,-1 , 0
  1047.9     .11       0  4975.3     .06       0  5005.6     .11       0
  5068.2     .17       0
Bank Sta=4975.3,5005.6
XS Rating Curve= 0 ,0
Exp/Cntr=0.3,0.1

Type RM Length L Ch R = 1 ,2641    ,1124,1124,1124
BEGIN DESCRIPTION:
CCLC 110 5.0
END DESCRIPTION:
XS GIS Cut Line= 3
       3718507.7     10172648.91      3722873.98     10171095.11
      3722483.35     10170088.14
#Sta/Elev= 30
  -122.9  264.64    25.9  260.87   243.5  249.43   429.2  244.75  1650.3  244.73
  1670.5  241.93  1675.8  244.27  1692.3  241.45  1737.5  244.82  3089.1  241.85
  3434.4   241.6    4181  239.81  4367.1  241.45  4422.4  237.85    4484  237.69
  4511.6  242.14  4542.6  236.09    4597  241.42  4831.6  238.83  4844.8  237.24
  4859.2  239.32  4983.7  239.29    5005  235.18  5011.4  235.18  5020.1   239.5
  5104.8  245.33  5231.4  252.36  5291.3  252.88  5416.9  258.62  5591.7  258.33
#Mann= 7 ,-1 , 0
  -122.9     .11       0  3089.1     .15       0  3434.4     .11       0
  4831.6     .15       0  4983.7     .09       0  5020.1     .15       0
  5104.8     .17       0
Bank Sta=4983.7,5020.1
XS Rating Curve= 0 ,0
Exp/Cntr=0.3,0.1

Type RM Length L Ch R = 1 ,1517    ,895,895,895
BEGIN DESCRIPTION:
CCLC 110 3.0
END DESCRIPTION:
XS GIS Cut Line= 3
       3718420.9     10172727.04      3723776.76     10170912.81
      3722943.41     10168916.24
#Sta/Elev= 30
  -910.3  263.29  -750.7  263.72  -258.9  244.97   881.4  244.73     913  240.82
   944.7  244.86  2010.4  242.62  2158.8  242.32  2491.1  241.87  2908.3  241.37
    3637  241.55  3668.7  238.51  3731.9  241.83  3911.6  238.12  3957.1  241.92
  4216.8  241.14  4732.1  239.45  4768.1  236.01  4811.7  239.26  4983.8  237.44
  4989.2  236.52  4991.9  231.94  5018.5  237.46  5028.1   235.4    5104  240.21
  5544.8  243.08  5808.3   249.6  6495.2  248.54    6556  251.46    6908  253.93
#Mann= 9 ,-1 , 0
  -910.3     .11       0  2010.4     .15       0  2158.8     .11       0
  2491.1     .15       0  2908.3     .11       0  4216.8     .15       0
  4983.8     .09       0  5018.5     .15       0  5544.8     .17       0
Bank Sta=4983.8,5018.5
XS Rating Curve= 0 ,0
Exp/Cntr=0.3,0.1

Type RM Length L Ch R = 1 ,622     ,0,0,0
BEGIN DESCRIPTION:
CCLC 110 1.0
END DESCRIPTION:
XS GIS Cut Line= 3
       3718394.8      10172796.5       3724384.4     10170765.24
      3724054.68     10169125.32
#Sta/Elev= 30
 -1536.1  261.66 -1285.2  261.66  -850.8  244.76   251.7  244.85   269.3  240.78
   300.7  244.64  1353.6  242.35    1573  242.46  1960.9  241.55  2124.1  241.99
  3074.9  239.27  3113.3  241.95  3271.7  238.84  3383.7  241.94  3620.9  241.42
  4986.6  237.65  5003.3  230.13 5035.14237.7026  5090.1  239.21  5153.2  238.92
  5170.2  234.68  5292.6  240.75  5656.8   246.6  5782.2  240.45  5809.4  246.14
    5925  245.37  6267.2  253.47    6282  257.17  6312.6  252.69  6461.3   253.3
#Mann= 9 ,-1 , 0
 -1536.1     .11       0  1353.6     .15       0    1573     .11       0
  1960.9     .15       0  2124.1     .11       0  3620.9     .15       0
  4986.6     .09       0 5035.14     .15       0  5090.1     .17       0
Bank Sta=4986.6,5035.14
XS Rating Curve= 0 ,0
Exp/Cntr=0.3,0.1

Chan Stop Cuts=-1
Use User Specified Reach Order=0
Composite Channel Slope=5