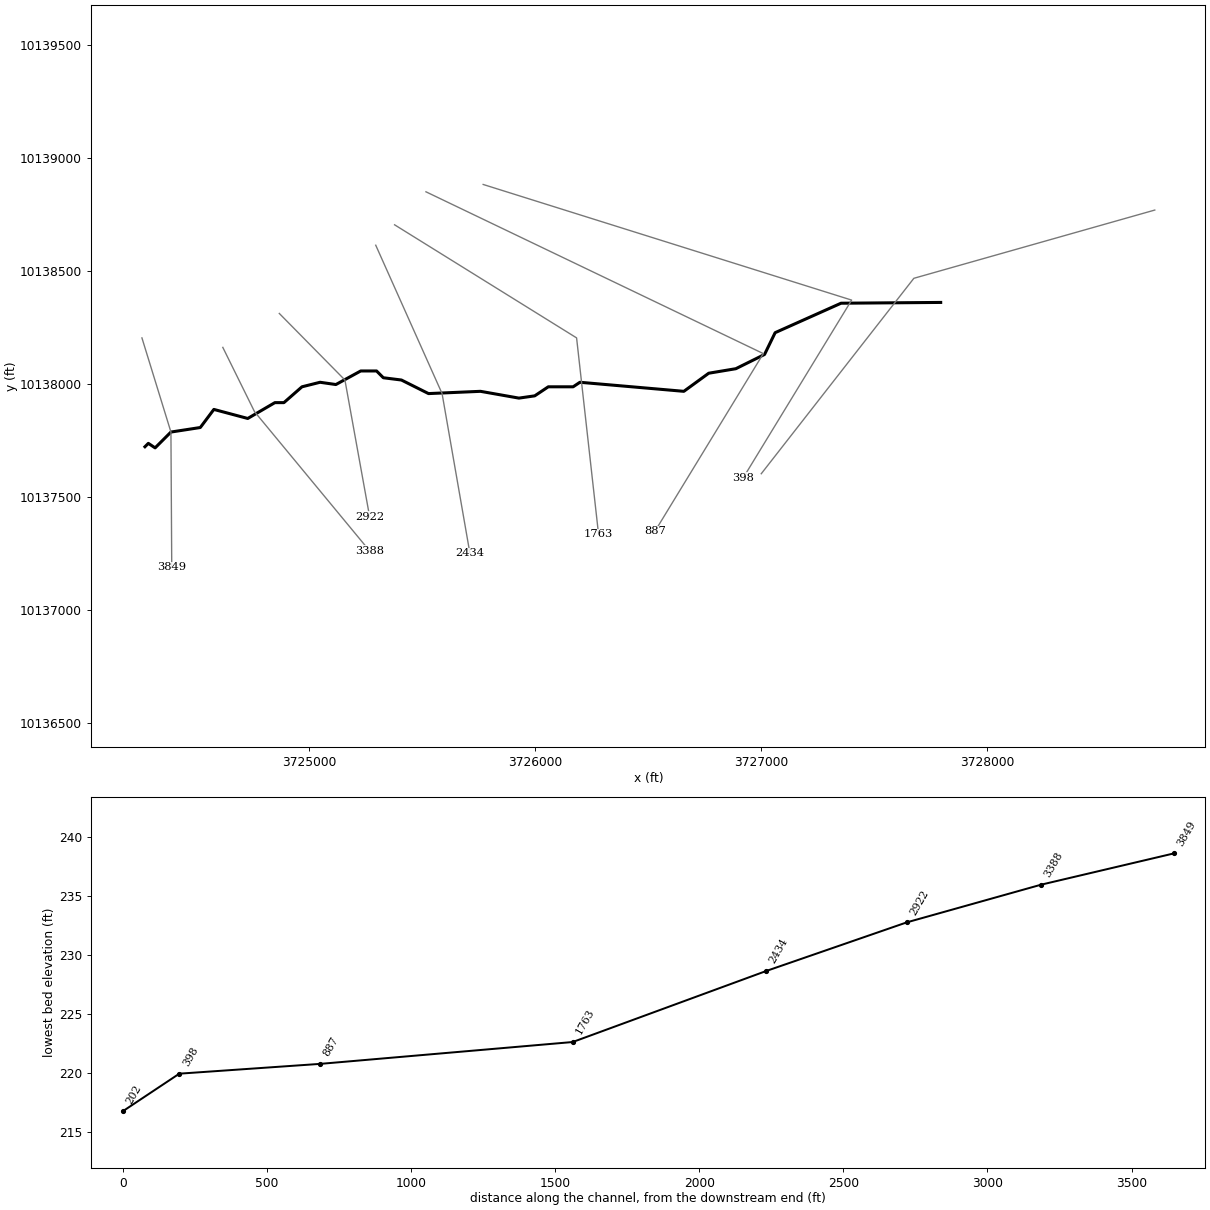
--- CCLC 112.prj (project) ---

Proj Title=CCLC 112 Base Level Engineering
Current Plan=p01
Default Exp/Contr=0.3,0.1
English Units
Geom File=g01
Flow File=f01
Flow File=f02
Plan File=p01
Y Axis Title=Elevation
X Axis Title(PF)=Main Channel Distance
X Axis Title(XS)=Station
BEGIN DESCRIPTION:
CCLC 112
END DESCRIPTION:
DSS Export Rating Curves= 0
DSS Export Rating Curve Sorted= 0
DSS Export Volume Flow Curves= 0
DXF OffsetX= 0
DXF OffsetY= 0
DXF ScaleX= 1
DXF ScaleY= 10

--- CCLC 112.p01 (plan) ---

Plan Title=Multiple Run
Short Identifier=Multiple
Geom File=g01
Flow File=f01
Subcritical Flow
K Sum by GR= 0
Std Step Tol= 0.01
Critical Tol= 0.01
Num of Std Step Trials= 20
Max Error Tol= 0.3
Flow Tol Ratio= 0.001
Split Flow NTrial= 30
Split Flow Tol= 0.02
Split Flow Ratio= 0.02
Log Output Level= 0
Friction Slope Method= 1
Unsteady Friction Slope Method= 2
Unsteady Bridges Friction Slope Method= 1
Parabolic Critical Depth
Global Vel Dist=  1 , 1 , 1
Global Log Level= 0
CheckData=True
Encroach Param= -1, 0, 0, 0
BEGIN DESCRIPTION:
Multiple Run
END DESCRIPTION:

--- CCLC 112.f01 (steady flow) ---

Flow Title=Multiple
Program Version=4.10
Number of Profiles= 7
Profile Names=10-year,25-year,50-year,1pct_min,100-year,1pct_plu,500-year
River Rch & RM=CCLC 112,Reach-1         ,3849
     565     763    1029     458    1382    4174    2575
River Rch & RM=CCLC 112,Reach-1         ,202
    5061    7229   10114    4614   13935   42083   27374
Boundary for River Rch & Prof#=CCLC 112,Reach-1         , 1
Up Type= 0
Dn Type= 3
Dn Slope=0.005
Boundary for River Rch & Prof#=CCLC 112,Reach-1         , 2
Up Type= 0
Dn Type= 3
Dn Slope=0.005
Boundary for River Rch & Prof#=CCLC 112,Reach-1         , 3
Up Type= 0
Dn Type= 3
Dn Slope=0.005
Boundary for River Rch & Prof#=CCLC 112,Reach-1         , 4
Up Type= 0
Dn Type= 3
Dn Slope=0.005
Boundary for River Rch & Prof#=CCLC 112,Reach-1         , 5
Up Type= 0
Dn Type= 3
Dn Slope=0.005
Boundary for River Rch & Prof#=CCLC 112,Reach-1         , 6
Up Type= 0
Dn Type= 3
Dn Slope=0.005
Boundary for River Rch & Prof#=CCLC 112,Reach-1         , 7
Up Type= 0
Dn Type= 3
Dn Slope=0.005
DSS Import GetInterval= 0
DSS Import GetPeak= 0
DSS Import FillOption= 0

--- CCLC 112.f02 (steady flow) ---

Flow Title=Orig_BLE_Flows
Program Version=4.10
Number of Profiles= 7
Profile Names=10-year,25-year,50-year,1pct_min,100-year,1pct_plu,500-year
River Rch & RM=CCLC 112,Reach-1         ,3849
     565     748     895     352    1063    3211    1497
River Rch & RM=CCLC 112,Reach-1         ,202
    5061    7087    8795    3549   10719   32370   15915
Boundary for River Rch & Prof#=CCLC 112,Reach-1         , 1
Up Type= 0
Dn Type= 3
Dn Slope=0.005
Boundary for River Rch & Prof#=CCLC 112,Reach-1         , 2
Up Type= 0
Dn Type= 3
Dn Slope=0.005
Boundary for River Rch & Prof#=CCLC 112,Reach-1         , 3
Up Type= 0
Dn Type= 3
Dn Slope=0.005
Boundary for River Rch & Prof#=CCLC 112,Reach-1         , 4
Up Type= 0
Dn Type= 3
Dn Slope=0.005
Boundary for River Rch & Prof#=CCLC 112,Reach-1         , 5
Up Type= 0
Dn Type= 3
Dn Slope=0.005
Boundary for River Rch & Prof#=CCLC 112,Reach-1         , 6
Up Type= 0
Dn Type= 3
Dn Slope=0.005
Boundary for River Rch & Prof#=CCLC 112,Reach-1         , 7
Up Type= 0
Dn Type= 3
Dn Slope=0.005
DSS Import GetInterval= 0
DSS Import GetPeak= 0
DSS Import FillOption= 0

--- CCLC 112.g01 (geometry) ---

Geom Title=Existing Conditions
Program Version=4.10

River Reach=CCLC 112        ,Reach-1
Reach XY= 30
      3724273.23     10137721.84      3724288.23     10137736.84
      3724318.23     10137716.84      3724388.23     10137786.84
      3724518.23     10137806.84      3724578.23     10137886.84
      3724728.23     10137846.84      3724848.23     10137916.84
      3724888.23     10137916.84      3724968.23     10137986.84
      3725048.23     10138006.84      3725118.23     10137996.84
      3725228.23     10138056.84      3725298.23     10138056.84
      3725328.23     10138026.84      3725408.23     10138016.84
      3725528.23     10137956.84      3725758.23     10137966.84
      3725928.23     10137936.84      3725998.23     10137946.84
      3726058.23     10137986.84      3726168.23     10137986.84
      3726198.23     10138006.84      3726658.23     10137966.84
      3726768.23     10138046.84      3726888.23     10138066.84
      3727015.32     10138129.78       3727062.2     10138226.13
      3727353.86     10138356.34      3727794.89     10138359.81

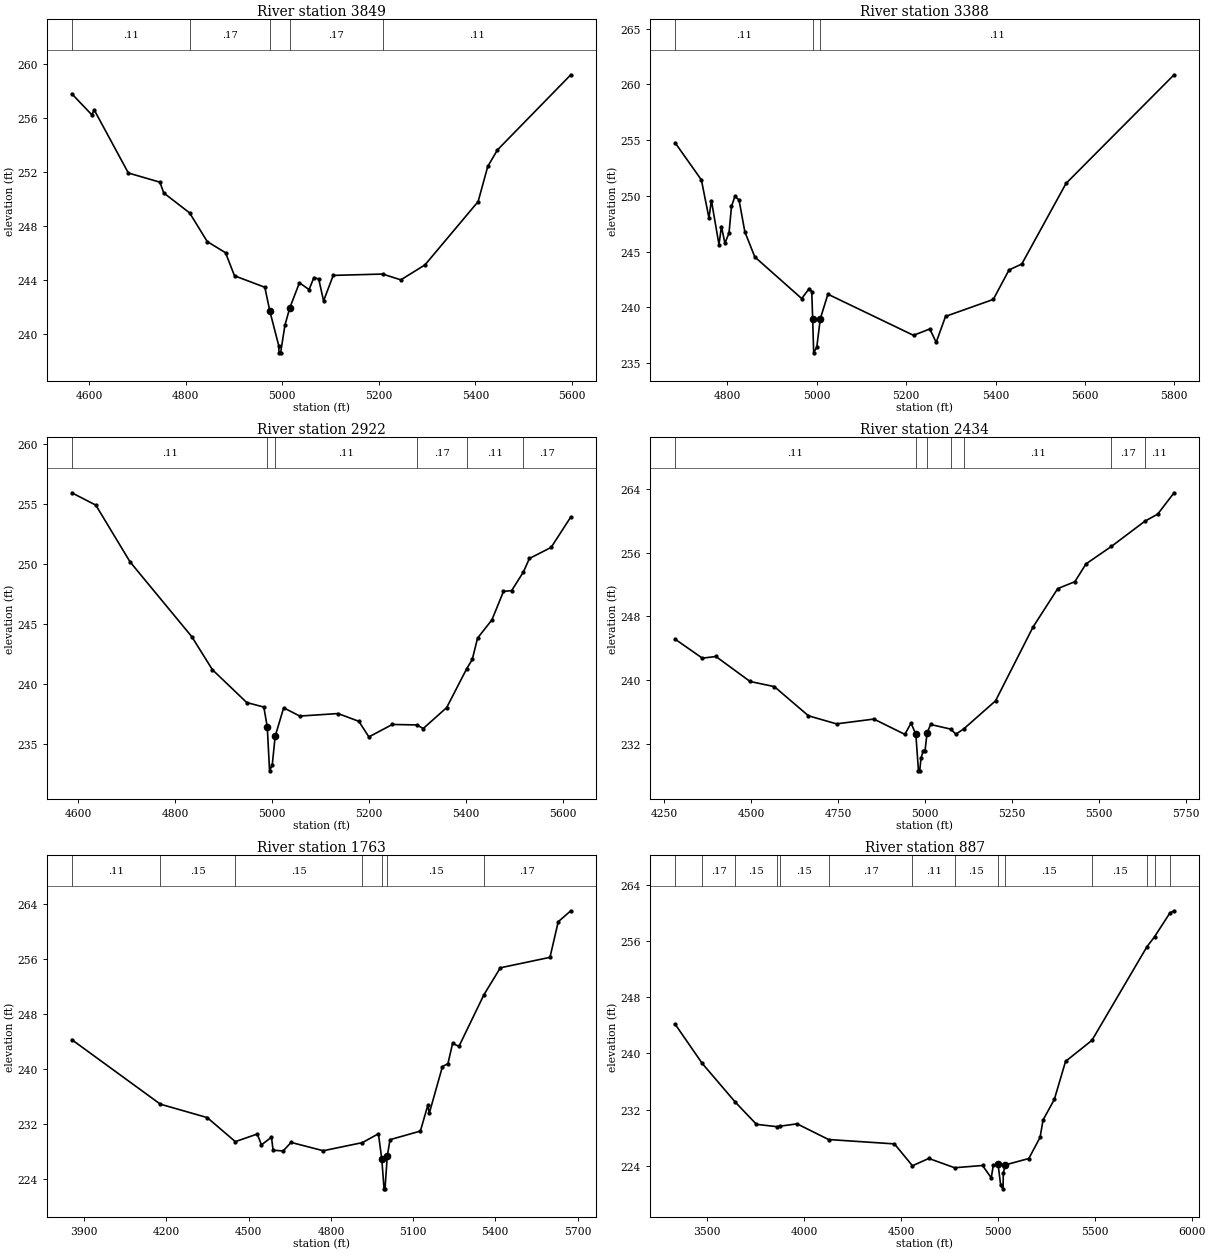
Type RM Length L Ch R = 1 ,3849    ,461,461,461
BEGIN DESCRIPTION:
CCLC 112 5.0
END DESCRIPTION:
XS GIS Cut Line= 3
       3724259.9     10138203.01      3724388.23     10137786.84
      3724391.83     10137189.16
#Sta/Elev= 30
  4564.5  257.77  4605.8  256.22    4611  256.57  4681.6   251.9  4746.9  251.22
  4754.9  250.42  4808.5  248.94  4844.9  246.82  4882.8  245.99  4901.4  244.28
  4964.2  243.43  4974.6  241.65  4993.2  239.07  4993.4  238.57  4996.9  238.57
  5005.8  240.62  5015.8   241.9  5035.8  243.76  5055.8  243.26  5065.8  244.15
  5075.8  244.04  5085.8  242.42  5105.8  244.31    5208  244.41  5245.8  243.98
  5295.8  245.09  5405.8  249.78  5425.8  252.39  5445.8  253.61  5597.7  259.18
#Mann= 5 ,-1 , 0
  4564.5     .11       0  4808.5     .17       0  4974.6     .09       0
  5015.8     .17       0    5208     .11       0
Bank Sta=4974.6,5015.8
XS Rating Curve= 0 ,0
Exp/Cntr=0.3,0.1

Type RM Length L Ch R = 1 ,3388    ,466,466,466
BEGIN DESCRIPTION:
CCLC 112 4.0
END DESCRIPTION:
XS GIS Cut Line= 3
      3724617.85     10138161.07      3724758.23     10137876.84
      3725267.85     10137261.08
#Sta/Elev= 30
    4683  254.77  4741.9  251.43  4758.8  248.02  4764.3  249.58  4781.2  245.63
  4786.8  247.25  4794.5  245.75  4803.7  246.67  4809.2  249.05  4816.8  249.95
  4826.1  249.63  4839.1  246.78  4861.4  244.52  4966.3  240.79  4983.2  241.69
  4988.8  241.42 4990.81238.9685  4993.1  235.92    5000  236.42 5007.92238.9784
  5024.9  241.18  5216.4  237.49  5252.9  238.06  5267.1  236.86  5288.1  239.19
  5394.9  240.71    5430  243.35  5458.7  243.89  5557.7  251.12  5799.3  260.86
#Mann= 3 , 0 , 0
    4683     .11       0 4990.81     .06       0 5007.92     .11       0
Bank Sta=4990.81,5007.92
XS Rating Curve= 0 ,0
Exp/Cntr=0.3,0.1

Type RM Length L Ch R = 1 ,2922    ,488,488,488
BEGIN DESCRIPTION:
CCLC 112 3.0
END DESCRIPTION:
XS GIS Cut Line= 3
      3724867.84     10138311.08      3725158.23     10138016.84
      3725267.85     10137411.08
#Sta/Elev= 30
  4586.6  255.93  4636.1   254.9  4706.8  250.16  4834.1  243.92  4876.5  241.17
  4947.3  238.43  4982.6  238.05  4989.7  236.39  4994.4  232.73    5000  233.23
  5005.9   235.6  5023.5  237.99  5056.7   237.3  5135.6  237.51  5178.6  236.86
  5199.2  235.56  5247.6   236.6  5298.1  236.56  5311.3  236.26  5359.7  238.01
  5400.8  241.24  5412.4  242.02  5423.3   243.8    5453  245.33  5476.8   247.7
  5493.7  247.77  5517.8  249.32  5530.3  250.45    5575  251.37  5615.6  253.91
#Mann= 6 ,-1 , 0
  4586.6     .11       0  4989.7     .06       0  5005.9     .11       0
  5298.1     .17       0  5400.8     .11       0  5517.8     .17       0
Bank Sta=4989.7,5005.9
XS Rating Curve= 0 ,0
Exp/Cntr=0.3,0.1

Type RM Length L Ch R = 1 ,2434    ,671,671,671
BEGIN DESCRIPTION:
CCLC 112 2.0
END DESCRIPTION:
XS GIS Cut Line= 3
      3725294.63     10138612.73      3725588.23     10137956.84
      3725711.27      10137251.7
#Sta/Elev= 30
  4281.4  245.15  4359.9  242.76  4398.8  242.97  4497.1  239.83  4566.7  239.19
  4664.9  235.52  4745.5  234.51  4852.9  235.11    4942  233.19  4959.7   234.6
  4973.5  233.22  4981.1  228.61  4984.6  228.61  4988.4  230.19  4994.9  231.16
    5000  231.16  5005.9  233.38    5016  234.43  5073.9  233.85  5088.6  233.21
  5111.9   233.9  5202.6   237.4  5310.4  246.67  5381.5   251.5  5430.6  252.36
  5462.7   254.6  5535.6  256.79  5631.9  259.96  5668.8  260.85  5715.8  263.53
#Mann= 7 ,-1 , 0
  4281.4     .11       0  4973.5     .06       0  5005.9     .11       0
  5073.9     .15       0  5111.9     .11       0  5535.6     .17       0
  5631.9     .11       0
Bank Sta=4973.5,5005.9
XS Rating Curve= 0 ,0
Exp/Cntr=0.3,0.1

Type RM Length L Ch R = 1 ,1763    ,876,876,876
BEGIN DESCRIPTION:
Mapping XS 768f65be
END DESCRIPTION:
XS GIS Cut Line= 3
      3725377.98     10138703.02       3726183.5     10138203.04
      3726280.66     10137335.54
#Sta/Elev= 30
  3854.5  244.29  4177.7  234.91  4348.7  232.96  4451.3  229.46  4531.2  230.57
  4546.6  228.99  4583.2  230.11  4589.1  228.21  4625.7  228.11  4654.7  229.35
  4772.2  228.14  4914.9  229.32  4973.5  230.61  4985.7  226.92    4994   222.6
  4997.5   222.6  5005.8  227.38  5015.9  229.75  5126.6     231  5153.9  234.78
  5158.9  233.56  5207.1  240.38  5227.2  240.81  5244.1  243.74  5267.4  243.32
  5358.5  250.82  5418.4  254.74  5599.5  256.26  5629.7  261.44  5675.5  263.03
#Mann= 7 ,-1 , 0
  3854.5     .11       0  4177.7     .15       0  4451.3     .15       0
  4914.9     .15       0  4985.7     .06       0  5005.8     .15       0
  5358.5     .17       0
Bank Sta=4985.7,5005.8
XS Rating Curve= 0 ,0
Exp/Cntr=0.3,0.1

Type RM Length L Ch R = 1 ,887     ,489,489,489
BEGIN DESCRIPTION:
CCLC 112 1.0
END DESCRIPTION:
XS GIS Cut Line= 3
      3725516.85     10138848.87      3727009.89      10138133.6
      3726530.72     10137348.86
#Sta/Elev= 30
  3334.2  244.17  3473.8   238.6  3644.9  233.08  3754.2  229.92  3858.8  229.59
  3876.9  229.66  3963.7  229.99  4126.5  227.76  4466.3  227.14  4559.1  224.03
  4643.7  225.07  4776.8  223.75  4920.9  224.07  4965.9  222.31  4976.4  224.11
  5000.9  224.26  5014.4  221.28 5026.54  220.75  5028.1  222.94  5037.7  224.15
  5159.7  225.06  5217.7  228.06  5233.2  230.54  5291.3  233.46  5349.3  238.87
  5485.4  241.86  5769.8  255.19  5808.6  256.59  5887.8  259.97  5909.2  260.28
#Mann= 14 ,-1 , 0
  3334.2     .11       0  3473.8     .17       0  3644.9     .15       0
  3858.8     .17       0  3876.9     .15       0  4126.5     .17       0
  4559.1     .11       0  4776.8     .15       0  5000.9     .06       0
  5037.7     .15       0  5485.4     .15       0  5769.8     .11       0
  5808.6     .17       0  5887.8     .11       0
Bank Sta=5000.9,5037.7
XS Rating Curve= 0 ,0
Exp/Cntr=0.3,0.1

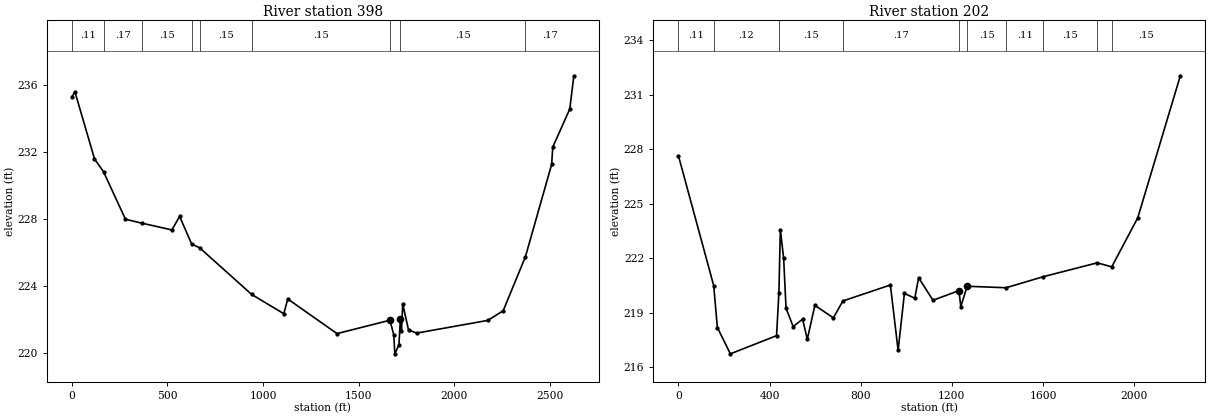
Type RM Length L Ch R = 1 ,398     ,196,196,196
BEGIN DESCRIPTION:
CCLC 112 1.0
END DESCRIPTION:
XS GIS Cut Line= 3
      3725770.09     10138881.29       3727400.7     10138370.14
      3726921.53     10137585.42
#Sta/Elev= 30
       0  235.29    15.4   235.6     118  231.58   165.3  230.81   280.1  227.97
   364.4  227.74   522.9  227.33   563.6  228.14   626.4  226.49   668.4  226.26
   940.8  223.47  1108.5  222.32  1129.5   223.2  1387.2  221.13  1663.9  221.93
  1684.3  221.06  1689.6  219.92  1711.2  220.45  1718.8  221.99  1724.6   221.3
  1731.2  222.89  1761.4  221.35    1804  221.16  2176.4  221.92  2256.9   222.5
    2373  225.72  2510.5  231.25  2516.4  232.29  2605.3  234.56  2626.7  236.55
#Mann= 9 ,-1 , 0
       0     .11       0   165.3     .17       0   364.4     .15       0
   626.4     .17       0   668.4     .15       0   940.8     .15       0
  1663.9     .06       0  1718.8     .15       0    2373     .17       0
Bank Sta=1663.9,1718.8
XS Rating Curve= 0 ,0
Exp/Cntr=0.3,0.1

Type RM Length L Ch R = 1 ,202     ,0,0,0
BEGIN DESCRIPTION:
CCLC 112 1.0
END DESCRIPTION:
XS GIS Cut Line= 3
      3728742.31     10138768.16      3727676.15     10138466.48
       3727000.8     10137602.58
#Sta/Elev= 30
       0  227.65     155  220.49   170.9  218.19   228.1  216.74   430.7  217.74
   441.1  220.11   447.4  223.57   461.9     222   472.3  219.26   503.5  218.24
     545  218.65   565.8  217.54   598.8  219.41   680.2  218.72   721.7  219.65
   930.3  220.53   964.3  216.93   991.9  220.07  1037.4   219.8  1054.3  220.93
  1117.3  219.69  1231.3  220.22  1239.4  219.34  1267.2  220.46  1438.3  220.38
    1602  220.99    1838  221.75  1901.9  221.53  2016.1  224.23  2202.9  232.05
#Mann= 10 ,-1 , 0
       0     .11       0     155     .12       0   441.1     .15       0
   721.7     .17       0  1231.3     .06       0  1267.2     .15       0
  1438.3     .11       0    1602     .15       0    1838     .12       0
  1901.9     .15       0
Bank Sta=1231.3,1267.2
XS Rating Curve= 0 ,0
Exp/Cntr=0.3,0.1

Chan Stop Cuts=-1
Use User Specified Reach Order=0
Composite Channel Slope=5