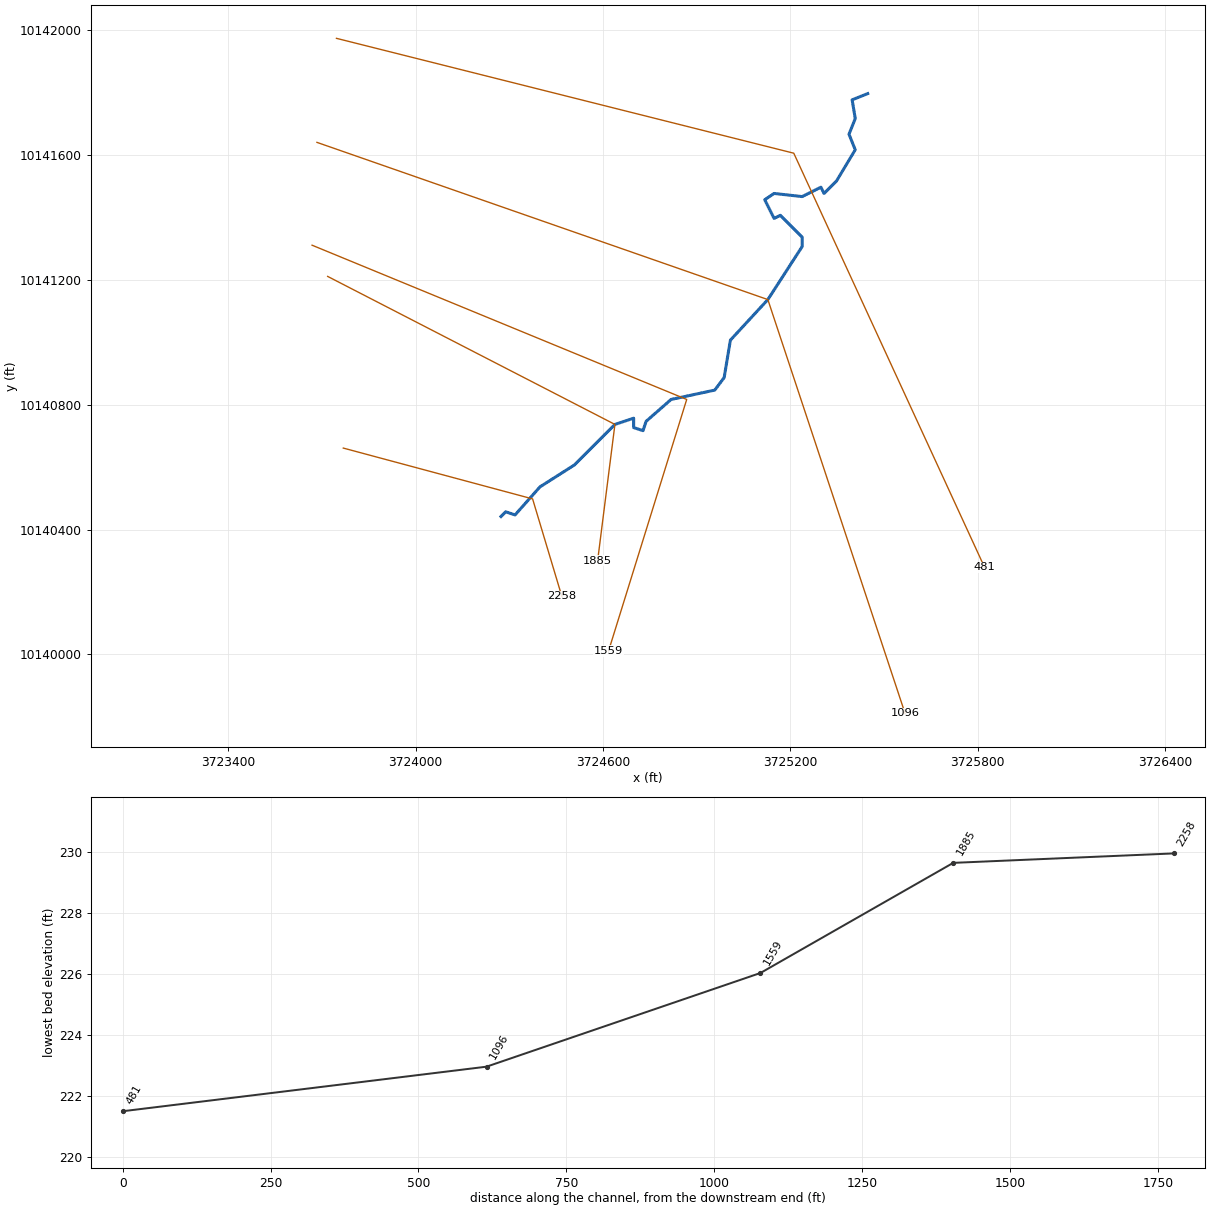
--- CCLC 113.prj (project) ---

Proj Title=CCLC 113 Base Level Engineering
Current Plan=p01
Default Exp/Contr=0.3,0.1
English Units
Geom File=g01
Flow File=f01
Flow File=f02
Plan File=p01
Y Axis Title=Elevation
X Axis Title(PF)=Main Channel Distance
X Axis Title(XS)=Station
BEGIN DESCRIPTION:
CCLC 113
END DESCRIPTION:
DSS Export Rating Curves= 0
DSS Export Rating Curve Sorted= 0
DSS Export Volume Flow Curves= 0
DXF OffsetX= 0
DXF OffsetY= 0
DXF ScaleX= 1
DXF ScaleY= 10

--- CCLC 113.p01 (plan) ---

Plan Title=Multiple Run
Short Identifier=Multiple
Geom File=g01
Flow File=f01
Subcritical Flow
K Sum by GR= 0
Std Step Tol= 0.01
Critical Tol= 0.01
Num of Std Step Trials= 20
Max Error Tol= 0.3
Flow Tol Ratio= 0.001
Split Flow NTrial= 30
Split Flow Tol= 0.02
Split Flow Ratio= 0.02
Log Output Level= 0
Friction Slope Method= 1
Unsteady Friction Slope Method= 2
Unsteady Bridges Friction Slope Method= 1
Parabolic Critical Depth
Global Vel Dist=  1 , 1 , 1
Global Log Level= 0
CheckData=True
Encroach Param= -1, 0, 0, 0
BEGIN DESCRIPTION:
Multiple Run
END DESCRIPTION:

--- CCLC 113.f01 (steady flow) ---

Flow Title=Multiple
Program Version=4.10
Number of Profiles= 7
Profile Names=10-year,25-year,50-year,1pct_min,100-year,1pct_plu,500-year
River Rch & RM=CCLC 113,Reach-1         ,2258
     445     592     790     347    1049    3168    1913
Boundary for River Rch & Prof#=CCLC 113,Reach-1         , 1
Up Type= 0
Dn Type= 3
Dn Slope=0.005
Boundary for River Rch & Prof#=CCLC 113,Reach-1         , 2
Up Type= 0
Dn Type= 3
Dn Slope=0.005
Boundary for River Rch & Prof#=CCLC 113,Reach-1         , 3
Up Type= 0
Dn Type= 3
Dn Slope=0.005
Boundary for River Rch & Prof#=CCLC 113,Reach-1         , 4
Up Type= 0
Dn Type= 3
Dn Slope=0.005
Boundary for River Rch & Prof#=CCLC 113,Reach-1         , 5
Up Type= 0
Dn Type= 3
Dn Slope=0.005
Boundary for River Rch & Prof#=CCLC 113,Reach-1         , 6
Up Type= 0
Dn Type= 3
Dn Slope=0.005
Boundary for River Rch & Prof#=CCLC 113,Reach-1         , 7
Up Type= 0
Dn Type= 3
Dn Slope=0.005
DSS Import GetInterval= 0
DSS Import GetPeak= 0
DSS Import FillOption= 0

--- CCLC 113.f02 (steady flow) ---

Flow Title=Orig_BLE_Flows
Program Version=4.10
Number of Profiles= 7
Profile Names=10-year,25-year,50-year,1pct_min,100-year,1pct_plu,500-year
River Rch & RM=CCLC 113,Reach-1         ,2258
     445     580     687     267     807    2437    1112
Boundary for River Rch & Prof#=CCLC 113,Reach-1         , 1
Up Type= 0
Dn Type= 3
Dn Slope=0.005
Boundary for River Rch & Prof#=CCLC 113,Reach-1         , 2
Up Type= 0
Dn Type= 3
Dn Slope=0.005
Boundary for River Rch & Prof#=CCLC 113,Reach-1         , 3
Up Type= 0
Dn Type= 3
Dn Slope=0.005
Boundary for River Rch & Prof#=CCLC 113,Reach-1         , 4
Up Type= 0
Dn Type= 3
Dn Slope=0.005
Boundary for River Rch & Prof#=CCLC 113,Reach-1         , 5
Up Type= 0
Dn Type= 3
Dn Slope=0.005
Boundary for River Rch & Prof#=CCLC 113,Reach-1         , 6
Up Type= 0
Dn Type= 3
Dn Slope=0.005
Boundary for River Rch & Prof#=CCLC 113,Reach-1         , 7
Up Type= 0
Dn Type= 3
Dn Slope=0.005
DSS Import GetInterval= 0
DSS Import GetPeak= 0
DSS Import FillOption= 0

--- CCLC 113.g01 (geometry) ---

Geom Title=Existing Conditions
Program Version=4.10

River Reach=CCLC 113        ,Reach-1
Reach XY= 30
      3724273.23     10140441.84      3724288.23     10140456.84
      3724318.23     10140446.84      3724398.23     10140536.84
      3724508.23     10140606.84      3724638.23     10140736.84
      3724698.23     10140756.84      3724698.23     10140726.84
      3724728.23     10140716.84      3724738.23     10140746.84
      3724818.23     10140816.84      3724958.23     10140846.84
      3724988.23     10140886.84      3725008.23     10141006.84
      3725128.23     10141136.84      3725238.23     10141306.84
      3725238.23     10141336.84      3725168.23     10141406.84
      3725148.23     10141396.84      3725118.23     10141456.84
      3725148.23     10141476.84      3725238.23     10141466.84
      3725298.23     10141496.84      3725308.23     10141476.84
      3725348.23     10141516.84      3725408.23     10141616.84
      3725388.23     10141666.84      3725408.23     10141716.84
      3725398.23     10141776.84      3725448.23     10141796.84

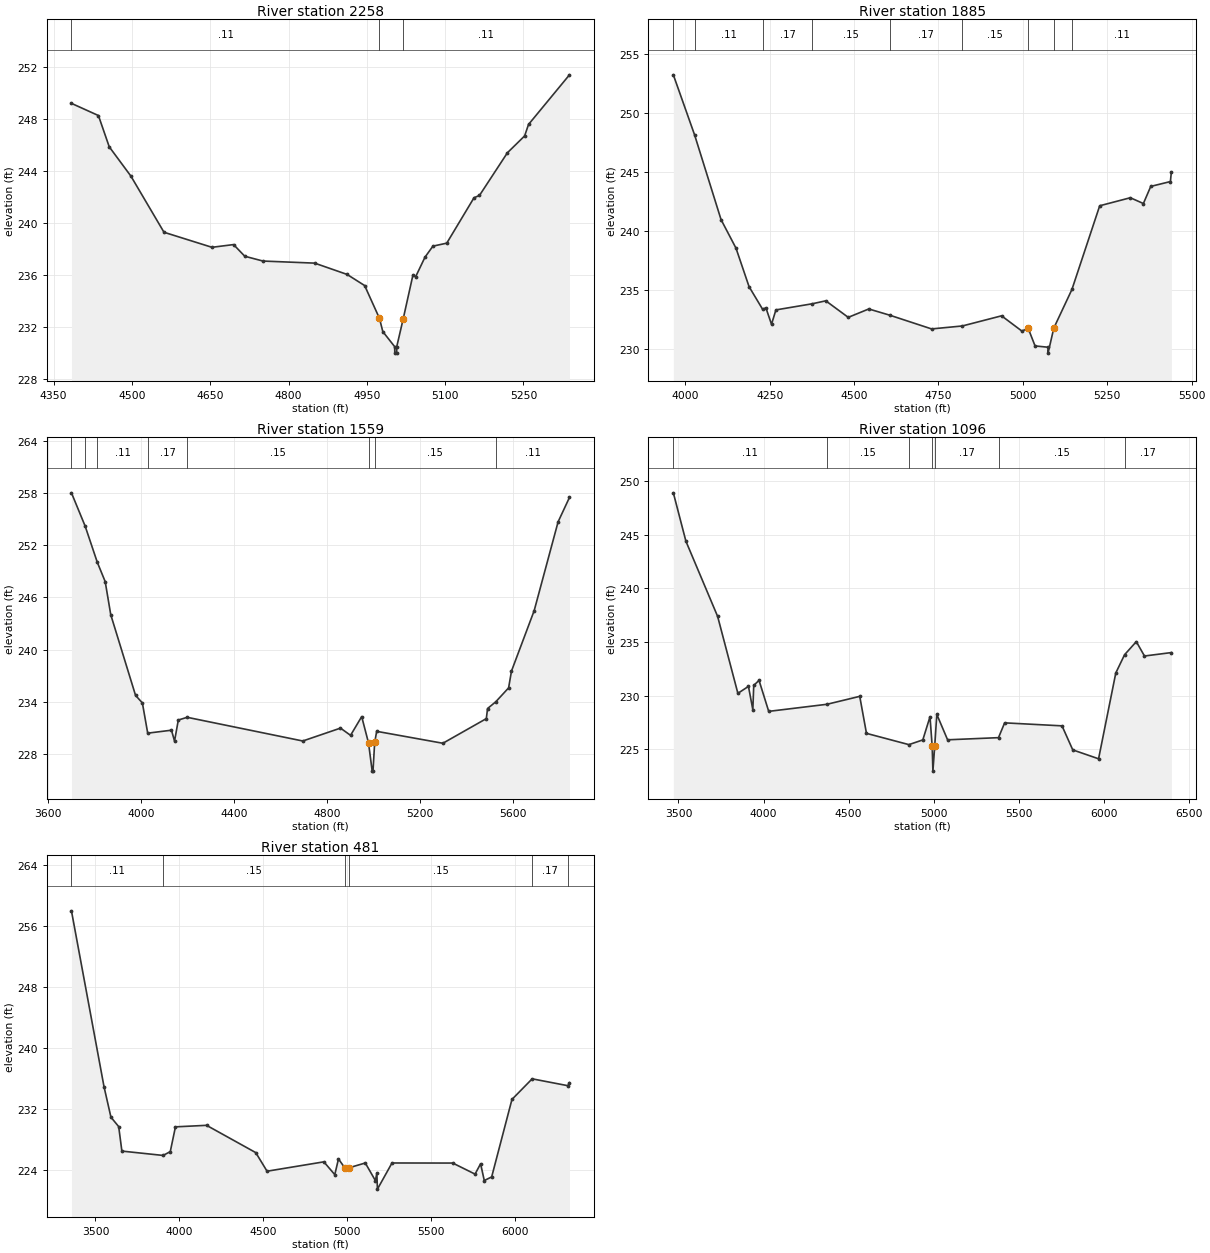
Type RM Length L Ch R = 1 ,2258    ,373,373,373
BEGIN DESCRIPTION:
CCLC 113 5.0
END DESCRIPTION:
XS GIS Cut Line= 3
      3723767.89     10140661.06      3724374.47     10140498.18
      3724468.16      10140185.9
#Sta/Elev= 30
  4384.1  249.22  4435.8  248.28  4456.5  245.87    4498  243.61  4561.4  239.28
  4653.3  238.12  4694.7  238.33  4716.2  237.43    4751  237.06    4850   236.9
  4912.1  236.03  4945.8  235.17  4974.2  232.64  4980.6  231.62  5003.3  230.46
  5003.6  229.96  5007.1  229.96  5007.3  230.46  5019.6  232.59  5038.3  235.98
  5043.5  235.85  5061.4  237.36  5076.6  238.21  5103.1  238.44  5155.3  241.94
  5165.8  242.12  5219.3  245.41  5252.3  246.71  5259.7  247.59  5338.2  251.42
#Mann= 3 , 0 , 0
  4384.1     .11       0  4974.2     .06       0  5019.6     .11       0
Bank Sta=4974.2,5019.6
XS Rating Curve= 0 ,0
Exp/Cntr=0.3,0.1

Type RM Length L Ch R = 1 ,1885    ,326,326,326
BEGIN DESCRIPTION:
CCLC 113 4.0
END DESCRIPTION:
XS GIS Cut Line= 3
      3723717.82     10141211.09      3724638.23     10140736.84
      3724582.83     10140300.45
#Sta/Elev= 30
  3964.6  253.22  4027.7  248.12  4105.9  240.96  4150.2  238.54  4188.9  235.28
  4228.9  233.37  4238.9  233.48  4255.4  232.09  4268.4  233.31  4376.1  233.83
  4416.2  234.08  4482.7  232.68  4543.6  233.39    4606  232.86  4729.6   231.7
  4820.6  231.95  4936.9  232.81    4997  231.52  5015.9  231.74  5036.1  230.26
  5074.4  230.15  5074.6  229.65 5091.64231.7707  5145.3  235.04  5227.6  242.13
  5318.3  242.81    5357  242.32  5378.8  243.77    5437  244.18  5439.9     245
#Mann= 9 ,-1 , 0
  3964.6     .17       0  4027.7     .11       0  4228.9     .17       0
  4376.1     .15       0    4606     .17       0  4820.6     .15       0
  5015.9     .09       0 5091.64     .15       0  5145.3     .11       0
Bank Sta=5015.9,5091.64
XS Rating Curve= 0 ,0
Exp/Cntr=0.3,0.1

Type RM Length L Ch R = 1 ,1559    ,463,463,463
BEGIN DESCRIPTION:
CCLC 113 3.0
END DESCRIPTION:
XS GIS Cut Line= 3
      3723667.89     10141311.06      3724868.23     10140816.84
      3724617.84     10140011.05
#Sta/Elev= 30
  3701.9     258  3760.8  254.18    3813  250.03  3847.1   247.8    3871     244
  3977.6  234.74    4007  233.87  4029.9   230.4  4132.1  230.74  4145.3  229.49
  4161.5  231.91  4199.8  232.22  4696.8   229.5    4859  230.98  4902.3  230.15
  4950.2   232.3  4979.6  229.27  4995.3  226.04  4998.8  226.04    5006  229.33
  5014.7  230.61  5299.3  229.24  5486.2  232.07  5491.5  233.23  5526.7     234
    5582   235.6  5594.4  237.53    5692  244.47  5794.9  254.67  5843.8  257.47
#Mann= 8 ,-1 , 0
  3701.9     .11       0  3760.8     .17       0    3813     .11       0
  4029.9     .17       0  4199.8     .15       0  4979.6     .09       0
    5006     .15       0  5526.7     .11       0
Bank Sta=4979.6,5006
XS Rating Curve= 0 ,0
Exp/Cntr=0.3,0.1

Type RM Length L Ch R = 1 ,1096    ,615,615,615
BEGIN DESCRIPTION:
CCLC 113 2.0
END DESCRIPTION:
XS GIS Cut Line= 3
      3723683.52     10141640.54      3725128.23     10141136.84
      3725567.86     10139811.03
#Sta/Elev= 30
    3470  248.91  3543.9   244.4  3730.3  237.39  3849.3  230.22  3911.5  230.87
  3937.2  228.69  3942.5  230.96  3973.6  231.43  4030.5  228.54  4372.8   229.2
  4565.4  229.94    4605  226.49  4854.3  225.44  4936.1  225.88  4978.4  228.04
  4991.1225.2952  4995.4  222.97  5006.1  225.31  5018.3  228.26  5081.7  225.89
  5380.9  226.09    5417  227.47  5754.1  227.19  5817.3  224.95    5969  224.12
  6070.2  232.12  6121.8  233.82  6190.8  235.04  6238.7   233.7  6396.8  234.02
#Mann= 7 ,-1 , 0
    3470     .11       0  4372.8     .15       0  4854.3     .17       0
  4991.1     .09       0  5006.1     .17       0  5380.9     .15       0
  6121.8     .17       0
Bank Sta=4991.1,5006.1
XS Rating Curve= 0 ,0
Exp/Cntr=0.3,0.1

Type RM Length L Ch R = 1 ,481     ,0,0,0
BEGIN DESCRIPTION:
CCLC 113 1.0
END DESCRIPTION:
XS GIS Cut Line= 3
        3723746.     10141973.87      3725211.28     10141605.82
      3725822.39     10140279.42
#Sta/Elev= 30
  3356.6  258.02    3551  234.94  3592.2  230.95  3638.5  229.71  3657.5   226.5
  3903.3  225.93  3946.2  226.43  3977.1  229.68  4162.7  229.88  4456.2   226.3
  4523.6  223.86  4862.5  225.09  4927.7  223.41  4949.7  225.47  4989.4  224.24
  5012.4  224.31  5109.7  224.94  5169.9  222.63  5178.6   223.6  5182.1  221.51
    5269  224.94  5631.4  224.93  5764.5  223.48  5797.5  224.84  5819.5  222.64
  5863.6  223.11  5984.7  233.28  6105.3  235.98    6318  235.08  6327.8  235.47
#Mann= 6 ,-1 , 0
  3356.6     .11       0  3903.3     .15       0  4989.4     .09       0
  5012.4     .15       0  6105.3     .17       0    6318     .11       0
Bank Sta=4989.4,5012.4
XS Rating Curve= 0 ,0
Exp/Cntr=0.3,0.1

Chan Stop Cuts=-1
Use User Specified Reach Order=0
Composite Channel Slope=5