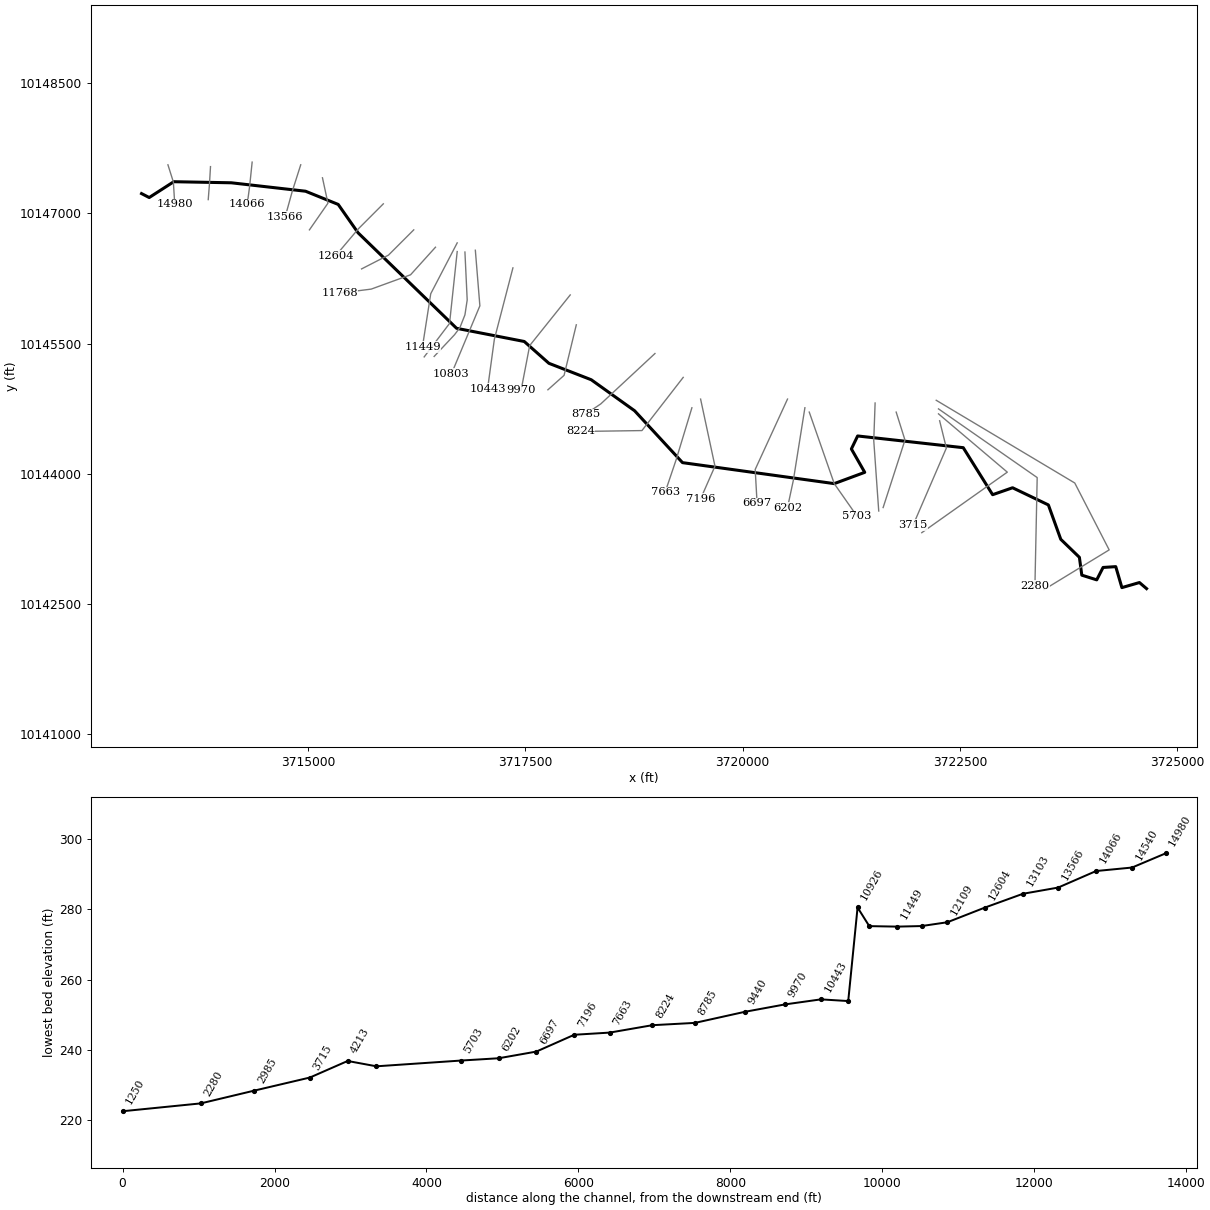
--- CCLC 114.prj (project) ---

Proj Title=CCLC 114 Base Level Engineering
Current Plan=p01
Default Exp/Contr=0.3,0.1
English Units
Geom File=g01
Flow File=f01
Flow File=f02
Plan File=p01
Y Axis Title=Elevation
X Axis Title(PF)=Main Channel Distance
X Axis Title(XS)=Station
BEGIN DESCRIPTION:
CCLC 114
END DESCRIPTION:
DSS Export Rating Curves= 0
DSS Export Rating Curve Sorted= 0
DSS Export Volume Flow Curves= 0
DXF OffsetX= 0
DXF OffsetY= 0
DXF ScaleX= 1
DXF ScaleY= 10

--- CCLC 114.p01 (plan) ---

Plan Title=Multiple Run
Short Identifier=Multiple
Geom File=g01
Flow File=f01
Subcritical Flow
K Sum by GR= 0
Std Step Tol= 0.01
Critical Tol= 0.01
Num of Std Step Trials= 20
Max Error Tol= 0.3
Flow Tol Ratio= 0.001
Split Flow NTrial= 30
Split Flow Tol= 0.02
Split Flow Ratio= 0.02
Log Output Level= 0
Friction Slope Method= 1
Unsteady Friction Slope Method= 2
Unsteady Bridges Friction Slope Method= 1
Parabolic Critical Depth
Global Vel Dist=  1 , 1 , 1
Global Log Level= 0
CheckData=True
Encroach Param= -1, 0, 0, 0
BEGIN DESCRIPTION:
Multiple Run
END DESCRIPTION:

--- CCLC 114.f01 (steady flow) ---

Flow Title=Multiple
Program Version=4.10
Number of Profiles= 7
Profile Names=10-year,25-year,50-year,1pct_min,100-year,1pct_plu,500-year
River Rch & RM=CCLC 114,Reach-1         ,14980
     553     751    1017     453    1369    4134    2568
River Rch & RM=CCLC 114,Reach-1         ,11080
     995    1398    1938     883    2668    8057    5231
River Rch & RM=CCLC 114,Reach-1         ,7663
    1094    1521    2090     942    2846    8595    5463
Boundary for River Rch & Prof#=CCLC 114,Reach-1         , 1
Up Type= 0
Dn Type= 3
Dn Slope=0.005
Boundary for River Rch & Prof#=CCLC 114,Reach-1         , 2
Up Type= 0
Dn Type= 3
Dn Slope=0.005
Boundary for River Rch & Prof#=CCLC 114,Reach-1         , 3
Up Type= 0
Dn Type= 3
Dn Slope=0.005
Boundary for River Rch & Prof#=CCLC 114,Reach-1         , 4
Up Type= 0
Dn Type= 3
Dn Slope=0.005
Boundary for River Rch & Prof#=CCLC 114,Reach-1         , 5
Up Type= 0
Dn Type= 3
Dn Slope=0.005
Boundary for River Rch & Prof#=CCLC 114,Reach-1         , 6
Up Type= 0
Dn Type= 3
Dn Slope=0.005
Boundary for River Rch & Prof#=CCLC 114,Reach-1         , 7
Up Type= 0
Dn Type= 3
Dn Slope=0.005
DSS Import GetInterval= 0
DSS Import GetPeak= 0
DSS Import FillOption= 0

--- CCLC 114.f02 (steady flow) ---

Flow Title=Orig_BLE_Flows
Program Version=4.10
Number of Profiles= 7
Profile Names=10-year,25-year,50-year,1pct_min,100-year,1pct_plu,500-year
River Rch & RM=CCLC 114,Reach-1         ,14980
     553     736     884     349    1053    3180    1493
River Rch & RM=CCLC 114,Reach-1         ,11080
     995    1371    1685     680    2052    6198    3041
River Rch & RM=CCLC 114,Reach-1         ,7663
    1094    1491    1817     725    2189    6610    3176
Boundary for River Rch & Prof#=CCLC 114,Reach-1         , 1
Up Type= 0
Dn Type= 3
Dn Slope=0.005
Boundary for River Rch & Prof#=CCLC 114,Reach-1         , 2
Up Type= 0
Dn Type= 3
Dn Slope=0.005
Boundary for River Rch & Prof#=CCLC 114,Reach-1         , 3
Up Type= 0
Dn Type= 3
Dn Slope=0.005
Boundary for River Rch & Prof#=CCLC 114,Reach-1         , 4
Up Type= 0
Dn Type= 3
Dn Slope=0.005
Boundary for River Rch & Prof#=CCLC 114,Reach-1         , 5
Up Type= 0
Dn Type= 3
Dn Slope=0.005
Boundary for River Rch & Prof#=CCLC 114,Reach-1         , 6
Up Type= 0
Dn Type= 3
Dn Slope=0.005
Boundary for River Rch & Prof#=CCLC 114,Reach-1         , 7
Up Type= 0
Dn Type= 3
Dn Slope=0.005
DSS Import GetInterval= 0
DSS Import GetPeak= 0
DSS Import FillOption= 0

--- CCLC 114.g01 (geometry) ---

Geom Title=Existing Conditions
Program Version=4.10

River Reach=CCLC 114        ,Reach-1
Reach XY= 30
      3713086.42     10147229.23      3713174.58     10147183.63
      3713457.31     10147366.04      3714119.24     10147353.55
      3714973.13     10147256.35        3715349.      10147104.1
       3715577.4     10146777.11      3716710.63     10145676.75
      3717489.26     10145524.78      3717772.76     10145273.27
      3718259.86     10145083.79      3718758.51     10144726.64
      3719309.89     10144128.58      3721055.42      10143886.8
      3721406.08     10144016.84      3721252.56      10144286.4
      3721324.65     10144436.02      3722539.46     10144300.98
      3722877.42     10143759.21      3723107.03     10143839.19
      3723518.94     10143641.23      3723661.33     10143245.26
      3723875.67     10143037.56      3723903.44       10142832.
      3724075.06      10142777.8      3724147.99     10142920.68
      3724293.95      10142930.1      3724364.58     10142688.41
       3724566.3     10142746.89      3724648.23     10142676.84

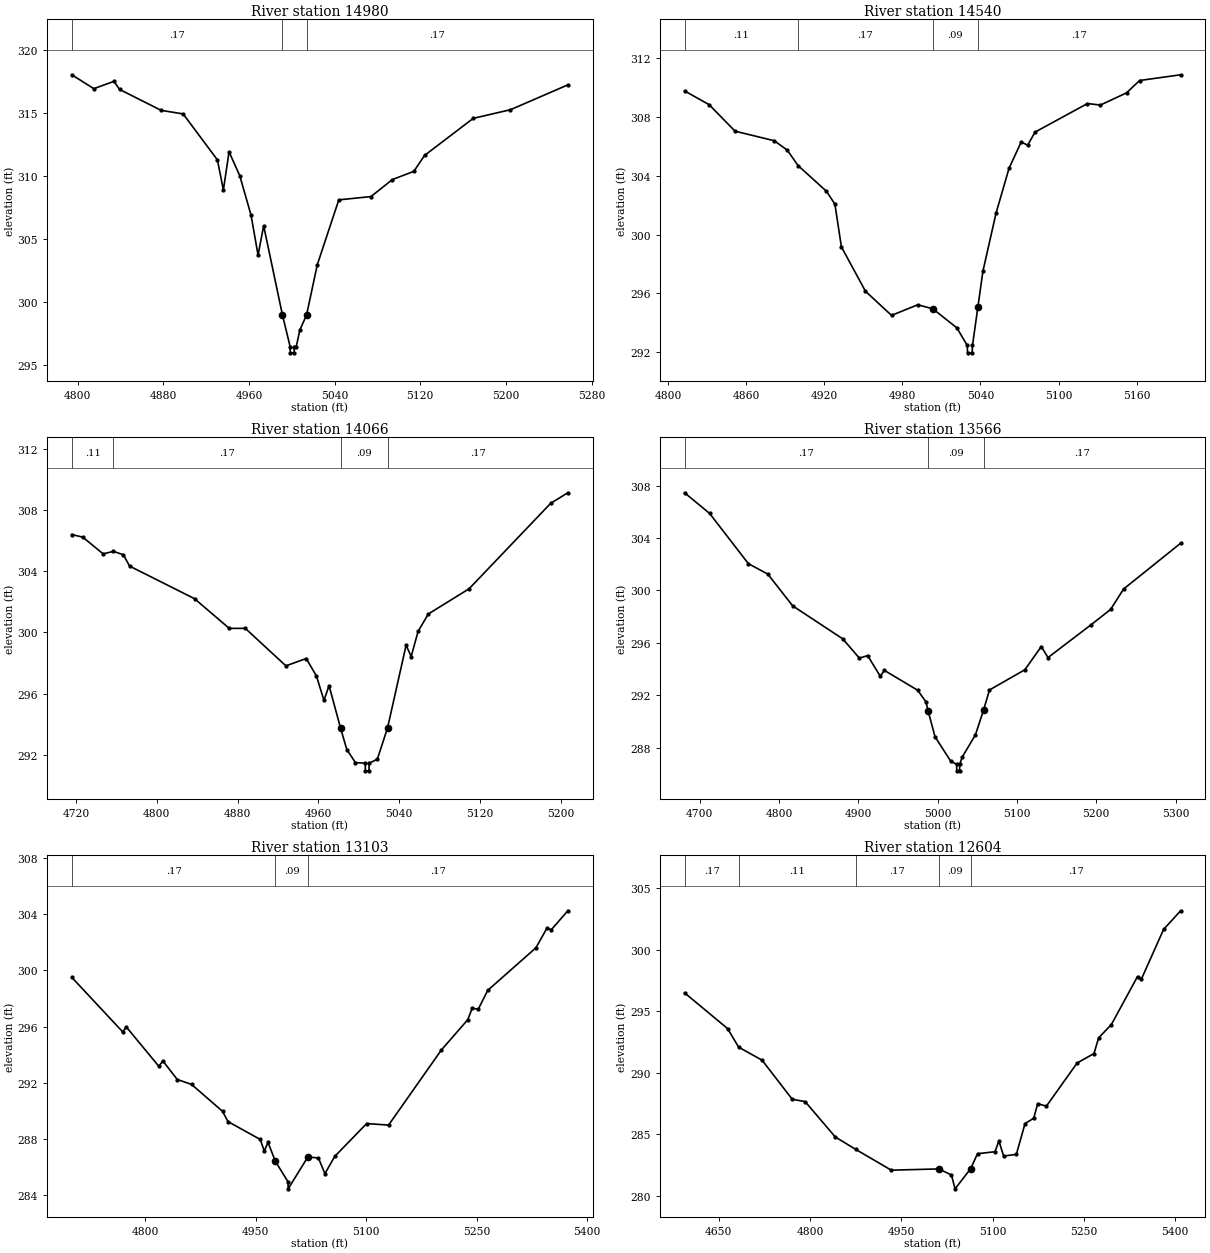
Type RM Length L Ch R = 1 ,14980   ,440,440,440
BEGIN DESCRIPTION:
CCLC 114 25.0
END DESCRIPTION:
XS GIS Cut Line= 3
      3713390.08     10147560.73       3713452.6     10147362.76
      3713468.22     10147107.54
#Sta/Elev= 30
  4794.5  318.02  4815.1  316.92  4833.9   317.5  4839.1  316.86    4878   315.2
  4898.5  314.92  4930.5  311.28  4936.1  308.89  4941.4  311.92  4951.4  310.02
  4961.9  306.91  4968.5  303.73  4973.7  306.06 4991.21299.0116  4998.4  296.49
  4998.6  295.99  5002.1  295.99  5002.4  296.49  5004.2  296.49  5007.5   297.8
  5013.8  298.99  5023.8  302.97  5043.9  308.11  5073.9  308.37    5094  309.72
    5114  310.37    5124  311.63  5169.5  314.57  5204.2  315.25  5257.8  317.22
#Mann= 3 , 0 , 0
  4794.5     .17       0 4991.21     .09       0  5013.8     .17       0
Bank Sta=4991.21,5013.8
XS Rating Curve= 0 ,0
Exp/Cntr=0.3,0.1

Type RM Length L Ch R = 1 ,14540   ,474,474,474
BEGIN DESCRIPTION:
CCLC 114 24.0
END DESCRIPTION:
XS GIS Cut Line= 3
      3713879.68     10147539.84      3713868.75     10147352.86
      3713853.64     10147159.65
#Sta/Elev= 30
  4812.7  309.79  4831.5  308.86  4851.5  307.05  4881.6   306.4  4891.6  305.76
  4899.9  304.71  4921.7  302.96  4928.2  302.08  4933.2  299.17  4951.7  296.15
  4971.7  294.51  4991.8  295.23  5003.4  294.96  5021.9  293.66  5029.9  292.46
  5030.1  291.96  5033.6  291.96  5033.9  292.46 5038.07295.0923  5041.9  297.51
    5052  301.47    5062  304.53  5071.3  306.31  5076.3   306.1    5082  306.99
  5122.2  308.93  5132.2  308.83  5152.3  309.66  5162.3   310.5  5193.8  310.89
#Mann= 4 ,-1 , 0
  4812.7     .11       0  4899.9     .17       0  5003.4     .09       0
 5038.07     .17       0
Bank Sta=5003.4,5038.07
XS Rating Curve= 0 ,0
Exp/Cntr=0.3,0.1

Type RM Length L Ch R = 1 ,14066   ,500,500,500
BEGIN DESCRIPTION:
CCLC 114 23.0
END DESCRIPTION:
XS GIS Cut Line= 3
      3714358.85     10147591.94      3714329.55     10147309.25
      3714301.81     10147104.22
#Sta/Elev= 30
  4715.8   306.4  4726.7  306.23  4746.8  305.14  4757.1   305.3  4766.9  305.08
    4773  304.34  4837.3  302.21  4871.7  300.27  4887.6  300.27  4927.8  297.82
  4947.9   298.3    4958  297.16  4965.5  295.56  4970.5  296.53 4981.95293.7399
  4988.1  292.35  4996.6   291.5  5006.3  291.46  5006.5  290.96    5010  290.96
  5010.3  291.46  5018.3  291.72  5028.4  293.76  5046.8  299.17  5051.8  298.43
  5058.7  300.08  5068.8  301.21  5109.2  302.86  5189.9  308.44  5206.9  309.13
#Mann= 4 ,-1 , 0
  4715.8     .11       0  4757.1     .17       0 4981.95     .09       0
  5028.4     .17       0
Bank Sta=4981.95,5028.4
XS Rating Curve= 0 ,0
Exp/Cntr=0.3,0.1

Type RM Length L Ch R = 1 ,13566   ,463,463,463
BEGIN DESCRIPTION:
CCLC 114 22.0
END DESCRIPTION:
XS GIS Cut Line= 3
      3714917.84     10147561.04      3714820.88     10147257.03
      3714739.07     10146961.75
#Sta/Elev= 30
  4680.9  307.45  4712.4  305.88  4761.4  302.04  4785.8  301.25  4817.3  298.82
  4880.3  296.31  4901.3  294.84  4911.8  295.03  4927.6  293.46  4932.9   293.9
  4974.8  292.39  4985.3   291.5 4987.96 290.825  4996.7  288.84  5016.6  286.97
  5023.9  286.74  5024.2  286.24  5027.7  286.24  5027.9  286.74  5031.1   287.3
  5047.7  288.99  5058.1  290.91  5065.4  292.41    5110  293.95  5130.7  295.72
  5139.2  294.88    5193  297.36  5218.1  298.55  5234.5  300.11  5306.4   303.6
#Mann= 3 , 0 , 0
  4680.9     .17       0 4987.96     .09       0  5058.1     .17       0
Bank Sta=4987.96,5058.1
XS Rating Curve= 0 ,0
Exp/Cntr=0.3,0.1

Type RM Length L Ch R = 1 ,13103   ,499,499,499
BEGIN DESCRIPTION:
CCLC 114 21.0
END DESCRIPTION:
XS GIS Cut Line= 3
      3715167.84     10147411.12      3715230.76      10147118.4
      3715017.84     10146811.05
#Sta/Elev= 30
  4700.6   299.5  4769.6  295.63  4774.7  295.97  4818.9  293.17  4824.1  293.57
  4843.8  292.24  4863.2  291.89  4905.2  289.98  4912.6  289.25  4956.4  287.98
  4961.9  287.15    4967  287.77  4976.8  286.44  4994.1  284.97  4994.3  284.47
  5021.1  286.74  5035.4  286.66  5044.2  285.55  5057.6  286.78  5100.9  289.11
  5130.6     289  5202.3  294.34  5238.1  296.49  5244.2  297.32  5252.2  297.22
  5265.1  298.57  5330.6   301.6  5345.5  302.99  5351.6  302.89  5373.9  304.23
#Mann= 3 , 0 , 0
  4700.6     .17       0  4976.8     .09       0  5021.1     .17       0
Bank Sta=4976.8,5021.1
XS Rating Curve= 0 ,0
Exp/Cntr=0.3,0.1

Type RM Length L Ch R = 1 ,12604   ,495,495,495
BEGIN DESCRIPTION:
CCLC 114 20.0
END DESCRIPTION:
XS GIS Cut Line= 3
      3715867.84     10147111.06      3715581.35     10146823.67
      3715317.87      10146511.1
#Sta/Elev= 30
  4594.2   296.5  4664.9  293.59    4683  292.08  4721.5  291.02    4771  287.84
  4792.2  287.65  4841.7  284.77  4875.3  283.76  4933.6  282.07  5011.6  282.17
  5032.4  281.68  5038.4  280.55 5064.04282.1943  5075.3  283.41  5103.9  283.57
  5110.4  284.44  5118.2  283.22    5139  283.35  5153.3  285.86  5167.6   286.3
  5174.1  287.48  5188.4  287.28  5238.8  290.79  5266.5  291.56  5274.2  292.84
  5295.1  293.92    5338  297.83  5344.5  297.63  5380.8  301.66  5408.8  303.18
#Mann= 5 ,-1 , 0
  4594.2     .17       0    4683     .11       0  4875.3     .17       0
  5011.6     .09       0 5064.04     .17       0
Bank Sta=5011.6,5064.04
XS Rating Curve= 0 ,0
Exp/Cntr=0.3,0.1

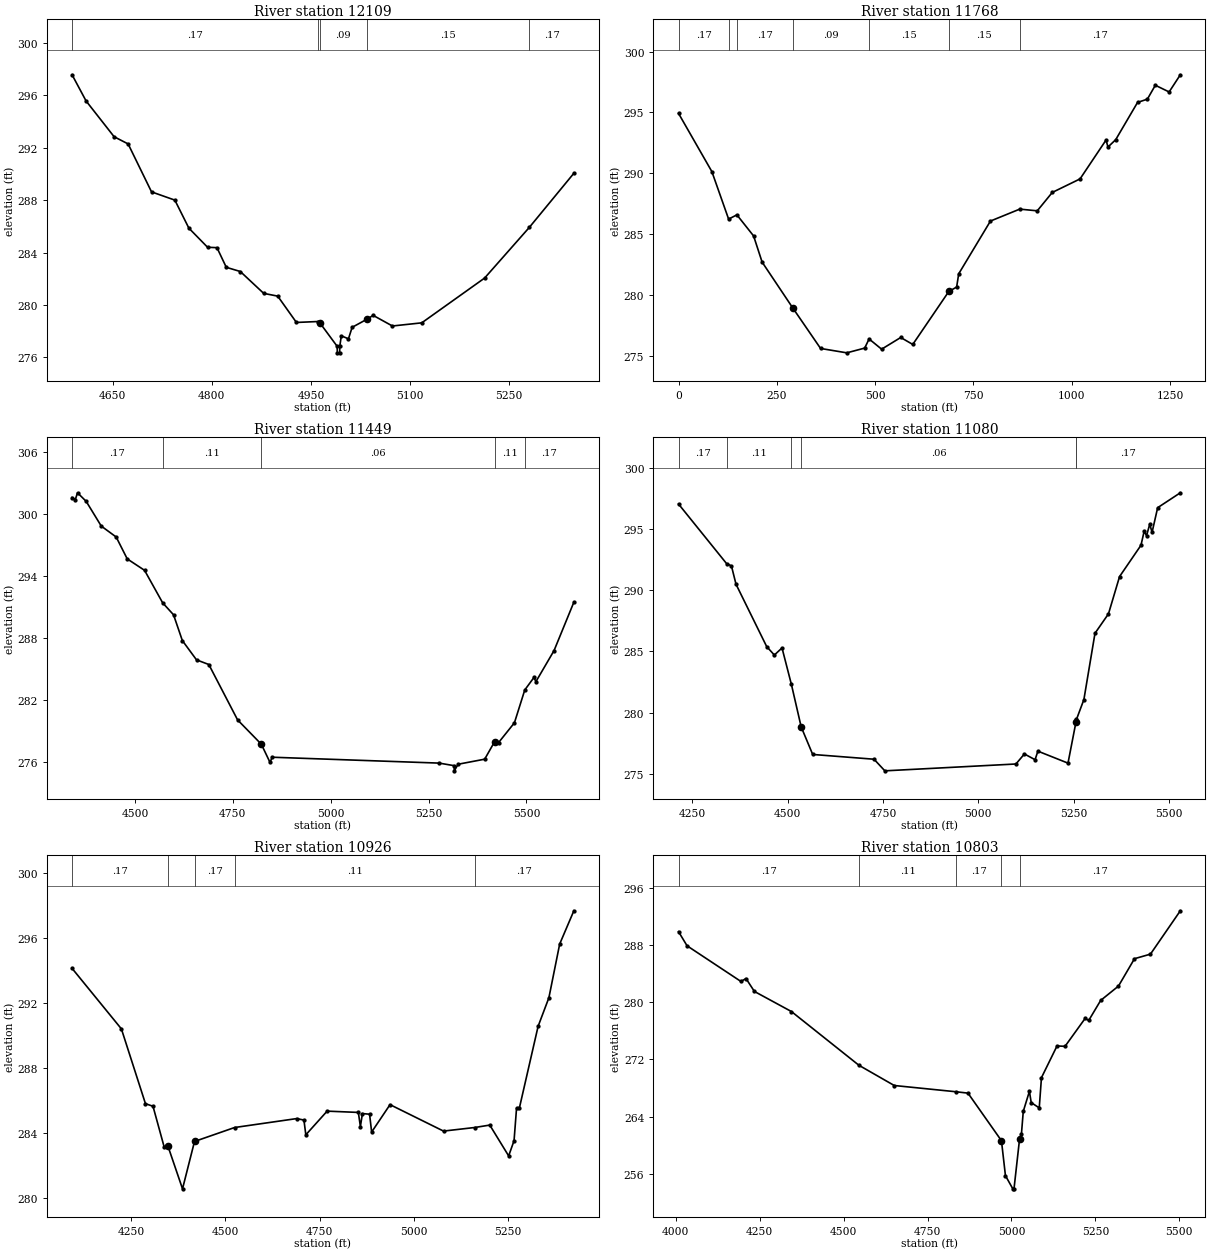
Type RM Length L Ch R = 1 ,12109   ,341,341,341
BEGIN DESCRIPTION:
CCLC 114 19.0
END DESCRIPTION:
XS GIS Cut Line= 3
      3716217.83     10146811.05      3715927.07       10146520.
      3715617.82     10146361.06
#Sta/Elev= 30
  4588.6  297.58  4609.8  295.58  4652.2  292.85  4673.4   292.3  4708.8  288.64
  4744.1  288.01  4765.3  285.87  4793.6  284.41  4807.8  284.38  4821.9  282.88
  4843.1  282.56  4878.5  280.89  4899.7  280.68    4928  278.67    4960  278.74
  4963.3  278.65  4989.6  276.85  4989.9  276.35  4993.4  276.35  4993.6  276.85
  4995.9  277.65  5006.7  277.42  5012.3   278.3  5034.5  278.91  5044.1  279.21
  5073.2   278.4  5117.6  278.64  5212.7  282.06  5280.2  285.92  5347.7  290.06
#Mann= 5 ,-1 , 0
  4588.6     .17       0    4960     .15       0  4963.3     .09       0
  5034.5     .15       0  5280.2     .17       0
Bank Sta=4963.3,5034.5
XS Rating Curve= 0 ,0
Exp/Cntr=0.3,0.1

Type RM Length L Ch R = 1 ,11768   ,319,319,319
BEGIN DESCRIPTION:
CCLC 114 18.0
END DESCRIPTION:
XS GIS Cut Line= 4
      3716467.85     10146611.07      3716181.14     10146293.31
      3715728.64     10146128.39      3715364.72     10146082.48
#Sta/Elev= 30
       0  294.92    84.8  290.14   127.4  286.24   148.4  286.59   190.9  284.86
   212.6  282.71   290.3  278.96   361.3  275.62     428  275.26   473.5  275.65
   484.7   276.4   516.6  275.56   565.2  276.52   595.8  275.95   687.5   280.3
   707.4  280.66   712.7  281.75   793.4  286.08   867.9  287.06   912.5  286.92
   950.7  288.43  1021.3  289.54  1087.4  292.73  1092.4  292.16    1112  292.76
  1167.6  295.82  1192.6  296.09  1212.8  297.23  1247.9  296.68  1276.4  298.09
#Mann= 7 ,-1 , 0
       0     .17       0   127.4     .11       0   148.4     .17       0
   290.3     .09       0   484.7     .15       0   687.5     .15       0
   867.9     .17       0
Bank Sta=290.3,687.5
XS Rating Curve= 0 ,0
Exp/Cntr=0.3,0.1

Type RM Length L Ch R = 1 ,11449   ,369,369,369
BEGIN DESCRIPTION:
CCLC 114 17.0
END DESCRIPTION:
XS GIS Cut Line= 3
      3716717.86     10146661.08      3716413.28     10146074.78
      3716317.85     10145461.05
#Sta/Elev= 30
  4339.3   301.6  4347.6   301.4  4353.2  302.06  4375.3  301.23  4413.9  298.83
    4452  297.77  4480.2  295.65  4524.5  294.54  4570.7  291.39  4598.5  290.23
    4621  287.73  4657.2  285.86  4688.6  285.41  4762.1  280.04  4822.8  277.68
  4844.9  275.92  4850.6  276.42    5277  275.85  5315.5   275.6  5315.7   275.1
  5325.4  275.74  5393.3  276.23  5418.7  277.93  5428.8  277.84  5469.3  279.76
  5495.7  282.94  5519.1  284.15  5524.2  283.75  5570.5  286.76  5621.1  291.45
#Mann= 5 ,-1 , 0
  4339.3     .17       0  4570.7     .11       0  4822.8     .06       0
  5418.7     .11       0  5495.7     .17       0
Bank Sta=4822.8,5418.7
XS Rating Curve= 0 ,0
Exp/Cntr=0.3,0.1

Type RM Length L Ch R = 1 ,11080   ,154,154,154
BEGIN DESCRIPTION:
CCLC 114 16.0
END DESCRIPTION:
XS GIS Cut Line= 3
      3716717.85     10146561.07      3716629.68     10145732.56
      3716338.03     10145347.16
#Sta/Elev= 30
  4213.4  297.06  4339.4  292.19  4352.2     292  4364.2   290.5  4444.7   285.4
  4464.8  284.71  4484.9  285.29  4509.5  282.31  4535.2  278.83  4565.4  276.58
  4726.3  276.19  4754.7  275.24  5098.6   275.8  5120.8  276.62  5148.8  276.15
  5156.2  276.85  5235.2  275.87  5256.1  279.23  5257.5  279.45  5276.9  281.07
    5306  286.49  5341.4  288.08  5370.5  291.13  5426.7  293.69    5435  294.84
  5441.3  294.47  5449.6  295.41  5455.8  294.75  5470.4  296.76  5529.9  297.98
#Mann= 6 ,-1 , 0
  4213.4     .17       0  4339.4     .11       0  4509.5     .17       0
  4535.2     .06       0  5256.1     .11       0  5257.5     .17       0
Bank Sta=4535.2,5256.1
XS Rating Curve= 0 ,0
Exp/Cntr=0.3,0.1

Type RM Length L Ch R = 1 ,10926   ,123,123,123
BEGIN DESCRIPTION:
Mapping XS fa82fcdf
END DESCRIPTION:
XS GIS Cut Line= 6
      3716806.77     10146555.45      3716832.81     10146003.39
      3716806.77     10145831.51      3716749.47     10145685.68
      3716686.97     10145602.35      3716452.71     10145352.48
#Sta/Elev= 30
  4093.6  294.15  4224.4  290.42  4288.2  285.81  4308.2  285.65  4338.2  283.11
  4348.2  283.17  4386.5  280.56  4418.3  283.48  4524.6  284.34  4689.1  284.89
  4708.5   284.8  4713.5  283.89    4770  285.35  4852.8  285.27  4858.2   284.4
  4863.6   285.2  4882.6  285.16    4888  284.06  4936.8  285.75  5078.6  284.12
  5161.1  284.34  5201.3  284.49  5251.4  282.59  5265.7  283.53  5272.3  285.53
    5280  285.56  5329.5  290.58  5358.1  292.34  5386.7  295.65  5424.3   297.7
#Mann= 5 ,-1 , 0
  4093.6     .17       0  4348.2     .06       0  4418.3     .17       0
  4524.6     .11       0  5161.1     .17       0
Bank Sta=4348.2,4418.3
XS Rating Curve= 0 ,0
Exp/Cntr=0.3,0.1

Type RM Length L Ch R = 1 ,10803   ,360,360,360
BEGIN DESCRIPTION:
Mapping XS cf8c726b
END DESCRIPTION:
XS GIS Cut Line= 3
      3716926.55     10146576.34      3716978.64     10145935.68
      3716650.53     10145149.26
#Sta/Elev= 30
  4008.2  289.92  4033.6  287.94  4194.1  282.94  4209.2  283.35  4234.2  281.54
  4344.6  278.72  4545.5  271.19  4650.8  268.35  4835.4  267.47  4870.5  267.28
  4970.2  260.61  4982.1  255.71  5004.1  253.86  5007.6  253.86  5024.3   260.9
  5029.7  261.52  5035.2  264.72  5053.5  267.53  5058.9  265.95  5082.8  265.21
  5089.4  269.45  5135.8   273.9  5159.6  273.84  5219.4  277.75  5230.3  277.48
  5265.8  280.28  5318.8  282.29  5366.5  286.13  5414.1  286.77  5503.1  292.85
#Mann= 5 ,-1 , 0
  4008.2     .17       0  4545.5     .11       0  4835.4     .17       0
  4970.2     .09       0  5024.3     .17       0
Bank Sta=4970.2,5024.3
XS Rating Curve= 0 ,0
Exp/Cntr=0.3,0.1

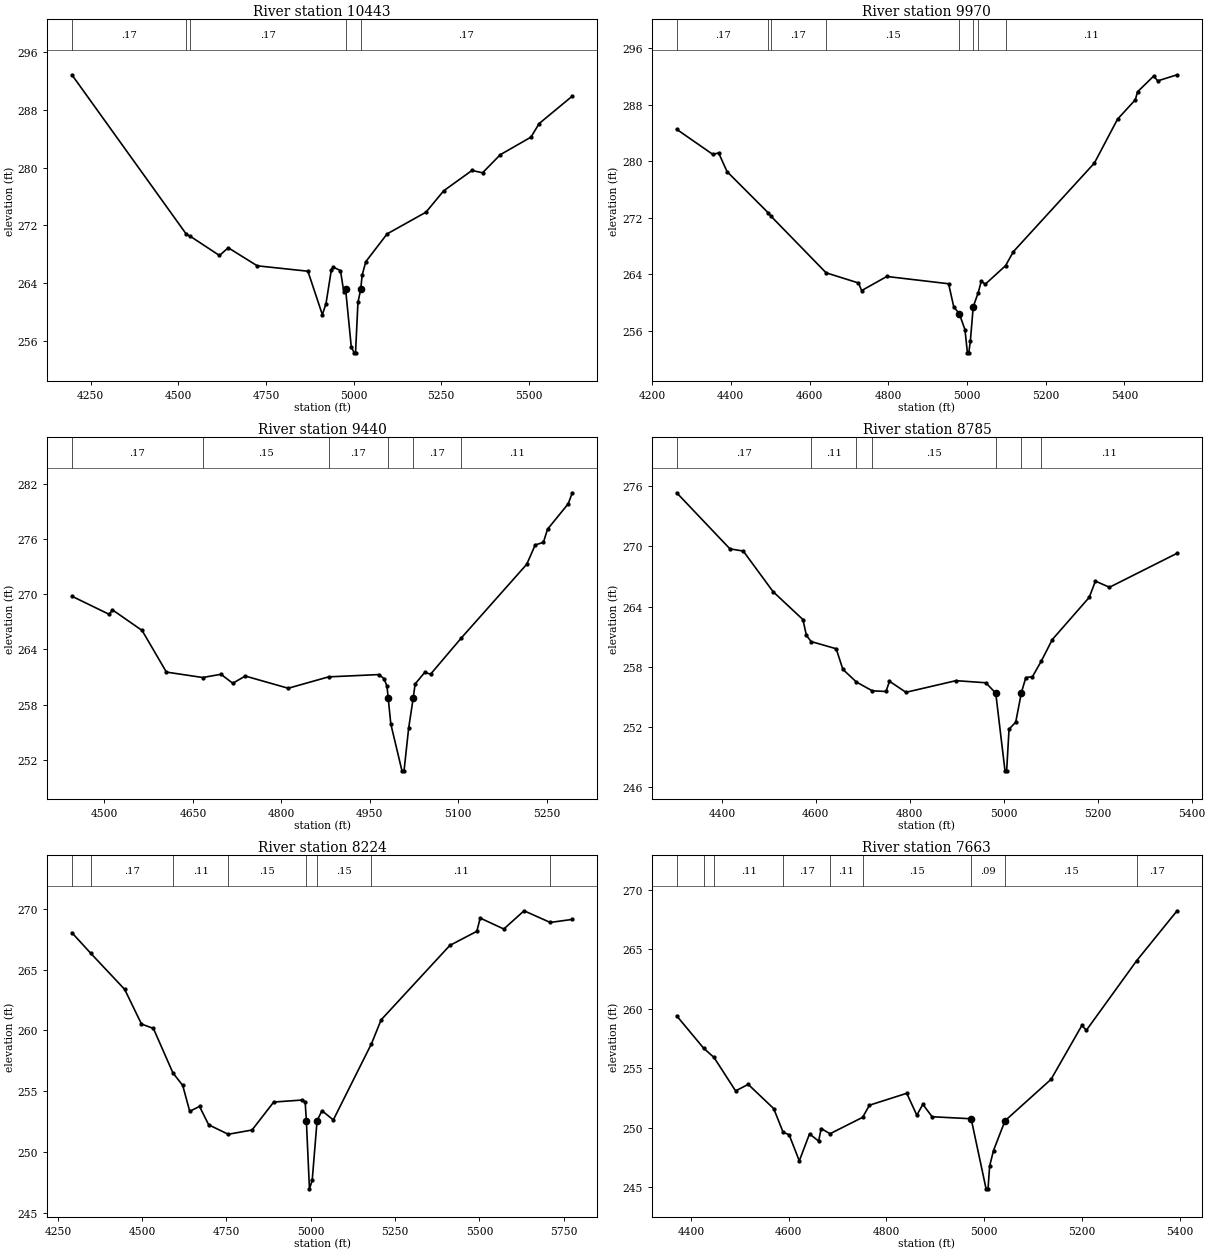
Type RM Length L Ch R = 1 ,10443   ,473,473,473
BEGIN DESCRIPTION:
CCLC 114 15.0
END DESCRIPTION:
XS GIS Cut Line= 3
      3717358.84     10146373.16      3717145.31     10145550.26
      3717067.18     10144977.32
#Sta/Elev= 30
    4196  292.87    4523  270.76  4533.9  270.49  4617.3  267.83  4642.4   268.9
  4725.1   266.4  4869.7  265.65    4911  259.63  4921.3  261.14  4936.7  265.84
    4942  266.22  4962.7  265.74  4972.1  262.83  4977.2  263.23  4993.7  255.09
  5002.2  254.34  5005.7  254.34  5012.6  261.32 5020.37263.1282  5024.7  265.13
    5035  266.97  5095.8  270.82  5206.8  273.83  5257.3  276.79    5338  279.61
  5368.3  279.29  5418.8  281.79  5506.5  284.23  5529.8  286.11  5624.4  289.91
#Mann= 5 ,-1 , 0
    4196     .17       0    4523     .11       0  4533.9     .17       0
  4977.2     .09       0 5020.37     .17       0
Bank Sta=4977.2,5020.37
XS Rating Curve= 0 ,0
Exp/Cntr=0.3,0.1

Type RM Length L Ch R = 1 ,9970    ,530,530,530
BEGIN DESCRIPTION:
CCLC 114 14.0
END DESCRIPTION:
XS GIS Cut Line= 3
      3718017.85     10146061.07      3717551.56     10145477.35
      3717452.72     10144962.35
#Sta/Elev= 30
  4262.5  284.54  4354.6  280.98    4369  281.21  4390.5  278.55  4495.4   272.7
  4501.1   272.3  4642.1  264.23  4724.4  262.79  4732.4  261.71  4796.4  263.71
  4953.4  262.68  4966.4  259.43  4980.6  258.43    4995  256.18  5001.2   252.9
  5004.7   252.9  5008.6  254.51    5016  259.43  5028.7  261.42  5036.4  263.04
  5046.5  262.61  5098.2  265.24  5117.8  267.21  5323.8  279.76  5382.6  285.97
  5427.8  288.72  5433.5  289.85  5474.2  292.06  5484.9   291.4    5534  292.26
#Mann= 8 ,-1 , 0
  4262.5     .17       0  4495.4     .11       0  4501.1     .17       0
  4642.1     .15       0  4980.6     .09       0    5016     .15       0
  5028.7     .17       0  5098.2     .11       0
Bank Sta=4980.6,5016
XS Rating Curve= 0 ,0
Exp/Cntr=0.3,0.1

Type RM Length L Ch R = 1 ,9440    ,655,655,655
BEGIN DESCRIPTION:
CCLC 114 13.0
END DESCRIPTION:
XS GIS Cut Line= 3
        3718088.     10145716.89      3717947.33     10145134.56
      3717761.34     10144968.22
#Sta/Elev= 30
  4444.8  269.79  4508.3  267.81  4513.5  268.31  4563.9  266.06  4605.1  261.53
  4666.6  260.94  4697.7  261.29  4717.7  260.31  4738.8   261.1  4811.7  259.77
  4880.2  261.01  4965.2  261.26    4974  260.83  4979.2  259.99 4981.24258.6969
  4985.7  255.87  5004.6  250.78  5008.1  250.78  5015.9  255.42 5023.74258.7351
  5026.9  260.24  5043.1  261.49  5053.2  261.31  5104.9  265.22  5216.2  273.27
  5230.5  275.37  5244.4  275.65  5251.4  277.08  5286.5  279.85  5293.4  281.05
#Mann= 6 ,-1 , 0
  4444.8     .17       0  4666.6     .15       0  4880.2     .17       0
 4981.24     .09       0 5023.74     .17       0  5104.9     .11       0
Bank Sta=4981.24,5023.74
XS Rating Curve= 0 ,0
Exp/Cntr=0.3,0.1

Type RM Length L Ch R = 1 ,8785    ,561,561,561
BEGIN DESCRIPTION:
CCLC 114 11.0
END DESCRIPTION:
XS GIS Cut Line= 3
      3718992.84     10145386.06      3718369.88     10144805.71
      3718192.82     10144686.05
#Sta/Elev= 30
  4303.8  275.35  4417.1  269.76  4445.5  269.54    4509  265.49  4572.5  262.71
  4579.8  261.14  4589.9  260.52  4643.3   259.8  4657.5  257.75  4686.4  256.48
  4720.1  255.61  4749.3  255.54  4756.7  256.56  4791.8  255.46  4898.3  256.62
  4961.9  256.41  4982.9  255.37  5002.6  247.63  5006.1  247.63  5011.2  251.79
  5025.4  252.48 5037.55255.4379  5046.9  256.93  5061.1  257.02  5080.1  258.59
  5103.3  260.72  5181.8  264.92  5195.1  266.54    5225  265.93  5368.9  269.32
#Mann= 7 ,-1 , 0
  4303.8     .17       0  4589.9     .11       0  4686.4     .17       0
  4720.1     .15       0  4982.9     .09       0 5037.55     .17       0
  5080.1     .11       0
Bank Sta=4982.9,5037.55
XS Rating Curve= 0 ,0
Exp/Cntr=0.3,0.1

Type RM Length L Ch R = 1 ,8224    ,561,561,561
BEGIN DESCRIPTION:
CCLC 114 10.0
END DESCRIPTION:
XS GIS Cut Line= 3
      3719317.83     10145111.04      3718843.22     10144498.18
      3718134.84     10144487.76
#Sta/Elev= 30
  4291.6  268.05  4347.3  266.36  4448.2  263.38    4498  260.53  4533.3  260.17
    4591  256.52  4620.2  255.48    4641  253.35    4670  253.75  4697.2  252.24
  4755.2  251.46  4825.7  251.81    4890  254.11  4975.1  254.28  4983.3  254.12
  4986.8252.5479    4996  246.97  5004.1  247.66  5018.6  252.58  5033.1   253.4
  5066.7  252.64  5179.8  258.91  5208.6  260.88  5412.2     267  5492.2  268.16
  5502.2  269.25  5572.2  268.35  5632.2  269.85  5709.8  268.89  5775.2  269.14
#Mann= 8 ,-1 , 0
  4291.6     .11       0  4347.3     .17       0    4591     .11       0
  4755.2     .15       0  4986.8     .09       0  5018.6     .15       0
  5179.8     .11       0  5709.8     .17       0
Bank Sta=4986.8,5018.6
XS Rating Curve= 0 ,0
Exp/Cntr=0.3,0.1

Type RM Length L Ch R = 1 ,7663    ,467,467,467
BEGIN DESCRIPTION:
CCLC 114 9.0
END DESCRIPTION:
XS GIS Cut Line= 3
      3719417.85     10144761.08      3719235.58     10144159.17
       3719109.1     10143785.39
#Sta/Elev= 30
  4371.1   259.4  4426.4  256.67  4447.5   255.9  4491.6  253.09  4517.4  253.64
  4569.6   251.6  4588.8  249.61    4601  249.41  4621.9  247.21  4642.8  249.48
  4661.4  248.87  4666.6  249.93  4684.7  249.49  4751.4  250.87  4765.4  251.89
  4841.7  252.89  4862.2  251.05  4874.6  251.96  4893.5  250.92  4973.4  250.75
  5003.9  244.86  5007.9  244.86  5011.2  246.78  5019.1  248.08  5042.6  250.58
  5136.9  254.07  5199.8  258.59  5209.1  258.19    5312  264.04  5394.6  268.23
#Mann= 9 ,-1 , 0
  4371.1     .11       0  4426.4     .17       0  4447.5     .11       0
  4588.8     .17       0  4684.7     .11       0  4751.4     .15       0
  4973.4     .09       0  5042.6     .15       0    5312     .17       0
Bank Sta=4973.4,5042.6
XS Rating Curve= 0 ,0
Exp/Cntr=0.3,0.1

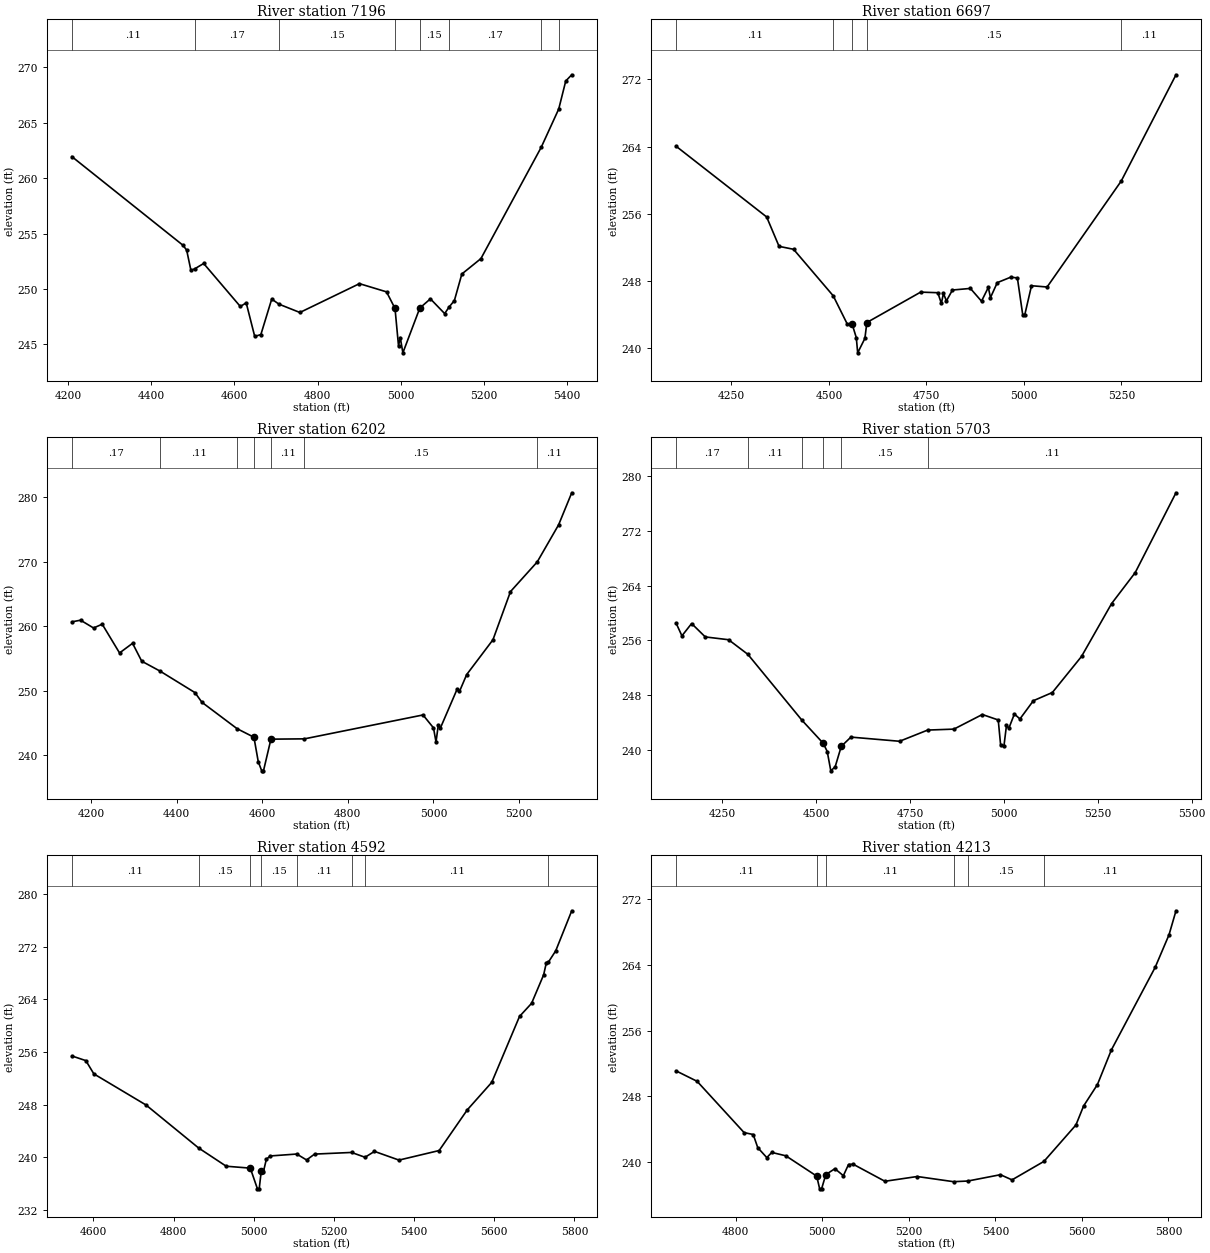
Type RM Length L Ch R = 1 ,7196    ,499,499,499
BEGIN DESCRIPTION:
CCLC 114 8.0
END DESCRIPTION:
XS GIS Cut Line= 3
      3719517.85      10144861.1      3719683.27     10144087.79
      3719517.87     10143711.11
#Sta/Elev= 30
  4209.2  261.94  4476.2  253.95  4485.3  253.51  4495.6  251.67  4504.8  251.82
  4526.2   252.3  4614.4  248.42  4628.5  248.75    4649  245.72  4663.8  245.89
  4689.9  249.09  4707.3  248.63  4757.6  247.88  4900.9  250.48    4966  249.74
  4986.4  248.24  4994.8  244.87    4999  245.62  5005.3  244.24    5046 248.279
  5071.5  249.11  5105.8  247.78  5116.2  248.36  5129.2  248.96  5147.1  251.35
    5193  252.74    5338  262.78  5380.1  266.23    5397  268.76  5411.4  269.32
#Mann= 8 ,-1 , 0
  4209.2     .11       0  4504.8     .17       0  4707.3     .15       0
  4986.4     .09       0    5046     .15       0  5116.2     .17       0
    5338     .11       0  5380.1     .17       0
Bank Sta=4986.4,5046
XS Rating Curve= 0 ,0
Exp/Cntr=0.3,0.1

Type RM Length L Ch R = 1 ,6697    ,495,495,495
BEGIN DESCRIPTION:
CCLC 114 7.0
END DESCRIPTION:
XS GIS Cut Line= 3
      3720517.85     10144861.07      3720145.96      10144050.3
      3720167.85     10143661.11
#Sta/Elev= 30
    4108  264.04  4340.2  255.62    4372  252.12  4409.2  251.77  4510.9  246.23
  4547.2  242.84  4559.1  242.91  4570.1  241.24  4573.6  239.44  4592.1  241.16
 4597.14 243.052  4735.1  246.67  4779.1   246.6  4788.1  245.33  4793.6  246.52
  4801.1  245.62  4816.6  246.92  4862.6  247.11  4891.1  245.59  4908.6  247.23
  4914.1  246.02  4931.6   247.8  4966.1  248.45  4983.1  248.36  4996.8  243.98
  5002.1  243.98  5019.3  247.43  5059.3  247.28  5249.3  259.89  5389.8  272.55
#Mann= 5 ,-1 , 0
    4108     .11       0  4510.9     .15       0  4559.1     .09       0
 4597.14     .15       0  5249.3     .11       0
Bank Sta=4559.1,4597.14
XS Rating Curve= 0 ,0
Exp/Cntr=0.3,0.1

Type RM Length L Ch R = 1 ,6202    ,499,499,499
BEGIN DESCRIPTION:
CCLC 114 6.0
END DESCRIPTION:
XS GIS Cut Line= 3
      3720717.86     10144761.11       3720585.2     10143926.89
      3720517.86     10143611.09
#Sta/Elev= 30
  4155.3  260.68  4175.6  260.94    4206  259.73  4226.2  260.32  4266.7  255.85
  4297.1  257.35  4318.5  254.57  4361.1  253.04  4442.9  249.69  4459.1  248.19
  4541.2  244.09  4580.6  242.76  4590.7  238.96  4598.8  237.54  4602.9  237.54
  4620.3  242.46  4698.7  242.51  4975.5  246.22    5000  244.21  5005.9  242.02
  5011.2  244.65  5016.3  244.22  5055.6  250.29  5060.7  249.87  5077.5  252.49
  5138.9   257.9  5179.8  265.38  5242.3  269.99  5292.2  275.75  5322.9  280.73
#Mann= 7 ,-1 , 0
  4155.3     .17       0  4361.1     .11       0  4541.2     .15       0
  4580.6     .09       0  4620.3     .11       0  4698.7     .15       0
  5242.3     .11       0
Bank Sta=4580.6,4620.3
XS Rating Curve= 0 ,0
Exp/Cntr=0.3,0.1

Type RM Length L Ch R = 1 ,5703    ,1111,1111,1111
BEGIN DESCRIPTION:
CCLC 114 5.0
END DESCRIPTION:
XS GIS Cut Line= 3
      3720767.85     10144711.08      3721055.42      10143886.8
      3721317.85     10143511.07
#Sta/Elev= 30
    4127  258.51  4142.5  256.65  4168.3  258.45  4204.7  256.49  4266.8  256.08
  4318.1  253.94    4462   244.3  4518.9  240.91  4529.5  239.71    4539  236.88
  4550.6  237.47  4566.9  240.47  4592.6  241.82  4722.2  241.21    4797  242.85
  4866.9  242.99  4942.5  245.13  4984.9  244.33  4991.2   240.7    5000  240.47
  5006.9  243.55    5013  243.09  5027.9   245.2  5042.7  244.48  5078.5  247.15
    5129  248.35  5206.7  253.63  5286.9  261.38  5349.7  265.91  5458.3   277.6
#Mann= 6 ,-1 , 0
    4127     .17       0  4318.1     .11       0    4462     .15       0
  4518.9     .07       0  4566.9     .15       0    4797     .11       0
Bank Sta=4518.9,4566.9
XS Rating Curve= 0 ,0
Exp/Cntr=0.3,0.1

Type RM Length L Ch R = 1 ,4592    ,379,379,379
BEGIN DESCRIPTION:
CCLC 114 4.0
END DESCRIPTION:
XS GIS Cut Line= 3
      3721525.52     10144815.93      3721509.89      10144383.6
      3721567.18     10143571.13
#Sta/Elev= 30
  4546.3   255.4  4581.2  254.69  4601.2  252.68  4731.3  247.96  4862.5  241.44
  4931.4  238.67  4991.5  238.38  5009.3  235.24  5013.7  235.24  5018.8  237.93
  5023.8  237.73  5031.6  239.74  5041.6  240.23  5107.4  240.52  5131.8  239.62
  5151.9  240.51  5244.1  240.76  5277.7  240.03  5301.3  240.92  5362.4   239.6
  5462.6  241.05  5532.8  247.22  5593.8  251.39  5663.1  261.39  5693.2  263.38
  5723.3   267.7  5730.1  269.56  5734.6  269.58  5753.4  271.34  5793.4  277.42
#Mann= 8 ,-1 , 0
  4546.3     .11       0  4862.5     .15       0  4991.5     .09       0
  5018.8     .15       0  5107.4     .11       0  5244.1     .15       0
  5277.7     .11       0  5734.6     .17       0
Bank Sta=4991.5,5018.8
XS Rating Curve= 0 ,0
Exp/Cntr=0.3,0.1

Type RM Length L Ch R = 1 ,4213    ,498,498,498
BEGIN DESCRIPTION:
CCLC 114 3.0
END DESCRIPTION:
XS GIS Cut Line= 3
      3721767.86     10144711.06      3721869.05     10144388.88
      3721617.84     10143611.03
#Sta/Elev= 30
  4662.3  251.11  4710.9  249.84  4819.5   243.6  4840.5  243.37    4851  241.77
  4871.9  240.56  4883.4  241.19  4915.8  240.78  4987.2  238.31    4994  236.76
  4998.5  236.76  5008.2  238.49  5029.2  239.21  5048.8  238.36  5060.7  239.72
  5071.3  239.76  5144.8  237.68  5219.5  238.26  5303.4  237.63  5336.4  237.71
  5411.7  238.48  5438.5  237.85  5512.3   240.1  5586.2  244.53  5603.9  246.84
  5635.9  249.45    5668  253.65  5769.3  263.71  5801.3  267.67  5817.4  270.59
#Mann= 6 ,-1 , 0
  4662.3     .11       0  4987.2     .09       0  5008.2     .11       0
  5303.4     .11       0  5336.4     .15       0  5512.3     .11       0
Bank Sta=4987.2,5008.2
XS Rating Curve= 0 ,0
Exp/Cntr=0.3,0.1

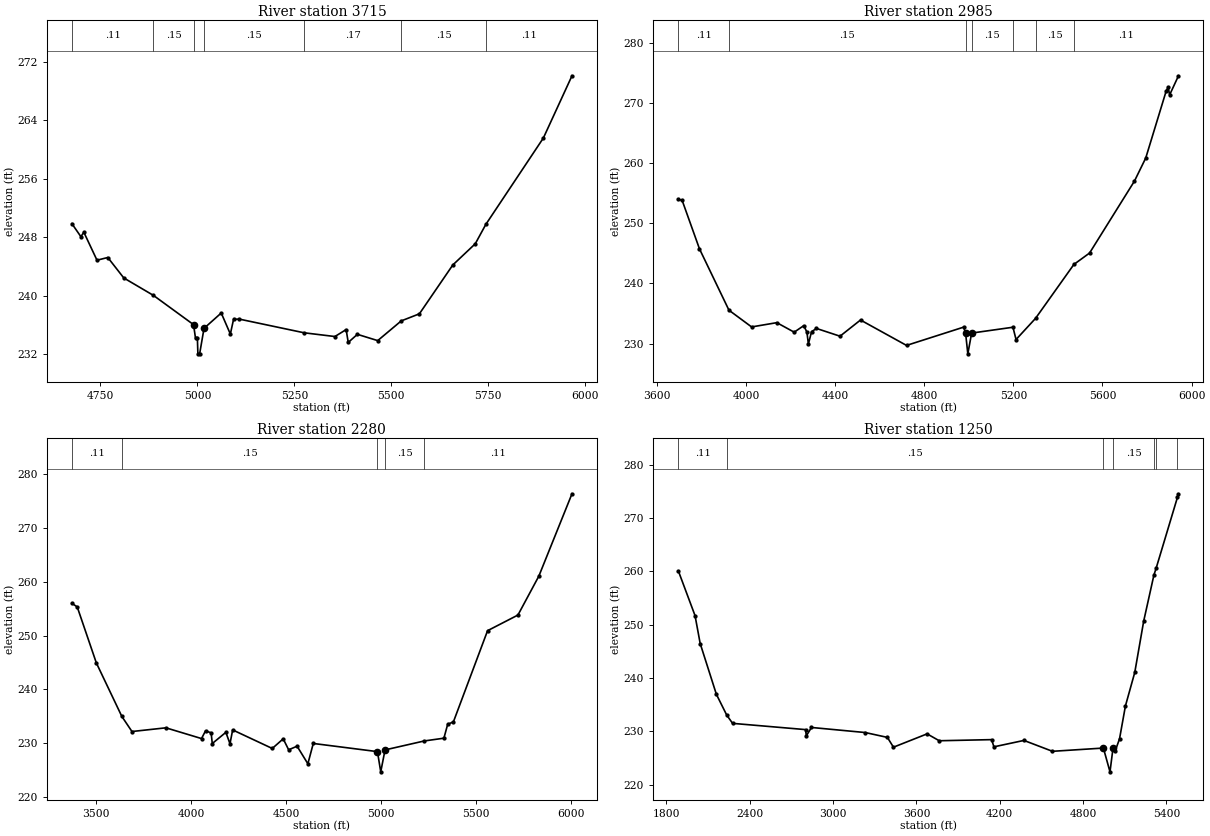
Type RM Length L Ch R = 1 ,3715    ,730,730,730
BEGIN DESCRIPTION:
CCLC 114 2.0
END DESCRIPTION:
XS GIS Cut Line= 3
      3722267.85     10144611.09      3722345.33      10144296.8
      3721963.03     10143409.67
#Sta/Elev= 30
  4676.3  249.86  4699.6  248.07  4707.2  248.68  4741.1  244.85    4769  245.22
  4810.2  242.42  4886.7  240.03  4990.1  236.03  4995.2  234.15    5000  234.15
  5001.3  232.03  5005.8  232.03  5017.1  235.52  5061.5  237.62    5085  234.74
  5093.3  236.76  5108.5  236.78  5275.4  234.91  5354.6   234.4  5383.6  235.35
    5389  233.59  5412.6   234.7    5465  233.84  5525.7  236.54  5572.5  237.51
  5658.7   244.2  5716.6   247.1  5743.9  249.76  5892.2  261.58    5966   270.1
#Mann= 7 ,-1 , 0
  4676.3     .11       0  4886.7     .15       0  4990.1     .09       0
  5017.1     .15       0  5275.4     .17       0  5525.7     .15       0
  5743.9     .11       0
Bank Sta=4990.1,5017.1
XS Rating Curve= 0 ,0
Exp/Cntr=0.3,0.1

Type RM Length L Ch R = 1 ,2985    ,705,705,705
BEGIN DESCRIPTION:
Mapping XS 925dc390
END DESCRIPTION:
XS GIS Cut Line= 3
       3722254.7     10144690.88      3723046.35     10144019.01
      3722062.38     10143321.39
#Sta/Elev= 30
  3696.6  253.96  3713.4  253.83  3791.4  245.75  3923.7  235.56  4025.3  232.78
  4138.4  233.49  4216.4  231.91  4259.3  232.99  4273.6  231.92  4280.1  229.94
  4294.4  231.99  4316.4  232.53  4422.1  231.24  4514.1  233.93  4720.6  229.71
  4977.1  232.75  4985.8231.6949  4995.7  228.31  5012.8  231.76  5198.2  232.73
  5212.1  230.69  5299.5   234.2  5471.8  243.17  5542.1  245.06  5743.6  257.02
  5794.1  260.84  5886.3  272.03    5895  272.63  5901.1  271.31  5941.1  274.51
#Mann= 7 ,-1 , 0
  3696.6     .11       0  3923.7     .15       0  4985.8     .09       0
  5012.8     .15       0  5198.2     .11       0  5299.5     .15       0
  5471.8     .11       0
Bank Sta=4985.8,5012.8
XS Rating Curve= 0 ,0
Exp/Cntr=0.3,0.1

Type RM Length L Ch R = 1 ,2280    ,1030,1030,1030
BEGIN DESCRIPTION:
Mapping XS 6102b370
END DESCRIPTION:
XS GIS Cut Line= 3
      3722254.66     10144748.19       3723390.1     10143956.51
      3723364.06     10142706.47
#Sta/Elev= 30
  3371.2  256.02  3399.5  255.34  3500.2  244.92  3634.6  234.96  3687.8  232.16
  3866.6  232.85  4054.2  230.85  4075.2  232.28  4104.8  231.92  4110.9  229.93
  4182.5  232.01  4204.1  229.88  4218.2  232.46  4426.8  229.01  4484.5   230.8
  4513.2  228.76  4557.6  229.43  4614.4  226.16  4642.9  229.94  4980.9  228.42
  4998.3  224.66  5020.9  228.74  5228.2  230.41    5331  230.92    5351  233.52
    5381  233.95    5561  250.92    5721  253.83  5831.1  261.07  6005.7  276.39
#Mann= 5 ,-1 , 0
  3371.2     .11       0  3634.6     .15       0  4980.9     .09       0
  5020.9     .15       0  5228.2     .11       0
Bank Sta=4980.9,5020.9
XS Rating Curve= 0 ,0
Exp/Cntr=0.3,0.1

Type RM Length L Ch R = 1 ,1250    ,0,0,0
BEGIN DESCRIPTION:
CCLC 114 1.0
END DESCRIPTION:
XS GIS Cut Line= 4
      3722228.65     10144847.13      3723822.39     10143894.01
      3724218.22     10143123.18      3723469.24     10142665.47
#Sta/Elev= 30
  1885.6  260.09  2005.8  251.71  2042.8  246.48  2159.5  236.95  2233.7  233.07
  2276.2  231.51  2801.4  230.34  2807.2  229.17  2844.2  230.74  3231.2  229.79
  3390.7  228.88  3434.4  227.04  3676.7  229.54  3764.1  228.25  4141.3  228.46
  4157.9  227.11  4374.1  228.31  4579.4  226.27  4946.2  226.88  4993.7  222.42
 5015.58226.8932  5031.5  226.36  5062.3   228.6  5104.9  234.78  5172.1  241.06
  5236.5   250.7  5309.9  259.31  5325.9  260.59  5479.4  273.89  5486.9  274.56
#Mann= 7 ,-1 , 0
  1885.6     .11       0  2233.7     .15       0  4946.2     .09       0
 5015.58     .15       0  5309.9     .11       0  5325.9     .17       0
  5479.4     .11       0
Bank Sta=4946.2,5015.58
XS Rating Curve= 0 ,0
Exp/Cntr=0.3,0.1

Chan Stop Cuts=-1
Use User Specified Reach Order=0
Composite Channel Slope=5