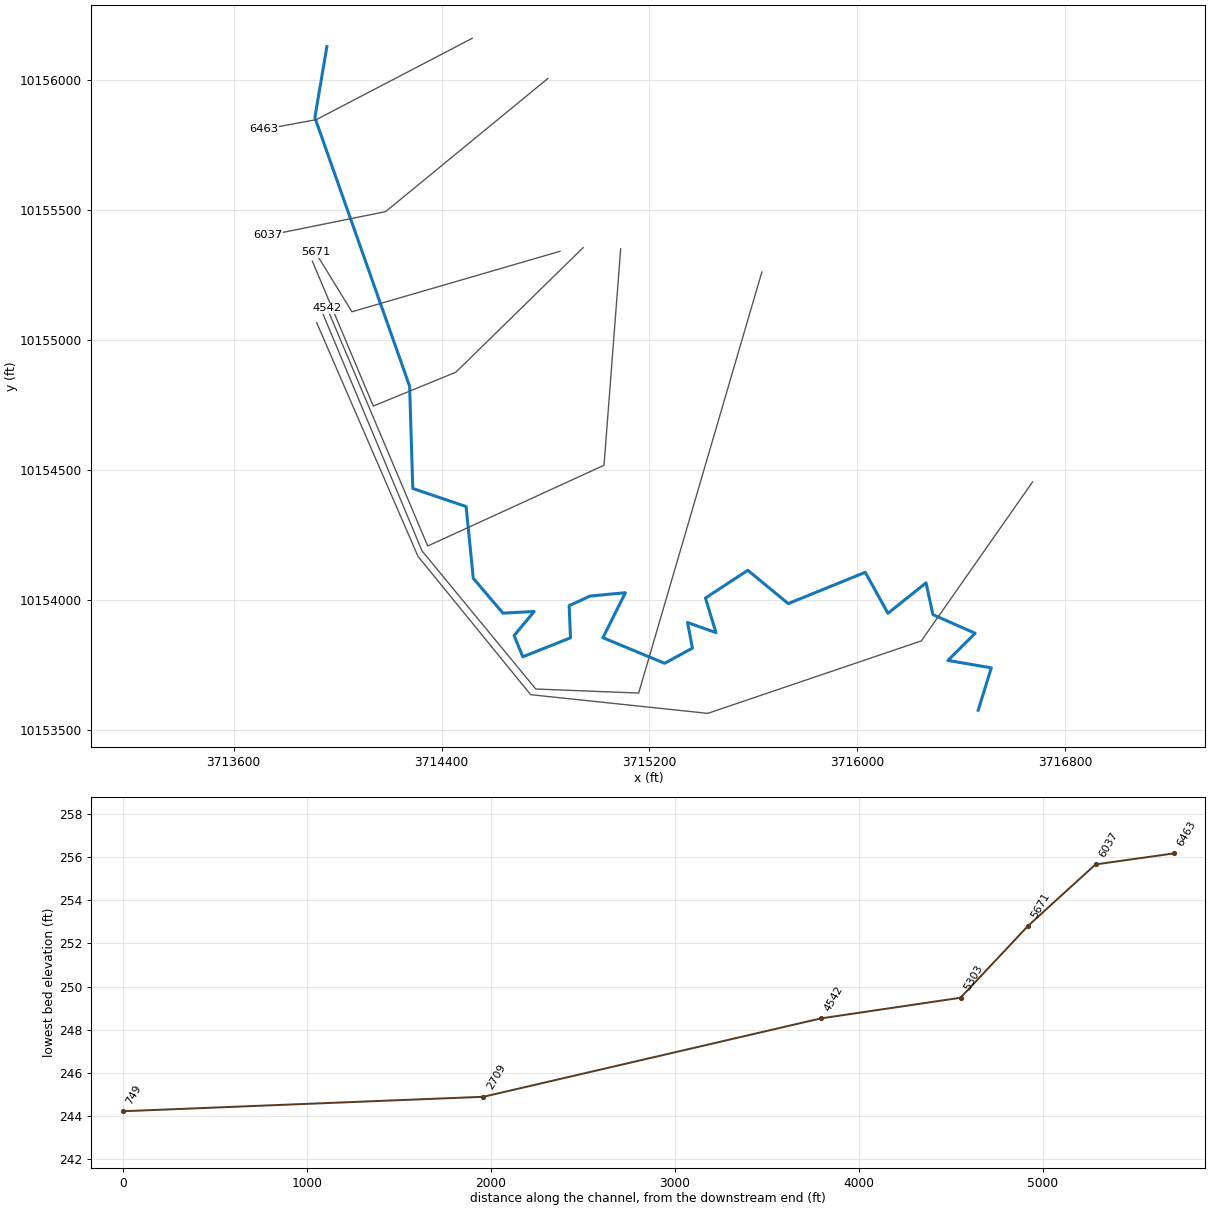
--- CCLC 115.prj (project) ---

Proj Title=CCLC 115 Base Level Engineering
Current Plan=p01
Default Exp/Contr=0.3,0.1
English Units
Geom File=g01
Flow File=f01
Flow File=f02
Plan File=p01
Y Axis Title=Elevation
X Axis Title(PF)=Main Channel Distance
X Axis Title(XS)=Station
BEGIN DESCRIPTION:
CCLC 115
END DESCRIPTION:
DSS Export Rating Curves= 0
DSS Export Rating Curve Sorted= 0
DSS Export Volume Flow Curves= 0
DXF OffsetX= 0
DXF OffsetY= 0
DXF ScaleX= 1
DXF ScaleY= 10

--- CCLC 115.p01 (plan) ---

Plan Title=Multiple Run
Short Identifier=Multiple
Geom File=g01
Flow File=f01
Subcritical Flow
K Sum by GR= 0
Std Step Tol= 0.01
Critical Tol= 0.01
Num of Std Step Trials= 20
Max Error Tol= 0.3
Flow Tol Ratio= 0.001
Split Flow NTrial= 30
Split Flow Tol= 0.02
Split Flow Ratio= 0.02
Log Output Level= 0
Friction Slope Method= 1
Unsteady Friction Slope Method= 2
Unsteady Bridges Friction Slope Method= 1
Parabolic Critical Depth
Global Vel Dist=  1 , 1 , 1
Global Log Level= 0
CheckData=True
Encroach Param= -1, 0, 0, 0
BEGIN DESCRIPTION:
Multiple Run
END DESCRIPTION:

--- CCLC 115.f01 (steady flow) ---

Flow Title=Multiple
Program Version=4.10
Number of Profiles= 7
Profile Names=10-year,25-year,50-year,1pct_min,100-year,1pct_plu,500-year
River Rch & RM=CCLC 115,Reach-1         ,6463
     951    1313    1797     808    2439    7366    4647
River Rch & RM=CCLC 115,Reach-1         ,749
     951    1313    1797     808    2439    7366    4647
Boundary for River Rch & Prof#=CCLC 115,Reach-1         , 1
Up Type= 0
Dn Type= 3
Dn Slope=0.005
Boundary for River Rch & Prof#=CCLC 115,Reach-1         , 2
Up Type= 0
Dn Type= 3
Dn Slope=0.005
Boundary for River Rch & Prof#=CCLC 115,Reach-1         , 3
Up Type= 0
Dn Type= 3
Dn Slope=0.005
Boundary for River Rch & Prof#=CCLC 115,Reach-1         , 4
Up Type= 0
Dn Type= 3
Dn Slope=0.005
Boundary for River Rch & Prof#=CCLC 115,Reach-1         , 5
Up Type= 0
Dn Type= 3
Dn Slope=0.005
Boundary for River Rch & Prof#=CCLC 115,Reach-1         , 6
Up Type= 0
Dn Type= 3
Dn Slope=0.005
Boundary for River Rch & Prof#=CCLC 115,Reach-1         , 7
Up Type= 0
Dn Type= 3
Dn Slope=0.005
DSS Import GetInterval= 0
DSS Import GetPeak= 0
DSS Import FillOption= 0

--- CCLC 115.f02 (steady flow) ---

Flow Title=Orig_BLE_Flows
Program Version=4.10
Number of Profiles= 7
Profile Names=10-year,25-year,50-year,1pct_min,100-year,1pct_plu,500-year
River Rch & RM=CCLC 115,Reach-1         ,6463
     951    1287    1563     621    1876    5664    2702
River Rch & RM=CCLC 115,Reach-1         ,749
     951    1287    1563     621    1876    5664    2702
Boundary for River Rch & Prof#=CCLC 115,Reach-1         , 1
Up Type= 0
Dn Type= 3
Dn Slope=0.005
Boundary for River Rch & Prof#=CCLC 115,Reach-1         , 2
Up Type= 0
Dn Type= 3
Dn Slope=0.005
Boundary for River Rch & Prof#=CCLC 115,Reach-1         , 3
Up Type= 0
Dn Type= 3
Dn Slope=0.005
Boundary for River Rch & Prof#=CCLC 115,Reach-1         , 4
Up Type= 0
Dn Type= 3
Dn Slope=0.005
Boundary for River Rch & Prof#=CCLC 115,Reach-1         , 5
Up Type= 0
Dn Type= 3
Dn Slope=0.005
Boundary for River Rch & Prof#=CCLC 115,Reach-1         , 6
Up Type= 0
Dn Type= 3
Dn Slope=0.005
Boundary for River Rch & Prof#=CCLC 115,Reach-1         , 7
Up Type= 0
Dn Type= 3
Dn Slope=0.005
DSS Import GetInterval= 0
DSS Import GetPeak= 0
DSS Import FillOption= 0

--- CCLC 115.g01 (geometry) ---

Geom Title=Existing Conditions
Program Version=4.10

River Reach=CCLC 115        ,Reach-1
Reach XY= 30
      3713958.91     10156129.17      3713912.67     10155856.44
      3714277.25     10154822.59       3714289.4     10154429.33
       3714494.4     10154359.99      3714522.18     10154083.67
      3714636.29     10153949.75      3714756.42     10153956.17
      3714679.23     10153863.53      3714712.68     10153781.84
      3714896.11     10153854.74      3714891.05     10153978.48
      3714971.64      10154015.6      3715107.38     10154028.36
      3715020.97     10153855.25      3715258.23     10153756.82
      3715365.29     10153815.13      3715346.38     10153913.75
      3715455.77     10153874.73      3715415.31     10154007.78
      3715578.19      10154114.6      3715733.78     10153986.42
      3716030.02     10154106.87      3716117.33     10153949.13
      3716263.95      10154066.3      3716290.46     10153944.03
       3716452.9     10153872.23      3716347.99      10153767.8
      3716515.01     10153739.32      3716464.47     10153576.28

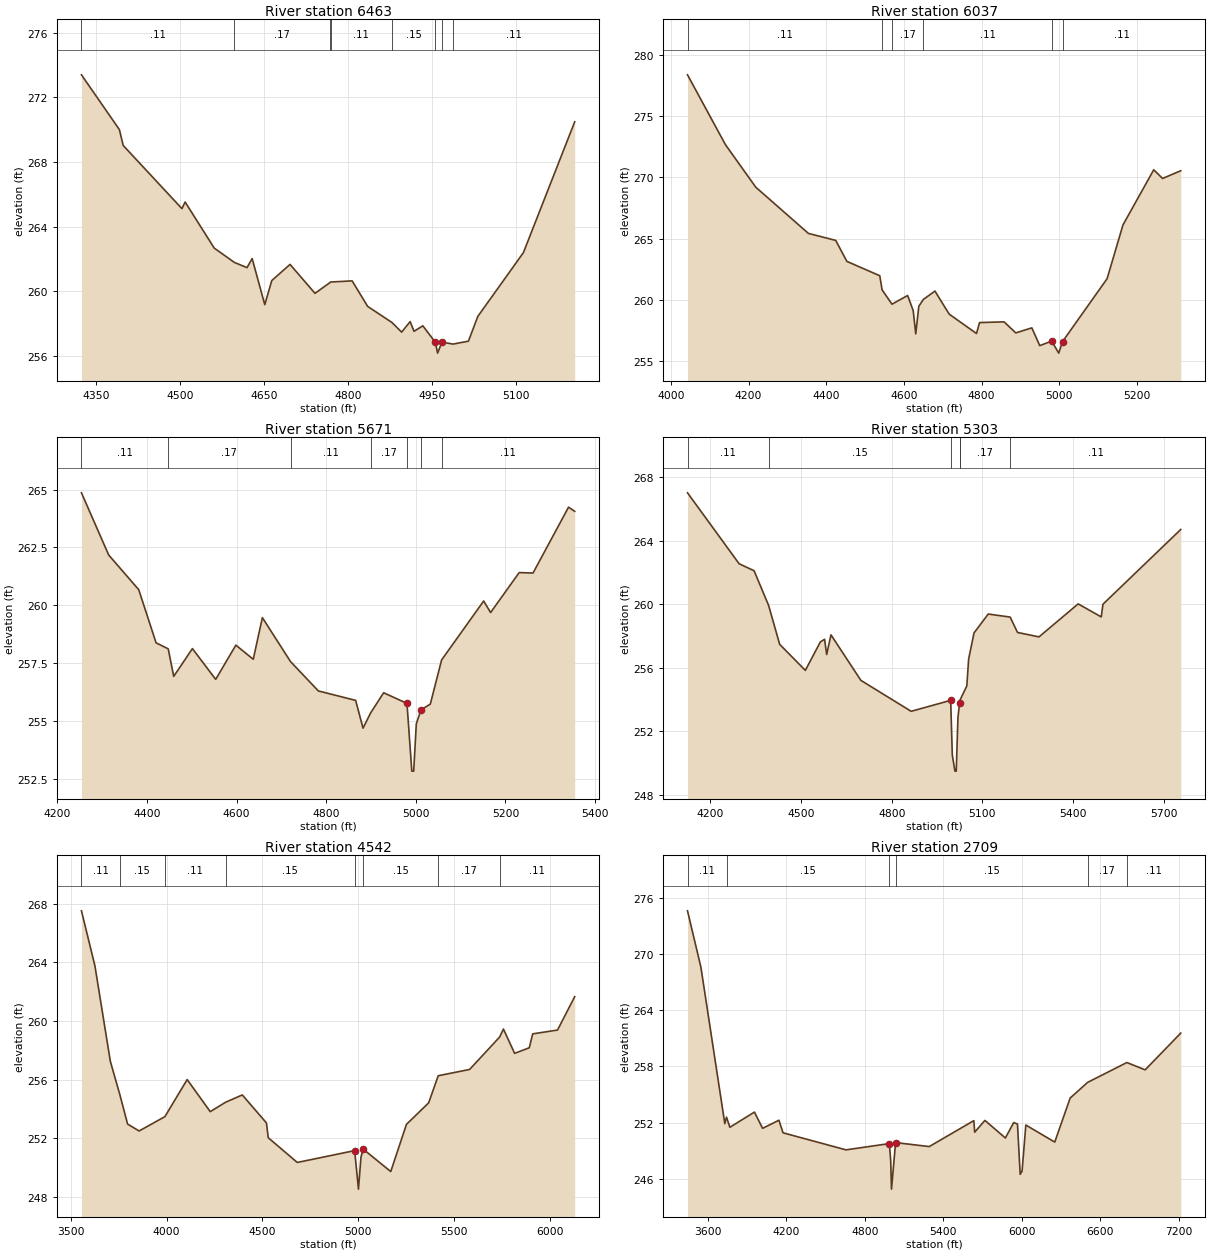
Type RM Length L Ch R = 1 ,6463    ,426,426,426
BEGIN DESCRIPTION:
CCLC 115 2.0
END DESCRIPTION:
XS GIS Cut Line= 3
      3714517.88     10156161.09      3713918.61      10155848.5
      3713717.87     10155811.07
#Sta/Elev= 30
  4324.1  273.39  4391.8     270  4398.6  269.02  4503.4  265.11  4509.1  265.52
    4561  262.67  4597.1  261.78  4619.5  261.46  4628.7  262.02  4651.2  259.17
  4663.7  260.66  4696.3  261.66  4740.8  259.87    4767  260.52  4768.6  260.57
  4807.1  260.64  4834.8  259.06    4878  258.07  4895.4  257.47  4910.6  258.12
  4917.5  257.52  4933.2  257.86  4955.4256.8519  4959.6  256.17  4967.3  256.85
  4987.1  256.73  5014.6  256.91  5031.3  258.44  5112.7  262.39  5204.2  270.48
#Mann= 8 ,-1 , 0
  4324.1     .11       0  4597.1     .17       0    4767     .15       0
  4768.6     .11       0    4878     .15       0  4955.4     .06       0
  4967.3     .15       0  4987.1     .11       0
Bank Sta=4955.4,4967.3
XS Rating Curve= 0 ,0
Exp/Cntr=0.3,0.1

Type RM Length L Ch R = 1 ,6037    ,366,366,366
BEGIN DESCRIPTION:
Mapping XS 3b900086
END DESCRIPTION:
XS GIS Cut Line= 3
       3714809.4     10156006.88      3714184.79     10155494.37
      3713732.01     10155402.85
#Sta/Elev= 30
  4042.8  278.35  4140.2  272.67  4218.5  269.19  4354.1  265.42  4424.4  264.85
  4453.1  263.14  4537.8  261.97  4543.8  260.82  4569.2  259.65  4609.6  260.36
  4623.9  259.12  4630.4  257.23  4638.3  259.48  4650.1  260.04  4679.9  260.72
  4716.5  258.84  4786.8  257.26  4794.7  258.15  4857.8  258.21    4888  257.31
  4929.3  257.72  4949.7  256.27  4980.3  256.64  4998.6  255.66 5008.33256.5997
  5123.1  261.73  5163.9  266.11  5243.2  270.61  5265.9   269.9  5312.7  270.53
#Mann= 6 ,-1 , 0
  4042.8     .11       0  4543.8     .15       0  4569.2     .17       0
  4650.1     .11       0  4980.3     .07       0 5008.33     .11       0
Bank Sta=4980.3,5008.33
XS Rating Curve= 0 ,0
Exp/Cntr=0.3,0.1

Type RM Length L Ch R = 1 ,5671    ,368,368,368
BEGIN DESCRIPTION:
Mapping XS 2073f026
END DESCRIPTION:
XS GIS Cut Line= 3
      3714855.67     10155341.76       3714055.3     10155109.12
      3713915.34      10155337.2
#Sta/Elev= 30
  4253.5  264.86  4314.3  262.17  4381.4  260.67  4420.1  258.37  4447.2  258.11
  4459.5  256.92  4501.2  258.12  4553.2  256.79  4598.2  258.27    4637  257.66
  4657.4  259.46  4720.2  257.56  4782.3  256.29  4865.6  255.88  4882.1  254.68
  4899.1  255.34  4928.1  256.21  4980.2  255.75    4991  252.82  4995.2  252.82
    5001  254.86  5011.4  255.47  5032.3  255.72  5057.5  257.63  5151.4  260.18
  5166.9  259.68  5230.7  261.41  5261.6  261.39  5340.9  264.24  5354.6  264.06
#Mann= 7 ,-1 , 0
  4253.5     .11       0  4447.2     .17       0  4720.2     .11       0
  4899.1     .17       0  4980.2     .09       0  5011.4     .17       0
  5057.5     .11       0
Bank Sta=4980.2,5011.4
XS Rating Curve= 0 ,0
Exp/Cntr=0.3,0.1

Type RM Length L Ch R = 1 ,5303    ,761,761,761
BEGIN DESCRIPTION:
Mapping XS 0d8ea606
END DESCRIPTION:
XS GIS Cut Line= 4
       3714944.8     10155355.84       3714455.2     10154876.65
      3714137.49     10154746.44      3713903.12     10155303.74
#Sta/Elev= 30
  4123.9  267.02  4294.8  262.55  4344.3  262.11  4392.3  259.93  4429.1  257.47
    4514  255.83  4563.6  257.62  4577.7  257.79  4584.7  256.83  4598.9  258.07
  4697.9   255.2  4864.4  253.25  4995.2  253.94  5000.6  250.49  5009.3  249.48
  5013.6  249.48  5019.2  252.84  5024.6  253.77  5026.7  253.98  5048.6  254.85
  5054.7  256.55  5072.5  258.19  5119.5  259.38  5192.1  259.19  5216.5  258.22
  5287.5  257.94  5417.3  260.02  5493.6   259.2  5499.4     260  5756.9  264.71
#Mann= 6 ,-1 , 0
  4123.9     .11       0  4392.3     .15       0  4995.2     .09       0
  5024.6     .15       0  5026.7     .17       0  5192.1     .11       0
Bank Sta=4995.2,5024.6
XS Rating Curve= 0 ,0
Exp/Cntr=0.3,0.1

Type RM Length L Ch R = 1 ,4542    ,1833,1833,1833
BEGIN DESCRIPTION:
Mapping XS 82189686
END DESCRIPTION:
XS GIS Cut Line= 4
      3715089.15     10155351.29      3715025.12      10154518.7
      3714346.96     10154208.07      3713959.82     10155122.97
#Sta/Elev= 30
  3555.6  267.52    3626  263.76  3706.3  257.25  3755.8  254.98  3796.5  252.96
  3856.7  252.49  3991.3  253.47  4107.4     256  4227.8  253.81  4307.7  254.45
  4395.1  254.95  4521.1  253.04  4530.6  252.03  4682.1  250.34  4981.6  251.15
  5001.4  248.52  5014.6  250.71  5026.2  251.25  5169.9  249.72  5251.8  252.94
  5367.8  254.41  5417.6  256.26  5581.5  256.69  5738.1   258.9  5758.1  259.45
  5816.4  257.79  5892.9  258.17  5910.8  259.12  6040.4  259.38    6130  261.66
#Mann= 8 ,-1 , 0
  3555.6     .11       0  3755.8     .15       0  3991.3     .11       0
  4307.7     .15       0  4981.6     .09       0  5026.2     .15       0
  5417.6     .17       0  5738.1     .11       0
Bank Sta=4981.6,5026.2
XS Rating Curve= 0 ,0
Exp/Cntr=0.3,0.1

Type RM Length L Ch R = 1 ,2709    ,1960,1960,1960
BEGIN DESCRIPTION:
Mapping XS 4fcd0edc
END DESCRIPTION:
XS GIS Cut Line= 5
      3715632.28     10155262.04      3715158.33     10153642.28
      3714762.49      10153657.9      3714324.99     10154189.15
      3713939.59       10155111.
#Sta/Elev= 30
  3444.6  274.59    3547  268.58  3729.8  251.88  3742.8  252.57  3768.6  251.49
  3956.2  253.11  4018.7  251.38  4143.7  252.24    4175   250.9  4656.4  249.08
  4987.7  249.75  4998.1  247.93  5004.2  244.89 5035.51249.8576  5292.9  249.43
  5633.8   252.2  5640.3  250.97  5718.5  252.22  5874.9  250.35  5938.7  251.99
  5967.4  251.84  5988.2  246.47  6002.6   246.8  6031.3  251.73  6252.4  249.91
  6370.4  254.61  6503.7  256.28  6803.9   258.4  6943.8  257.62  7215.8  261.54
#Mann= 6 ,-1 , 0
  3444.6     .11       0  3742.8     .15       0  4987.7     .09       0
 5035.51     .15       0  6503.7     .17       0  6803.9     .11       0
Bank Sta=4987.7,5035.51
XS Rating Curve= 0 ,0
Exp/Cntr=0.3,0.1

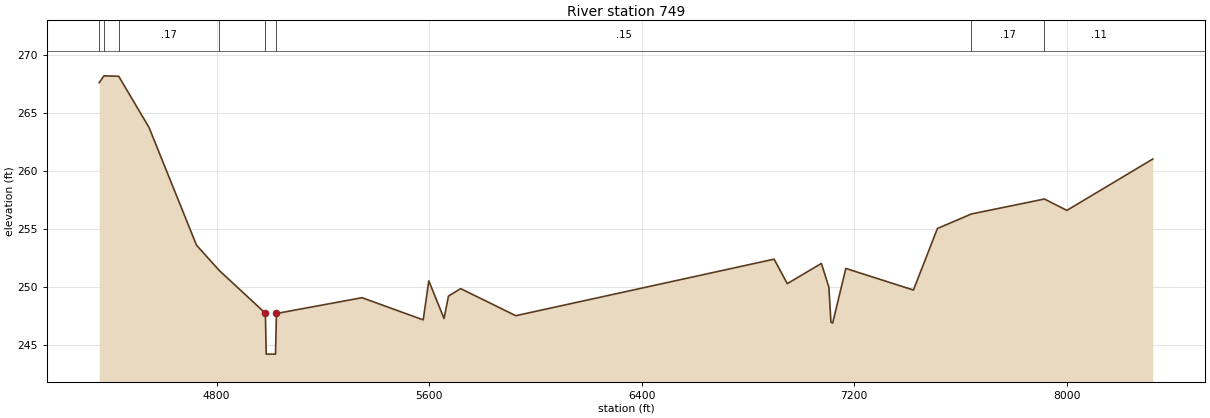
Type RM Length L Ch R = 1 ,749     ,0,0,0
BEGIN DESCRIPTION:
CCLC 115 1.0
END DESCRIPTION:
XS GIS Cut Line= 6
      3716673.93     10154454.74      3716245.78     10153842.96
      3715423.95     10153564.15      3714742.85     10153636.07
      3714309.37     10154168.32      3713919.48     10155067.67
#Sta/Elev= 30
    4358   267.6  4375.7  268.19  4431.4  268.15  4545.6  263.74  4724.3   253.6
  4810.1  251.42 4983.59247.7432  4986.7  244.22  5021.7  244.22  5025.1  247.72
  5347.4  249.08  5577.7  247.17  5598.8  250.53  5656.1  247.29  5672.8  249.22
  5718.9  249.86  5926.2  247.53  6898.7   252.4  6948.3  250.29  7076.6  252.03
  7104.8     250  7112.7  246.96  7119.2   246.9  7168.7   251.6  7423.2  249.74
  7513.5  255.04  7641.3  256.29  7916.4  257.58  8000.8   256.6  8324.1  261.02
#Mann= 8 ,-1 , 0
    4358     .17       0  4375.7     .11       0  4431.4     .17       0
  4810.1     .15       0 4983.59     .09       0  5025.1     .15       0
  7641.3     .17       0  7916.4     .11       0
Bank Sta=4983.59,5025.1
XS Rating Curve= 0 ,0
Exp/Cntr=0.3,0.1

Chan Stop Cuts=-1
Use User Specified Reach Order=0
Composite Channel Slope=5