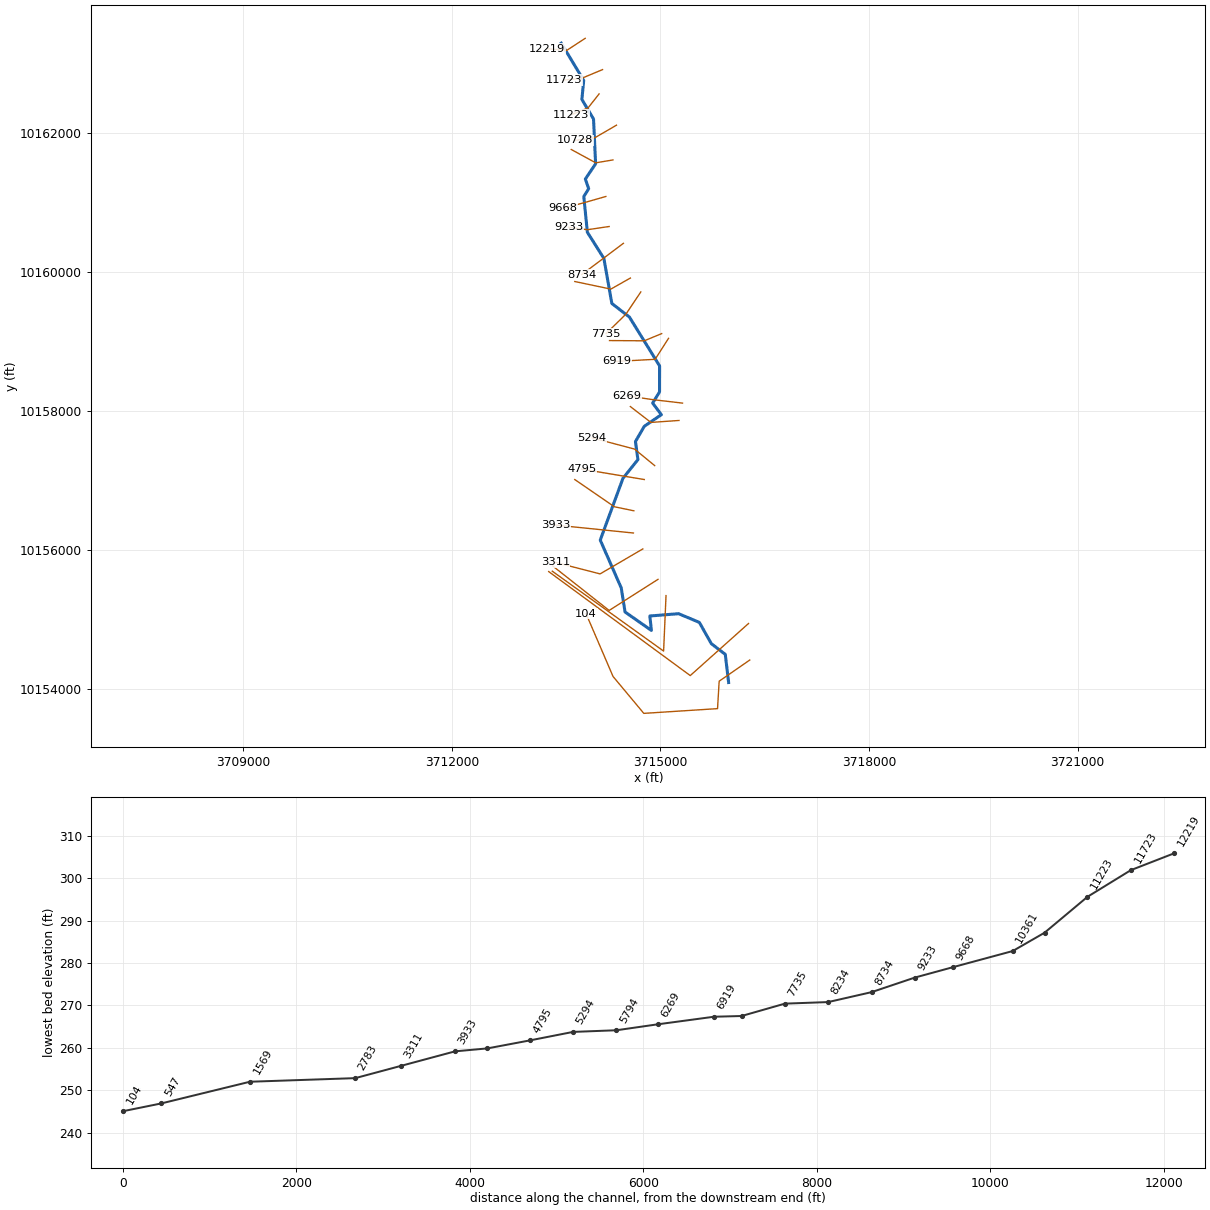
--- CCLC 116.prj (project) ---

Proj Title=CCLC 116 Base Level Engineering
Current Plan=p01
Default Exp/Contr=0.3,0.1
English Units
Geom File=g01
Flow File=f01
Flow File=f02
Plan File=p01
Y Axis Title=Elevation
X Axis Title(PF)=Main Channel Distance
X Axis Title(XS)=Station
BEGIN DESCRIPTION:
CCLC 116
END DESCRIPTION:
DSS File=dss
DSS Export Rating Curves= 0
DSS Export Rating Curve Sorted= 0
DSS Export Volume Flow Curves= 0
DXF OffsetX= 0
DXF OffsetY= 0
DXF ScaleX= 1
DXF ScaleY= 10

--- CCLC 116.p01 (plan) ---

Plan Title=Multiple Run
Program Version=4.10
Short Identifier=Multiple Run
Geom File=g01
Flow File=f01
Subcritical Flow
K Sum by GR= 0
Std Step Tol= 0.01
Critical Tol= 0.01
Num of Std Step Trials= 20
Max Error Tol= 0.3
Flow Tol Ratio= 0.001
Split Flow NTrial= 30
Split Flow Tol= 0.02
Split Flow Ratio= 0.02
Log Output Level= 0
Friction Slope Method= 1
Unsteady Friction Slope Method= 2
Unsteady Bridges Friction Slope Method= 1
Parabolic Critical Depth
Global Vel Dist= 1 , 1 , 1
Global Log Level= 0
CheckData=True
Encroach Param=-1 ,0,0, 0
BEGIN DESCRIPTION:
Multiple Run
END DESCRIPTION:
Computation Interval=1HOUR
Output Interval=1HOUR
Run HTab= 0
Run UNet= 0
Run PostProcess= 0
Run WQNet= 0
UNET Theta= 1
UNET Theta Warmup= 1
UNET ZTol= 0.02
UNET ZSATol= 0.05
UNET MxIter= 20
UNET MaxInSteps= 0
UNET DtIC= 0
UNET DtMin= 0
UNET MaxCRTS= 20
UNET WFStab= 2
UNET SFStab= 1
UNET WFX= 1
UNET SFX= 1
UNET DSS MLevel= 4
UNET DZMax Abort= 100
UNET Convert EG Bridges= 0
UNET Use Existing IB Tables=-1
UNET Froude Reduction=False
UNET Froude Limit= 1
UNET Froude Power= 10
UNET Time Slicing=0,0, 5
UNET Junction Losses=0
Instantaneous Interval=1HOUR
DSS File=dss
Write IC File= 0
Write IC File at Sim End=0
Echo Input=False
Echo Parameters=False
Echo Output=False
Write Detailed= 0
WQ AD Non Conservative
WQ ULTIMATE=-1
WQ Max Comp Step=1HOUR
WQ Output Interval=15MIN
WQ Output Selected Increments= 0
WQ Output face flow=0
WQ Output face velocity=0
WQ Output face area=0
WQ Output face dispersion=0
WQ Output cell volume=0
WQ Output cell surface area=0
WQ Output cell continuity=0
WQ Output cumulative cell continuity=0
WQ Output face conc=0
WQ Output face dconc_dx=0
WQ Output face courant=0
WQ Output face peclet=0
WQ Output face adv mass=0
WQ Output face disp mass=0
WQ Output cell mass=0
WQ Output cell source sink temp=0
WQ Output cell source sink nsm=0
WQ Output MaxMinRange=-1
WQ Daily Max Min Mean=-1
WQ Daily Range=0
WQ Daily Time=0
WQ Create Restart=0
WQ Fixed Restart=0
WQ System Summary=0
WQ Use Fixed Temperature=0
Sorting and Armoring Iterations= 10
XS Update Threshold= 0.02
Hydraulics Update Threshold= 0.02
Energy Slope Method= 1
Volume Change Method= 0
XS Weighting Method= 0
Number of US Weighted Cross Sections= 1
Number of DS Weighted Cross Sections= 1
Upstream XS Weight=0.25
Main XS Weight=0.5
Downstream XS Weight=0.25
Number of DS XS's Weighted with US Boundary= 1
Upstream Boundary Weight= 1
Weight of XSs Associated with US Boundary= 0
Number of US XS's Weighted with DS Boundary= 1
Downstream Boundary Weight= 0.5
Weight of XSs Associated with DS Boundary= 0.5
Sediment Output Level= 4
Mass or Volume Output= 0
Output Increment Type= 1
Profile and TS Output Increment= 10
XS Output Flag= 0
XS Output Increment= 10
Disregard all LS=0
Disregard all Conn=0
Disregard all Breaches=0
Disregard all Pumps=0

--- CCLC 116.f01 (steady flow) ---

Flow Title=Multiple
Program Version=4.10
Number of Profiles= 7
Profile Names=10-year,25-year,50-year,1pct_min,100-year,1pct_plu,500-year
River Rch & RM=CCLC 116,Reach-1         ,12219
     865    1202    1651     746    2254    6807    4343
River Rch & RM=CCLC 116,Reach-1         ,6269
     922    1275    1746     786    2373    7166    4530
River Rch & RM=CCLC 116,Reach-1         ,3311
     951    1313    1797     808    2439    7366    4647
Boundary for River Rch & Prof#=CCLC 116,Reach-1         , 1
Up Type= 0
Dn Type= 3
Dn Slope=0.005
Boundary for River Rch & Prof#=CCLC 116,Reach-1         , 2
Up Type= 0
Dn Type= 3
Dn Slope=0.005
Boundary for River Rch & Prof#=CCLC 116,Reach-1         , 3
Up Type= 0
Dn Type= 3
Dn Slope=0.005
Boundary for River Rch & Prof#=CCLC 116,Reach-1         , 4
Up Type= 0
Dn Type= 3
Dn Slope=0.005
Boundary for River Rch & Prof#=CCLC 116,Reach-1         , 5
Up Type= 0
Dn Type= 3
Dn Slope=0.005
Boundary for River Rch & Prof#=CCLC 116,Reach-1         , 6
Up Type= 0
Dn Type= 3
Dn Slope=0.005
Boundary for River Rch & Prof#=CCLC 116,Reach-1         , 7
Up Type= 0
Dn Type= 3
Dn Slope=0.005
DSS Import GetInterval= 0
DSS Import GetPeak= 0
DSS Import FillOption= 0

--- CCLC 116.f02 (steady flow) ---

Flow Title=Orig_BLE_Flows
Program Version=4.10
Number of Profiles= 7
Profile Names=10-year,25-year,50-year,1pct_min,100-year,1pct_plu,500-year
River Rch & RM=CCLC 116,Reach-1         ,12219
     865    1178    1436     574    1734    5236    2525
River Rch & RM=CCLC 116,Reach-1         ,6269
     922    1250    1518     604    1825    5510    2634
River Rch & RM=CCLC 116,Reach-1         ,3311
     951    1287    1563     621    1876    5664    2702
Boundary for River Rch & Prof#=CCLC 116,Reach-1         , 1
Up Type= 0
Dn Type= 3
Dn Slope=0.005
Boundary for River Rch & Prof#=CCLC 116,Reach-1         , 2
Up Type= 0
Dn Type= 3
Dn Slope=0.005
Boundary for River Rch & Prof#=CCLC 116,Reach-1         , 3
Up Type= 0
Dn Type= 3
Dn Slope=0.005
Boundary for River Rch & Prof#=CCLC 116,Reach-1         , 4
Up Type= 0
Dn Type= 3
Dn Slope=0.005
Boundary for River Rch & Prof#=CCLC 116,Reach-1         , 5
Up Type= 0
Dn Type= 3
Dn Slope=0.005
Boundary for River Rch & Prof#=CCLC 116,Reach-1         , 6
Up Type= 0
Dn Type= 3
Dn Slope=0.005
Boundary for River Rch & Prof#=CCLC 116,Reach-1         , 7
Up Type= 0
Dn Type= 3
Dn Slope=0.005
DSS Import GetInterval= 0
DSS Import GetPeak= 0
DSS Import FillOption= 0

--- CCLC 116.g01 (geometry) ---

Geom Title=Existing Conditions
Program Version=4.10

River Reach=CCLC 116        ,Reach-1
Reach XY= 30
      3713573.23     10163291.84      3713896.44     10162755.95
      3713870.62     10162481.86      3714037.87      10162199.9
       3714067.9     10161554.91      3713920.17     10161336.05
      3713968.27     10161196.93      3713898.02     10161084.14
      3713949.12     10160570.12      3714186.64     10160194.28
      3714301.22     10159545.08       3714554.5      10159348.8
      3714988.25     10158645.87      3714987.44     10158272.06
      3714887.81     10158111.09       3715013.6     10157944.23
       3714767.6     10157776.77      3714641.17     10157558.38
       3714676.2     10157297.76      3714460.92     10157027.64
      3714134.57     10156138.97       3714436.5     10155451.01
      3714491.21      10155104.5      3714870.15     10154839.05
      3714847.86     10155046.75      3715261.24     10155080.18
      3715560.13     10154954.55      3715732.37     10154648.57
      3715932.98     10154494.56       3715981.2     10154089.62

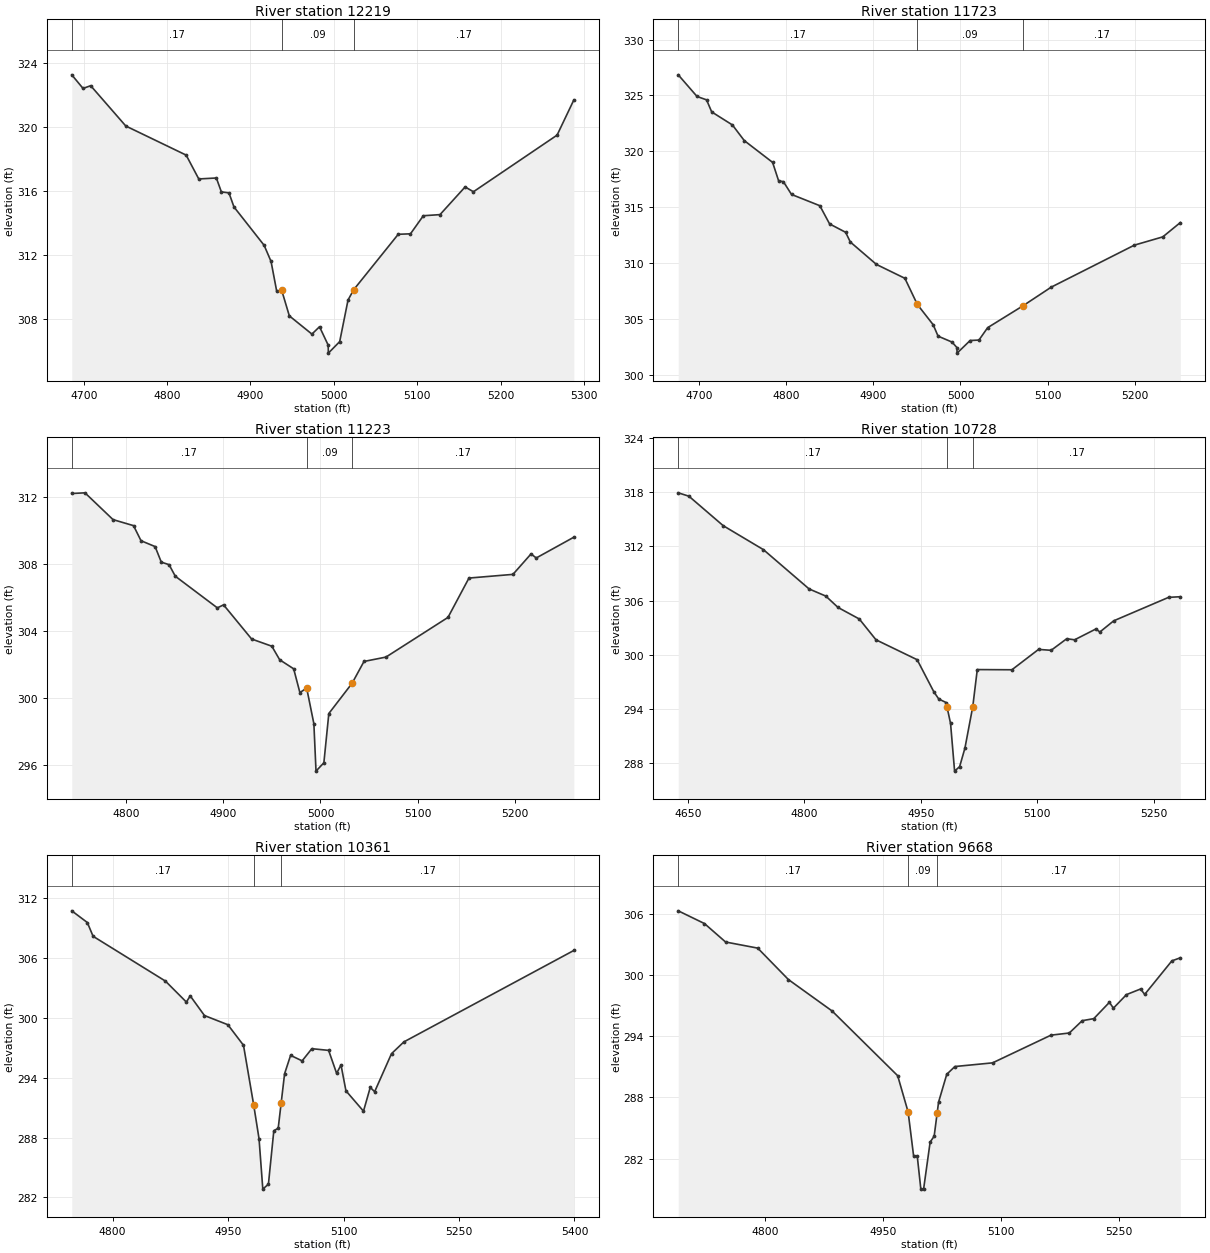
Type RM Length L Ch R = 1 ,12219   ,496,496,496
BEGIN DESCRIPTION:
CCLC 116 18.0
END DESCRIPTION:
XS GIS Cut Line= 3
      3713917.85     10163361.07       3713654.8     10163189.06
      3713367.84     10163211.07
#Sta/Elev= 30
  4685.7  323.27  4699.2  322.42  4708.4  322.59  4750.5  320.07  4822.9  318.25
    4838  316.76  4859.1  316.82  4865.1  315.95  4874.2  315.89  4880.2  315.01
  4916.4  312.61  4924.7   311.6  4931.5  309.73  4937.5  309.79  4946.6   308.2
  4973.7  307.06  4982.8  307.52  4993.2  306.37  4993.4  305.87    5007  306.59
    5017  309.19 5023.79309.8351  5077.2   313.3  5091.9  313.33  5107.3  314.46
  5127.3  314.53  5157.4  316.26  5167.4  315.96  5267.7   319.5  5287.8   321.7
#Mann= 3 , 0 , 0
  4685.7     .17       0  4937.5     .09       0 5023.79     .17       0
Bank Sta=4937.5,5023.79
XS Rating Curve= 0 ,0
Exp/Cntr=0.3,0.1

Type RM Length L Ch R = 1 ,11723   ,500,500,500
BEGIN DESCRIPTION:
CCLC 116 17.0
END DESCRIPTION:
XS GIS Cut Line= 3
      3714167.82     10162911.06      3713868.94     10162786.22
       3713617.9     10162761.08
#Sta/Elev= 30
  4676.1  326.84  4697.7   324.9  4708.6   324.6  4714.5  323.52  4738.3  322.35
  4751.9  320.95  4784.4     319  4791.3  317.35  4796.8  317.27  4806.1  316.13
  4838.6  315.12  4849.8  313.49  4868.2  312.74  4873.6  311.87  4903.6  309.86
  4936.2  308.62  4950.5  306.28  4968.7  304.46  4974.3  303.44  4990.3  302.91
  4995.9  302.42  4996.1  301.92  5011.1  303.05  5021.2  303.09  5031.2   304.2
  5071.4  306.14  5104.2  307.83  5199.6  311.59  5232.2  312.33  5252.3  313.61
#Mann= 3 , 0 , 0
  4676.1     .17       0  4950.5     .09       0  5071.4     .17       0
Bank Sta=4950.5,5071.4
XS Rating Curve= 0 ,0
Exp/Cntr=0.3,0.1

Type RM Length L Ch R = 1 ,11223   ,495,495,495
BEGIN DESCRIPTION:
CCLC 116 16.0
END DESCRIPTION:
XS GIS Cut Line= 3
      3714117.84     10162561.06      3713959.33     10162359.91
      3713717.87     10162261.08
#Sta/Elev= 30
  4743.9  312.21  4757.5  312.25  4786.4  310.65  4807.5  310.29  4815.2  309.39
  4829.7  309.04  4836.1  308.11  4844.1  307.96  4850.5  307.27  4893.8  305.38
  4900.2  305.56  4929.1  303.52  4949.9  303.09    4958  302.28  4972.4  301.74
  4978.8  300.32  4985.8  300.59  4993.2  298.46  4995.4  295.63  5003.5  296.13
  5008.6  299.07  5032.6  300.88  5044.8  302.18  5067.4  302.44  5131.3  304.81
  5152.9  307.16  5198.2  307.38  5216.8   308.6  5222.2  308.36  5260.9   309.6
#Mann= 3 , 0 , 0
  4743.9     .17       0  4985.8     .09       0  5032.6     .17       0
Bank Sta=4985.8,5032.6
XS Rating Curve= 0 ,0
Exp/Cntr=0.3,0.1

Type RM Length L Ch R = 1 ,10728   ,367,367,367
BEGIN DESCRIPTION:
CCLC 116 15.0
END DESCRIPTION:
XS GIS Cut Line= 3
      3714367.89      10162111.1      3714054.61     10161929.12
      3713772.91     10161892.28
#Sta/Elev= 30
  4637.7   317.9  4651.4  317.53  4695.6  314.27  4747.4  311.62  4806.2  307.28
  4827.7  306.49  4843.5  305.23  4870.8  303.96  4892.3  301.66  4945.3  299.46
  4966.8  295.91  4973.1  295.12  4982.5  294.73 4983.81294.2082  4988.3  292.42
  4993.5  287.15    5000  287.65  5006.8  289.69  5016.9  294.28  5022.7  298.37
  5067.3  298.35  5101.6   300.6  5117.8   300.5  5137.9  301.78    5148  301.66
  5175.5  302.86  5180.5  302.52  5198.4  303.76    5269  306.35  5284.1  306.42
#Mann= 3 , 0 , 0
  4637.7     .17       0 4983.81     .09       0  5016.9     .17       0
Bank Sta=4983.81,5016.9
XS Rating Curve= 0 ,0
Exp/Cntr=0.3,0.1

Type RM Length L Ch R = 1 ,10361   ,693,693,693
BEGIN DESCRIPTION:
CCLC 116 14.0
END DESCRIPTION:
XS GIS Cut Line= 3
      3714317.82     10161611.07      3714069.79     10161569.36
      3713717.83     10161761.08
#Sta/Elev= 30
  4746.9  310.71  4767.1  309.54  4774.6  308.16  4868.6  303.67  4895.8  301.57
  4900.8  302.19  4919.3  300.22  4949.7   299.3    4970  297.24 4983.21291.2851
  4990.2  287.88  4995.1  282.83  5002.4  283.33  5009.4  288.68  5015.1  288.93
  5018.9291.4297  5023.4  294.39  5031.2  296.23  5046.2  295.68  5058.8   296.9
  5080.6  296.73    5091  294.43  5096.7  295.27  5103.1  292.68  5125.9  290.64
  5134.7  293.02  5140.4  292.59  5162.3   296.4  5178.4  297.58  5399.2  306.74
#Mann= 3 , 0 , 0
  4746.9     .17       0 4983.21     .09       0  5018.9     .17       0
Bank Sta=4983.21,5018.9
XS Rating Curve= 0 ,0
Exp/Cntr=0.3,0.1

Type RM Length L Ch R = 1 ,9668    ,435,435,435
BEGIN DESCRIPTION:
CCLC 116 13.0
END DESCRIPTION:
XS GIS Cut Line= 3
      3714215.63     10161084.99      3713923.95     10161001.65
      3713601.98     10160913.37
#Sta/Elev= 30
  4690.2  306.31  4723.5  305.06  4750.3  303.25  4791.1  302.65  4830.1  299.56
  4885.5  296.48  4968.7  290.13 4981.97286.5664  4988.9  282.27  4993.5  282.27
  4998.1     279  5001.6     279  5009.9  283.62    5015  284.19 5018.82 286.475
  5020.6  287.54    5031  290.27  5041.3  291.03  5089.1  291.39  5163.3  294.11
  5186.5  294.32  5202.9  295.53  5217.6  295.73  5237.4  297.33  5242.5  296.76
  5259.1  298.09    5277  298.64  5282.2  298.11  5316.7   301.4  5327.4   301.7
#Mann= 3 , 0 , 0
  4690.2     .17       0 4981.97     .09       0 5018.82     .17       0
Bank Sta=4981.97,5018.82
XS Rating Curve= 0 ,0
Exp/Cntr=0.3,0.1

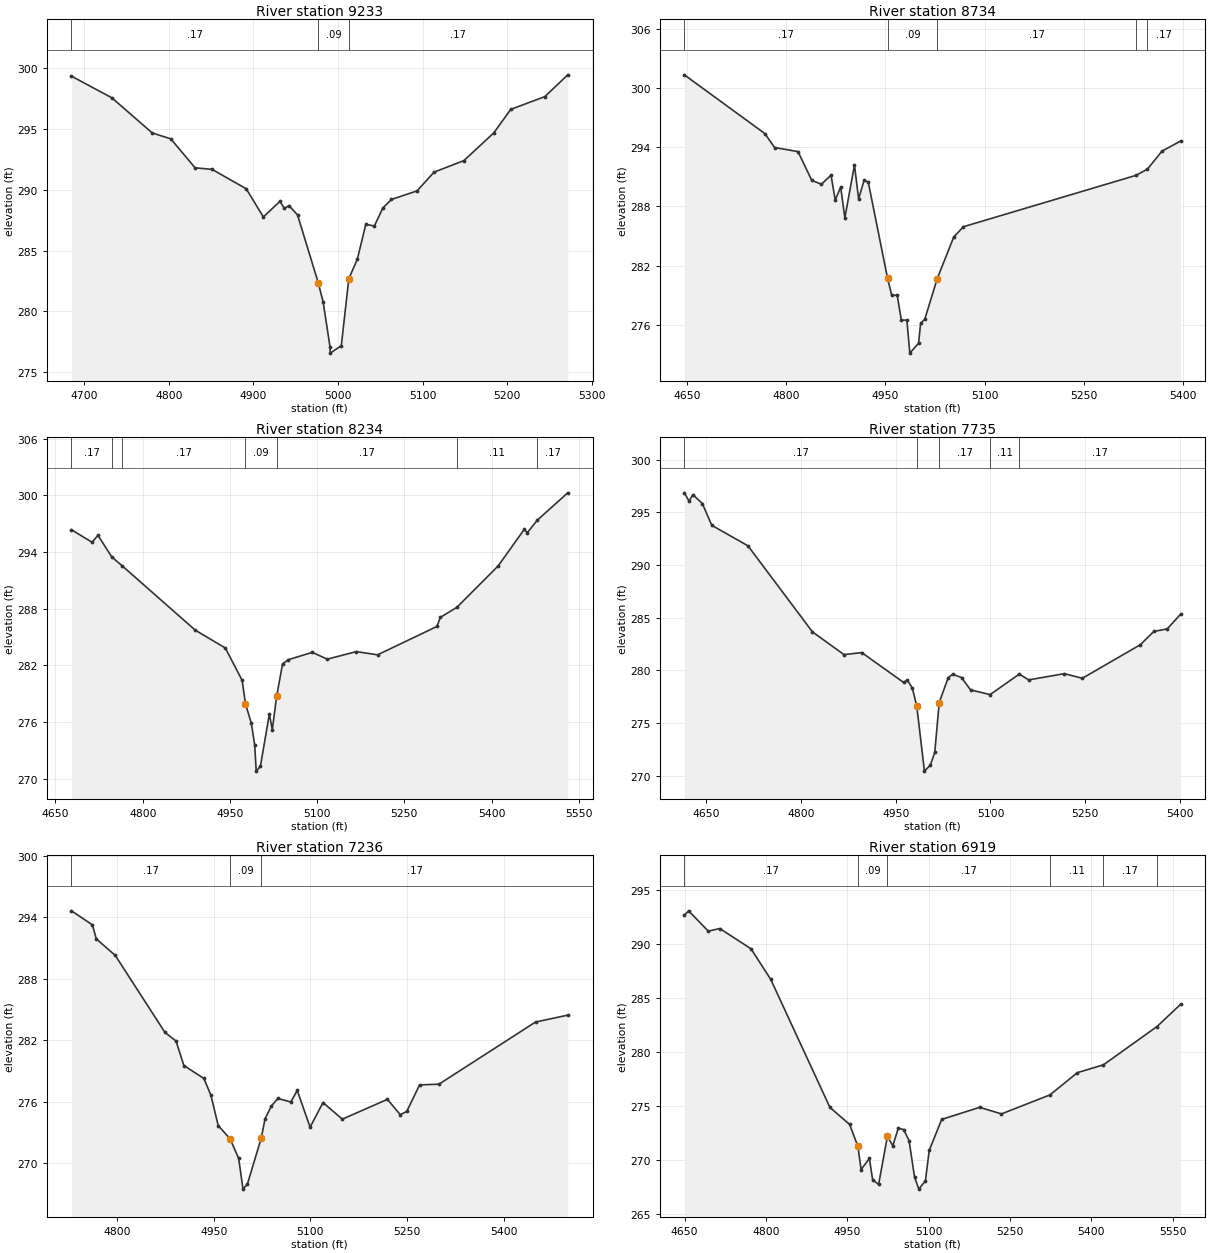
Type RM Length L Ch R = 1 ,9233    ,499,499,499
BEGIN DESCRIPTION:
CCLC 116 12.0
END DESCRIPTION:
XS GIS Cut Line= 3
      3714262.45     10160652.69      3713950.51     10160606.74
      3713681.01     10160642.03
#Sta/Elev= 30
  4684.7  299.33  4732.5  297.55  4780.3  294.66  4802.2  294.18  4830.9   291.8
  4851.1  291.67  4891.5  290.07  4911.7  287.76  4931.4  289.05  4936.5  288.46
    4942  288.69  4952.1  287.93  4976.6282.3639  4982.5  280.74  4990.6  277.07
  4990.8  276.57  5003.9  277.18  5012.8  282.68  5022.9   284.3  5032.9  287.15
    5043  287.02  5053.1   288.5  5063.2   289.2  5093.5   289.9  5113.6  291.44
  5148.9  292.39  5184.2  294.66  5204.4   296.6  5244.7  297.65  5271.8  299.44
#Mann= 3 , 0 , 0
  4684.7     .17       0  4976.6     .09       0  5012.8     .17       0
Bank Sta=4976.6,5012.8
XS Rating Curve= 0 ,0
Exp/Cntr=0.3,0.1

Type RM Length L Ch R = 1 ,8734    ,500,500,500
BEGIN DESCRIPTION:
CCLC 116 11.0
END DESCRIPTION:
XS GIS Cut Line= 3
      3714467.81     10160411.04      3714184.89     10160198.28
      3713867.82     10159961.04
#Sta/Elev= 30
    4646  301.34  4767.8  295.38  4782.4  293.97  4817.8  293.56  4838.6  290.64
  4853.2  290.25  4867.7  291.17    4874  288.65  4882.3  289.96  4888.6  286.84
  4903.1  292.19  4909.4  288.77  4917.7  290.65    4924  290.45  4953.1  280.72
  4959.4  279.01  4967.7  278.99    4974  276.47  4982.3  276.48  4986.8  273.13
    5000  274.14  5003.1  276.15  5009.4  276.57 5028.12280.6692  5053.1  284.89
  5067.7  285.94  5328.6  291.15  5345.9  291.78  5367.8   293.6    5396  294.63
#Mann= 5 ,-1 , 0
    4646     .17       0  4953.1     .09       0 5028.12     .17       0
  5328.6     .11       0  5345.9     .17       0
Bank Sta=4953.1,5028.12
XS Rating Curve= 0 ,0
Exp/Cntr=0.3,0.1

Type RM Length L Ch R = 1 ,8234    ,499,499,499
BEGIN DESCRIPTION:
CCLC 116 10.0
END DESCRIPTION:
XS GIS Cut Line= 3
      3714567.89      10159911.1      3714287.46     10159751.84
      3713767.82     10159861.08
#Sta/Elev= 30
  4677.5  296.36  4712.9  295.03    4723  295.77  4746.9  293.47  4764.1  292.57
  4890.2  285.73  4942.1  283.83    4971  280.41  4976.7  277.94  4986.9  275.84
  4992.6  273.56  4995.2  270.79  5002.4  271.29  5017.8  276.83  5022.9  275.17
  5030.3   278.7  5040.5  282.14  5050.7   282.6  5091.6  283.37  5117.5  282.65
  5167.3  283.45    5204  283.11  5306.2  286.12  5311.7  287.07  5340.3  288.14
  5411.4  292.53  5456.2   296.4  5461.3  296.04  5478.9  297.39    5531  300.27
#Mann= 7 ,-1 , 0
  4677.5     .17       0  4746.9     .11       0  4764.1     .17       0
  4976.7     .09       0  5030.3     .17       0  5340.3     .11       0
  5478.9     .17       0
Bank Sta=4976.7,5030.3
XS Rating Curve= 0 ,0
Exp/Cntr=0.3,0.1

Type RM Length L Ch R = 1 ,7735    ,499,499,499
BEGIN DESCRIPTION:
CCLC 116 9.0
END DESCRIPTION:
XS GIS Cut Line= 3
      3714717.83     10159711.04      3714504.21     10159391.46
      3714217.83     10159111.05
#Sta/Elev= 30
  4615.6  296.86  4623.1  296.07  4629.1  296.69  4644.1  295.84  4659.1  293.77
  4716.2  291.83  4818.3  283.65  4868.2  281.49  4896.4  281.68  4962.4  278.85
  4968.4  279.06  4976.4  278.31  4983.4  276.57  4995.5  270.42  5004.8  270.99
  5011.8  272.19  5018.9  276.94  5033.1   279.3  5040.1  279.62  5054.2  279.31
  5068.4  278.14  5099.4  277.69  5145.6  279.64  5160.4  279.09    5217  279.68
  5245.3  279.24  5337.1  282.43  5358.4  283.69  5379.6  283.93  5400.8  285.33
#Mann= 5 ,-1 , 0
  4615.6     .17       0  4983.4     .09       0  5018.9     .17       0
  5099.4     .11       0  5145.6     .17       0
Bank Sta=4983.4,5018.9
XS Rating Curve= 0 ,0
Exp/Cntr=0.3,0.1

Type RM Length L Ch R = 1 ,7236    ,317,317,317
BEGIN DESCRIPTION:
CCLC 116 8.0
END DESCRIPTION:
XS GIS Cut Line= 3
      3715017.87     10159111.08      3714767.33     10159007.77
      3714267.84     10159011.07
#Sta/Elev= 30
    4729  294.63  4761.5  293.26  4767.6  291.89    4797  290.28  4874.2  282.77
  4891.3  281.94  4903.5  279.55  4934.5  278.29  4945.4  276.67  4956.8   273.7
  4975.3   272.4  4988.6  270.49  4995.3   267.5  5002.2     268 5023.79272.5157
  5029.5  274.36  5039.5  275.61  5049.5  276.34  5069.5  275.99  5079.5  277.12
  5099.5  273.54  5119.5  275.94  5149.5  274.32  5219.5  276.25  5239.5  274.76
  5249.5  275.07  5269.5  277.66  5299.5  277.73  5449.5  283.79  5499.5  284.46
#Mann= 3 , 0 , 0
    4729     .17       0  4975.3     .09       0 5023.79     .17       0
Bank Sta=4975.3,5023.79
XS Rating Curve= 0 ,0
Exp/Cntr=0.3,0.1

Type RM Length L Ch R = 1 ,6919    ,650,650,650
BEGIN DESCRIPTION:
CCLC 116 7.0
END DESCRIPTION:
XS GIS Cut Line= 3
      3715116.67     10159043.33      3714923.95     10158741.24
       3714367.9     10158711.07
#Sta/Elev= 30
  4649.4  292.66  4657.3  293.08  4693.6   291.2  4714.8  291.44  4772.3  289.57
  4808.7  286.74  4917.9  274.89  4954.3  273.31  4969.5  271.28  4975.4  269.14
  4990.7  270.17  4996.6  268.21  5007.7  267.76  5023.9  272.22  5033.9  271.34
  5043.9  272.96  5053.9  272.84  5063.9  271.82  5073.9  268.45  5081.9  267.33
    5094   268.1    5101  270.91    5124  273.78  5194.1   274.9  5234.2  274.29
  5323.7  276.05  5374.4  278.11  5422.3  278.83    5521  282.37  5564.6  284.43
#Mann= 6 ,-1 , 0
  4649.4     .17       0  4969.5     .09       0  5023.9     .17       0
  5323.7     .11       0  5422.3     .17       0    5521     .11       0
Bank Sta=4969.5,5023.9
XS Rating Curve= 0 ,0
Exp/Cntr=0.3,0.1

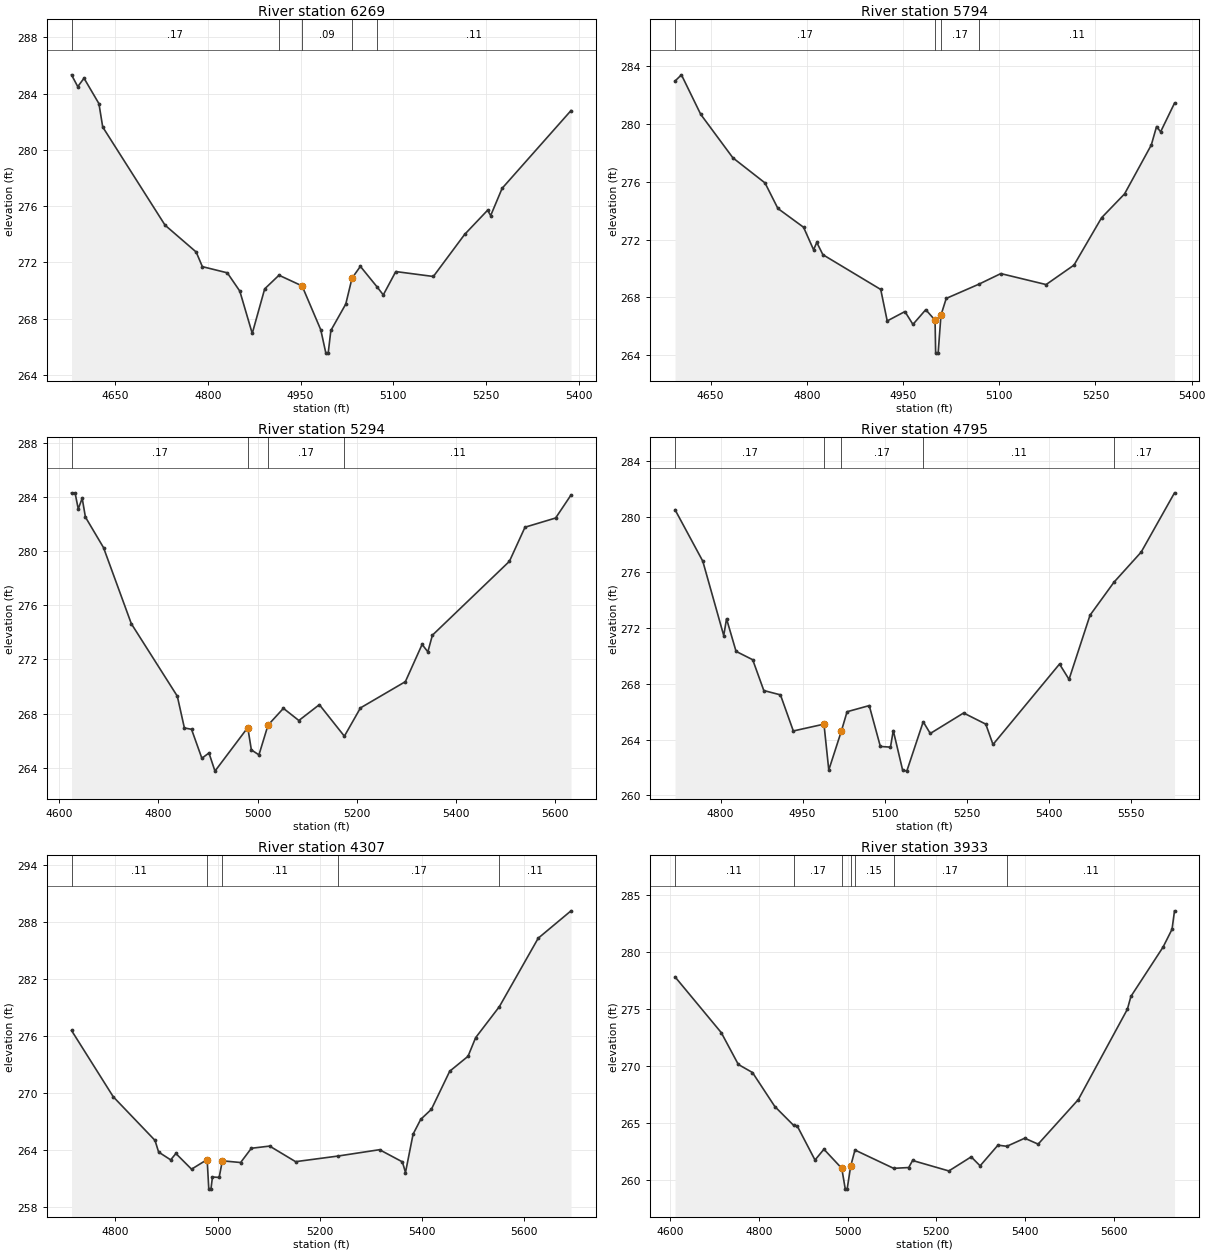
Type RM Length L Ch R = 1 ,6269    ,475,475,475
BEGIN DESCRIPTION:
CCLC 116 6.0
END DESCRIPTION:
XS GIS Cut Line= 3
      3715317.89     10158111.07      3714900.61     10158159.61
      3714517.72     10158215.19
#Sta/Elev= 30
  4579.9  285.33    4590  284.49  4600.1  285.09  4624.2  283.28  4630.3  281.62
    4731  274.64  4781.3  272.73  4791.3  271.69  4831.6  271.25  4851.8  269.95
  4871.9  266.94    4892  270.11  4915.1  271.08  4952.4  270.32  4982.6   267.2
  4990.8  265.54  4994.6  265.54  4998.9  267.15    5023  269.03  5033.1  270.87
  5046.6  271.71  5074.1  270.22  5083.6  269.68  5103.8  271.34  5164.5  270.99
    5215  273.98  5252.1   275.7  5257.1  275.32  5275.6  277.26  5386.9  282.79
#Mann= 5 ,-1 , 0
  4579.9     .17       0  4915.1     .15       0  4952.4     .09       0
  5033.1     .15       0  5074.1     .11       0
Bank Sta=4952.4,5033.1
XS Rating Curve= 0 ,0
Exp/Cntr=0.3,0.1

Type RM Length L Ch R = 1 ,5794    ,500,500,500
BEGIN DESCRIPTION:
CCLC 116 5.0
END DESCRIPTION:
XS GIS Cut Line= 3
      3715267.82     10157861.07      3714863.39     10157832.99
      3714567.86     10158061.06
#Sta/Elev= 30
  4594.6  282.99  4604.6  283.42  4634.7  280.68  4684.8  277.67  4734.9  275.93
    4755  274.16    4795  272.86  4810.6   271.3  4815.6  271.81  4825.1  270.96
  4915.3  268.55  4925.4  266.37    4953  267.02  4965.5  266.13  4985.5  267.15
    5000  266.42  5000.9  264.14  5004.8  264.14  5009.2  266.77  5017.4  267.93
  5068.5  268.92  5102.5  269.65  5173.1  268.89  5216.6  270.24  5259.6  273.52
  5295.4  275.17  5337.1  278.56  5345.3  279.84  5351.6  279.47  5373.3  281.46
#Mann= 4 ,-1 , 0
  4594.6     .17       0    5000     .09       0  5009.2     .17       0
  5068.5     .11       0
Bank Sta=5000,5009.2
XS Rating Curve= 0 ,0
Exp/Cntr=0.3,0.1

Type RM Length L Ch R = 1 ,5294    ,499,499,499
BEGIN DESCRIPTION:
CCLC 116 4.0
END DESCRIPTION:
XS GIS Cut Line= 3
      3714917.83     10157211.09      3714628.12     10157449.05
      3714017.87     10157611.07
#Sta/Elev= 30
  4625.1   284.3  4632.2  284.31  4638.7  283.12  4646.6  283.91  4653.1  282.52
  4689.6  280.26  4745.6  274.64  4838.2  269.29  4852.5  266.94  4866.9  266.84
  4887.7   264.7    4902  265.09  4914.1  263.75  4980.2  266.97  4987.4  265.32
  5002.7  264.95    5021  267.15    5052  268.39  5083.1  267.49  5124.4  268.66
  5174.8  266.33  5207.2  268.42  5297.7  270.36  5331.4  273.11    5343  272.56
  5352.1  273.79  5507.3  279.25  5538.7  281.77  5600.4  282.45  5631.4  284.15
#Mann= 4 ,-1 , 0
  4625.1     .17       0  4980.2     .09       0    5021     .17       0
  5174.8     .11       0
Bank Sta=4980.2,5021
XS Rating Curve= 0 ,0
Exp/Cntr=0.3,0.1

Type RM Length L Ch R = 1 ,4795    ,488,488,488
BEGIN DESCRIPTION:
CCLC 116 3.0
END DESCRIPTION:
XS GIS Cut Line= 3
      3714767.89     10157011.07      3714488.59     10157057.31
      3713867.81     10157161.08
#Sta/Elev= 30
  4716.9  280.49  4767.6   276.8  4805.9  271.46    4811  272.67  4828.4  270.33
  4858.8  269.73  4879.1  267.52  4909.5  267.21    4933  264.62    4989  265.11
  4997.8  261.82    5021  264.64  5031.2     266  5071.7  266.44    5092  263.51
  5110.5  263.46  5115.6  264.65  5132.6  261.83  5140.3  261.74  5170.3  265.28
  5183.2  264.44  5244.1  265.91  5284.6  265.11  5297.8  263.65  5419.3  269.42
  5436.7  268.32    5475  272.92  5518.8  275.29  5568.5  277.45  5629.4   281.7
#Mann= 5 ,-1 , 0
  4716.9     .17       0    4989     .09       0    5021     .17       0
  5170.3     .11       0  5518.8     .17       0
Bank Sta=4989,5021
XS Rating Curve= 0 ,0
Exp/Cntr=0.3,0.1

Type RM Length L Ch R = 1 ,4307    ,374,374,374
BEGIN DESCRIPTION:
CCLC 116 2.0
END DESCRIPTION:
XS GIS Cut Line= 3
      3714617.87     10156561.07      3714337.82     10156619.11
      3713767.88     10157011.05
#Sta/Elev= 30
    4714  276.56  4795.7  269.58  4877.4  264.99  4884.5  263.76  4908.1  262.94
  4918.3  263.61  4948.9  261.96  4979.5  262.97  4982.7  259.86  4986.9  259.86
  4989.9  261.14    5003  261.09  5009.2  262.84    5045  262.66    5066  264.16
  5101.8  264.39  5152.6  262.75  5235.4  263.34  5316.9  264.01  5361.6  262.73
  5367.7  261.61  5382.6  265.65  5397.5   267.2  5418.4  268.26  5454.3  272.27
  5490.1  273.84    5505   275.8  5551.5  279.07  5627.5  286.27  5691.7  289.15
#Mann= 5 ,-1 , 0
    4714     .11       0  4979.5     .07       0  5009.2     .11       0
  5235.4     .17       0  5551.5     .11       0
Bank Sta=4979.5,5009.2
XS Rating Curve= 0 ,0
Exp/Cntr=0.3,0.1

Type RM Length L Ch R = 1 ,3933    ,622,622,622
BEGIN DESCRIPTION:
Mapping XS b30d6951
END DESCRIPTION:
XS GIS Cut Line= 2
      3714611.49     10156241.23      3713492.23     10156355.76
#Sta/Elev= 30
  4611.4  277.84  4715.6  272.93    4754  270.13  4785.9  269.42  4836.2  266.43
  4878.3  264.78  4886.5  264.73  4926.7  261.72  4946.8  262.67    4987  260.99
  4994.9  259.16  4999.1  259.16  5007.1  261.19  5016.7   262.6  5103.8  260.99
  5137.8  261.06  5146.5  261.68  5228.2  260.76  5278.5     262  5298.6  261.21
  5338.8  263.03  5358.8  262.93  5399.1  263.64  5429.3  263.12  5519.8  267.04
  5630.3  274.99  5638.3  276.12  5710.7  280.46  5730.9  282.03  5736.5  283.65
#Mann= 7 ,-1 , 0
  4611.4     .11       0  4878.3     .17       0    4987     .09       0
  5007.1     .17       0  5016.7     .15       0  5103.8     .17       0
  5358.8     .11       0
Bank Sta=4987,5007.1
XS Rating Curve= 0 ,0
Exp/Cntr=0.3,0.1

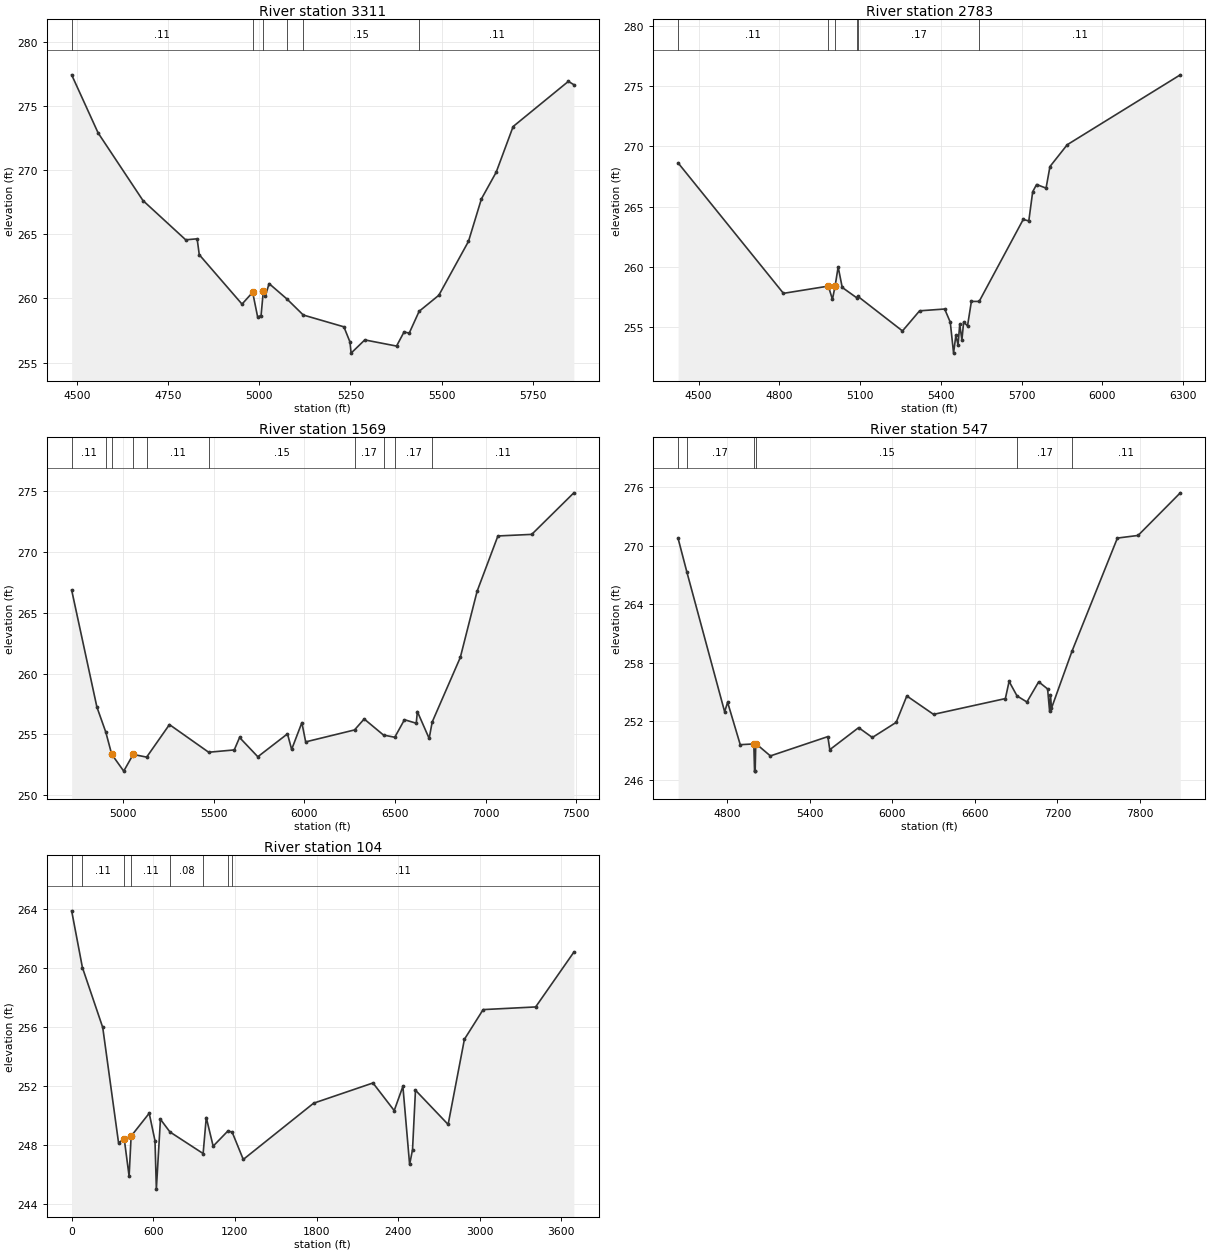
Type RM Length L Ch R = 1 ,3311    ,528,528,528
BEGIN DESCRIPTION:
Mapping XS 335b9fdb
END DESCRIPTION:
XS GIS Cut Line= 3
      3714746.87     10156012.07      3714132.29     10155652.69
      3713486.48     10155819.35
#Sta/Elev= 30
  4484.4  277.43  4557.1   272.9  4680.3  267.63  4797.6  264.57    4829  264.65
  4834.8  263.41  4952.2  259.56  4981.4  260.48  4995.1  258.56  5004.5  258.67
  5010.8  260.61  5016.6  260.22  5026.5  261.16  5075.5  259.96  5120.4  258.71
  5231.9  257.79  5248.6  256.61  5251.7  255.74  5289.3  256.77  5376.5  256.29
  5397.1  257.39  5411.3   257.3  5438.5     259  5492.6  260.25    5574  264.45
  5609.5  267.76  5650.1  269.84  5696.6   273.4  5848.3  276.92  5863.3  276.66
#Mann= 6 ,-1 , 0
  4484.4     .11       0  4981.4     .07       0  5010.8     .15       0
  5075.5     .11       0  5120.4     .15       0  5438.5     .11       0
Bank Sta=4981.4,5010.8
XS Rating Curve= 0 ,0
Exp/Cntr=0.3,0.1

Type RM Length L Ch R = 1 ,2783    ,1214,1214,1214
BEGIN DESCRIPTION:
Mapping XS cf584817
END DESCRIPTION:
XS GIS Cut Line= 3
      3714965.63     10155574.58      3714262.49     10155126.65
      3713452.17     10155765.56
#Sta/Elev= 30
    4424  268.62  4815.3   257.8  4982.1   258.4  4997.3   257.3 5007.24  258.41
  5018.5  259.99  5033.7  258.29    5087  257.44  5091.3  257.56  5257.5  254.68
  5321.1  256.35  5414.2   256.5    5435  255.41  5447.3  252.84  5455.8  254.31
  5463.9  253.53  5470.2  255.22  5478.3  253.94  5484.7  255.42  5499.1   255.1
  5513.5  257.13  5542.4  257.13    5706  263.93  5726.8  263.81  5741.2  266.23
  5755.7  266.83  5790.9  266.53  5805.4  268.32  5869.5  270.13  6289.6  275.93
#Mann= 6 ,-1 , 0
    4424     .11       0  4982.1     .07       0 5007.24     .17       0
    5087     .11       0  5091.3     .17       0  5542.4     .11       0
Bank Sta=4982.1,5007.24
XS Rating Curve= 0 ,0
Exp/Cntr=0.3,0.1

Type RM Length L Ch R = 1 ,1569    ,1022,1022,1022
BEGIN DESCRIPTION:
Mapping XS 400a9585
END DESCRIPTION:
XS GIS Cut Line= 3
      3715080.69     10155340.21      3715045.97     10154541.64
      3713444.41     10155691.81
#Sta/Elev= 30
  4715.5  266.85  4854.8  257.25  4903.9  255.19 4936.46253.3757  5002.8  251.99
    5055  253.36  5129.4  253.14  5255.1  255.81  5471.6  253.54  5612.7  253.73
  5642.1  254.75  5742.8  253.17  5906.5  255.05  5929.4  253.77  5985.9  255.97
  6006.8  254.39  6276.4  255.37  6329.7  256.27  6436.3  254.95  6498.6  254.77
  6551.9  256.21    6617  255.92  6623.2  256.88  6688.2  254.67    6705  256.02
  6860.1  261.32    6953  266.76  7067.6  271.29  7254.3  271.42  7486.6  274.83
#Mann= 10 ,-1 , 0
  4715.5     .11       0  4903.9     .15       0 4936.46     .07       0
    5055     .15       0  5129.4     .11       0  5471.6     .15       0
  6276.4     .17       0  6436.3     .11       0  6498.6     .17       0
    6705     .11       0
Bank Sta=4936.46,5055
XS Rating Curve= 0 ,0
Exp/Cntr=0.3,0.1

Type RM Length L Ch R = 1 ,547     ,443,443,443
BEGIN DESCRIPTION:
CCLC 116 1.0
END DESCRIPTION:
XS GIS Cut Line= 3
       3716267.7     10154939.15      3715429.16     10154189.15
      3713392.87     10155686.05
#Sta/Elev= 30
  4441.8  270.73  4505.6  267.28  4780.1  252.96  4801.8  253.93  4893.7  249.58
  4992.4  249.66  4997.7  246.87  5002.1  246.87  5006.6   249.7  5112.8  248.43
  5530.7  250.41  5544.9  249.07  5754.6  251.33  5854.4  250.32  6027.7  251.87
  6105.1  254.58  6299.5  252.69  6821.8  254.31  6848.9  256.07  6906.8  254.58
  6978.5  253.96  7064.1  256.03  7128.9   255.3  7143.6  253.01  7149.8  254.71
  7157.1  253.32  7306.2  259.16  7636.6  270.77    7787  271.04  8094.1  275.41
#Mann= 6 ,-1 , 0
  4441.8     .11       0  4505.6     .17       0  4992.4     .07       0
  5006.6     .15       0  6906.8     .17       0  7306.2     .11       0
Bank Sta=4992.4,5006.6
XS Rating Curve= 0 ,0
Exp/Cntr=0.3,0.1

Type RM Length L Ch R = 1 ,104     ,0,0,0
BEGIN DESCRIPTION:
CCLC 116 0.5
END DESCRIPTION:
XS GIS Cut Line= 6
      3716285.16     10154413.01      3715845.05     10154108.32
      3715821.82     10153713.64      3714761.17     10153645.26
      3714318.47     10154176.51      3713930.44     10155080.16
#Sta/Elev= 30
       0  263.88    79.1  260.04   228.5  255.98   344.7  248.17   386.6  248.43
   422.4   245.9   437.2  248.62   570.2  250.17   612.7   248.3   622.7  245.03
   652.7  249.76   722.9   248.9   966.5  247.44   989.5  249.88  1040.2  247.94
  1147.7  248.96  1179.4   248.9  1261.6  247.04  1778.7  250.85    2215  252.22
  2371.2  250.35    2435  251.99  2484.4   246.7  2505.8   247.7  2527.4  251.73
  2767.5  249.41  2887.2  255.18  3024.9  257.19  3410.9  257.37  3691.6  261.08
#Mann= 8 ,-1 , 0
       0     .11       0    79.1     .11       0   386.6     .06       0
   437.2     .11       0   722.9     .08       0   966.5     .11       0
  1147.7     .11       0  1179.4     .11       0
Bank Sta=386.6,437.2
XS Rating Curve= 0 ,0
Exp/Cntr=0.3,0.1

Chan Stop Cuts=-1
Use User Specified Reach Order=0
Composite Channel Slope=5