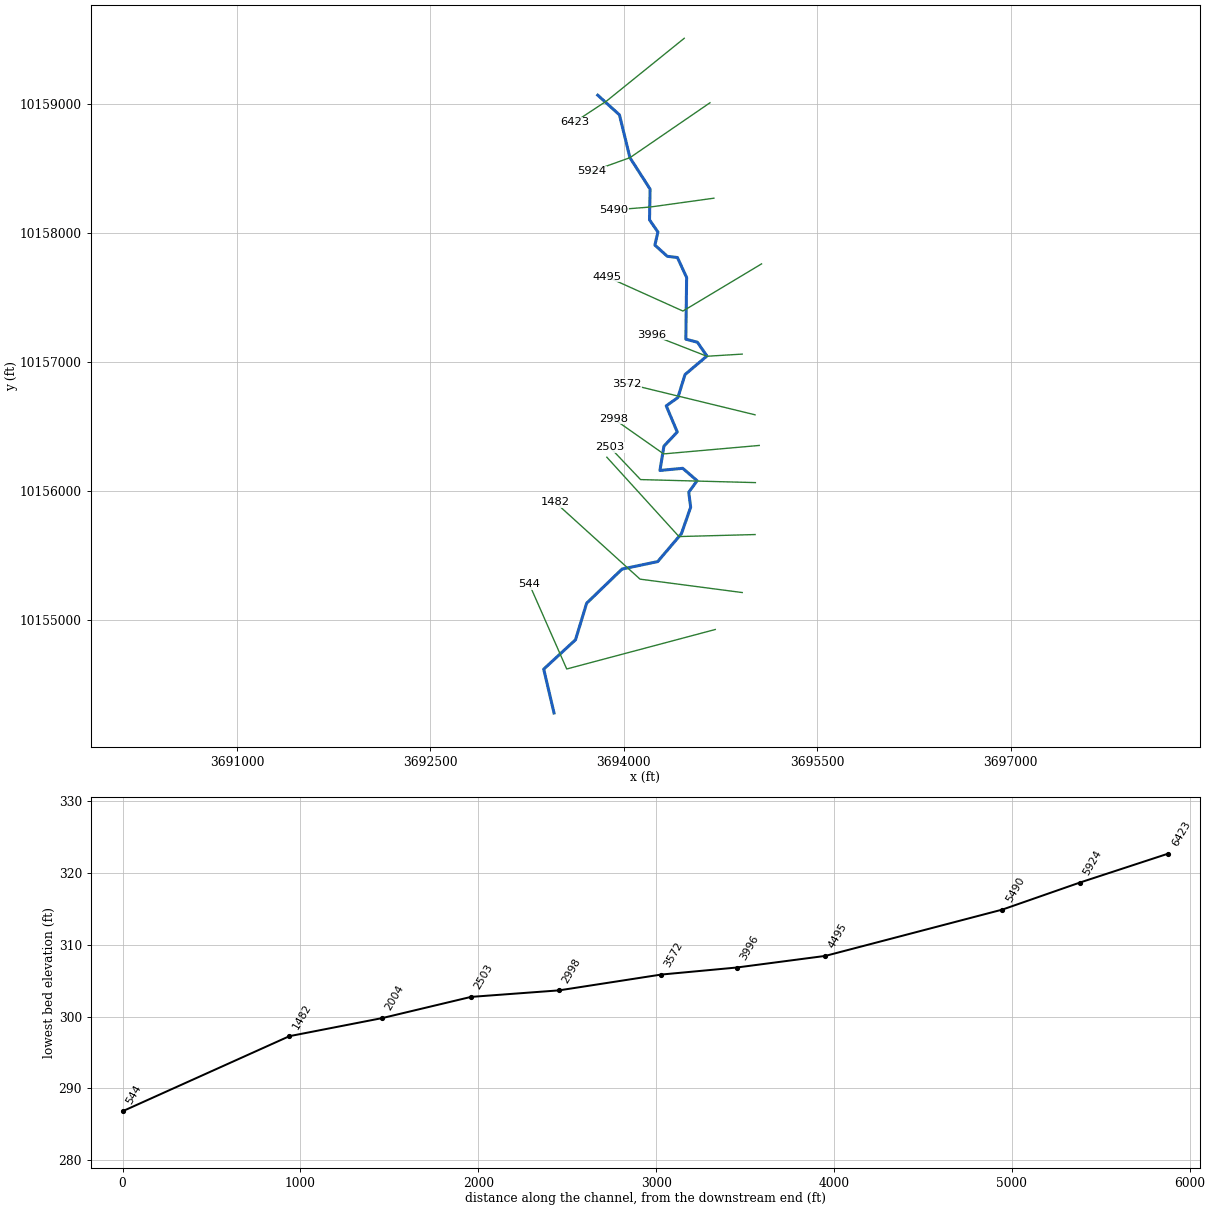
--- CCLC 117.prj (project) ---

Proj Title=CCLC 117 Base Level Engineering
Current Plan=p01
Default Exp/Contr=0.3,0.1
English Units
Geom File=g01
Flow File=f01
Flow File=f02
Plan File=p01
Y Axis Title=Elevation
X Axis Title(PF)=Main Channel Distance
X Axis Title(XS)=Station
BEGIN DESCRIPTION:
CCLC 117
END DESCRIPTION:
DSS Export Rating Curves= 0
DSS Export Rating Curve Sorted= 0
DSS Export Volume Flow Curves= 0
DXF OffsetX= 0
DXF OffsetY= 0
DXF ScaleX= 1
DXF ScaleY= 10

--- CCLC 117.p01 (plan) ---

Plan Title=Multiple Run
Short Identifier=Multiple
Geom File=g01
Flow File=f01
Subcritical Flow
K Sum by GR= 0
Std Step Tol= 0.01
Critical Tol= 0.01
Num of Std Step Trials= 20
Max Error Tol= 0.3
Flow Tol Ratio= 0.001
Split Flow NTrial= 30
Split Flow Tol= 0.02
Split Flow Ratio= 0.02
Log Output Level= 0
Friction Slope Method= 1
Unsteady Friction Slope Method= 2
Unsteady Bridges Friction Slope Method= 1
Parabolic Critical Depth
Global Vel Dist=  1 , 1 , 1
Global Log Level= 0
CheckData=True
Encroach Param= -1, 0, 0, 0
BEGIN DESCRIPTION:
Multiple Run
END DESCRIPTION:

--- CCLC 117.f01 (steady flow) ---

Flow Title=Multiple
Program Version=4.10
Number of Profiles= 7
Profile Names=10-year,25-year,50-year,1pct_min,100-year,1pct_plu,500-year
River Rch & RM=CCLC 117,Reach-1         ,6423
     413     548     730     321     970    2929    1765
River Rch & RM=CCLC 117,Reach-1         ,5924
     726     998    1360     610    1842    5563    3497
Boundary for River Rch & Prof#=CCLC 117,Reach-1         , 1
Up Type= 0
Dn Type= 3
Dn Slope=0.005
Boundary for River Rch & Prof#=CCLC 117,Reach-1         , 2
Up Type= 0
Dn Type= 3
Dn Slope=0.005
Boundary for River Rch & Prof#=CCLC 117,Reach-1         , 3
Up Type= 0
Dn Type= 3
Dn Slope=0.005
Boundary for River Rch & Prof#=CCLC 117,Reach-1         , 4
Up Type= 0
Dn Type= 3
Dn Slope=0.005
Boundary for River Rch & Prof#=CCLC 117,Reach-1         , 5
Up Type= 0
Dn Type= 3
Dn Slope=0.005
Boundary for River Rch & Prof#=CCLC 117,Reach-1         , 6
Up Type= 0
Dn Type= 3
Dn Slope=0.005
Boundary for River Rch & Prof#=CCLC 117,Reach-1         , 7
Up Type= 0
Dn Type= 3
Dn Slope=0.005
DSS Import GetInterval= 0
DSS Import GetPeak= 0
DSS Import FillOption= 0

--- CCLC 117.f02 (steady flow) ---

Flow Title=Orig_BLE_Flows
Program Version=4.10
Number of Profiles= 7
Profile Names=10-year,25-year,50-year,1pct_min,100-year,1pct_plu,500-year
River Rch & RM=CCLC 117,Reach-1         ,6423
     413     537     635     247     746    2253    1026
River Rch & RM=CCLC 117,Reach-1         ,5924
     726     978    1183     469    1417    4280    2033
Boundary for River Rch & Prof#=CCLC 117,Reach-1         , 1
Up Type= 0
Dn Type= 3
Dn Slope=0.005
Boundary for River Rch & Prof#=CCLC 117,Reach-1         , 2
Up Type= 0
Dn Type= 3
Dn Slope=0.005
Boundary for River Rch & Prof#=CCLC 117,Reach-1         , 3
Up Type= 0
Dn Type= 3
Dn Slope=0.005
Boundary for River Rch & Prof#=CCLC 117,Reach-1         , 4
Up Type= 0
Dn Type= 3
Dn Slope=0.005
Boundary for River Rch & Prof#=CCLC 117,Reach-1         , 5
Up Type= 0
Dn Type= 3
Dn Slope=0.005
Boundary for River Rch & Prof#=CCLC 117,Reach-1         , 6
Up Type= 0
Dn Type= 3
Dn Slope=0.005
Boundary for River Rch & Prof#=CCLC 117,Reach-1         , 7
Up Type= 0
Dn Type= 3
Dn Slope=0.005
DSS Import GetInterval= 0
DSS Import GetPeak= 0
DSS Import FillOption= 0

--- CCLC 117.g01 (geometry) ---

Geom Title=Existing Conditions
Program Version=4.10

River Reach=CCLC 117        ,Reach-1
Reach XY= 30
      3693797.47     10159069.72      3693965.51     10158917.55
      3694046.95     10158584.96      3694203.42       10158341.
      3694198.77      10158102.9      3694263.96     10158008.06
       3694240.4     10157906.83      3694336.61      10157819.8
      3694415.33     10157810.34      3694486.62     10157655.25
      3694480.45     10157176.71      3694570.09     10157153.27
      3694644.05     10157046.23      3694474.01     10156902.27
      3694418.79     10156723.75      3694328.37      10156659.7
        3694414.     10156456.83      3694310.54     10156346.82
      3694279.67     10156158.24      3694456.43     10156174.98
      3694567.97     10156078.78      3694502.98     10155989.53
      3694517.83     10155872.98      3694446.18      10155667.7
      3694262.16     10155451.24      3693985.86     10155393.21
      3693711.29     10155128.38      3693624.69     10154844.42
      3693378.23     10154616.84      3693458.23     10154276.84

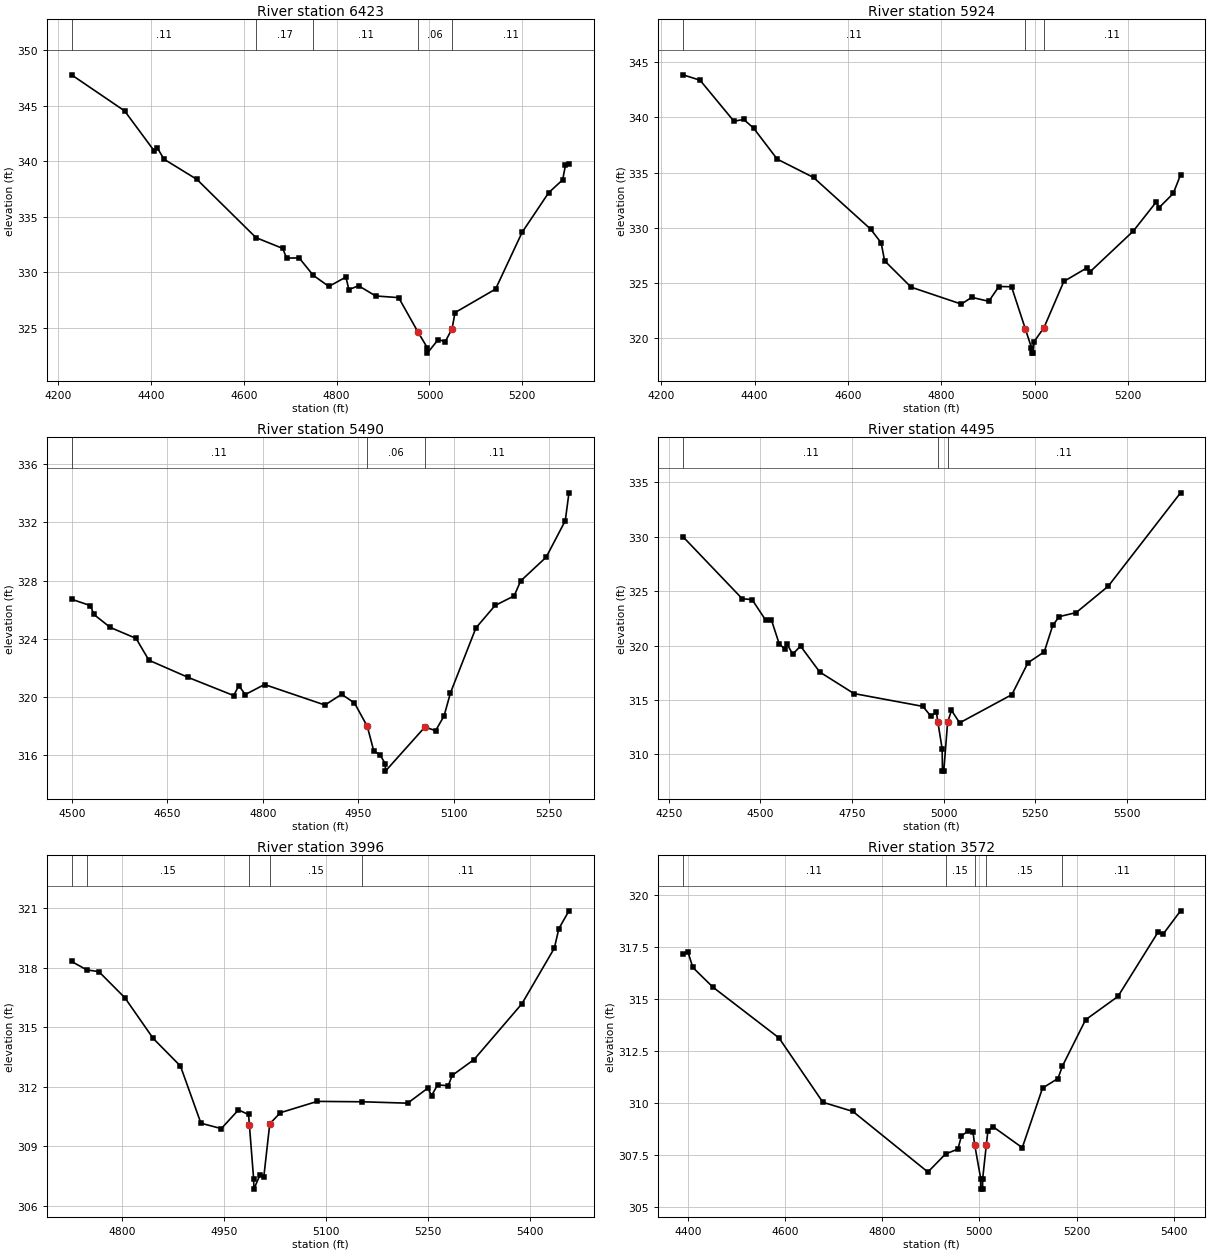
Type RM Length L Ch R = 1 ,6423    ,499,499,499
BEGIN DESCRIPTION:
CCLC 117 9.0
END DESCRIPTION:
XS GIS Cut Line= 3
      3694467.86     10159511.08      3693868.46     10159026.63
      3693617.81     10158861.05
#Sta/Elev= 30
  4229.3  347.78  4343.6  344.53  4407.6  340.91    4414   341.2  4428.4  340.18
  4499.3  338.36  4626.6  333.11  4684.2  332.14  4692.2  331.27  4719.4  331.29
  4749.7  329.72  4783.4  328.72  4820.1  329.56  4826.5  328.43  4847.4  328.78
  4884.1  327.86  4933.7  327.71  4975.3  324.61  4995.2  323.21  4995.4  322.71
  5018.9  323.93    5034  323.75  5048.7   324.9    5055  326.36  5142.4  328.48
  5199.5  333.59  5256.7  337.16  5286.8  338.32  5292.8  339.62  5300.4  339.72
#Mann= 5 ,-1 , 0
  4229.3     .11       0  4626.6     .17       0  4749.7     .11       0
  4975.3     .06       0  5048.7     .11       0
Bank Sta=4975.3,5048.7
XS Rating Curve= 0 ,0
Exp/Cntr=0.3,0.1

Type RM Length L Ch R = 1 ,5924    ,434,434,434
BEGIN DESCRIPTION:
CCLC 117 8.0
END DESCRIPTION:
XS GIS Cut Line= 3
      3694667.81     10159011.04      3694046.95     10158584.96
      3693752.46     10158479.22
#Sta/Elev= 30
    4247  343.85  4283.3  343.36  4355.9  339.65  4376.9  339.81  4397.9  339.03
  4448.6  336.22  4526.4  334.56  4648.9  329.88  4671.4  328.64  4678.7  327.02
  4735.6  324.63  4843.1   323.1  4865.5  323.71  4901.9  323.35  4923.7  324.69
  4950.7  324.67  4980.5  320.83  4993.4  319.16  4993.7  318.66  4997.2  318.66
    4999   319.7  5020.3  320.97  5062.8  325.15  5112.8  326.39  5118.2  325.99
  5211.5   329.7  5261.2  332.36  5266.5  331.81  5297.2  333.11  5312.9  334.79
#Mann= 3 , 0 , 0
    4247     .11       0  4980.5     .06       0  5020.3     .11       0
Bank Sta=4980.5,5020.3
XS Rating Curve= 0 ,0
Exp/Cntr=0.3,0.1

Type RM Length L Ch R = 1 ,5490    ,995,995,995
BEGIN DESCRIPTION:
CCLC 117 7.0
END DESCRIPTION:
XS GIS Cut Line= 3
      3694698.28     10158270.75      3694202.54     10158201.88
      3693922.12     10158179.66
#Sta/Elev= 30
  4499.5  326.72  4529.3  326.28  4534.4  325.68  4560.5  324.78  4600.9  324.03
  4621.1  322.53  4682.8  321.35  4754.4   320.1  4762.4  320.79  4772.5  320.17
  4802.8  320.86  4897.8  319.45    4924  320.19  4944.2  319.59  4964.3  317.99
  4974.5   316.3  4984.5  316.03  4992.6  315.41  4992.9  314.91  5054.9  317.94
  5071.7  317.69    5085   318.7    5095  320.28  5135.1  324.75  5165.2  326.29
  5195.2  326.95  5205.3  327.97  5245.5  329.61  5275.5  332.11  5281.3  334.03
#Mann= 3 , 0 , 0
  4499.5     .11       0  4964.3     .06       0  5054.9     .11       0
Bank Sta=4964.3,5054.9
XS Rating Curve= 0 ,0
Exp/Cntr=0.3,0.1

Type RM Length L Ch R = 1 ,4495    ,499,499,499
BEGIN DESCRIPTION:
CCLC 117 6.0
END DESCRIPTION:
XS GIS Cut Line= 3
      3695067.83     10157761.06      3694458.07     10157394.99
      3693867.88     10157661.06
#Sta/Elev= 30
  4288.8  329.99  4450.1  324.31  4477.3  324.22  4514.2  322.34  4529.8  322.37
  4551.1  320.17  4566.7  319.67  4572.5  320.16  4588.1   319.2  4609.4  319.96
  4661.9  317.57  4755.3  315.59  4943.7  314.41  4965.3  313.52  4980.6  313.86
 4984.55312.9763  4996.2  310.52  4997.2  308.46  5000.7  308.46  5011.2  312.96
  5021.8  314.04  5044.1   312.9  5186.7  315.49  5230.6  318.42  5275.1  319.42
  5298.3  321.85  5315.9  322.66  5362.2  323.03    5450  325.46  5647.4  334.04
#Mann= 3 , 0 , 0
  4288.8     .11       0 4984.55     .06       0  5011.2     .11       0
Bank Sta=4984.55,5011.2
XS Rating Curve= 0 ,0
Exp/Cntr=0.3,0.1

Type RM Length L Ch R = 1 ,3996    ,424,424,424
BEGIN DESCRIPTION:
CCLC 117 5.0
END DESCRIPTION:
XS GIS Cut Line= 3
      3694917.85     10157061.07      3694643.76     10157044.32
      3694217.84     10157211.07
#Sta/Elev= 30
  4725.4  318.31  4748.1  317.88  4765.5   317.8  4803.9  316.48  4845.6  314.43
  4885.7  313.04  4915.8  310.16  4945.8  309.89    4971  310.83  4985.9   310.6
 4987.09310.0828  4993.4  307.34  4993.7  306.84  5002.9  307.57  5008.3  307.44
  5017.1  310.13  5032.7  310.69    5087  311.26  5153.5  311.24    5220  311.17
  5249.8  311.93  5255.2  311.55  5264.1  312.09  5279.7  312.05  5285.6  312.57
  5317.8  313.37  5388.2  316.18  5435.9  318.98  5442.5  319.96  5457.4  320.86
#Mann= 5 ,-1 , 0
  4725.4     .17       0  4748.1     .15       0 4987.09     .09       0
  5017.1     .15       0  5153.5     .11       0
Bank Sta=4987.09,5017.1
XS Rating Curve= 0 ,0
Exp/Cntr=0.3,0.1

Type RM Length L Ch R = 1 ,3572    ,574,574,574
BEGIN DESCRIPTION:
Mapping XS 5448cab2
END DESCRIPTION:
XS GIS Cut Line= 2
      3695017.25     10156590.09       3694022.7     10156832.22
#Sta/Elev= 30
  4390.3  317.14    4400  317.26  4410.3   316.5  4451.4  315.56  4587.5  313.12
  4677.9  310.03  4739.6  309.59    4894  306.68  4930.4  307.55  4955.7  307.78
    4963  308.41  4976.3  308.65  4986.6  308.62 4990.24307.9944  5002.7  306.36
    5003  305.86  5006.5  305.86  5006.7  306.36 5014.17307.9721  5017.5  308.66
  5027.8  308.86  5088.2  307.85  5129.9  310.71  5161.6  311.17  5170.9  311.77
  5218.5  313.99  5285.1  315.11  5367.4  318.19  5377.7  318.09  5413.9  319.22
#Mann= 5 ,-1 , 0
  4390.3     .11       0  4930.4     .15       0 4990.24     .09       0
 5014.17     .15       0  5170.9     .11       0
Bank Sta=4990.24,5014.17
XS Rating Curve= 0 ,0
Exp/Cntr=0.3,0.1

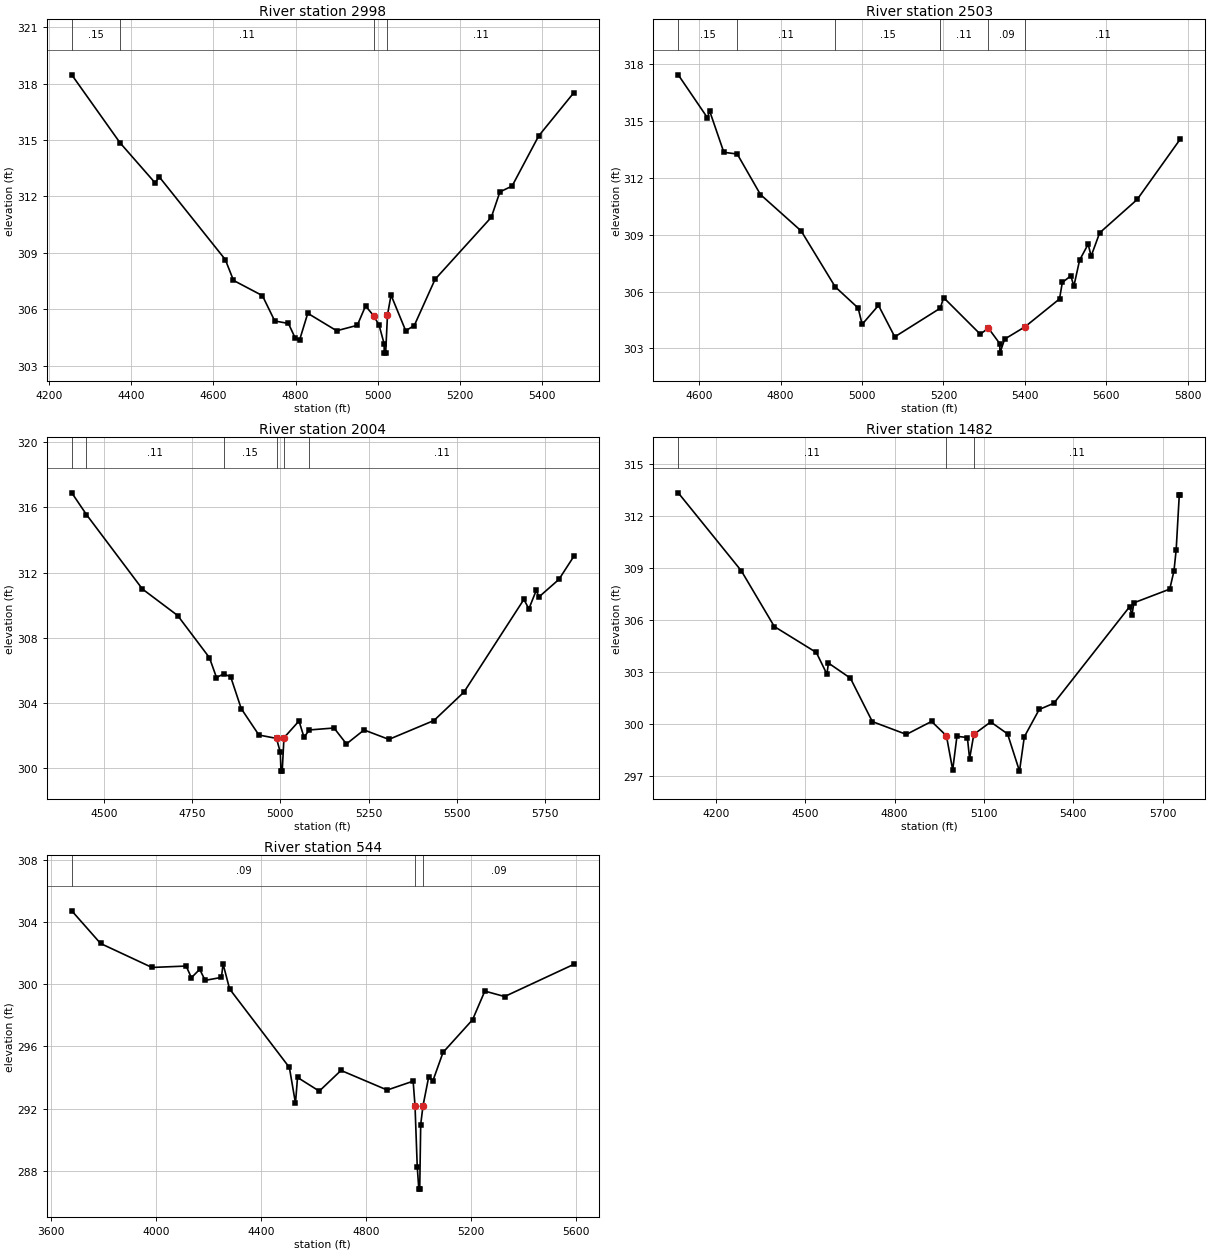
Type RM Length L Ch R = 1 ,2998    ,495,495,495
BEGIN DESCRIPTION:
CCLC 117 4.0
END DESCRIPTION:
XS GIS Cut Line= 3
      3695049.86     10156352.35      3694308.36     10156286.74
      3693917.88     10156561.05
#Sta/Elev= 30
  4255.6  318.47  4373.1  314.85  4458.4  312.72  4468.4  313.04  4629.1  308.64
  4649.1  307.53  4719.4  306.72  4749.5  305.37  4782.7  305.24  4799.7  304.44
  4809.8  304.35  4829.8  305.78  4900.1  304.85  4950.3  305.14  4970.4  306.17
  4990.5  305.64  5003.4  305.14  5015.6  304.16  5015.8  303.66  5019.3  303.66
 5023.76305.6877  5032.4  306.75  5068.1  304.85    5089  305.13  5139.6  307.59
  5276.4  310.89  5297.3  312.24  5326.9  312.55  5391.7  315.22  5477.2  317.52
#Mann= 4 ,-1 , 0
  4255.6     .15       0  4373.1     .11       0  4990.5     .06       0
 5023.76     .11       0
Bank Sta=4990.5,5023.76
XS Rating Curve= 0 ,0
Exp/Cntr=0.3,0.1

Type RM Length L Ch R = 1 ,2503    ,499,499,499
BEGIN DESCRIPTION:
Mapping XS c4a22844
END DESCRIPTION:
XS GIS Cut Line= 3
      3695019.89     10156064.05      3694129.23     10156087.49
      3693893.24     10156336.45
#Sta/Elev= 30
  4548.2  317.44  4620.1  315.17  4625.1  315.55  4660.3  313.35  4693.2  313.26
  4750.3  311.12  4850.3   309.2    4934  306.25  4990.4  305.13  5000.2  304.27
  5040.4  305.27  5080.4  303.61  5192.1  305.12  5200.5  305.68  5290.5  303.75
  5310.5  304.07  5338.5  303.25  5338.8  302.75  5350.5  303.49  5400.5  304.14
  5485.3  305.61  5492.2  306.48  5513.2  306.83  5520.5  306.28  5534.7  307.66
  5555.7   308.5    5563  307.87    5584   309.1  5676.2  310.86  5782.2  314.05
#Mann= 6 ,-1 , 0
  4548.2     .15       0  4693.2     .11       0    4934     .15       0
  5192.1     .11       0  5310.5     .09       0  5400.5     .11       0
Bank Sta=5310.5,5400.5
XS Rating Curve= 0 ,0
Exp/Cntr=0.3,0.1

Type RM Length L Ch R = 1 ,2004    ,522,522,522
BEGIN DESCRIPTION:
CCLC 117 3.0
END DESCRIPTION:
XS GIS Cut Line= 3
      3695017.85     10155661.07      3694427.16     10155645.43
      3693867.83      10156261.1
#Sta/Elev= 30
  4409.1   316.9  4450.8  315.56  4609.2  310.99  4709.2  309.36  4799.2  306.77
  4819.2  305.55  4839.3  305.77  4859.3   305.6  4889.3  303.64  4939.3  302.02
  4989.3  301.81    5000  300.95  5001.9   299.8  5005.4   299.8  5010.4  301.85
    5053  302.88  5067.2  301.88  5082.3  302.33  5152.3  302.45  5187.4  301.47
  5237.3  302.33  5307.7  301.75  5435.4  302.91  5520.6  304.66  5690.2  310.35
  5704.4  309.77  5725.3  310.91  5732.8   310.5  5789.5  311.58  5831.8     313
#Mann= 6 ,-1 , 0
  4409.1     .15       0  4450.8     .11       0  4839.3     .15       0
  4989.3     .06       0  5010.4     .15       0  5082.3     .11       0
Bank Sta=4989.3,5010.4
XS Rating Curve= 0 ,0
Exp/Cntr=0.3,0.1

Type RM Length L Ch R = 1 ,1482    ,938,938,938
BEGIN DESCRIPTION:
CCLC 117 2.0
END DESCRIPTION:
XS GIS Cut Line= 3
      3694917.87     10155211.07      3694125.34     10155315.02
      3693467.83     10155911.09
#Sta/Elev= 30
    4073  313.35  4284.8  308.85  4395.8  305.63    4537  304.13  4572.5  302.88
  4577.6  303.52  4651.3  302.65  4725.1  300.14  4839.5   299.4  4924.1  300.15
 4974.04  299.32  4995.1  297.35  5009.3  299.29  5044.4  299.22  5051.9  297.99
    5066   299.4  5122.8  300.12  5179.4  299.43  5219.5  297.28  5235.7  299.26
  5285.7  300.84    5335   301.2  5589.8  306.78  5597.2  306.29    5604     307
  5724.3  307.79  5738.5  308.84  5745.9  310.06  5756.4  313.25  5759.8  313.25
#Mann= 3 , 0 , 0
    4073     .11       0 4974.04     .06       0    5066     .11       0
Bank Sta=4974.04,5066
XS Rating Curve= 0 ,0
Exp/Cntr=0.3,0.1

Type RM Length L Ch R = 1 ,544     ,0,0,0
BEGIN DESCRIPTION:
CCLC 117 1.0
END DESCRIPTION:
XS GIS Cut Line= 3
      3694708.67     10154924.39      3693556.77     10154617.97
      3693266.34     10155276.84
#Sta/Elev= 30
  3679.6  304.71  3789.4  302.61    3985  301.07  4115.1  301.16  4135.2  300.41
  4166.8  300.95  4187.5  300.24  4249.6  300.43  4255.7   301.3  4280.6  299.69
  4508.3  294.64  4531.5  292.34  4539.3     294  4622.1  293.12  4704.9  294.45
  4880.8  293.19  4979.6  293.76 4986.76292.1726  4995.2  288.27  5001.2  286.82
  5004.7  286.82  5008.4  290.97    5017  292.16  5038.9  294.04    5055  293.79
  5093.5  295.61  5205.9  297.71  5252.6  299.55    5328   299.2  5591.6  301.27
#Mann= 3 , 0 , 0
  3679.6     .09       0 4986.76     .06       0    5017     .09       0
Bank Sta=4986.76,5017
XS Rating Curve= 0 ,0
Exp/Cntr=0.3,0.1

Chan Stop Cuts=-1
Use User Specified Reach Order=0
Composite Channel Slope=5