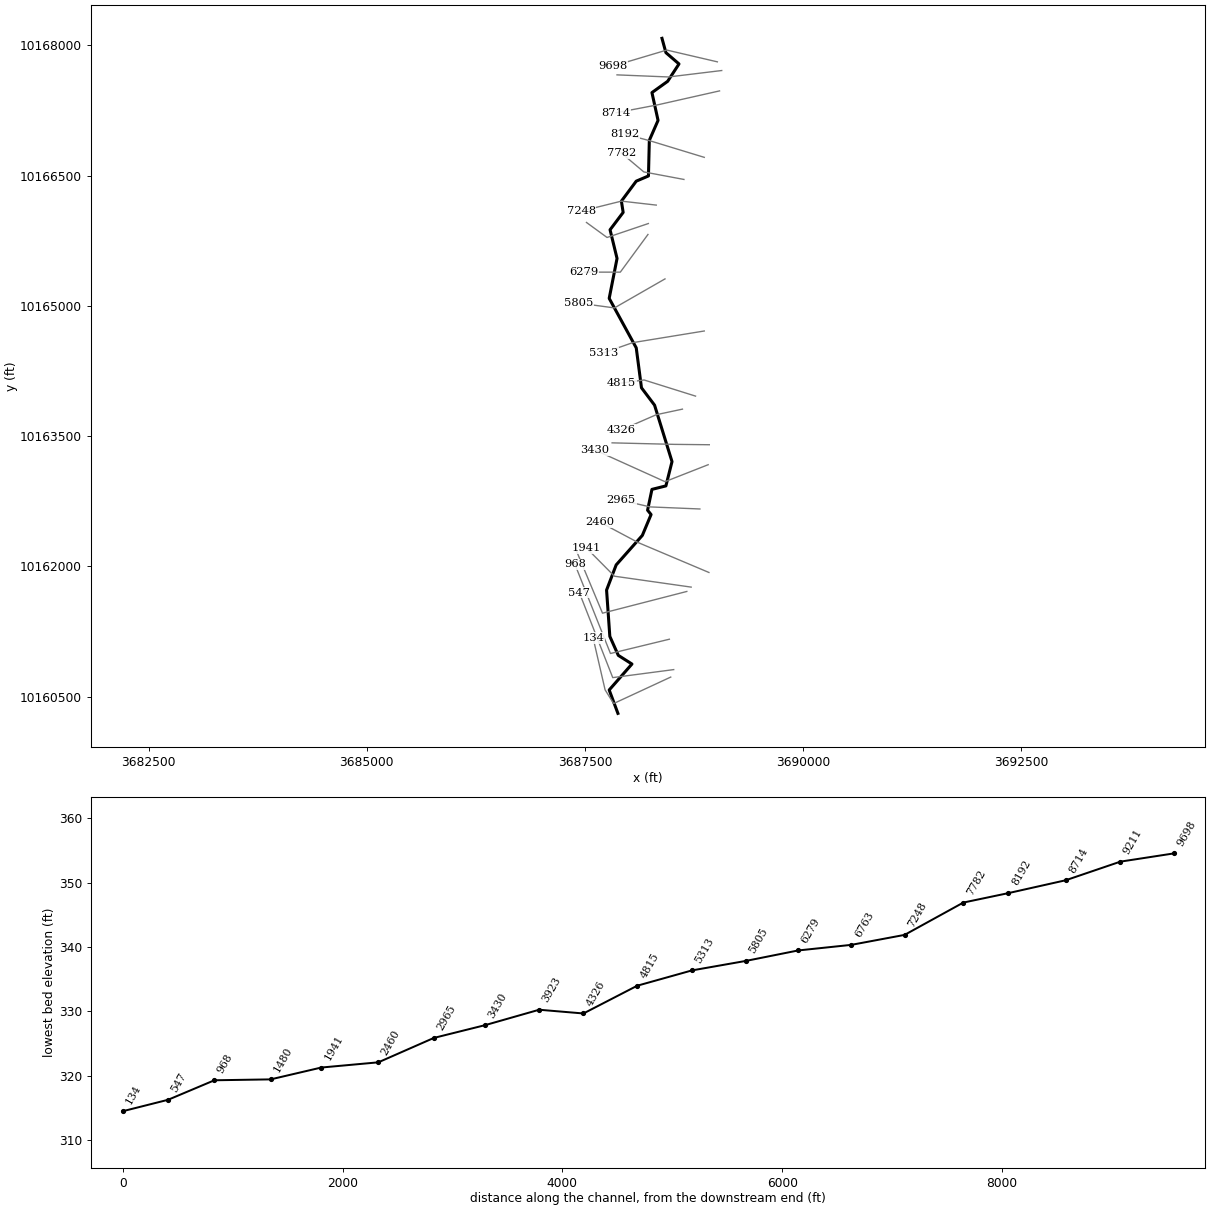
--- CCLC 118.prj (project) ---

Proj Title=CCLC 118 Base Level Engineering
Current Plan=p01
Default Exp/Contr=0.3,0.1
English Units
Geom File=g01
Flow File=f01
Flow File=f02
Plan File=p01
Y Axis Title=Elevation
X Axis Title(PF)=Main Channel Distance
X Axis Title(XS)=Station
BEGIN DESCRIPTION:
CCLC 118
END DESCRIPTION:
DSS Export Rating Curves= 0
DSS Export Rating Curve Sorted= 0
DSS Export Volume Flow Curves= 0
DXF OffsetX= 0
DXF OffsetY= 0
DXF ScaleX= 1
DXF ScaleY= 10

--- CCLC 118.p01 (plan) ---

Plan Title=Multiple Run
Short Identifier=Multiple
Geom File=g01
Flow File=f01
Subcritical Flow
K Sum by GR= 0
Std Step Tol= 0.01
Critical Tol= 0.01
Num of Std Step Trials= 20
Max Error Tol= 0.3
Flow Tol Ratio= 0.001
Split Flow NTrial= 30
Split Flow Tol= 0.02
Split Flow Ratio= 0.02
Log Output Level= 0
Friction Slope Method= 1
Unsteady Friction Slope Method= 2
Unsteady Bridges Friction Slope Method= 1
Parabolic Critical Depth
Global Vel Dist=  1 , 1 , 1
Global Log Level= 0
CheckData=True
Encroach Param= -1, 0, 0, 0
BEGIN DESCRIPTION:
Multiple Run
END DESCRIPTION:

--- CCLC 118.f01 (steady flow) ---

Flow Title=Multiple
Program Version=4.10
Number of Profiles= 7
Profile Names=10-year,25-year,50-year,1pct_min,100-year,1pct_plu,500-year
River Rch & RM=CCLC 118,Reach-1         ,9698
     752    1038    1424     641    1937    5850    3713
River Rch & RM=CCLC 118,Reach-1         ,5805
     874    1210    1658     746    2254    6807    4314
Boundary for River Rch & Prof#=CCLC 118,Reach-1         , 1
Up Type= 0
Dn Type= 3
Dn Slope=0.005
Boundary for River Rch & Prof#=CCLC 118,Reach-1         , 2
Up Type= 0
Dn Type= 3
Dn Slope=0.005
Boundary for River Rch & Prof#=CCLC 118,Reach-1         , 3
Up Type= 0
Dn Type= 3
Dn Slope=0.005
Boundary for River Rch & Prof#=CCLC 118,Reach-1         , 4
Up Type= 0
Dn Type= 3
Dn Slope=0.005
Boundary for River Rch & Prof#=CCLC 118,Reach-1         , 5
Up Type= 0
Dn Type= 3
Dn Slope=0.005
Boundary for River Rch & Prof#=CCLC 118,Reach-1         , 6
Up Type= 0
Dn Type= 3
Dn Slope=0.005
Boundary for River Rch & Prof#=CCLC 118,Reach-1         , 7
Up Type= 0
Dn Type= 3
Dn Slope=0.005
DSS Import GetInterval= 0
DSS Import GetPeak= 0
DSS Import FillOption= 0

--- CCLC 118.f02 (steady flow) ---

Flow Title=Orig_BLE_Flows
Program Version=4.10
Number of Profiles= 7
Profile Names=10-year,25-year,50-year,1pct_min,100-year,1pct_plu,500-year
River Rch & RM=CCLC 118,Reach-1         ,9698
     752    1018    1238     493    1490    4500    2159
River Rch & RM=CCLC 118,Reach-1         ,5805
     874    1186    1442     574    1734    5237    2508
Boundary for River Rch & Prof#=CCLC 118,Reach-1         , 1
Up Type= 0
Dn Type= 3
Dn Slope=0.005
Boundary for River Rch & Prof#=CCLC 118,Reach-1         , 2
Up Type= 0
Dn Type= 3
Dn Slope=0.005
Boundary for River Rch & Prof#=CCLC 118,Reach-1         , 3
Up Type= 0
Dn Type= 3
Dn Slope=0.005
Boundary for River Rch & Prof#=CCLC 118,Reach-1         , 4
Up Type= 0
Dn Type= 3
Dn Slope=0.005
Boundary for River Rch & Prof#=CCLC 118,Reach-1         , 5
Up Type= 0
Dn Type= 3
Dn Slope=0.005
Boundary for River Rch & Prof#=CCLC 118,Reach-1         , 6
Up Type= 0
Dn Type= 3
Dn Slope=0.005
Boundary for River Rch & Prof#=CCLC 118,Reach-1         , 7
Up Type= 0
Dn Type= 3
Dn Slope=0.005
DSS Import GetInterval= 0
DSS Import GetPeak= 0
DSS Import FillOption= 0

--- CCLC 118.g01 (geometry) ---

Geom Title=Existing Conditions
Program Version=4.10

River Reach=CCLC 118        ,Reach-1
Reach XY= 30
      3688383.23     10168081.84      3688428.23     10167916.84
      3688578.23     10167786.84      3688448.23     10167586.84
      3688268.23     10167456.84      3688338.23     10167136.84
      3688238.23     10166906.84      3688228.23     10166496.84
      3688088.23     10166436.84      3687918.23     10166206.84
      3687938.23     10166076.84      3687788.23     10165876.84
      3687868.23     10165546.84      3687778.23     10165086.84
      3688088.23     10164516.84      3688148.23     10164056.84
      3688298.23     10163856.84      3688498.23     10163206.84
      3688428.23     10162926.84      3688268.23     10162886.84
      3688218.23     10162646.84      3688258.23     10162596.84
      3688158.23     10162356.84      3687858.23     10162016.84
      3687748.23     10161726.84      3687785.48     10161193.74
       3687882.7     10160974.99      3688038.95     10160875.17
      3687778.23     10160576.22      3687878.23     10160306.84

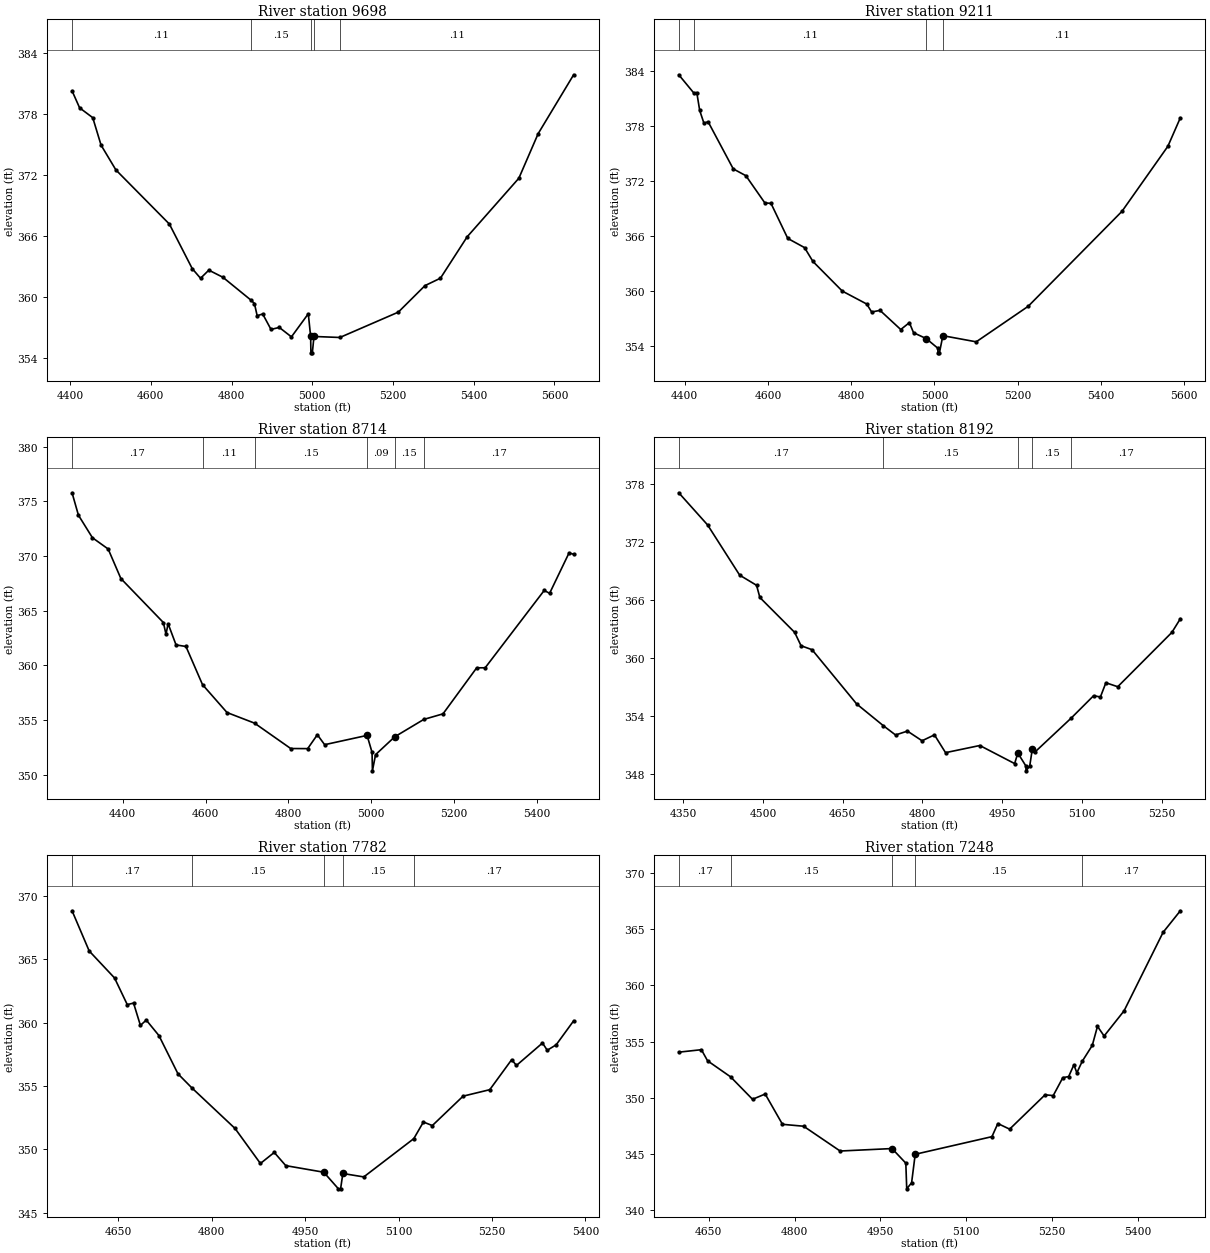
Type RM Length L Ch R = 1 ,9698    ,487,487,487
BEGIN DESCRIPTION:
CCLC 118 20.0
END DESCRIPTION:
XS GIS Cut Line= 3
      3689017.84     10167811.07      3688438.23     10167946.84
      3687817.85     10167761.07
#Sta/Elev= 30
  4404.7  380.29  4423.4  378.62    4456  377.65  4476.6  374.95  4513.4  372.51
  4645.9  367.19  4702.5  362.81  4723.1  361.86  4743.6  362.66  4778.5  361.96
  4847.8  359.72  4856.6  359.38  4863.4  358.18  4877.1  358.35  4897.7  356.83
  4918.2  357.03  4948.3   356.1  4990.1  358.37  4995.9  356.14  4996.6  354.53
  5000.1  354.53  5004.2  356.14  5068.3  356.04  5213.1  358.53  5279.3  361.14
  5317.6  361.87  5383.8  365.94  5511.9   371.7  5559.7  376.08  5647.6  381.87
#Mann= 5 ,-1 , 0
  4404.7     .11       0  4847.8     .15       0  4995.9     .09       0
  5004.2     .15       0  5068.3     .11       0
Bank Sta=4995.9,5004.2
XS Rating Curve= 0 ,0
Exp/Cntr=0.3,0.1

Type RM Length L Ch R = 1 ,9211    ,497,497,497
BEGIN DESCRIPTION:
CCLC 118 19.0
END DESCRIPTION:
XS GIS Cut Line= 3
      3689067.83     10167711.07      3688458.23     10167636.84
      3687867.83     10167661.07
#Sta/Elev= 30
  4385.9  383.56  4422.3  381.56  4429.2  381.62  4436.2  379.67  4446.3  378.29
  4456.4  378.44  4516.8   373.3  4547.1  372.56  4592.6   369.6  4607.5  369.54
  4647.8  365.72  4688.1  364.72  4708.2  363.21  4778.8  359.98  4837.5  358.57
  4849.3   357.7  4869.4  357.88  4919.2  355.79  4939.9  356.54    4950  355.44
  4980.2  354.81  5008.4  353.75  5008.6  353.25  5012.1  353.25  5020.4  355.12
  5100.5  354.45  5225.3  358.32  5450.8  368.68  5560.9  375.76  5590.9  378.87
#Mann= 4 ,-1 , 0
  4385.9     .17       0  4422.3     .11       0  4980.2     .06       0
  5020.4     .11       0
Bank Sta=4980.2,5020.4
XS Rating Curve= 0 ,0
Exp/Cntr=0.3,0.1

Type RM Length L Ch R = 1 ,8714    ,522,522,522
BEGIN DESCRIPTION:
CCLC 118 18.0
END DESCRIPTION:
XS GIS Cut Line= 3
      3689042.87     10167476.48      3688338.23     10167316.84
      3687857.98     10167224.74
#Sta/Elev= 30
  4277.5  375.78  4292.9  373.73  4326.7  371.67  4364.7  370.64  4395.4  367.94
    4498  363.92  4504.4  362.85  4509.5  363.81  4528.7  361.87  4552.6  361.73
  4592.6  358.24  4651.8  355.69  4718.3  354.72  4805.6   352.4  4846.6  352.39
    4870  353.66  4887.6  352.75  4990.1   353.6  5002.1  352.05    5003  350.36
  5010.6  351.84  5056.8  353.47    5127  355.06  5173.5  355.57  5254.9  359.78
  5275.3  359.78  5417.9  366.85    5431  366.59  5477.9  370.28    5489  370.16
#Mann= 6 ,-1 , 0
  4277.5     .17       0  4592.6     .11       0  4718.3     .15       0
  4990.1     .09       0  5056.8     .15       0    5127     .17       0
Bank Sta=4990.1,5056.8
XS Rating Curve= 0 ,0
Exp/Cntr=0.3,0.1

Type RM Length L Ch R = 1 ,8192    ,410,410,410
BEGIN DESCRIPTION:
CCLC 118 17.0
END DESCRIPTION:
XS GIS Cut Line= 3
      3688867.83     10166711.08      3688239.92     10166903.56
      3687962.49     10166977.26
#Sta/Elev= 30
  4341.5  377.12  4395.8  373.79  4456.1   368.6  4487.9  367.55  4494.1  366.29
  4559.6  362.68  4571.6   361.3  4592.3  360.89  4676.2  355.28  4726.4  353.03
  4749.4  352.07  4771.8  352.47  4799.3  351.47  4822.6  352.08  4843.5  350.24
    4908  350.98  4973.5  349.11  4979.5   350.2  4994.7  348.86    4995  348.36
  5001.9  348.86  5006.8  350.63    5012  350.32  5080.2  353.83  5122.1  356.13
  5134.9     356  5145.2  357.47  5167.5  357.06  5269.4  362.68  5285.3  364.09
#Mann= 5 ,-1 , 0
  4341.5     .17       0  4726.4     .15       0  4979.5     .09       0
  5006.8     .15       0  5080.2     .17       0
Bank Sta=4979.5,5006.8
XS Rating Curve= 0 ,0
Exp/Cntr=0.3,0.1

Type RM Length L Ch R = 1 ,7782    ,534,534,534
BEGIN DESCRIPTION:
CCLC 118 16.0
END DESCRIPTION:
XS GIS Cut Line= 3
      3688634.88     10166456.52      3688174.82     10166543.32
      3687917.85     10166761.07
#Sta/Elev= 30
    4576  368.82  4603.5  365.65  4644.2  363.52  4664.6  361.42  4674.7  361.54
  4685.7  359.78  4695.1   360.2  4715.4  358.98    4746  355.96  4767.9  354.87
  4837.6  351.65  4878.3  348.89  4900.5  349.76    4919  348.72    4980   348.2
  5003.5  346.89    5007  346.89  5010.6   348.1  5044.2  347.83  5124.5  350.85
  5139.9  352.16  5154.2  351.88  5203.6   354.2  5246.4  354.71  5281.6  357.08
  5289.2  356.62    5331  358.39  5338.7  357.82    5353  358.25    5381  360.14
#Mann= 5 ,-1 , 0
    4576     .17       0  4767.9     .15       0    4980     .09       0
  5010.6     .15       0  5124.5     .17       0
Bank Sta=4980,5010.6
XS Rating Curve= 0 ,0
Exp/Cntr=0.3,0.1

Type RM Length L Ch R = 1 ,7248    ,485,485,485
BEGIN DESCRIPTION:
CCLC 118 15.0
END DESCRIPTION:
XS GIS Cut Line= 3
      3688317.82     10166161.08      3687918.23     10166206.84
      3687458.68     10166091.93
#Sta/Elev= 30
  4597.8  354.05  4637.3  354.27  4648.1  353.28  4688.3  351.85  4726.6  349.85
  4748.7  350.32  4778.9  347.62  4815.8  347.45  4879.6  345.24  4970.2  345.46
  4994.3  344.16  4995.9  341.87  5004.4  342.41  5010.7  344.95  5144.7  346.52
    5155  347.69  5175.6  347.19  5237.5  350.25  5251.7  350.18  5268.4  351.77
  5278.7  351.88  5287.8  352.92    5293  352.21  5302.3  353.23  5319.9  354.65
    5329  356.35  5340.6  355.49  5375.4  357.73  5443.6  364.73  5473.7  366.65
#Mann= 5 ,-1 , 0
  4597.8     .17       0  4688.3     .15       0  4970.2     .09       0
  5010.7     .15       0  5302.3     .17       0
Bank Sta=4970.2,5010.7
XS Rating Curve= 0 ,0
Exp/Cntr=0.3,0.1

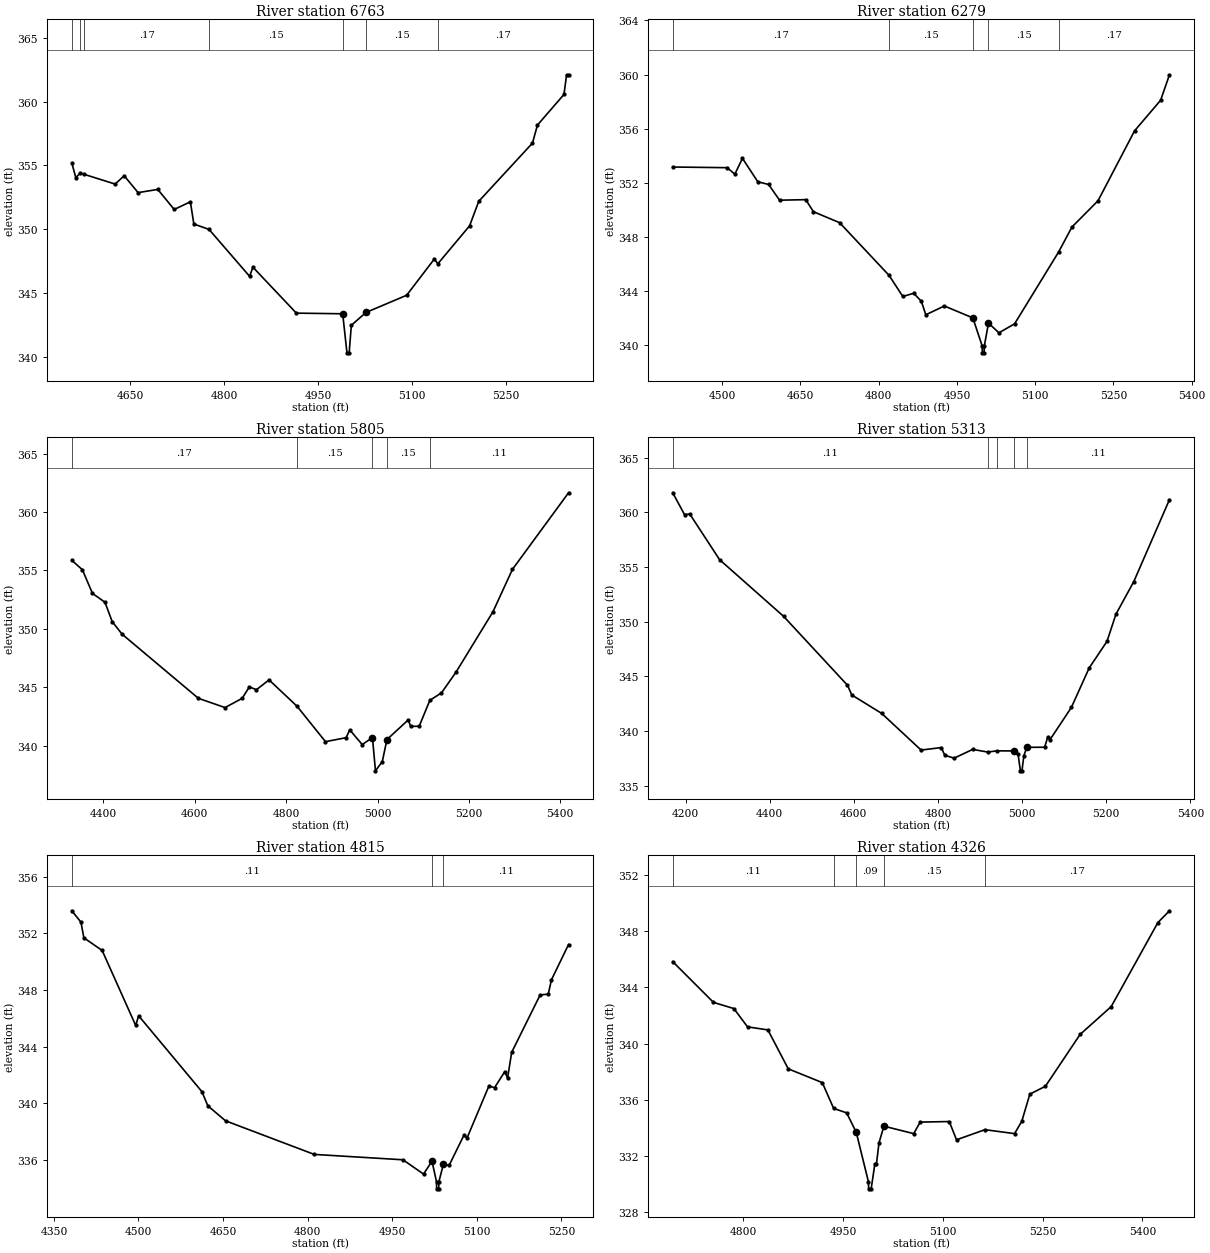
Type RM Length L Ch R = 1 ,6763    ,484,484,484
BEGIN DESCRIPTION:
CCLC 118 14.0
END DESCRIPTION:
XS GIS Cut Line= 3
      3688226.95     10165948.72      3687753.81     10165788.11
      3687517.86     10165961.07
#Sta/Elev= 30
  4557.4   355.2  4563.7  354.05  4571.1  354.41  4577.2   354.3  4626.5  353.54
  4640.9  354.19  4663.1  352.87  4694.5  353.12  4720.7  351.55  4746.5  352.15
    4752  350.41  4776.2  349.99    4841  346.31  4846.2  347.03  4915.5  343.43
  4989.4  343.38  4996.2  340.32  4999.7  340.32  5003.2  342.48 5026.51343.4823
  5091.4  344.83  5135.4  347.66  5141.2   347.3  5191.8  350.27  5206.4  352.19
  5292.1  356.75    5300  358.16  5342.3  360.56  5346.5   362.1  5349.6   362.1
#Mann= 7 ,-1 , 0
  4557.4     .17       0  4571.1     .15       0  4577.2     .17       0
  4776.2     .15       0  4989.4     .09       0 5026.51     .15       0
  5141.2     .17       0
Bank Sta=4989.4,5026.51
XS Rating Curve= 0 ,0
Exp/Cntr=0.3,0.1

Type RM Length L Ch R = 1 ,6279    ,474,474,474
BEGIN DESCRIPTION:
CCLC 118 13.0
END DESCRIPTION:
XS GIS Cut Line= 3
      3688222.58     10165822.86      3687905.72     10165388.81
      3687490.93     10165388.81
#Sta/Elev= 30
  4405.1  353.17  4509.5  353.12  4524.2  352.64  4538.8  353.81  4568.2  352.08
    4589  351.88  4609.9  350.72  4660.1  350.76  4674.8  349.87    4725  349.06
  4819.8  345.17  4846.2  343.61  4867.1  343.85  4881.8  343.25  4890.2  342.26
  4925.8  342.91  4980.4  342.03  4998.4  339.95  4998.6  339.45  5002.1  339.45
  5002.4  339.95  5010.4  341.65  5030.4  340.93  5060.4  341.59  5144.9   346.9
  5170.4  348.74  5220.4  350.68  5290.4  355.84  5340.4   358.1  5357.3  359.98
#Mann= 5 ,-1 , 0
  4405.1     .17       0  4819.8     .15       0  4980.4     .09       0
  5010.4     .15       0  5144.9     .17       0
Bank Sta=4980.4,5010.4
XS Rating Curve= 0 ,0
Exp/Cntr=0.3,0.1

Type RM Length L Ch R = 1 ,5805    ,492,492,492
BEGIN DESCRIPTION:
CCLC 118 12.0
END DESCRIPTION:
XS GIS Cut Line= 3
      3688417.87     10165311.08      3687838.23     10164976.84
      3687423.91     10165032.91
#Sta/Elev= 30
  4330.9  355.86    4354  355.06  4376.1  353.03  4403.5  352.27  4419.2  350.62
  4440.8  349.54    4608  344.04  4666.3  343.25  4703.7  344.04  4719.5  345.02
  4734.9  344.78  4762.6  345.62  4823.7  343.37  4886.1  340.33  4931.2  340.67
  4939.2  341.34  4966.5  340.08  4988.9  340.68  4995.5  337.83  5010.5  338.63
  5020.6  340.51  5067.4   342.2  5072.4  341.64  5091.2  341.65  5114.5  343.87
    5140  344.51  5171.9  346.29  5252.7  351.46  5295.3  355.09  5418.1  361.65
#Mann= 5 ,-1 , 0
  4330.9     .17       0  4823.7     .15       0  4988.9     .09       0
  5020.6     .15       0  5114.5     .11       0
Bank Sta=4988.9,5020.6
XS Rating Curve= 0 ,0
Exp/Cntr=0.3,0.1

Type RM Length L Ch R = 1 ,5313    ,498,498,498
BEGIN DESCRIPTION:
CCLC 118 11.0
END DESCRIPTION:
XS GIS Cut Line= 3
      3688867.81     10164711.07      3688048.23     10164576.84
      3687717.83     10164461.06
#Sta/Elev= 30
  4169.5  361.79  4197.6  359.79    4210  359.85  4280.9  355.67  4432.9  350.49
  4584.9  344.18  4595.1  343.29    4666  341.61  4759.8  338.25  4807.9  338.48
    4816  337.78  4838.3  337.51  4882.4  338.31    4918  338.07  4940.5  338.18
  4980.1  338.17  4990.3  337.87  4995.9  336.35  4999.5  336.35    5004  337.72
    5011   338.5  5053.4  338.51  5060.7  339.42    5066  339.19    5117  342.15
  5159.3  345.76  5201.7   348.2  5222.9  350.68  5265.3  353.66  5350.1  361.16
#Mann= 5 ,-1 , 0
  4169.5     .11       0    4918     .15       0  4940.5     .11       0
  4980.1     .06       0    5011     .11       0
Bank Sta=4980.1,5011
XS Rating Curve= 0 ,0
Exp/Cntr=0.3,0.1

Type RM Length L Ch R = 1 ,4815    ,489,489,489
BEGIN DESCRIPTION:
CCLC 118 10.0
END DESCRIPTION:
XS GIS Cut Line= 3
      3688767.86     10163961.07      3688178.23     10164146.84
      3687917.88     10164111.07
#Sta/Elev= 30
  4381.8  353.59    4398  352.79  4403.2  351.68  4435.6  350.79  4495.1   345.5
  4500.3  346.18  4612.5  340.83    4623  339.83  4654.4  338.77  4811.7   336.4
  4969.2  336.02  5005.6  335.01  5020.6  335.92  5028.6  334.47  5028.8  333.97
  5032.5  333.97  5032.8  334.47  5040.8   335.7  5050.9  335.62  5077.6  337.78
  5082.7  337.55  5121.5  341.22  5131.6  341.11  5149.7  342.24  5154.7  341.78
  5161.9   343.6  5212.4  347.65  5226.8  347.71  5232.5  348.72  5262.8  351.21
#Mann= 3 , 0 , 0
  4381.8     .11       0  5020.6     .06       0  5040.8     .11       0
Bank Sta=5020.6,5040.8
XS Rating Curve= 0 ,0
Exp/Cntr=0.3,0.1

Type RM Length L Ch R = 1 ,4326    ,403,403,403
BEGIN DESCRIPTION:
CCLC 118 9.0
END DESCRIPTION:
XS GIS Cut Line= 3
      3688617.82     10163811.07      3688318.23     10163746.84
      3687914.37     10163570.21
#Sta/Elev= 30
  4693.6  345.83  4754.9  342.93  4785.6  342.49  4806.1  341.19  4836.8  340.97
  4867.4   338.2  4918.6  337.22  4935.7  335.38  4955.2  335.07  4969.7  333.68
    4988  330.16  4988.3  329.66  4992.1  329.66  4997.6  331.41    5000  331.41
  5003.9  332.94  5011.3  334.12  5056.1  333.59  5065.9  334.41  5109.6  334.45
  5120.5  333.15  5163.2  333.87  5207.8  333.59  5218.7  334.47  5230.8   336.4
  5254.2  336.96  5306.4  340.65  5353.2  342.63  5423.4  348.61  5440.8  349.45
#Mann= 5 ,-1 , 0
  4693.6     .11       0  4935.7     .15       0  4969.7     .09       0
  5011.3     .15       0  5163.2     .17       0
Bank Sta=4969.7,5011.3
XS Rating Curve= 0 ,0
Exp/Cntr=0.3,0.1

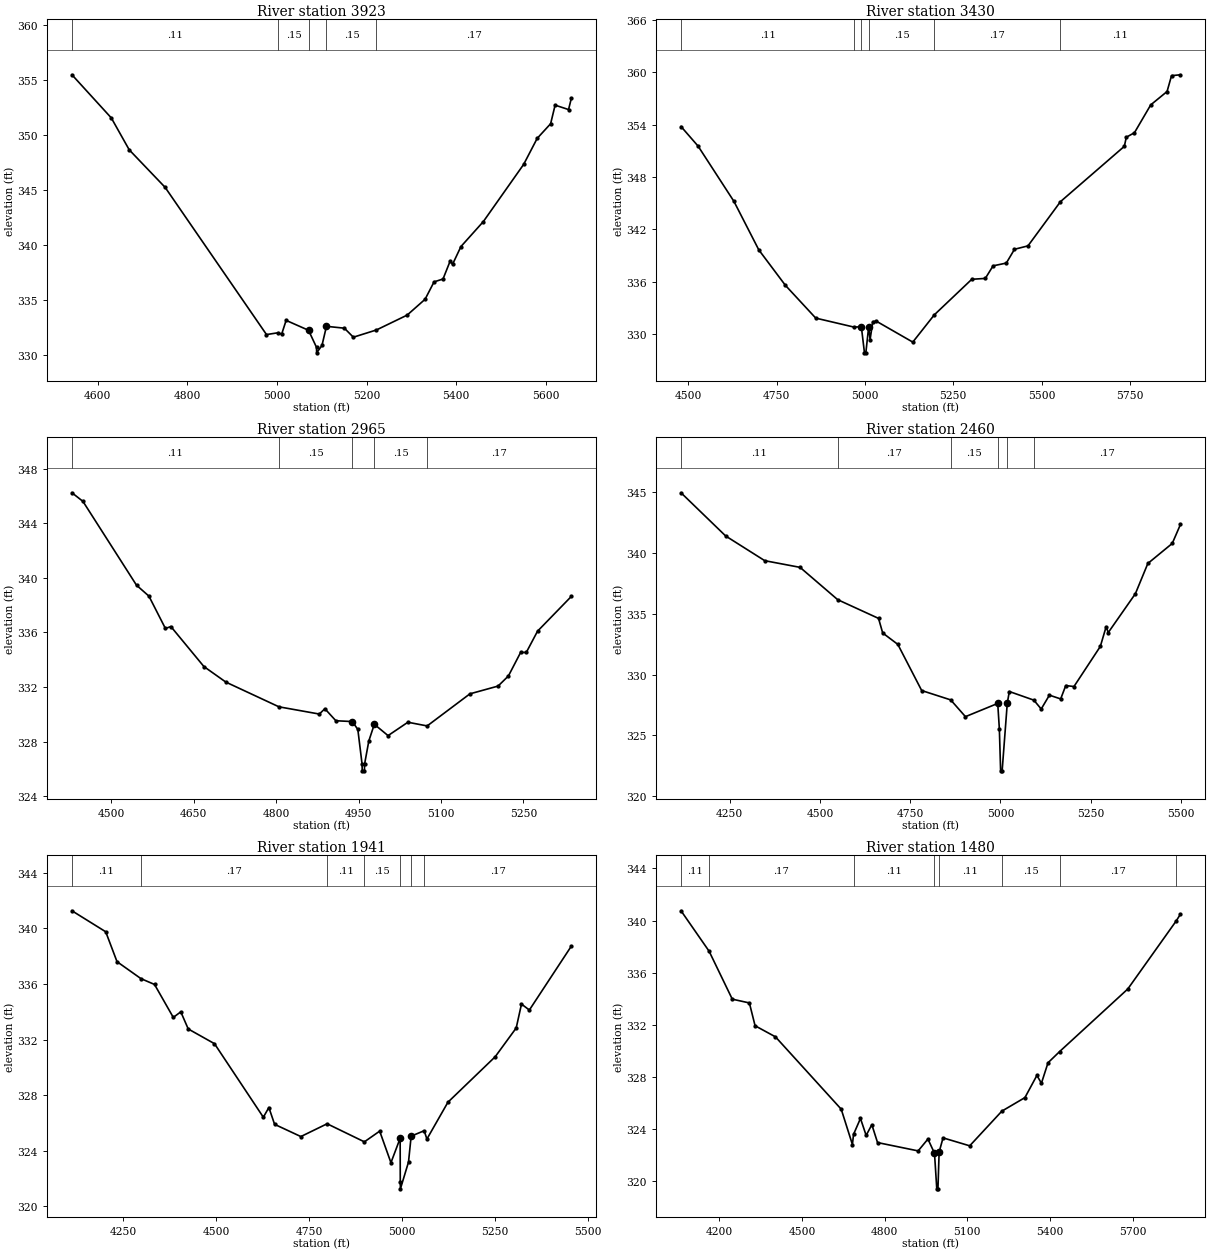
Type RM Length L Ch R = 1 ,3923    ,493,493,493
BEGIN DESCRIPTION:
CCLC 118 8.0
END DESCRIPTION:
XS GIS Cut Line= 3
      3688925.69     10163400.96      3688522.04      10163405.3
      3687811.53     10163422.63
#Sta/Elev= 30
  4542.5  355.51  4630.3  351.59  4670.3  348.69  4750.4  345.28  4976.6   331.9
  5003.2  332.07  5010.4  331.93  5020.4  333.19  5070.4  332.29  5088.2  330.74
  5088.5  330.24  5100.4  330.91  5110.4  332.65  5150.4  332.48  5170.4  331.66
    5222  332.32  5290.5  333.67  5330.5  335.11  5350.5  336.69  5370.5  336.95
  5386.7  338.61  5391.7  338.28  5410.5   339.9  5460.5  342.17  5550.5  347.37
  5580.6  349.73  5610.6  351.06  5620.6  352.75  5650.6  352.35  5656.9  353.38
#Mann= 5 ,-1 , 0
  4542.5     .11       0  5003.2     .15       0  5070.4     .06       0
  5110.4     .15       0    5222     .17       0
Bank Sta=5070.4,5110.4
XS Rating Curve= 0 ,0
Exp/Cntr=0.3,0.1

Type RM Length L Ch R = 1 ,3430    ,465,465,465
BEGIN DESCRIPTION:
CCLC 118 7.0
END DESCRIPTION:
XS GIS Cut Line= 3
      3688912.65     10163170.92      3688417.88     10162975.61
       3687614.9      10163340.2
#Sta/Elev= 30
  4479.2  353.78  4527.4  351.54    4629   345.2  4699.4  339.64  4774.6  335.58
  4860.6  331.82  4968.9  330.79  4989.7  330.83  4998.5  327.84  5002.4  327.84
  5010.5  330.85  5014.4  329.36  5022.1  331.41    5032  331.47  5135.3  329.07
  5196.1  332.19  5302.3  336.27  5340.6  336.37  5362.6  337.81  5400.1  338.13
  5423.2  339.71  5461.4   340.1  5553.4  345.17  5734.2  351.51  5739.7  352.55
  5762.8  353.07  5808.9  356.26  5855.1  357.79  5867.8  359.61    5893  359.71
#Mann= 6 ,-1 , 0
  4479.2     .11       0  4968.9     .15       0  4989.7     .09       0
  5010.5     .15       0  5196.1     .17       0  5553.4     .11       0
Bank Sta=4989.7,5010.5
XS Rating Curve= 0 ,0
Exp/Cntr=0.3,0.1

Type RM Length L Ch R = 1 ,2965    ,505,505,505
BEGIN DESCRIPTION:
CCLC 118 6.0
END DESCRIPTION:
XS GIS Cut Line= 3
       3688817.8     10162661.07      3688248.61     10162684.81
      3687917.87     10162761.07
#Sta/Elev= 30
  4428.3  346.23  4448.3   345.6  4545.8  339.46  4568.4  338.66  4598.4  336.29
  4608.4  336.43  4668.5   333.5  4708.5  332.36  4805.1  330.55  4878.6  330.02
  4888.7  330.41  4908.7  329.53  4938.7  329.47  4948.7  328.89  4956.4  326.36
  4956.7  325.86  4960.7  325.86    4961  326.36  4968.7  328.05  4978.7  329.27
  5003.7  328.44  5039.8  329.42  5074.9  329.15  5152.7   331.5    5204  332.07
  5222.8  332.81  5245.1  334.54  5255.3  334.53  5275.8  336.09  5337.4  338.64
#Mann= 5 ,-1 , 0
  4428.3     .11       0  4805.1     .15       0  4938.7     .09       0
  4978.7     .15       0  5074.9     .17       0
Bank Sta=4938.7,4978.7
XS Rating Curve= 0 ,0
Exp/Cntr=0.3,0.1

Type RM Length L Ch R = 1 ,2460    ,519,519,519
BEGIN DESCRIPTION:
CCLC 118 5.0
END DESCRIPTION:
XS GIS Cut Line= 3
      3688921.33     10161929.61      3688114.06     10162272.49
      3687667.82     10162511.09
#Sta/Elev= 30
  4115.4  344.96  4239.2   341.4  4347.3  339.37  4445.1  338.82  4549.3  336.16
  4662.4  334.62  4673.9  333.42  4715.8  332.48  4781.9  328.68  4862.2  327.91
  4903.1  326.53  4992.5  327.62    4997  325.52  5000.5  322.07  5004.7  322.07
  5018.9  327.63  5024.6   328.6  5092.5  327.89  5112.9  327.16  5135.6   328.3
  5166.8  327.99  5180.9  329.09  5203.6  329.01  5276.6  332.31  5292.8  333.94
  5298.5  333.45  5373.7  336.65  5408.2  339.14  5475.8  340.79  5498.5  342.35
#Mann= 6 ,-1 , 0
  4115.4     .11       0  4549.3     .17       0  4862.2     .15       0
  4992.5     .09       0  5018.9     .15       0  5092.5     .17       0
Bank Sta=4992.5,5018.9
XS Rating Curve= 0 ,0
Exp/Cntr=0.3,0.1

Type RM Length L Ch R = 1 ,1941    ,461,461,461
BEGIN DESCRIPTION:
CCLC 118 4.0
END DESCRIPTION:
XS GIS Cut Line= 3
      3688717.88     10161761.07      3687838.23     10161886.84
      3687517.86     10162211.06
#Sta/Elev= 30
  4111.4  341.26  4202.3  339.75  4232.7   337.6  4297.1  336.38  4333.7  335.96
  4384.2  333.59  4404.4  333.99  4424.4  332.76  4495.1   331.7  4626.6  326.41
  4641.5  327.11  4656.9   325.9  4727.6  325.02  4798.3  325.94  4898.6  324.64
  4939.8  325.41  4970.1  323.14  4994.9   324.9  4995.2  321.76  4995.6  321.26
  5017.4  323.19  5024.5  325.05  5059.6  325.44  5066.9  324.84  5123.5  327.49
  5250.7  330.76  5307.3  332.83  5321.5  334.55  5342.7  334.12  5455.8  338.72
#Mann= 7 ,-1 , 0
  4111.4     .11       0  4297.1     .17       0  4798.3     .11       0
  4898.6     .15       0  4994.9     .09       0  5024.5     .15       0
  5059.6     .17       0
Bank Sta=4994.9,5024.5
XS Rating Curve= 0 ,0
Exp/Cntr=0.3,0.1

Type RM Length L Ch R = 1 ,1480    ,512,512,512
BEGIN DESCRIPTION:
CCLC 118 3.0
END DESCRIPTION:
XS GIS Cut Line= 3
      3688667.83     10161711.07      3687701.73     10161460.85
      3687389.22     10162211.74
#Sta/Elev= 30
  4061.5  340.75  4163.3  337.65  4247.4  333.97  4309.4  333.68  4330.1  331.93
    4404  331.08  4642.5  325.53  4683.1  322.82  4687.2   323.6  4712.3  324.82
  4732.9  323.52  4753.6  324.34  4774.2  322.97  4921.5  322.33    4957  323.24
  4980.8  322.15  4989.1  319.42  4993.3  319.42  4997.6  322.24  5011.8  323.33
  5108.5  322.72  5225.1  325.38  5308.8  326.42  5352.2  328.12  5368.6  327.52
  5392.5  329.09  5434.6  329.95  5681.8  334.75  5857.4  339.97  5872.8  340.49
#Mann= 8 ,-1 , 0
  4061.5     .11       0  4163.3     .17       0  4687.2     .11       0
  4980.8     .06       0  4997.6     .11       0  5225.1     .15       0
  5434.6     .17       0  5857.4     .11       0
Bank Sta=4980.8,4997.6
XS Rating Curve= 0 ,0
Exp/Cntr=0.3,0.1

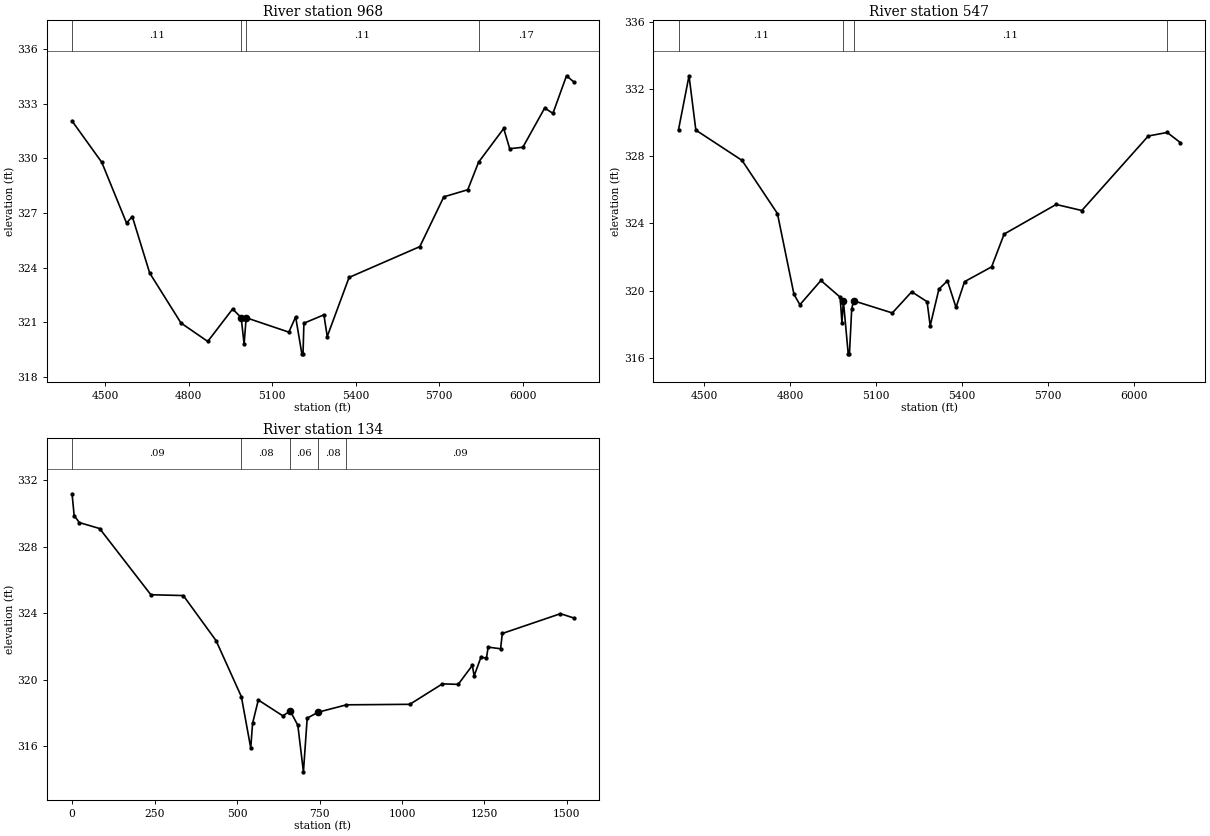
Type RM Length L Ch R = 1 ,968     ,421,421,421
BEGIN DESCRIPTION:
CCLC 118 2.0
END DESCRIPTION:
XS GIS Cut Line= 3
      3688467.85     10161161.07      3687792.88     10160996.44
      3687384.88     10162025.12
#Sta/Elev= 30
  4381.7  332.05  4488.5  329.78  4577.3  326.45  4597.9  326.81  4660.4  323.71
  4772.8  320.97  4868.8  319.96  4958.1  321.74  4988.7  321.27  4999.3  319.82
 5006.74  321.26    5160  320.47  5184.3  321.31  5206.6  319.28  5210.8  319.28
    5214  320.96  5285.8  321.42  5297.7  320.23  5376.1  323.47  5630.1  325.16
  5716.2  327.89  5802.2  328.28    5841  329.79  5931.3  331.64  5952.8  330.53
    6000  330.61  6078.3  332.76    6108  332.47  6156.7  334.53  6183.1  334.19
#Mann= 4 ,-1 , 0
  4381.7     .11       0  4988.7     .06       0 5006.74     .11       0
    5841     .17       0
Bank Sta=4988.7,5006.74
XS Rating Curve= 0 ,0
Exp/Cntr=0.3,0.1

Type RM Length L Ch R = 1 ,547     ,413,413,413
BEGIN DESCRIPTION:
CCLC 118 1.0
END DESCRIPTION:
XS GIS Cut Line= 3
      3688517.82     10160811.07      3687818.92     10160718.67
      3687436.97     10161695.25
#Sta/Elev= 30
  4409.6  329.58  4446.3  332.78  4470.1  329.55  4631.5  327.75  4755.2  324.59
    4813  319.79  4833.7  319.17  4907.2  320.61  4974.4  319.62  4980.6   318.1
  4985.7  319.39  5002.6  316.25  5006.9  316.25  5014.8  318.92 5021.25319.4054
  5156.7  318.68  5224.5  319.94  5278.2  319.35    5289  317.92  5319.6   320.1
  5349.4  320.59  5379.3  319.01  5409.1  320.54  5503.7  321.42  5547.5  323.37
  5729.2  325.13    5819  324.77  6051.3   329.2  6117.2  329.41  6163.2  328.81
#Mann= 4 ,-1 , 0
  4409.6     .11       0  4985.7     .06       0 5021.25     .11       0
  6117.2     .17       0
Bank Sta=4985.7,5021.25
XS Rating Curve= 0 ,0
Exp/Cntr=0.3,0.1

Type RM Length L Ch R = 1 ,134     ,0,0,0
BEGIN DESCRIPTION:
CCLC 118 1.0
END DESCRIPTION:
XS GIS Cut Line= 4
      3688483.52       10160725.      3687829.33     10160420.06
      3687731.35     10160577.56      3687593.82     10161175.71
#Sta/Elev= 30
       0  331.19     6.3  329.88      22  329.46    83.5   329.1   238.8  325.12
   337.2  325.07   436.5  322.36   513.2  318.99   541.6   315.9   547.1  317.38
   564.5  318.79   638.6  317.84   661.5  318.12   684.3  317.27   701.3  314.47
   712.7   317.7   746.5  318.06   831.8   318.5  1023.7  318.53  1122.5  319.76
  1170.4  319.73  1213.3  320.87  1218.7  320.24  1239.2  321.35  1256.1  321.32
  1261.2  321.97  1298.9  321.87  1304.1  322.79  1480.5  323.98    1521  323.72
#Mann= 5 ,-1 , 0
       0     .09       0   513.2     .08       0   661.5     .06       0
   746.5     .08       0   831.8     .09       0
Bank Sta=661.5,746.5
XS Rating Curve= 0 ,0
Exp/Cntr=0.3,0.1

Chan Stop Cuts=-1
Use User Specified Reach Order=0
Composite Channel Slope=5