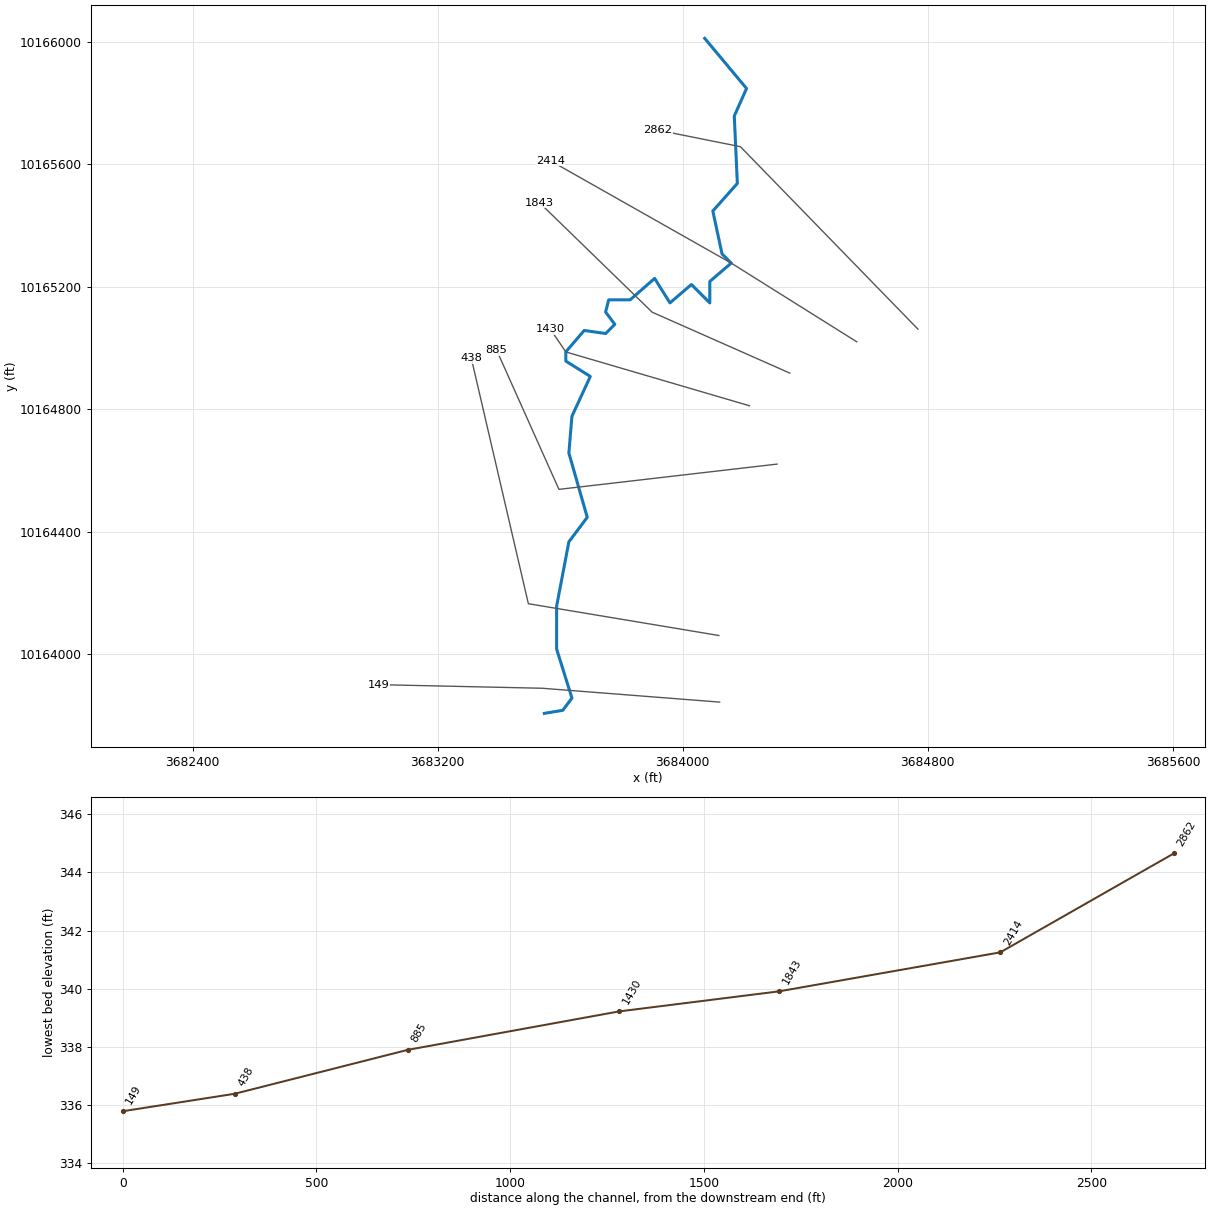
--- CCLC 120.prj (project) ---

Proj Title=CCLC 120 Base Level Engineering
Current Plan=p01
Default Exp/Contr=0.3,0.1
English Units
Geom File=g01
Flow File=f01
Flow File=f02
Plan File=p01
Y Axis Title=Elevation
X Axis Title(PF)=Main Channel Distance
X Axis Title(XS)=Station
BEGIN DESCRIPTION:
CCLC 120
END DESCRIPTION:
DSS Export Rating Curves= 0
DSS Export Rating Curve Sorted= 0
DSS Export Volume Flow Curves= 0
DXF OffsetX= 0
DXF OffsetY= 0
DXF ScaleX= 1
DXF ScaleY= 10

--- CCLC 120.p01 (plan) ---

Plan Title=Multiple Run
Short Identifier=Multiple
Geom File=g01
Flow File=f01
Subcritical Flow
K Sum by GR= 0
Std Step Tol= 0.01
Critical Tol= 0.01
Num of Std Step Trials= 20
Max Error Tol= 0.3
Flow Tol Ratio= 0.001
Split Flow NTrial= 30
Split Flow Tol= 0.02
Split Flow Ratio= 0.02
Log Output Level= 0
Friction Slope Method= 1
Unsteady Friction Slope Method= 2
Unsteady Bridges Friction Slope Method= 1
Parabolic Critical Depth
Global Vel Dist=  1 , 1 , 1
Global Log Level= 0
CheckData=True
Encroach Param= -1, 0, 0, 0
BEGIN DESCRIPTION:
Multiple Run
END DESCRIPTION:

--- CCLC 120.f01 (steady flow) ---

Flow Title=Multiple
Program Version=4.10
Number of Profiles= 7
Profile Names=10-year,25-year,50-year,1pct_min,100-year,1pct_plu,500-year
River Rch & RM=CCLC 120,Reach-1         ,2862
     623     850    1155     516    1559    4708    2939
River Rch & RM=CCLC 120,Reach-1         ,149
    1065    1481    2036     918    2772    8371    5322
Boundary for River Rch & Prof#=CCLC 120,Reach-1         , 1
Up Type= 0
Dn Type= 3
Dn Slope=0.005
Boundary for River Rch & Prof#=CCLC 120,Reach-1         , 2
Up Type= 0
Dn Type= 3
Dn Slope=0.005
Boundary for River Rch & Prof#=CCLC 120,Reach-1         , 3
Up Type= 0
Dn Type= 3
Dn Slope=0.005
Boundary for River Rch & Prof#=CCLC 120,Reach-1         , 4
Up Type= 0
Dn Type= 3
Dn Slope=0.005
Boundary for River Rch & Prof#=CCLC 120,Reach-1         , 5
Up Type= 0
Dn Type= 3
Dn Slope=0.005
Boundary for River Rch & Prof#=CCLC 120,Reach-1         , 6
Up Type= 0
Dn Type= 3
Dn Slope=0.005
Boundary for River Rch & Prof#=CCLC 120,Reach-1         , 7
Up Type= 0
Dn Type= 3
Dn Slope=0.005
DSS Import GetInterval= 0
DSS Import GetPeak= 0
DSS Import FillOption= 0

--- CCLC 120.f02 (steady flow) ---

Flow Title=Orig_BLE_Flows
Program Version=4.10
Number of Profiles= 7
Profile Names=10-year,25-year,50-year,1pct_min,100-year,1pct_plu,500-year
River Rch & RM=CCLC 120,Reach-1         ,2862
     623     833    1004     397    1199    3622    1709
River Rch & RM=CCLC 120,Reach-1         ,149
    1065    1452    1770     706    2132    6439    3094
Boundary for River Rch & Prof#=CCLC 120,Reach-1         , 1
Up Type= 0
Dn Type= 3
Dn Slope=0.005
Boundary for River Rch & Prof#=CCLC 120,Reach-1         , 2
Up Type= 0
Dn Type= 3
Dn Slope=0.005
Boundary for River Rch & Prof#=CCLC 120,Reach-1         , 3
Up Type= 0
Dn Type= 3
Dn Slope=0.005
Boundary for River Rch & Prof#=CCLC 120,Reach-1         , 4
Up Type= 0
Dn Type= 3
Dn Slope=0.005
Boundary for River Rch & Prof#=CCLC 120,Reach-1         , 5
Up Type= 0
Dn Type= 3
Dn Slope=0.005
Boundary for River Rch & Prof#=CCLC 120,Reach-1         , 6
Up Type= 0
Dn Type= 3
Dn Slope=0.005
Boundary for River Rch & Prof#=CCLC 120,Reach-1         , 7
Up Type= 0
Dn Type= 3
Dn Slope=0.005
DSS Import GetInterval= 0
DSS Import GetPeak= 0
DSS Import FillOption= 0

--- CCLC 120.g01 (geometry) ---

Geom Title=Existing Conditions
Program Version=4.10

River Reach=CCLC 120        ,Reach-1
Reach XY= 30
      3684071.64     10166010.55      3684208.23     10165846.84
      3684168.23     10165756.84      3684178.23     10165536.84
      3684098.23     10165446.84      3684128.23     10165306.84
      3684158.23     10165276.84      3684088.23     10165216.84
      3684088.23     10165146.84      3684028.23     10165206.84
      3683958.23     10165146.84      3683908.23     10165226.84
      3683828.23     10165156.84      3683758.23     10165156.84
      3683748.23     10165116.84      3683778.23     10165076.84
      3683748.23     10165046.84      3683678.23     10165056.84
      3683618.23     10164986.84      3683618.23     10164956.84
      3683698.23     10164906.84      3683638.23     10164776.84
      3683628.23     10164656.84      3683688.23     10164446.84
      3683628.23     10164366.84      3683588.23     10164156.84
      3683588.23     10164016.84      3683638.23     10163856.84
      3683608.23     10163816.84      3683548.23     10163806.84

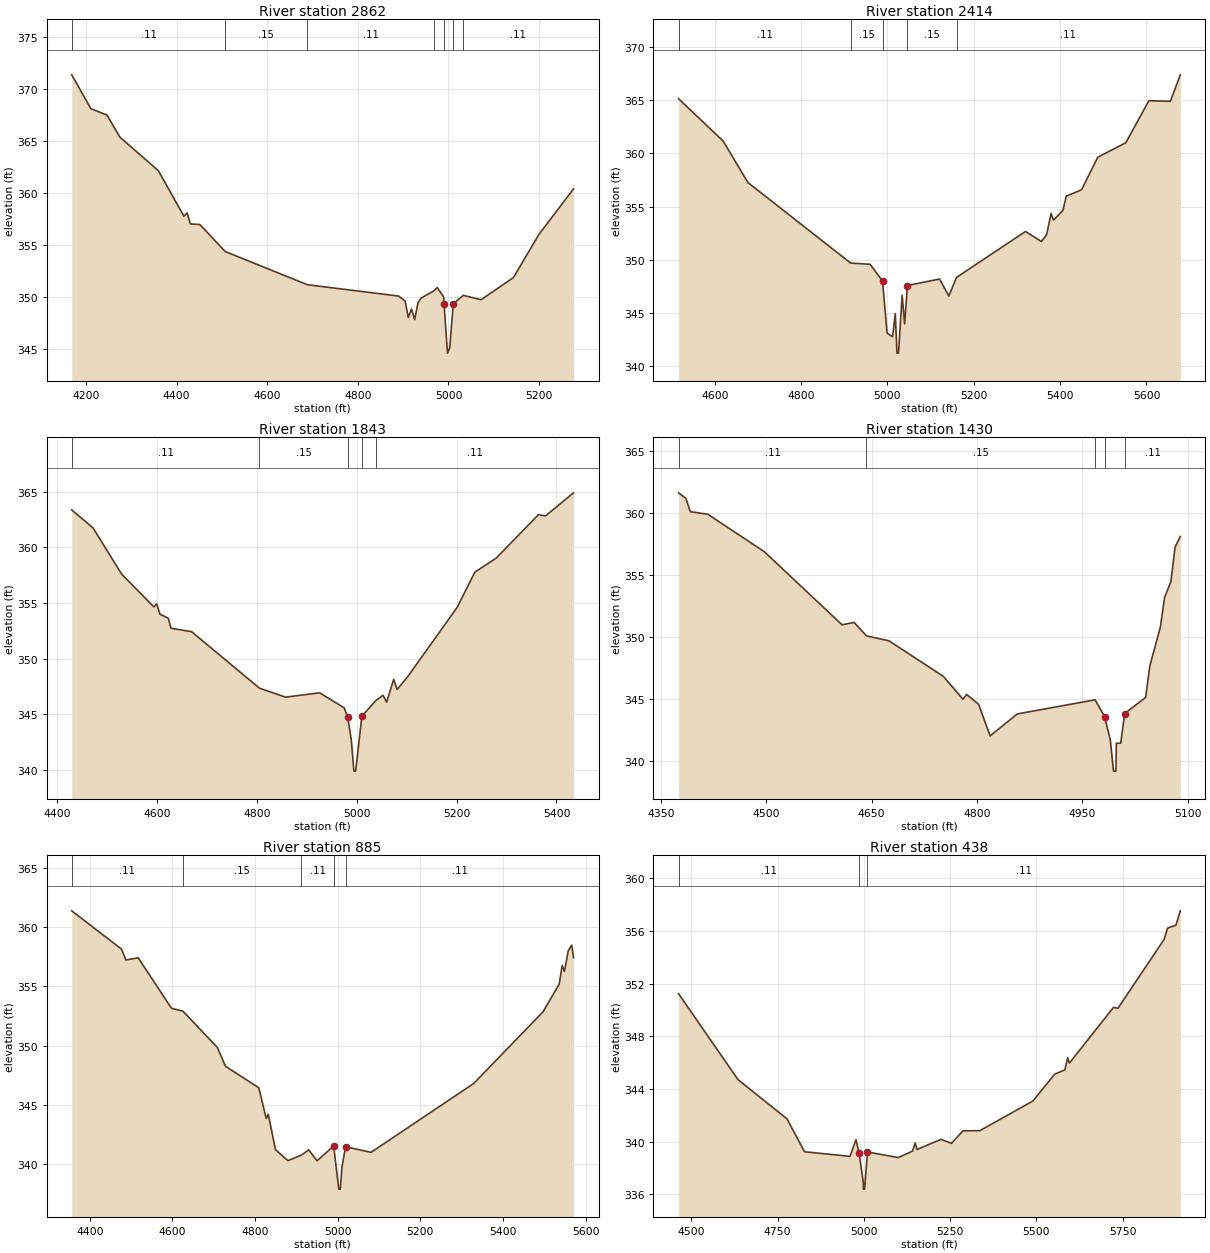
Type RM Length L Ch R = 1 ,2862    ,448,448,448
BEGIN DESCRIPTION:
CCLC 120 5.0
END DESCRIPTION:
XS GIS Cut Line= 3
      3684767.85     10165061.08      3684188.23     10165656.84
      3683917.82     10165711.08
#Sta/Elev= 30
  4168.8  371.38  4211.1  368.13  4246.6  367.51  4274.9   365.4  4359.8  362.18
  4416.3   357.8  4423.3  358.12  4430.5  357.06  4451.6     357  4507.3  354.41
  4688.6  351.22  4890.1  350.13  4904.3  349.66  4911.3  348.08  4918.4  348.89
  4925.4  347.87  4932.6  349.48  4939.6  349.94  4967.7  350.63    4975  350.95
  4989.2  350.07 4990.27349.3521  4997.7  344.65  5002.7  345.15  5010.6  349.41
  5032.8   350.2  5071.8  349.78  5143.2   351.9  5199.4  356.04  5275.8  360.43
#Mann= 7 ,-1 , 0
  4168.8     .11       0  4507.3     .15       0  4688.6     .11       0
  4967.7     .15       0 4990.27     .09       0  5010.6     .15       0
  5032.8     .11       0
Bank Sta=4990.27,5010.6
XS Rating Curve= 0 ,0
Exp/Cntr=0.3,0.1

Type RM Length L Ch R = 1 ,2414    ,571,571,571
BEGIN DESCRIPTION:
CCLC 120 4.0
END DESCRIPTION:
XS GIS Cut Line= 3
      3684568.04     10165019.89      3684158.23     10165276.84
      3683567.87     10165611.06
#Sta/Elev= 30
  4516.3  365.11  4619.5  361.14  4677.2  357.24  4914.7   349.7    4960  349.58
  4988.6  348.01  4999.3  343.13  5011.9  342.78  5018.2  344.96  5022.2  341.25
  5025.7  341.25  5034.1  346.67  5039.8     344  5046.4  347.59  5120.7   348.2
  5142.3  346.61    5160  348.35  5319.8  352.66  5356.7  351.72  5368.8  352.37
    5379  354.34  5384.7  353.72  5406.4  354.63  5414.1  355.97  5449.7  356.57
  5487.2  359.62  5552.1  360.98  5605.6  364.92  5655.4  364.87  5678.4  367.35
#Mann= 5 ,-1 , 0
  4516.3     .11       0  4914.7     .15       0  4988.6     .09       0
  5046.4     .15       0    5160     .11       0
Bank Sta=4988.6,5046.4
XS Rating Curve= 0 ,0
Exp/Cntr=0.3,0.1

Type RM Length L Ch R = 1 ,1843    ,413,413,413
BEGIN DESCRIPTION:
Mapping XS 4cbd692e
END DESCRIPTION:
XS GIS Cut Line= 3
      3684349.36     10164917.74      3683900.17     10165116.51
      3683531.96     10165474.42
#Sta/Elev= 30
  4429.4  363.36    4472  361.74  4529.5  357.58  4593.9  354.65  4599.4  354.92
    4606     354  4622.7  353.63  4628.2  352.73  4669.3  352.43  4805.1  347.36
  4857.5  346.55  4925.7  346.94    4975  345.59    4982  344.75  4989.1  342.73
  4994.4  339.91  4997.9  339.91  5010.3  344.83  5038.8  346.27  5052.7  346.72
  5059.9   346.1    5074  348.14    5081  347.24  5102.3   348.4  5201.3  354.62
  5236.6  357.77  5279.1  359.02  5363.9  362.93  5378.1  362.82  5434.1  364.89
#Mann= 5 ,-1 , 0
  4429.4     .11       0  4805.1     .15       0    4982     .09       0
  5010.3     .15       0  5038.8     .11       0
Bank Sta=4982,5010.3
XS Rating Curve= 0 ,0
Exp/Cntr=0.3,0.1

Type RM Length L Ch R = 1 ,1430    ,545,545,545
BEGIN DESCRIPTION:
CCLC 120 3.0
END DESCRIPTION:
XS GIS Cut Line= 3
       3684217.9     10164811.06      3683618.23     10164986.84
      3683567.86     10165061.06
#Sta/Elev= 30
  4375.1  361.66  4385.6  361.21  4391.8  360.14  4416.8  359.93  4497.3  356.91
  4607.9  351.02  4625.2  351.21  4642.7  350.12  4674.7  349.73    4752  346.87
  4780.2  345.02  4785.4   345.4  4802.4  344.61  4818.8  342.06  4857.4  343.83
  4968.3  344.97 4981.87343.6161    4990  341.74  4994.5  339.22    4998  339.22
  4998.6  341.47  5004.8  341.47  5010.4  343.86  5040.3  345.16  5046.3  347.71
  5061.2  350.82  5067.3  353.23  5076.2  354.49  5082.2  357.28  5089.7  358.14
#Mann= 5 ,-1 , 0
  4375.1     .11       0  4642.7     .15       0  4968.3     .11       0
 4981.87     .06       0  5010.4     .11       0
Bank Sta=4981.87,5010.4
XS Rating Curve= 0 ,0
Exp/Cntr=0.3,0.1

Type RM Length L Ch R = 1 ,885     ,447,447,447
BEGIN DESCRIPTION:
CCLC 120 2.0
END DESCRIPTION:
XS GIS Cut Line= 3
      3684307.65     10164620.58      3683595.83     10164538.11
      3683392.36     10164992.66
#Sta/Elev= 30
  4356.3  361.35  4476.9  358.12  4487.2  357.21  4517.2  357.39  4597.7  353.14
  4625.6  352.89  4708.4  349.85  4728.6  348.25  4809.1  346.44  4827.1  343.85
  4832.1  344.21  4849.4  341.23  4879.6   340.3    4912  340.76  4929.9  341.21
    4950  340.29  4990.3  341.53  5002.8   337.9  5006.3   337.9  5010.4  339.75
  5019.1341.4728  5080.9     341  5329.3   346.8  5497.1  352.84  5536.3  355.18
  5543.5  356.75    5549  356.25  5558.2  357.99  5566.7  358.46  5570.9  357.41
#Mann= 5 ,-1 , 0
  4356.3     .11       0  4625.6     .15       0    4912     .11       0
  4990.3     .06       0  5019.1     .11       0
Bank Sta=4990.3,5019.1
XS Rating Curve= 0 ,0
Exp/Cntr=0.3,0.1

Type RM Length L Ch R = 1 ,438     ,289,289,289
BEGIN DESCRIPTION:
CCLC 120 1.0
END DESCRIPTION:
XS GIS Cut Line= 3
      3684117.81     10164061.08        3683496.     10164164.85
      3683309.56     10164966.96
#Sta/Elev= 30
  4463.1  351.24  4635.4  344.71  4777.3  341.73    4828  339.23  4959.8  338.88
  4977.2  340.15 4986.33339.1034  4998.4  336.89  4998.6  336.39  5002.1  336.39
  5010.5  339.21  5099.9  338.79    5141  339.28  5148.8   339.9    5154   339.4
  5223.1  340.17  5253.9  339.87    5287  340.82    5336  340.83    5490  343.09
  5552.9  345.13  5582.4  345.45  5590.4  346.37  5595.6  345.97  5723.4   350.2
  5736.4  350.14  5869.9  355.36  5880.2  356.23  5904.1  356.44    5917  357.54
#Mann= 3 , 0 , 0
  4463.1     .11       0 4986.33     .06       0  5010.5     .11       0
Bank Sta=4986.33,5010.5
XS Rating Curve= 0 ,0
Exp/Cntr=0.3,0.1

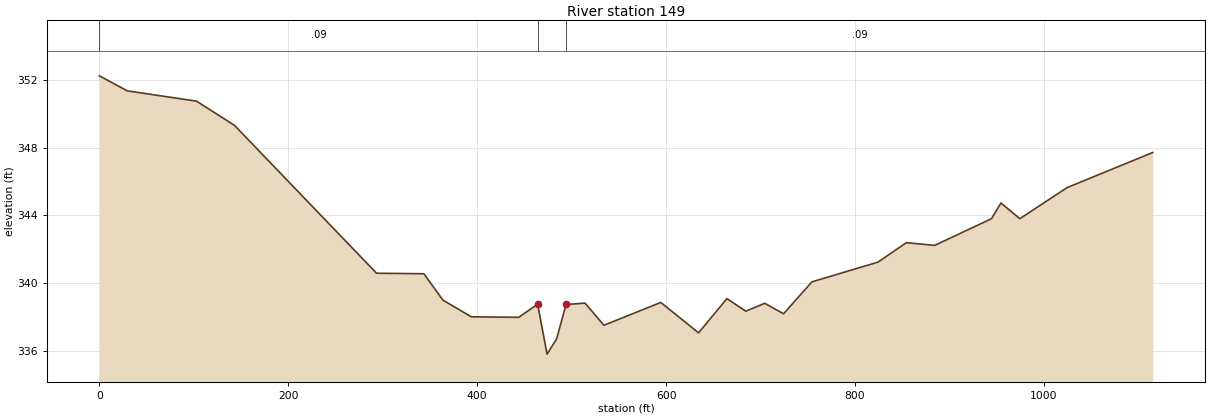
Type RM Length L Ch R = 1 ,149     ,0,0,0
BEGIN DESCRIPTION:
CCLC 120 1.0
END DESCRIPTION:
XS GIS Cut Line= 3
      3684120.46     10163843.62      3683541.01     10163888.86
      3683007.16     10163900.58
#Sta/Elev= 30
       0  352.27    29.6  351.38   102.9  350.77     143  349.34   293.5  340.58
   343.6  340.55   363.7  338.99   393.8     338     444  337.97     464  338.75
     474  335.79   484.1  336.69   494.1  338.73   514.2  338.81   534.2   337.5
   594.4  338.85   634.4  337.05   664.4  339.08   684.4  338.33   704.4   338.8
   724.4  338.18   754.4  340.07   824.4  341.24   854.4  342.39   884.4  342.23
   944.5  343.81   954.5  344.74   974.5  343.81  1024.5  345.65  1115.2  347.73
#Mann= 3 , 0 , 0
       0     .09       0     464     .06       0   494.1     .09       0
Bank Sta=464,494.1
XS Rating Curve= 0 ,0
Exp/Cntr=0.3,0.1

Chan Stop Cuts=-1
Use User Specified Reach Order=0
Composite Channel Slope=5