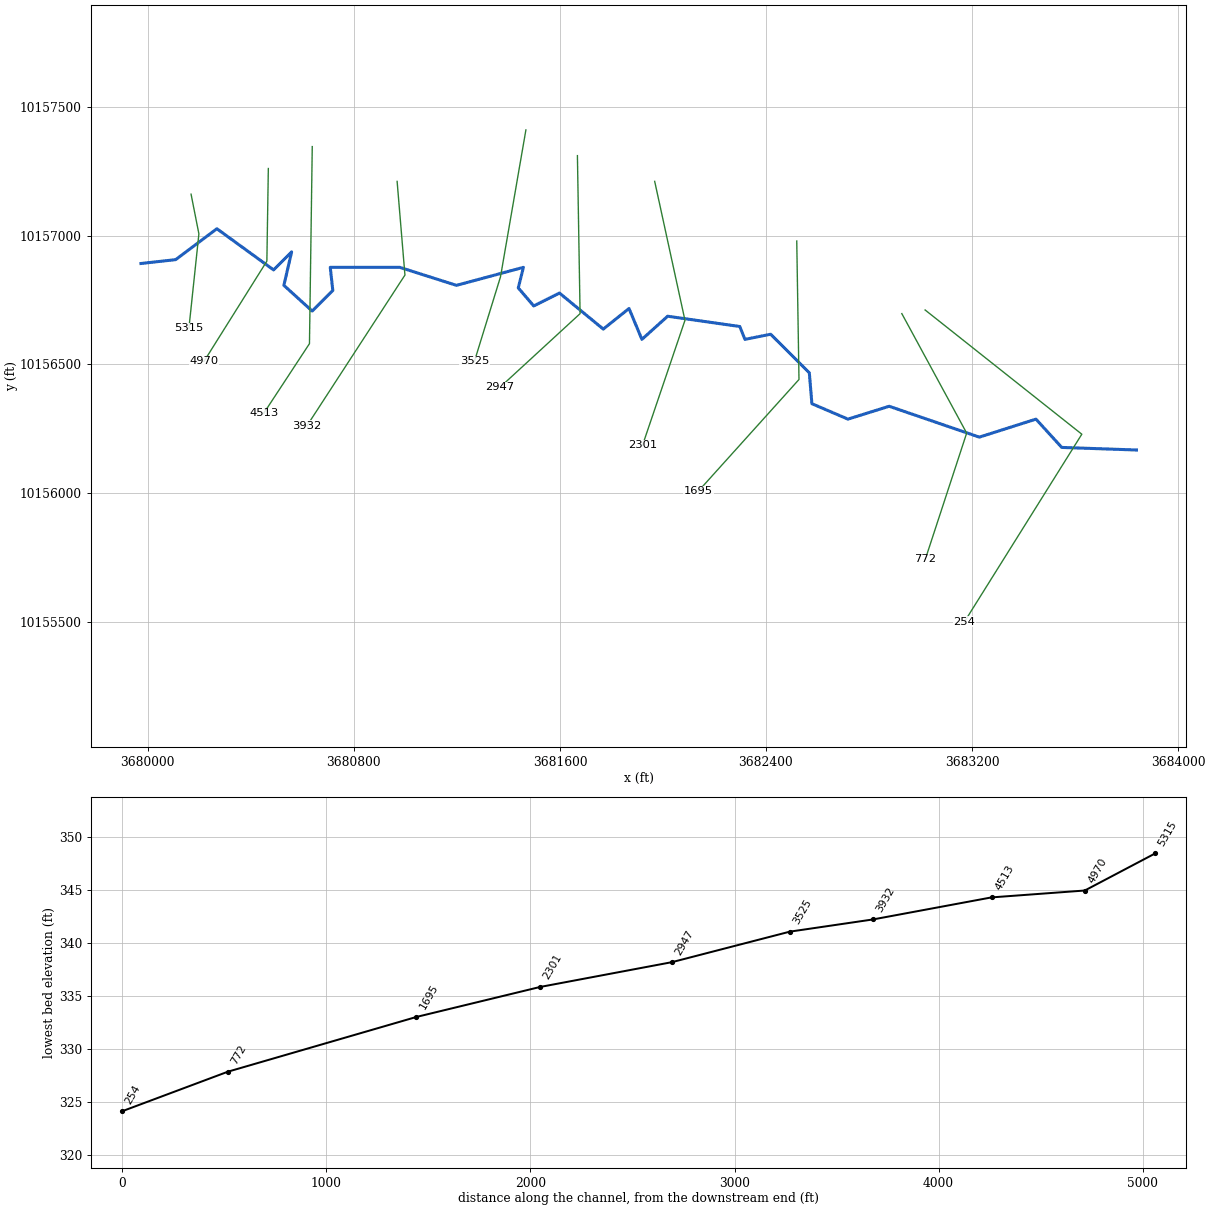
--- CCLC 121.prj (project) ---

Proj Title=CCLC 121 Base Level Engineering
Current Plan=p01
Default Exp/Contr=0.3,0.1
English Units
Geom File=g01
Flow File=f01
Flow File=f02
Plan File=p01
Y Axis Title=Elevation
X Axis Title(PF)=Main Channel Distance
X Axis Title(XS)=Station
BEGIN DESCRIPTION:
CCLC 121
END DESCRIPTION:
DSS Export Rating Curves= 0
DSS Export Rating Curve Sorted= 0
DSS Export Volume Flow Curves= 0
DXF OffsetX= 0
DXF OffsetY= 0
DXF ScaleX= 1
DXF ScaleY= 10

--- CCLC 121.p01 (plan) ---

Plan Title=Multiple Run
Short Identifier=Multiple
Geom File=g01
Flow File=f01
Subcritical Flow
K Sum by GR= 0
Std Step Tol= 0.01
Critical Tol= 0.01
Num of Std Step Trials= 20
Max Error Tol= 0.3
Flow Tol Ratio= 0.001
Split Flow NTrial= 30
Split Flow Tol= 0.02
Split Flow Ratio= 0.02
Log Output Level= 0
Friction Slope Method= 1
Unsteady Friction Slope Method= 2
Unsteady Bridges Friction Slope Method= 1
Parabolic Critical Depth
Global Vel Dist=  1 , 1 , 1
Global Log Level= 0
CheckData=True
Encroach Param= -1, 0, 0, 0
BEGIN DESCRIPTION:
Multiple Run
END DESCRIPTION:

--- CCLC 121.f01 (steady flow) ---

Flow Title=Multiple
Program Version=4.10
Number of Profiles= 7
Profile Names=10-year,25-year,50-year,1pct_min,100-year,1pct_plu,500-year
River Rch & RM=CCLC 121,Reach-1         ,5315
     598     811    1097     489    1476    4457    2761
Boundary for River Rch & Prof#=CCLC 121,Reach-1         , 1
Up Type= 0
Dn Type= 3
Dn Slope=0.005
Boundary for River Rch & Prof#=CCLC 121,Reach-1         , 2
Up Type= 0
Dn Type= 3
Dn Slope=0.005
Boundary for River Rch & Prof#=CCLC 121,Reach-1         , 3
Up Type= 0
Dn Type= 3
Dn Slope=0.005
Boundary for River Rch & Prof#=CCLC 121,Reach-1         , 4
Up Type= 0
Dn Type= 3
Dn Slope=0.005
Boundary for River Rch & Prof#=CCLC 121,Reach-1         , 5
Up Type= 0
Dn Type= 3
Dn Slope=0.005
Boundary for River Rch & Prof#=CCLC 121,Reach-1         , 6
Up Type= 0
Dn Type= 3
Dn Slope=0.005
Boundary for River Rch & Prof#=CCLC 121,Reach-1         , 7
Up Type= 0
Dn Type= 3
Dn Slope=0.005
DSS Import GetInterval= 0
DSS Import GetPeak= 0
DSS Import FillOption= 0

--- CCLC 121.f02 (steady flow) ---

Flow Title=Orig_BLE_Flows
Program Version=4.10
Number of Profiles= 7
Profile Names=10-year,25-year,50-year,1pct_min,100-year,1pct_plu,500-year
River Rch & RM=CCLC 121,Reach-1         ,5315
     598     795     954     376    1135    3428    1605
Boundary for River Rch & Prof#=CCLC 121,Reach-1         , 1
Up Type= 0
Dn Type= 3
Dn Slope=0.005
Boundary for River Rch & Prof#=CCLC 121,Reach-1         , 2
Up Type= 0
Dn Type= 3
Dn Slope=0.005
Boundary for River Rch & Prof#=CCLC 121,Reach-1         , 3
Up Type= 0
Dn Type= 3
Dn Slope=0.005
Boundary for River Rch & Prof#=CCLC 121,Reach-1         , 4
Up Type= 0
Dn Type= 3
Dn Slope=0.005
Boundary for River Rch & Prof#=CCLC 121,Reach-1         , 5
Up Type= 0
Dn Type= 3
Dn Slope=0.005
Boundary for River Rch & Prof#=CCLC 121,Reach-1         , 6
Up Type= 0
Dn Type= 3
Dn Slope=0.005
Boundary for River Rch & Prof#=CCLC 121,Reach-1         , 7
Up Type= 0
Dn Type= 3
Dn Slope=0.005
DSS Import GetInterval= 0
DSS Import GetPeak= 0
DSS Import FillOption= 0

--- CCLC 121.g01 (geometry) ---

Geom Title=Existing Conditions
Program Version=4.10

River Reach=CCLC 121        ,Reach-1
Reach XY= 30
      3679973.23     10156891.84      3680108.23     10156906.84
      3680268.23     10157026.84      3680488.23     10156866.84
      3680558.23     10156936.84      3680528.23     10156806.84
      3680638.23     10156706.84      3680718.23     10156786.84
      3680708.23     10156876.84      3680978.23     10156876.84
      3681198.23     10156806.84      3681458.23     10156876.84
      3681438.23     10156796.84      3681498.23     10156726.84
      3681598.23     10156776.84      3681768.23     10156636.84
      3681868.23     10156716.84      3681918.23     10156596.84
      3682018.23     10156686.84      3682298.23     10156646.84
      3682318.23     10156596.84      3682418.23     10156616.84
      3682568.23     10156466.84      3682578.23     10156346.84
      3682718.23     10156286.84      3682878.23     10156336.84
      3683228.23     10156216.84      3683448.23     10156286.84
      3683548.23     10156176.84      3683838.23     10156166.84

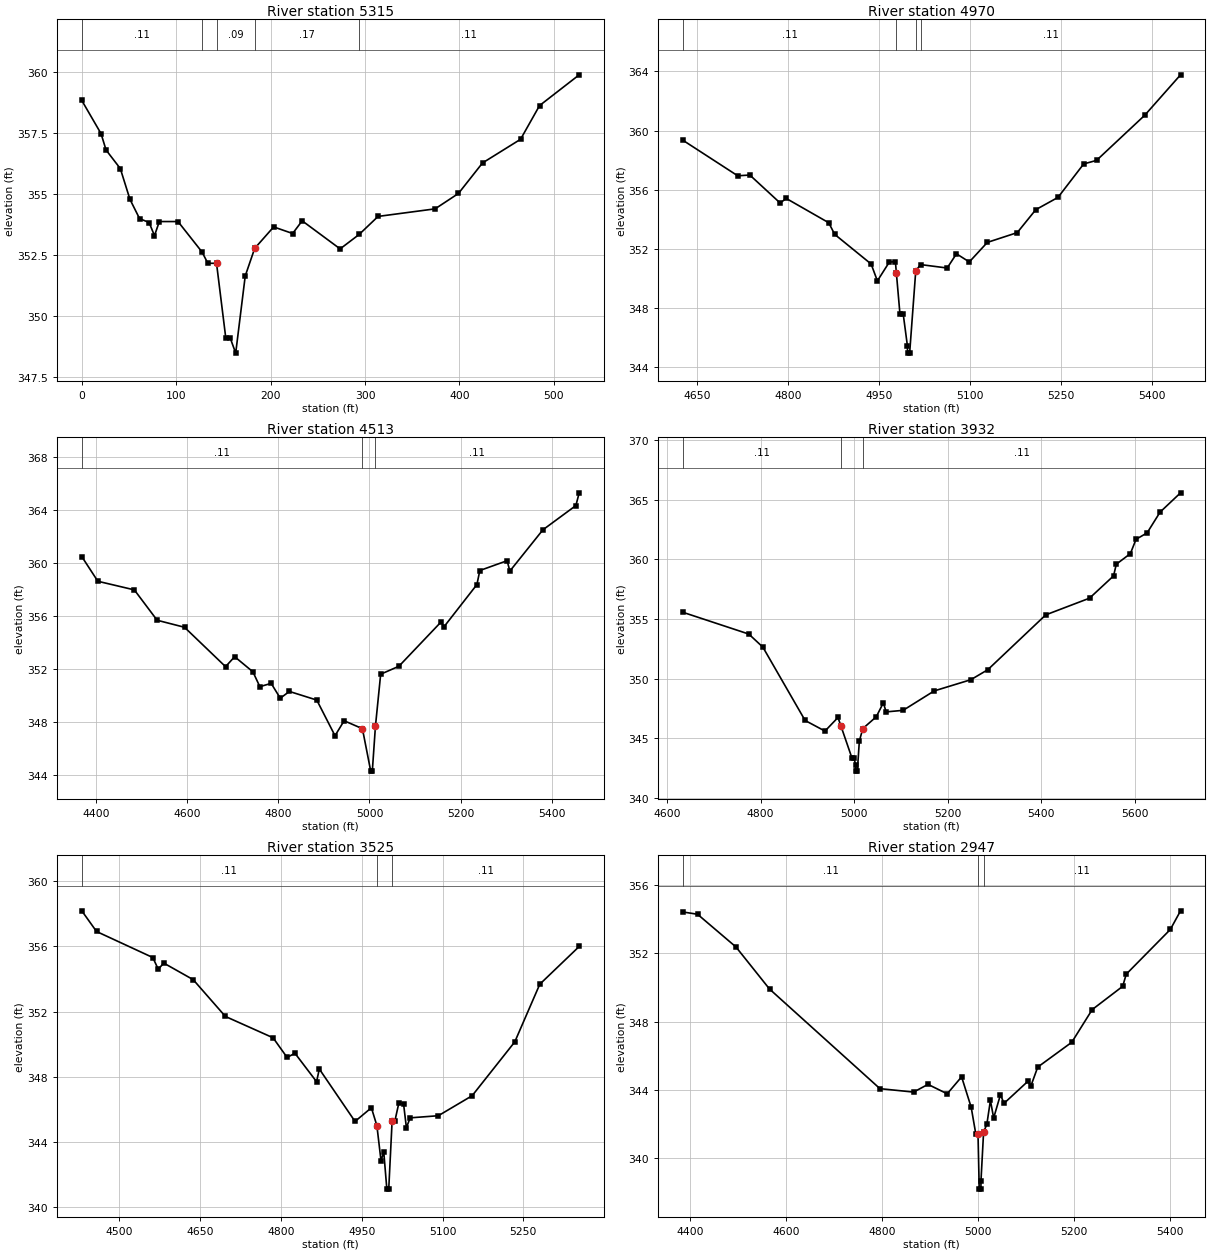
Type RM Length L Ch R = 1 ,5315    ,345,345,345
BEGIN DESCRIPTION:
CCLC 121 9.0
END DESCRIPTION:
XS GIS Cut Line= 3
      3680167.85     10157161.07      3680198.23     10157006.84
      3680159.37     10156639.32
#Sta/Elev= 30
       0  358.82    20.4  357.46    25.7  356.79    40.8  356.03      51  354.77
    61.2  353.98    71.3  353.82      77  353.28    82.1  353.86   101.9  353.86
   127.4  352.61   133.5  352.15   142.7  352.15   152.5  349.09   157.2  349.09
     163  348.47   173.1  351.63   183.1  352.76   203.2  353.64   223.3  353.37
   233.4  353.89   273.6  352.74   293.7  353.33   313.8  354.07   374.2  354.38
   398.9  355.01   424.4  356.26   464.7  357.23   484.8  358.61   526.8  359.87
#Mann= 5 ,-1 , 0
       0     .11       0   127.4     .17       0   142.7     .09       0
   183.1     .17       0   293.7     .11       0
Bank Sta=142.7,183.1
XS Rating Curve= 0 ,0
Exp/Cntr=0.3,0.1

Type RM Length L Ch R = 1 ,4970    ,457,457,457
BEGIN DESCRIPTION:
CCLC 121 8.0
END DESCRIPTION:
XS GIS Cut Line= 3
      3680467.85     10157261.03      3680462.15     10156900.96
      3680217.86     10156511.09
#Sta/Elev= 30
  4626.8  359.34  4716.8  356.95  4736.8     357  4786.8  355.11  4796.8  355.42
  4866.8  353.78  4876.8  352.99  4936.8  350.99  4947.1  349.85  4966.8  351.12
  4976.8  351.15  4978.4350.3976  4984.4  347.58  4989.8  347.58  4996.6  345.47
  4996.8  344.97  5000.3  344.97  5010.4  350.54  5018.5  350.95  5062.2  350.72
  5077.5  351.68  5098.7  351.13  5128.4  352.45  5177.7  353.11  5208.3  354.66
  5244.9  355.49  5287.3  357.75  5308.5  357.99    5388  361.04    5447  363.77
#Mann= 4 ,-1 , 0
  4626.8     .11       0  4978.4     .09       0  5010.4     .17       0
  5018.5     .11       0
Bank Sta=4978.4,5010.4
XS Rating Curve= 0 ,0
Exp/Cntr=0.3,0.1

Type RM Length L Ch R = 1 ,4513    ,581,581,581
BEGIN DESCRIPTION:
Mapping XS b94ba6bc
END DESCRIPTION:
XS GIS Cut Line= 3
      3680638.38     10157346.26      3680627.53     10156580.17
      3680449.58      10156308.9
#Sta/Elev= 30
  4369.3   360.5  4404.5  358.64  4484.5  357.99  4534.5   355.7  4594.5  355.17
  4684.5   352.2  4704.5  352.95  4744.5  351.81  4759.7  350.69  4784.5  350.94
  4804.5  349.82  4824.5  350.33  4884.5  349.68  4924.5  346.99  4944.5  348.12
  4984.6  347.52  5002.8  344.32  5006.3  344.32  5013.1347.6881  5024.6  351.63
  5064.6  352.23  5157.3  355.58  5163.3   355.2  5235.6  358.39    5242  359.45
  5301.8  360.19  5307.9  359.41  5380.3  362.52  5452.6  364.35  5459.9  365.31
#Mann= 3 , 0 , 0
  4369.3     .11       0  4984.6     .07       0  5013.1     .11       0
Bank Sta=4984.6,5013.1
XS Rating Curve= 0 ,0
Exp/Cntr=0.3,0.1

Type RM Length L Ch R = 1 ,3932    ,407,407,407
BEGIN DESCRIPTION:
CCLC 121 7.0
END DESCRIPTION:
XS GIS Cut Line= 3
      3680967.85     10157211.08      3680998.23     10156846.84
      3680617.87      10156261.1
#Sta/Elev= 30
  4634.5  355.56    4775  353.74  4805.1  352.64  4895.4  346.49  4937.9   345.6
  4965.7  346.74  4971.8346.0507  4995.4  343.36    5000  343.36  5003.4  342.74
  5003.6  342.24  5007.1  342.24  5011.4  344.76  5018.8  345.81  5047.6   346.8
  5062.7  347.97  5068.7  347.21    5105  347.34  5171.5  348.97  5249.9  349.91
  5286.2  350.75  5410.1  355.35  5503.7  356.75  5555.1  358.62    5561   359.6
  5591.1  360.49  5603.2  361.69  5626.9  362.23  5654.6  363.97  5698.4  365.59
#Mann= 3 , 0 , 0
  4634.5     .11       0  4971.8     .07       0  5018.8     .11       0
Bank Sta=4971.8,5018.8
XS Rating Curve= 0 ,0
Exp/Cntr=0.3,0.1

Type RM Length L Ch R = 1 ,3525    ,578,578,578
BEGIN DESCRIPTION:
CCLC 121 6.0
END DESCRIPTION:
XS GIS Cut Line= 3
      3681467.85     10157411.07      3681369.27     10156840.19
      3681267.86     10156511.09
#Sta/Elev= 30
  4430.1  358.19  4457.5  356.92    4562  355.32  4572.1   354.6  4582.3  354.98
    4637  353.96  4696.8   351.7  4785.3  350.39  4811.4  349.18  4825.9  349.44
  4866.1  347.69  4871.2  348.47  4937.5  345.25  4967.9  346.09  4978.1  344.99
  4985.8  342.82  4990.8   343.4  4996.6  341.09  5000.1  341.09  5006.4  345.29
  5011.6  345.29    5019   346.4  5027.7  346.31  5032.9  344.87  5039.9  345.47
  5092.2   345.6    5155  346.83  5234.2  350.14  5280.6  353.68  5353.8     356
#Mann= 3 , 0 , 0
  4430.1     .11       0  4978.1     .07       0  5006.4     .11       0
Bank Sta=4978.1,5006.4
XS Rating Curve= 0 ,0
Exp/Cntr=0.3,0.1

Type RM Length L Ch R = 1 ,2947    ,646,646,646
BEGIN DESCRIPTION:
CCLC 121 5.0
END DESCRIPTION:
XS GIS Cut Line= 3
      3681667.85     10157311.06      3681678.23     10156696.84
      3681367.85     10156411.07
#Sta/Elev= 30
  4385.7   354.4  4415.7  354.27  4495.7  352.36  4565.7   349.9  4795.7  344.08
  4865.8  343.88  4895.8  344.33  4935.8  343.78  4965.8  344.77  4985.8  342.99
  4995.4  341.43    5000  341.43  5002.5  338.21    5006  338.21  5006.2  338.71
  5011.6  341.54  5018.4     342  5025.8  343.39  5032.6  342.37  5046.8  343.73
  5054.1  343.22  5103.5   344.5  5110.3  344.25  5124.4  345.34  5195.3  346.79
  5237.9   348.7  5301.4  350.06  5308.8  350.77  5400.6  353.38  5421.9  354.47
#Mann= 3 , 0 , 0
  4385.7     .11       0    5000     .07       0  5011.6     .11       0
Bank Sta=5000,5011.6
XS Rating Curve= 0 ,0
Exp/Cntr=0.3,0.1

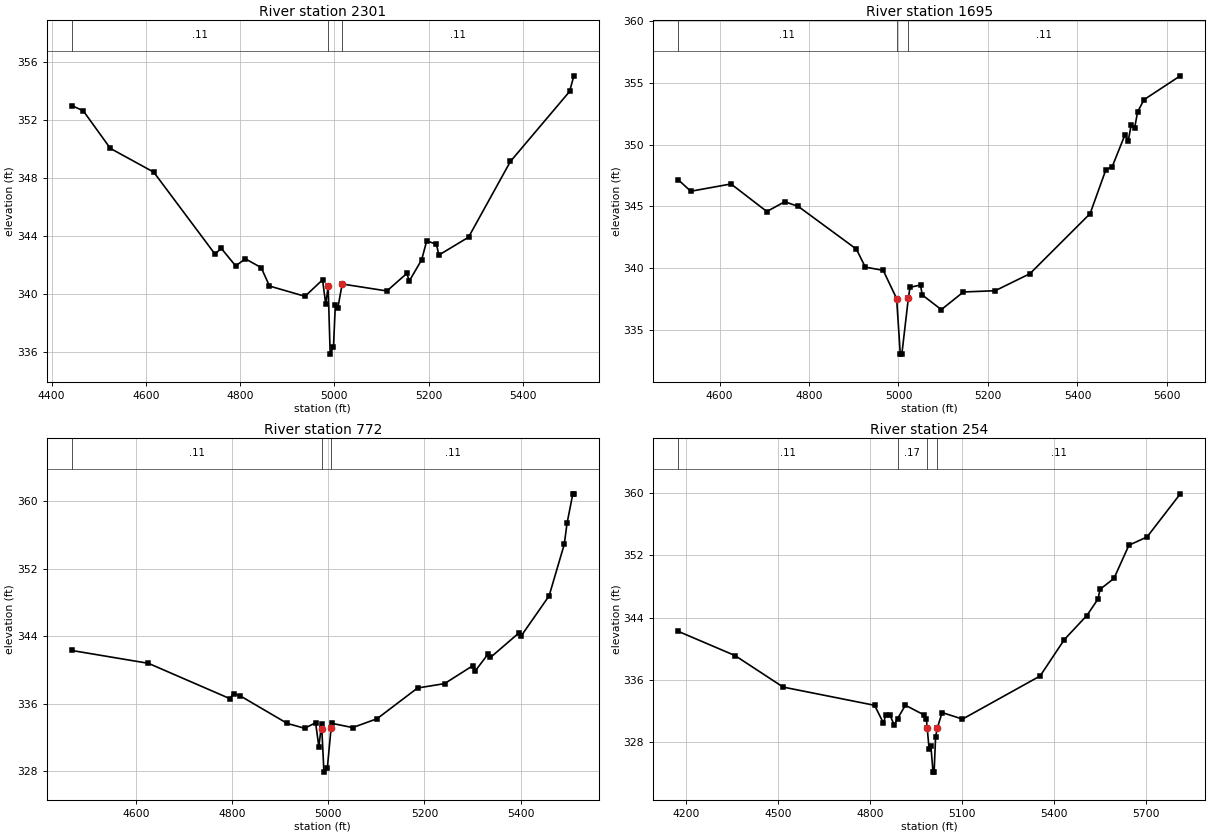
Type RM Length L Ch R = 1 ,2301    ,606,606,606
BEGIN DESCRIPTION:
CCLC 121 4.0
END DESCRIPTION:
XS GIS Cut Line= 3
      3681967.85     10157211.07      3682085.41     10156670.92
      3681920.68      10156185.4
#Sta/Elev= 30
  4442.9  353.03  4467.4  352.66  4524.8  350.07  4616.9  348.43  4746.7  342.78
  4760.2  343.17  4790.7  341.96  4811.3  342.45  4844.9  341.84  4862.5  340.57
  4937.9  339.86  4975.1     341  4981.9  339.31    4987  340.54  4991.3  335.87
  4998.3  336.37  5002.2  339.24  5007.5  339.04  5016.7  340.71  5111.7  340.23
  5153.9  341.44  5159.2  340.92  5185.4  342.38  5196.2  343.69  5216.8  343.45
    5222  342.71  5284.9  343.94  5373.8  349.17  5499.4     354  5508.4  355.08
#Mann= 3 , 0 , 0
  4442.9     .11       0    4987     .07       0  5016.7     .11       0
Bank Sta=4987,5016.7
XS Rating Curve= 0 ,0
Exp/Cntr=0.3,0.1

Type RM Length L Ch R = 1 ,1695    ,923,923,923
BEGIN DESCRIPTION:
CCLC 121 3.0
END DESCRIPTION:
XS GIS Cut Line= 3
      3682519.44     10156979.08      3682528.12     10156440.89
      3682137.49     10156006.85
#Sta/Elev= 30
  4507.7  347.15  4535.7  346.22  4625.7  346.81  4705.7  344.58  4745.7  345.37
  4775.7     345  4905.8  341.54  4925.8  340.08  4965.8  339.82  4995.8  337.54
    5004  333.04  5007.5  333.04 5022.12337.5963  5025.8  338.45  5049.2  338.63
  5053.1  337.83  5095.7  336.64  5145.1  338.07  5216.1  338.17  5293.8  339.55
  5428.3  344.41  5463.5  347.96  5477.7  348.21  5506.1  350.78  5513.6  350.32
  5520.3  351.62  5527.8  351.35  5534.5  352.64  5548.7  353.63  5629.9  355.56
#Mann= 3 , 0 , 0
  4507.7     .11       0  4995.8     .07       0 5022.12     .11       0
Bank Sta=4995.8,5022.12
XS Rating Curve= 0 ,0
Exp/Cntr=0.3,0.1

Type RM Length L Ch R = 1 ,772     ,518,518,518
BEGIN DESCRIPTION:
CCLC 121 2.0
END DESCRIPTION:
XS GIS Cut Line= 3
      3682927.43     10156696.95      3683179.16     10156232.56
      3683018.57     10155742.11
#Sta/Elev= 30
  4466.5   342.3  4625.8  340.78    4795   336.6  4803.1   337.2  4816.9  336.92
  4914.8  333.65  4950.9  333.08  4973.7  333.73  4980.4  330.89  4986.1  333.56
  4986.6332.9969    4991  327.88  4998.1  328.38 5005.81333.0682  5006.8  333.67
  5050.7  333.16  5101.5  334.21  5185.7  337.85  5241.8  338.37  5300.2  340.48
  5305.5  339.86  5332.1  341.86  5337.3  341.47  5395.8  344.34    5401     344
  5459.3  348.77  5490.9  354.89  5496.6  357.36  5508.7  360.87  5510.8  360.87
#Mann= 3 , 0 , 0
  4466.5     .11       0  4986.6     .07       0 5005.81     .11       0
Bank Sta=4986.6,5005.81
XS Rating Curve= 0 ,0
Exp/Cntr=0.3,0.1

Type RM Length L Ch R = 1 ,254     ,0,0,0
BEGIN DESCRIPTION:
CCLC 121 1.0
END DESCRIPTION:
XS GIS Cut Line= 3
      3683017.83     10156711.09      3683626.21     10156228.22
      3683170.47     10155499.03
#Sta/Elev= 30
  4174.5  342.23  4359.6  339.12  4516.6  335.07  4814.6  332.73  4843.4  330.45
  4851.2   331.5  4864.2  331.53  4878.7  330.17  4889.3  331.02    4915  332.74
  4976.9  331.47  4983.2  331.01  4986.1329.7727  4992.2  327.17  4998.1  327.47
  5005.1  324.15  5008.6  324.15  5013.4   328.7  5019.3  329.85  5034.7   331.8
  5101.1  330.96  5354.2   336.5  5433.2  341.18  5506.4  344.26  5542.9  346.38
  5549.3  347.62  5594.8  349.03  5643.6  353.29  5702.6  354.35  5811.1  359.89
#Mann= 4 ,-1 , 0
  4174.5     .11       0  4889.3     .17       0  4986.1     .07       0
  5019.3     .11       0
Bank Sta=4986.1,5019.3
XS Rating Curve= 0 ,0
Exp/Cntr=0.3,0.1

Chan Stop Cuts=-1
Use User Specified Reach Order=0
Composite Channel Slope=5