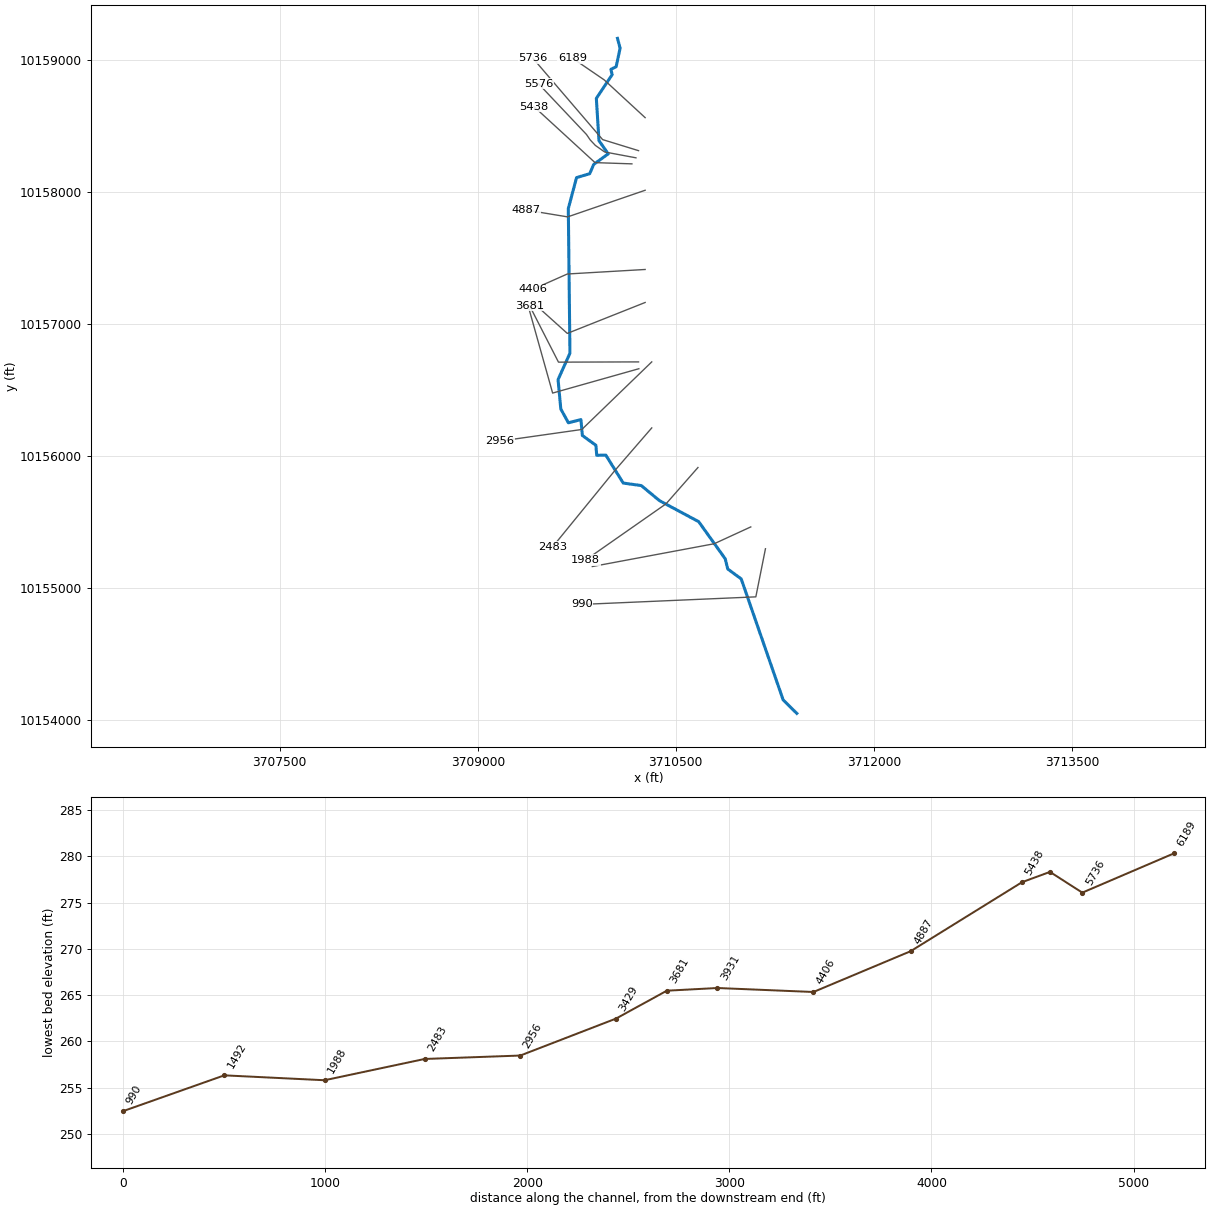
--- CCLC 124.prj (project) ---

Proj Title=CCLC 124 Base Level Engineering
Current Plan=p01
Default Exp/Contr=0.3,0.1
English Units
Geom File=g01
Flow File=f01
Flow File=f02
Plan File=p01
Y Axis Title=Elevation
X Axis Title(PF)=Main Channel Distance
X Axis Title(XS)=Station
BEGIN DESCRIPTION:
CCLC 124
END DESCRIPTION:
DSS Export Rating Curves= 0
DSS Export Rating Curve Sorted= 0
DSS Export Volume Flow Curves= 0
DXF OffsetX= 0
DXF OffsetY= 0
DXF ScaleX= 1
DXF ScaleY= 10

--- CCLC 124.p01 (plan) ---

Plan Title=Multiple Run
Short Identifier=Multiple
Geom File=g01
Flow File=f01
Subcritical Flow
K Sum by GR= 0
Std Step Tol= 0.01
Critical Tol= 0.01
Num of Std Step Trials= 20
Max Error Tol= 0.3
Flow Tol Ratio= 0.001
Split Flow NTrial= 30
Split Flow Tol= 0.02
Split Flow Ratio= 0.02
Log Output Level= 0
Friction Slope Method= 1
Unsteady Friction Slope Method= 2
Unsteady Bridges Friction Slope Method= 1
Parabolic Critical Depth
Global Vel Dist=  1 , 1 , 1
Global Log Level= 0
CheckData=True
Encroach Param= -1, 0, 0, 0
BEGIN DESCRIPTION:
Multiple Run
END DESCRIPTION:

--- CCLC 124.f01 (steady flow) ---

Flow Title=Multiple
Program Version=4.10
Number of Profiles= 7
Profile Names=10-year,25-year,50-year,1pct_min,100-year,1pct_plu,500-year
River Rch & RM=CCLC 124,Reach-1         ,6189
     473     631     843     371    1121    3385    2049
River Rch & RM=CCLC 124,Reach-1         ,5438
     521     699     937     414    1251    3778    2301
River Rch & RM=CCLC 124,Reach-1         ,2956
    1499    2117    2938    1337    4038   12195    7902
Boundary for River Rch & Prof#=CCLC 124,Reach-1         , 1
Up Type= 0
Dn Type= 3
Dn Slope=0.005
Boundary for River Rch & Prof#=CCLC 124,Reach-1         , 2
Up Type= 0
Dn Type= 3
Dn Slope=0.005
Boundary for River Rch & Prof#=CCLC 124,Reach-1         , 3
Up Type= 0
Dn Type= 3
Dn Slope=0.005
Boundary for River Rch & Prof#=CCLC 124,Reach-1         , 4
Up Type= 0
Dn Type= 3
Dn Slope=0.005
Boundary for River Rch & Prof#=CCLC 124,Reach-1         , 5
Up Type= 0
Dn Type= 3
Dn Slope=0.005
Boundary for River Rch & Prof#=CCLC 124,Reach-1         , 6
Up Type= 0
Dn Type= 3
Dn Slope=0.005
Boundary for River Rch & Prof#=CCLC 124,Reach-1         , 7
Up Type= 0
Dn Type= 3
Dn Slope=0.005
DSS Import GetInterval= 0
DSS Import GetPeak= 0
DSS Import FillOption= 0

--- CCLC 124.f02 (steady flow) ---

Flow Title=Orig_BLE_Flows
Program Version=4.10
Number of Profiles= 7
Profile Names=10-year,25-year,50-year,1pct_min,100-year,1pct_plu,500-year
River Rch & RM=CCLC 124,Reach-1         ,6189
     473     619     733     286     862    2604    1191
River Rch & RM=CCLC 124,Reach-1         ,5438
     521     685     815     319     962    2905    1338
River Rch & RM=CCLC 124,Reach-1         ,2956
    1499    2075    2555    1029    3106    9381    4594
Boundary for River Rch & Prof#=CCLC 124,Reach-1         , 1
Up Type= 0
Dn Type= 3
Dn Slope=0.005
Boundary for River Rch & Prof#=CCLC 124,Reach-1         , 2
Up Type= 0
Dn Type= 3
Dn Slope=0.005
Boundary for River Rch & Prof#=CCLC 124,Reach-1         , 3
Up Type= 0
Dn Type= 3
Dn Slope=0.005
Boundary for River Rch & Prof#=CCLC 124,Reach-1         , 4
Up Type= 0
Dn Type= 3
Dn Slope=0.005
Boundary for River Rch & Prof#=CCLC 124,Reach-1         , 5
Up Type= 0
Dn Type= 3
Dn Slope=0.005
Boundary for River Rch & Prof#=CCLC 124,Reach-1         , 6
Up Type= 0
Dn Type= 3
Dn Slope=0.005
Boundary for River Rch & Prof#=CCLC 124,Reach-1         , 7
Up Type= 0
Dn Type= 3
Dn Slope=0.005
DSS Import GetInterval= 0
DSS Import GetPeak= 0
DSS Import FillOption= 0

--- CCLC 124.g01 (geometry) ---

Geom Title=Existing Conditions
Program Version=4.10

River Reach=CCLC 124        ,Reach-1
Reach XY= 30
      3710058.23     10159161.84      3710078.23     10159086.84
      3710048.23     10158946.84      3710008.23     10158926.84
      3710018.23     10158886.84      3709898.23     10158706.84
      3709918.23     10158386.84      3709988.23     10158286.84
      3709878.23     10158206.84      3709848.23     10158136.84
      3709748.23     10158106.84      3709685.87     10157872.44
      3709698.23     10156776.84      3709608.23     10156576.84
      3709629.14     10156354.08      3709686.55     10156249.74
      3709781.41     10156274.08      3709792.33     10156153.73
      3709894.78     10156079.09      3709900.97     10156003.62
      3709969.97     10156005.13      3710101.98     10155793.24
      3710239.02     10155774.17      3710376.63     10155659.92
       3710673.5     10155500.75      3710874.58     10155219.16
       3710893.5     10155142.15      3710995.39     10155067.62
      3711313.24     10154150.61      3711416.42     10154048.81

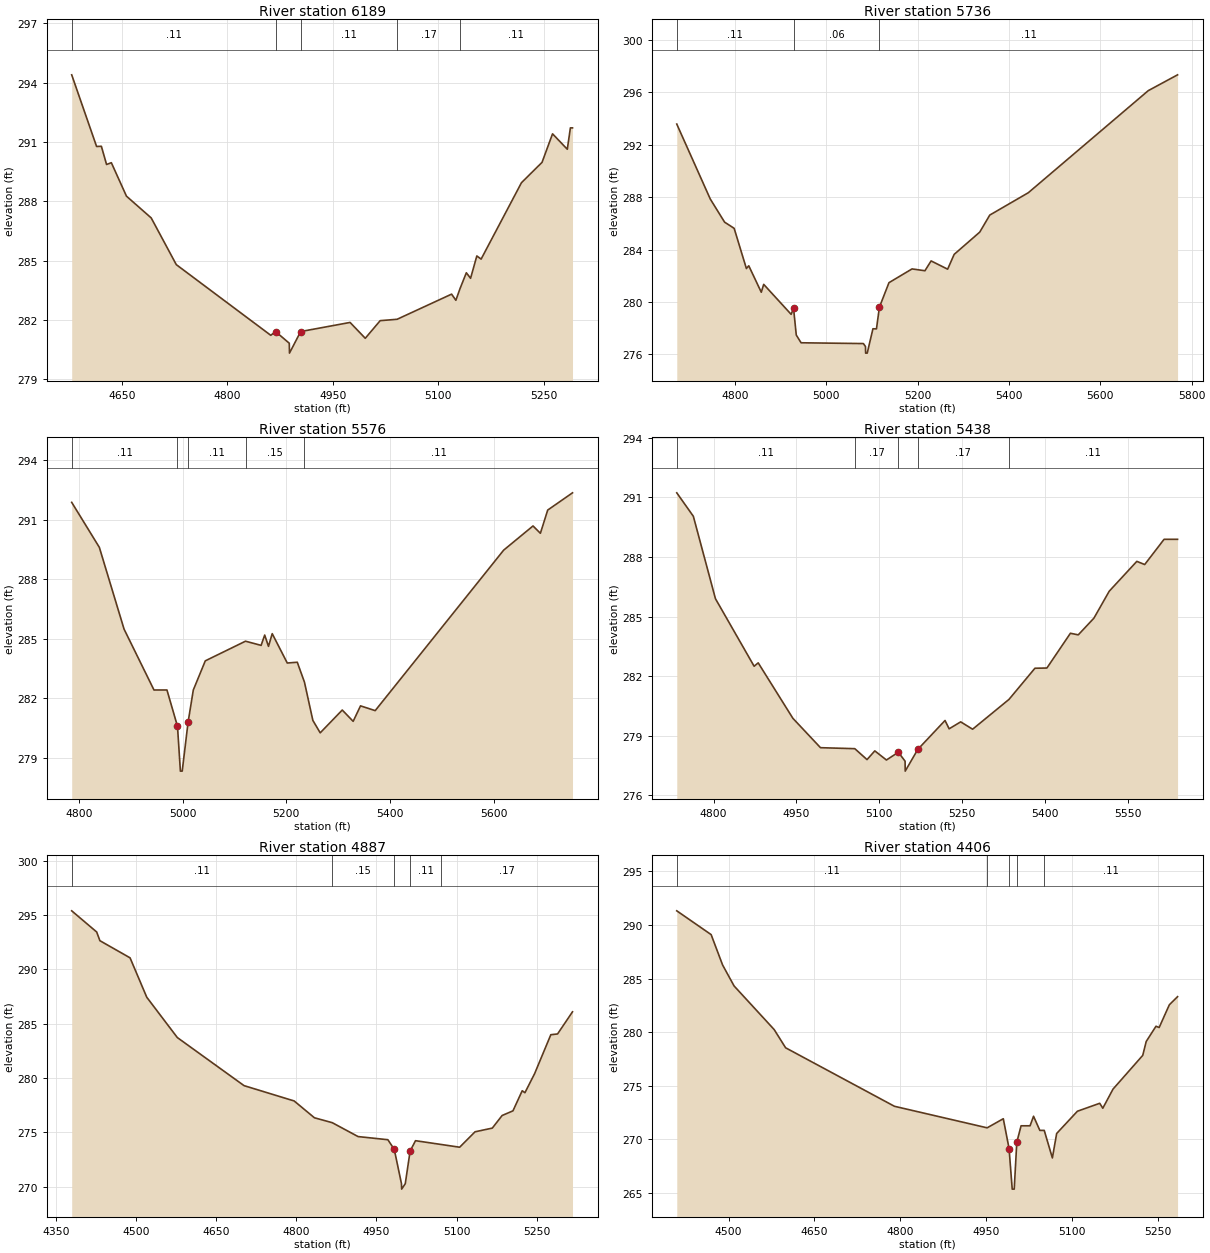
Type RM Length L Ch R = 1 ,6189    ,453,453,453
BEGIN DESCRIPTION:
CCLC 124 12.0
END DESCRIPTION:
XS GIS Cut Line= 3
      3710267.82      10158561.1      3709958.23     10158846.84
      3709717.87     10159011.06
#Sta/Elev= 30
  4578.7  294.39  4614.1  290.77  4620.9  290.78  4628.3  289.86  4635.1  289.95
  4656.6  288.26  4691.8  287.16  4727.5   284.8  4861.9  281.23  4868.7  281.42
  4888.2  280.83  4888.5  280.33  4904.4  281.42  4974.7  281.88  4996.3  281.08
  5017.5  281.97  5041.6  282.04  5119.1  283.31  5125.2     283  5131.1  283.59
  5140.1  284.39  5146.1  284.11    5155  285.24  5161.1  285.08  5218.5  288.94
  5247.8  289.97  5262.7  291.41  5283.7  290.63  5288.1  291.71  5291.1  291.71
#Mann= 5 ,-1 , 0
  4578.7     .11       0  4868.7     .06       0  4904.4     .11       0
  5041.6     .17       0  5131.1     .11       0
Bank Sta=4868.7,4904.4
XS Rating Curve= 0 ,0
Exp/Cntr=0.3,0.1

Type RM Length L Ch R = 1 ,5736    ,160,160,160
BEGIN DESCRIPTION:
CCLC 124 11.0
END DESCRIPTION:
XS GIS Cut Line= 3
      3710217.89     10158311.06      3709945.65     10158394.88
      3709417.84     10159011.09
#Sta/Elev= 30
    4673  293.58  4746.3  287.86  4777.7  286.09  4798.6  285.62  4825.4  282.55
  4830.6  282.76    4858  280.74  4863.3  281.34  4923.4  279.05  4928.6  279.52
  4934.6  277.47  4945.1  276.88  5081.5  276.82  5086.1  276.59  5086.4  276.09
  5089.9  276.09  5102.4  277.95  5110.1  277.94  5116.6   279.6  5137.5  281.47
    5188  282.52  5216.2  282.38  5229.7  283.13  5265.9   282.5  5280.2  283.63
  5336.2  285.33  5358.1  286.63  5442.6  288.34    5705  296.13  5769.2  297.34
#Mann= 3 , 0 , 0
    4673     .11       0  4928.6     .06       0  5116.6     .11       0
Bank Sta=4928.6,5116.6
XS Rating Curve= 0 ,0
Exp/Cntr=0.3,0.1

Type RM Length L Ch R = 1 ,5576    ,138,138,138
BEGIN DESCRIPTION:
Mapping XS 93d47814
END DESCRIPTION:
XS GIS Cut Line= 6
       3710198.3     10158256.85      3709961.28     10158301.13
      3709890.97     10158350.61       3709851.9     10158392.28
      3709823.26     10158433.94      3709458.68     10158819.36
#Sta/Elev= 30
  4786.3  291.88  4839.6  289.61  4887.2  285.49  4944.9  282.42  4969.9  282.42
  4990.2  280.59  4995.8  278.33  4999.3  278.33  5010.6  280.79  5020.7  282.42
  5043.8  283.89  5121.3  284.88  5151.4  284.67  5158.3  285.19  5165.6  284.62
  5172.8  285.26  5201.8  283.78  5221.1  283.82    5235  282.81  5251.1  280.89
  5265.3  280.26  5307.8  281.41  5328.8  280.84    5343  281.62  5371.3  281.38
  5618.9  289.47  5675.5  290.69  5689.7  290.32  5703.8  291.49  5751.6  292.36
#Mann= 5 ,-1 , 0
  4786.3     .11       0  4990.2     .06       0  5010.6     .11       0
  5121.3     .15       0    5235     .11       0
Bank Sta=4990.2,5010.6
XS Rating Curve= 0 ,0
Exp/Cntr=0.3,0.1

Type RM Length L Ch R = 1 ,5438    ,551,551,551
BEGIN DESCRIPTION:
CCLC 124 10.0
END DESCRIPTION:
XS GIS Cut Line= 3
      3710167.81     10158211.07      3709888.36      10158220.4
      3709426.53     10158644.04
#Sta/Elev= 30
  4733.4  291.23  4763.4  290.05  4803.4   285.9  4873.4   282.5  4880.8  282.67
  4943.5  279.88  4993.5   278.4  5055.6  278.35  5077.7   277.8  5091.8  278.24
  5112.8  277.78  5134.4  278.17  5146.6  277.72  5146.8  277.22  5169.5  278.31
  5218.9  279.77  5226.3  279.35  5247.2   279.7  5268.8  279.33  5334.6  280.83
  5381.6   282.4  5403.2  282.41  5445.8  284.16    5460  284.08  5488.3  284.92
  5516.1  286.28    5566  287.78  5580.2  287.62  5615.3  288.89  5639.7  288.89
#Mann= 5 ,-1 , 0
  4733.4     .11       0  5055.6     .17       0  5134.4     .06       0
  5169.5     .17       0  5334.6     .11       0
Bank Sta=5134.4,5169.5
XS Rating Curve= 0 ,0
Exp/Cntr=0.3,0.1

Type RM Length L Ch R = 1 ,4887    ,481,481,481
BEGIN DESCRIPTION:
CCLC 124 9.0
END DESCRIPTION:
XS GIS Cut Line= 3
      3710267.82     10158011.06      3709680.79      10157809.4
      3709367.83     10157861.08
#Sta/Elev= 30
  4379.3  295.39  4426.1  293.44  4432.1  292.64  4488.6  291.06  4519.9  287.43
  4577.1  283.72  4702.1  279.29  4795.9  277.88  4833.9  276.33  4867.2  275.88
  4915.6   274.6  4971.4  274.31  4983.4  273.42  4996.9  270.26  4997.2  269.76
    5004  270.26  5013.1  273.27  5023.2  274.22  5071.5  273.87  5105.9  273.62
  5134.7  275.04    5167  275.38  5185.4  276.54  5205.7  276.97    5223  278.82
  5228.1  278.64  5246.2  280.39  5276.6  283.98  5289.2  284.05  5317.2  286.09
#Mann= 5 ,-1 , 0
  4379.3     .11       0  4867.2     .15       0  4983.4     .07       0
  5013.1     .11       0  5071.5     .17       0
Bank Sta=4983.4,5013.1
XS Rating Curve= 0 ,0
Exp/Cntr=0.3,0.1

Type RM Length L Ch R = 1 ,4406    ,475,475,475
BEGIN DESCRIPTION:
CCLC 124 8.0
END DESCRIPTION:
XS GIS Cut Line= 3
      3710267.84     10157411.07      3709678.23     10157376.84
      3709417.81     10157261.05
#Sta/Elev= 30
  4409.4  291.32  4469.5   289.1  4489.5  286.27  4509.6  284.31  4579.7  280.24
  4599.7  278.54    4790  273.08  4952.1  271.07  4980.3  271.92  4990.4  269.14
  4995.9  265.35  4999.4  265.35  5003.9  269.72  5011.4  271.26  5027.1  271.26
  5033.2  272.15  5044.2  270.83  5051.9  270.83  5066.1  268.26  5073.6  270.54
  5109.9  272.62  5148.9  273.36  5154.3   272.9  5172.1  274.68  5224.1  277.83
  5230.2  279.13  5247.3  280.55  5252.8  280.43  5270.6  282.55    5285  283.31
#Mann= 5 ,-1 , 0
  4409.4     .11       0  4952.1     .17       0  4990.4     .09       0
  5003.9     .17       0  5051.9     .11       0
Bank Sta=4990.4,5003.9
XS Rating Curve= 0 ,0
Exp/Cntr=0.3,0.1

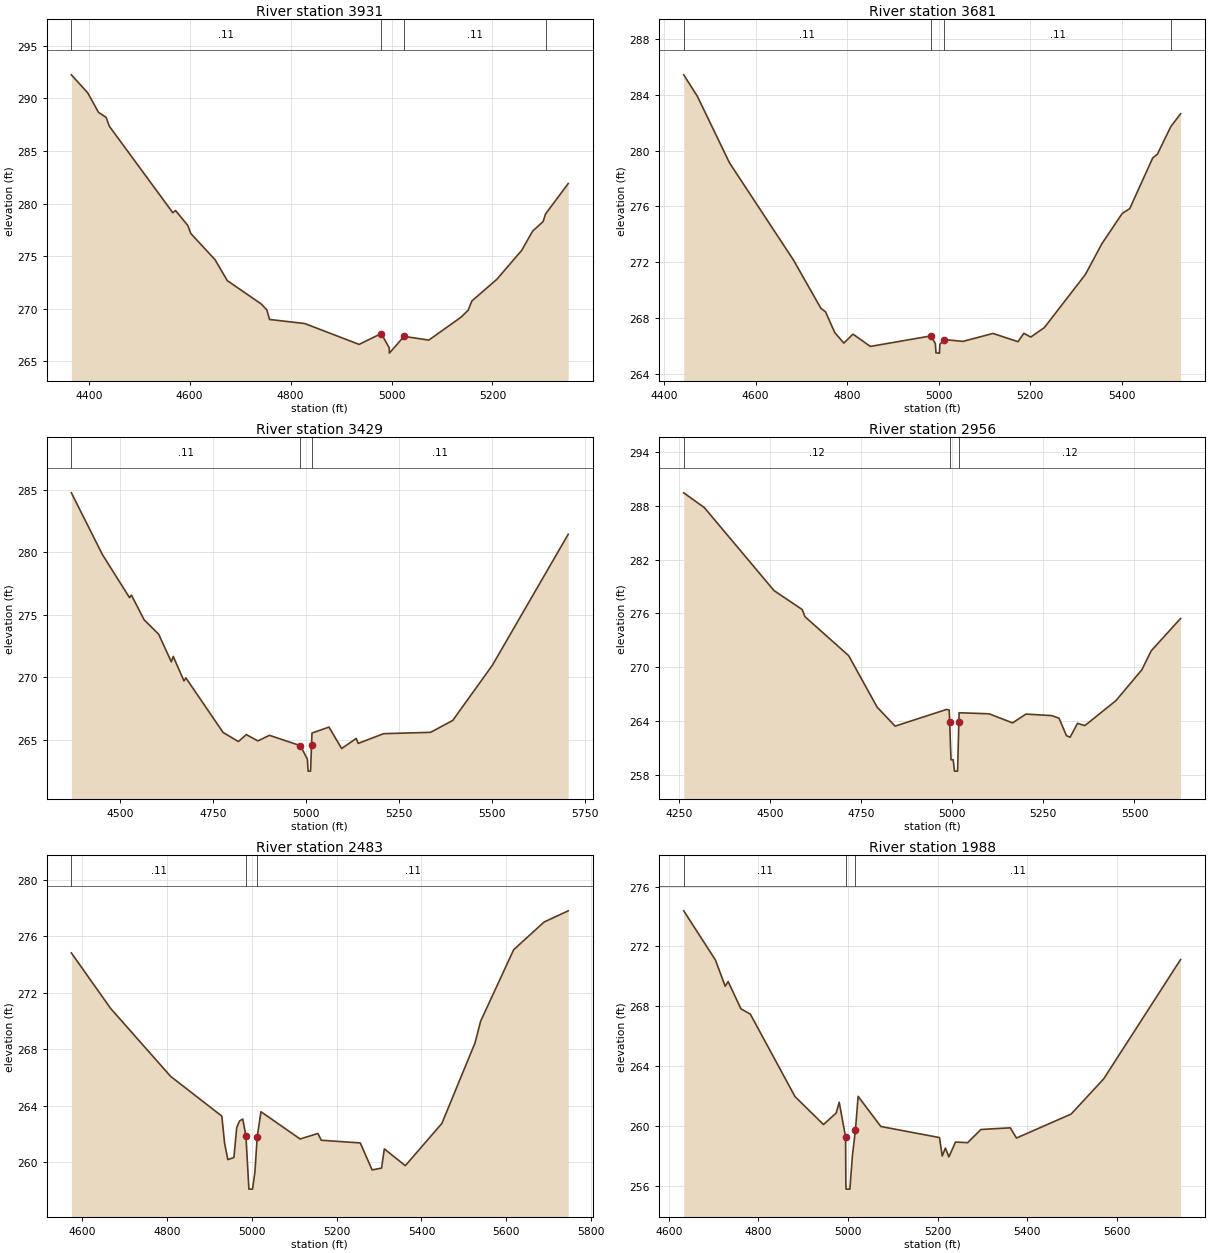
Type RM Length L Ch R = 1 ,3931    ,250,250,250
BEGIN DESCRIPTION:
CCLC 124 7.0
END DESCRIPTION:
XS GIS Cut Line= 3
      3710267.81     10157161.06      3709678.23     10156926.84
      3709417.87     10157161.05
#Sta/Elev= 30
  4365.6  292.23  4397.8  290.53  4419.4  288.66  4434.4  288.19  4440.9  287.34
  4566.7  279.12    4572  279.34  4596.3  277.91  4602.3  277.15  4650.3  274.66
  4674.6  272.67  4742.2  270.44  4752.9  269.89  4758.3  268.98  4828.2  268.59
  4935.8  266.61  4979.6  267.64  4995.5  266.28  4995.8  265.78  5024.7  267.37
    5074  267.02  5137.6  269.19  5151.8  269.85  5159.3  270.74  5208.6  272.79
  5257.9  275.54  5279.6  277.37  5300.5  278.29  5305.2     279  5350.2   281.9
#Mann= 4 ,-1 , 0
  4365.6     .11       0  4979.6     .06       0  5024.7     .11       0
  5305.2     .17       0
Bank Sta=4979.6,5024.7
XS Rating Curve= 0 ,0
Exp/Cntr=0.3,0.1

Type RM Length L Ch R = 1 ,3681    ,252,252,252
BEGIN DESCRIPTION:
CCLC 124 6.0
END DESCRIPTION:
XS GIS Cut Line= 3
      3710217.86     10156711.07      3709611.45     10156709.12
      3709392.84      10157136.1
#Sta/Elev= 30
  4442.8  285.42  4472.8  283.87  4542.8  279.12  4682.8  272.15  4742.8  268.69
  4752.8  268.45  4772.8  266.97  4792.8  266.21  4812.8  266.85  4850.8  265.97
  4982.8  266.72  4992.8  266.18 4994.23  265.51 5001.82  265.49  5002.8  266.13
  5012.8  266.46  5053.1  266.33  5118.8   266.9  5173.6  266.31  5186.2  266.91
  5201.4  266.64  5231.2  267.32    5321  271.13  5356.8  273.32  5401.3  275.49
  5417.8  275.84  5467.9  279.46  5478.3  279.74  5507.5  281.71  5528.9  282.63
#Mann= 4 ,-1 , 0
  4442.8     .11       0  4982.8     .06       0  5012.8     .11       0
  5507.5     .17       0
Bank Sta=4982.8,5012.8
XS Rating Curve= 0 ,0
Exp/Cntr=0.3,0.1

Type RM Length L Ch R = 1 ,3429    ,473,473,473
BEGIN DESCRIPTION:
Mapping XS 2adf2441
END DESCRIPTION:
XS GIS Cut Line= 3
      3710220.32     10156659.37      3709567.12     10156474.91
      3709389.53     10157107.31
#Sta/Elev= 30
  4369.5  284.77  4452.6  279.84  4525.8  276.37    4531  276.57    4565   274.6
  4604.1  273.44  4638.1  271.23  4643.3  271.66  4672.1   269.7  4677.3  269.94
  4777.3  265.57  4818.4  264.84  4839.7   265.4  4870.8  264.89    4902  265.34
  4985.1  264.51  5003.9  263.43  5005.8  262.47  5012.5  262.47  5015.1264.5929
  5016.3  265.52  5061.9     266    5096  264.28  5135.3  265.09  5140.5  264.69
  5208.6  265.47  5335.1  265.58  5394.6  266.53  5501.3  270.96  5705.1  281.45
#Mann= 3 , 0 , 0
  4369.5     .11       0  4985.1     .07       0  5015.1     .11       0
Bank Sta=4985.1,5015.1
XS Rating Curve= 0 ,0
Exp/Cntr=0.3,0.1

Type RM Length L Ch R = 1 ,2956    ,473,473,473
BEGIN DESCRIPTION:
CCLC 124 5.0
END DESCRIPTION:
XS GIS Cut Line= 3
      3710317.84     10156711.06      3709788.16     10156199.18
      3709167.89     10156111.08
#Sta/Elev= 30
  4263.4  289.41  4319.9  287.77    4511  278.55  4588.7  276.43  4595.9  275.65
    4716  271.31  4793.7  265.61  4843.3  263.48  4984.8  265.34  4991.8  265.27
 4992.98263.9382  4996.7  259.74  5002.7  259.74  5006.2  258.48  5014.7  258.48
 5018.17263.9218  5018.8  264.97  5101.3  264.85  5165.6  263.84  5202.3  264.82
    5273  264.65  5293.2  264.36  5313.4  262.42  5323.5  262.25  5343.7  263.79
  5363.9  263.54  5449.3  266.32  5520.2  269.74  5545.7  271.84  5626.5  275.45
#Mann= 3 ,-1 , 0
  4263.4     .12       0 4992.98     .09       0 5018.17     .12       0
Bank Sta=4992.98,5018.17
XS Rating Curve= 0 ,0
Exp/Cntr=0.3,0.1

Type RM Length L Ch R = 1 ,2483    ,495,495,495
BEGIN DESCRIPTION:
CCLC 124 4.0
END DESCRIPTION:
XS GIS Cut Line= 3
      3710317.85     10156211.07      3710039.32     10155889.27
      3709567.83     10155311.04
#Sta/Elev= 30
  4574.4  274.83    4667   270.9  4808.5  266.09  4929.2  263.28  4935.8  261.34
  4943.4   260.2  4957.7  260.35  4964.3  262.47  4971.2  262.94  4978.6  263.07
 4986.04261.8546  4993.1  258.11  5001.6  258.11  5007.2  259.31 5012.68261.8188
  5021.5  263.59  5113.8  261.66  5155.8  262.05  5163.7  261.57  5255.7  261.38
  5283.6  259.47  5305.9   259.6  5312.4  260.96  5361.9  259.77  5448.1  262.76
  5526.3  268.46  5539.6     270  5617.5  275.06  5689.3  277.02  5746.1  277.81
#Mann= 3 , 0 , 0
  4574.4     .11       0 4986.04     .06       0 5012.68     .11       0
Bank Sta=4986.04,5012.68
XS Rating Curve= 0 ,0
Exp/Cntr=0.3,0.1

Type RM Length L Ch R = 1 ,1988    ,496,496,496
BEGIN DESCRIPTION:
CCLC 124 3.0
END DESCRIPTION:
XS GIS Cut Line= 3
      3710667.84     10155911.06      3710425.78     10155635.74
      3709817.82     10155211.05
#Sta/Elev= 30
  4633.4  274.38  4704.1   271.1  4725.9  269.35  4732.5  269.66    4761  267.84
  4781.9  267.49  4881.5  261.99  4945.1  260.12  4973.5  260.89  4980.2  261.61
  4994.4  259.29    4995  256.31  4995.5  255.81    5004  255.81  5009.7  258.07
  5016.3  259.73  5022.4     262    5073  259.99  5203.9  259.25    5210  258.02
    5217  258.55  5224.8  257.96  5239.6  258.95  5266.6  258.91  5296.3  259.79
  5361.7   259.9  5375.6  259.22  5497.6  260.82  5570.2  263.17  5741.6  271.13
#Mann= 3 , 0 , 0
  4633.4     .11       0  4994.4     .06       0  5016.3     .11       0
Bank Sta=4994.4,5016.3
XS Rating Curve= 0 ,0
Exp/Cntr=0.3,0.1

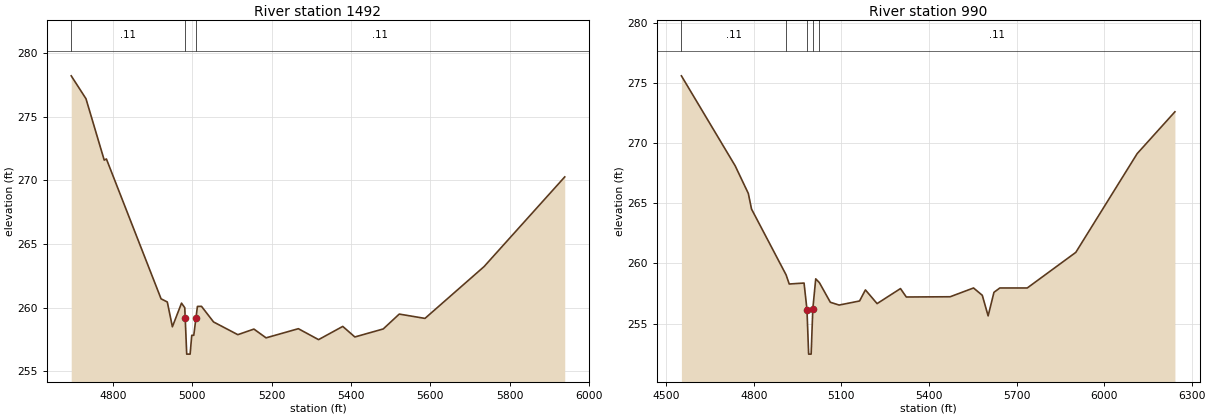
Type RM Length L Ch R = 1 ,1492    ,502,502,502
BEGIN DESCRIPTION:
CCLC 124 2.0
END DESCRIPTION:
XS GIS Cut Line= 3
      3711067.86     10155461.07      3710790.94     10155333.71
      3709867.85     10155161.07
#Sta/Elev= 30
  4695.2  278.23  4732.4  276.43  4778.4   271.6  4783.9  271.69  4921.7  260.69
  4937.4  260.44  4950.2  258.49  4973.2  260.35  4981.4  259.99  4982.5259.2024
  4986.3  256.34  4994.9  256.34    4999  257.82  5004.1  257.82 5009.72259.2068
  5013.3  260.09  5023.5   260.1    5054  258.87  5115.1  257.87  5155.7  258.31
  5186.3  257.62  5267.7  258.34  5318.6  257.48  5379.6  258.52  5410.1  257.69
  5481.6  258.32    5522  259.49  5586.8  259.15  5735.6  263.22  5939.1  270.28
#Mann= 3 , 0 , 0
  4695.2     .11       0  4982.5     .06       0 5009.72     .11       0
Bank Sta=4982.5,5009.72
XS Rating Curve= 0 ,0
Exp/Cntr=0.3,0.1

Type RM Length L Ch R = 1 ,990     ,0,0,0
BEGIN DESCRIPTION:
CCLC 124 1.0
END DESCRIPTION:
XS GIS Cut Line= 3
      3711179.15     10155295.89      3711106.24     10154931.34
      3709788.56     10154874.05
#Sta/Elev= 30
    4552   275.6  4736.2  268.12  4781.3  265.82  4792.3  264.52  4910.7  259.05
  4921.4  258.29  4972.2  258.37  4982.2  256.16  4987.9  252.46  4996.5  252.46
  5002.2  256.22  5012.2  258.72  5024.8   258.4  5062.3  256.77  5092.3  256.54
  5162.4  256.88  5182.4   257.8  5222.4  256.66  5302.5  257.91  5322.5  257.21
  5472.7  257.23  5552.8  257.96  5582.8  257.35  5602.8  255.64  5622.8   257.6
  5642.8  257.96  5736.8  257.96  5903.1  260.92  6113.3  269.13  6242.7  272.61
#Mann= 5 ,-1 , 0
    4552     .11       0  4910.7     .17       0  4982.2     .09       0
  5002.2     .17       0  5024.8     .11       0
Bank Sta=4982.2,5002.2
XS Rating Curve= 0 ,0
Exp/Cntr=0.3,0.1

Chan Stop Cuts=-1
Use User Specified Reach Order=0
Composite Channel Slope=5