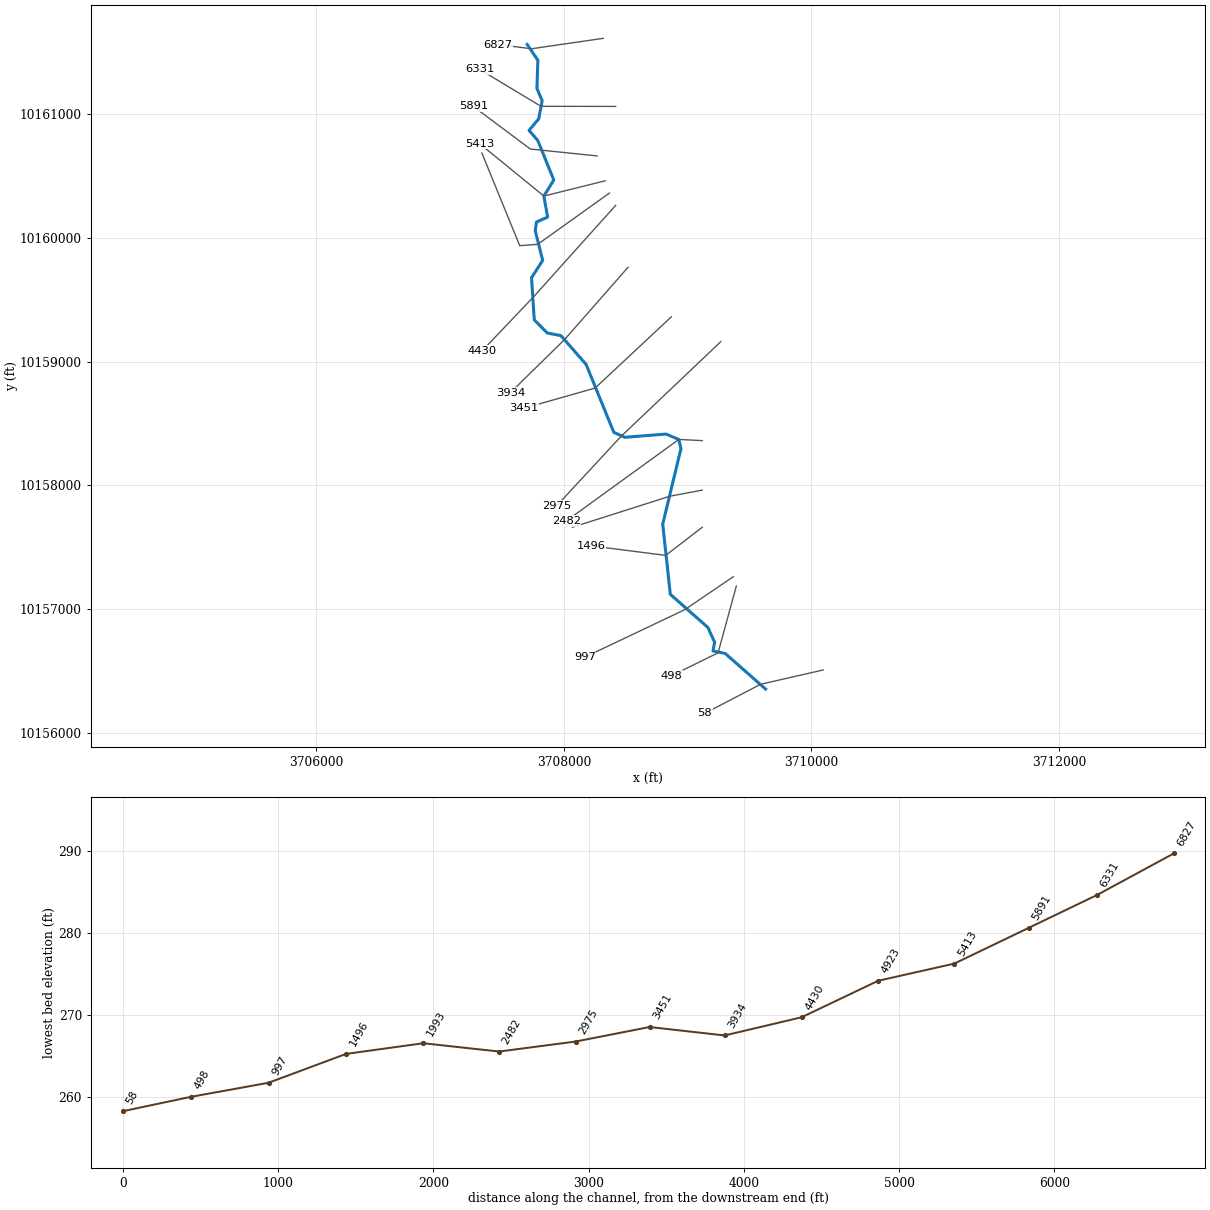
--- CCLC 125.prj (project) ---

Proj Title=CCLC 125 Base Level Engineering
Current Plan=p01
Default Exp/Contr=0.3,0.1
English Units
Geom File=g01
Flow File=f01
Flow File=f02
Plan File=p01
Y Axis Title=Elevation
X Axis Title(PF)=Main Channel Distance
X Axis Title(XS)=Station
BEGIN DESCRIPTION:
CCLC 125
END DESCRIPTION:
DSS Export Rating Curves= 0
DSS Export Rating Curve Sorted= 0
DSS Export Volume Flow Curves= 0
DXF OffsetX= 0
DXF OffsetY= 0
DXF ScaleX= 1
DXF ScaleY= 10

--- CCLC 125.p01 (plan) ---

Plan Title=Multiple Run
Short Identifier=Multiple
Geom File=g01
Flow File=f01
Subcritical Flow
K Sum by GR= 0
Std Step Tol= 0.01
Critical Tol= 0.01
Num of Std Step Trials= 20
Max Error Tol= 0.3
Flow Tol Ratio= 0.001
Split Flow NTrial= 30
Split Flow Tol= 0.02
Split Flow Ratio= 0.02
Log Output Level= 0
Friction Slope Method= 1
Unsteady Friction Slope Method= 2
Unsteady Bridges Friction Slope Method= 1
Parabolic Critical Depth
Global Vel Dist=  1 , 1 , 1
Global Log Level= 0
CheckData=True
Encroach Param= -1, 0, 0, 0
BEGIN DESCRIPTION:
Multiple Run
END DESCRIPTION:

--- CCLC 125.f01 (steady flow) ---

Flow Title=Multiple
Program Version=4.10
Number of Profiles= 7
Profile Names=10-year,25-year,50-year,1pct_min,100-year,1pct_plu,500-year
River Rch & RM=CCLC 125,Reach-1         ,6827
     571     774    1047     466    1407    4249    2628
River Rch & RM=CCLC 125,Reach-1         ,4430
    1268    1778    2458    1114    3364   10159    6531
River Rch & RM=CCLC 125,Reach-1         ,58
    1499    2117    2938    1337    4038   12195    7902
Boundary for River Rch & Prof#=CCLC 125,Reach-1         , 1
Up Type= 0
Dn Type= 3
Dn Slope=0.005
Boundary for River Rch & Prof#=CCLC 125,Reach-1         , 2
Up Type= 0
Dn Type= 3
Dn Slope=0.005
Boundary for River Rch & Prof#=CCLC 125,Reach-1         , 3
Up Type= 0
Dn Type= 3
Dn Slope=0.005
Boundary for River Rch & Prof#=CCLC 125,Reach-1         , 4
Up Type= 0
Dn Type= 3
Dn Slope=0.005
Boundary for River Rch & Prof#=CCLC 125,Reach-1         , 5
Up Type= 0
Dn Type= 3
Dn Slope=0.005
Boundary for River Rch & Prof#=CCLC 125,Reach-1         , 6
Up Type= 0
Dn Type= 3
Dn Slope=0.005
Boundary for River Rch & Prof#=CCLC 125,Reach-1         , 7
Up Type= 0
Dn Type= 3
Dn Slope=0.005
DSS Import GetInterval= 0
DSS Import GetPeak= 0
DSS Import FillOption= 0

--- CCLC 125.f02 (steady flow) ---

Flow Title=Orig_BLE_Flows
Program Version=4.10
Number of Profiles= 7
Profile Names=10-year,25-year,50-year,1pct_min,100-year,1pct_plu,500-year
River Rch & RM=CCLC 125,Reach-1         ,6827
     571     759     910     358    1082    3268    1528
River Rch & RM=CCLC 125,Reach-1         ,4430
    1268    1743    2137     857    2588    7816    3797
River Rch & RM=CCLC 125,Reach-1         ,58
    1499    2075    2555    1029    3106    9381    4594
Boundary for River Rch & Prof#=CCLC 125,Reach-1         , 1
Up Type= 0
Dn Type= 3
Dn Slope=0.005
Boundary for River Rch & Prof#=CCLC 125,Reach-1         , 2
Up Type= 0
Dn Type= 3
Dn Slope=0.005
Boundary for River Rch & Prof#=CCLC 125,Reach-1         , 3
Up Type= 0
Dn Type= 3
Dn Slope=0.005
Boundary for River Rch & Prof#=CCLC 125,Reach-1         , 4
Up Type= 0
Dn Type= 3
Dn Slope=0.005
Boundary for River Rch & Prof#=CCLC 125,Reach-1         , 5
Up Type= 0
Dn Type= 3
Dn Slope=0.005
Boundary for River Rch & Prof#=CCLC 125,Reach-1         , 6
Up Type= 0
Dn Type= 3
Dn Slope=0.005
Boundary for River Rch & Prof#=CCLC 125,Reach-1         , 7
Up Type= 0
Dn Type= 3
Dn Slope=0.005
DSS Import GetInterval= 0
DSS Import GetPeak= 0
DSS Import FillOption= 0

--- CCLC 125.g01 (geometry) ---

Geom Title=Existing Conditions
Program Version=4.10

River Reach=CCLC 125        ,Reach-1
Reach XY= 30
      3707703.23     10161561.84      3707789.32     10161434.19
      3707782.02     10161206.44      3707824.41     10161106.76
      3707796.13     10160960.31      3707718.23     10160866.84
      3707788.23     10160786.84      3707918.23     10160466.84
      3707838.23     10160336.84      3707868.23     10160166.84
      3707778.23     10160126.84      3707768.23     10160056.84
      3707828.23     10159816.84      3707738.23     10159676.84
      3707760.53     10159336.86      3707865.83     10159230.41
      3707975.51     10159209.44      3708179.45     10158976.42
      3708403.07     10158427.81      3708492.48     10158387.87
      3708824.95     10158413.92      3708928.25     10158370.51
      3708945.61     10158295.86      3708798.26     10157685.61
      3708859.65     10157119.34      3709163.62     10156850.83
      3709217.43     10156732.54      3709204.41      10156661.5
      3709302.97     10156641.66      3709629.14     10156354.08

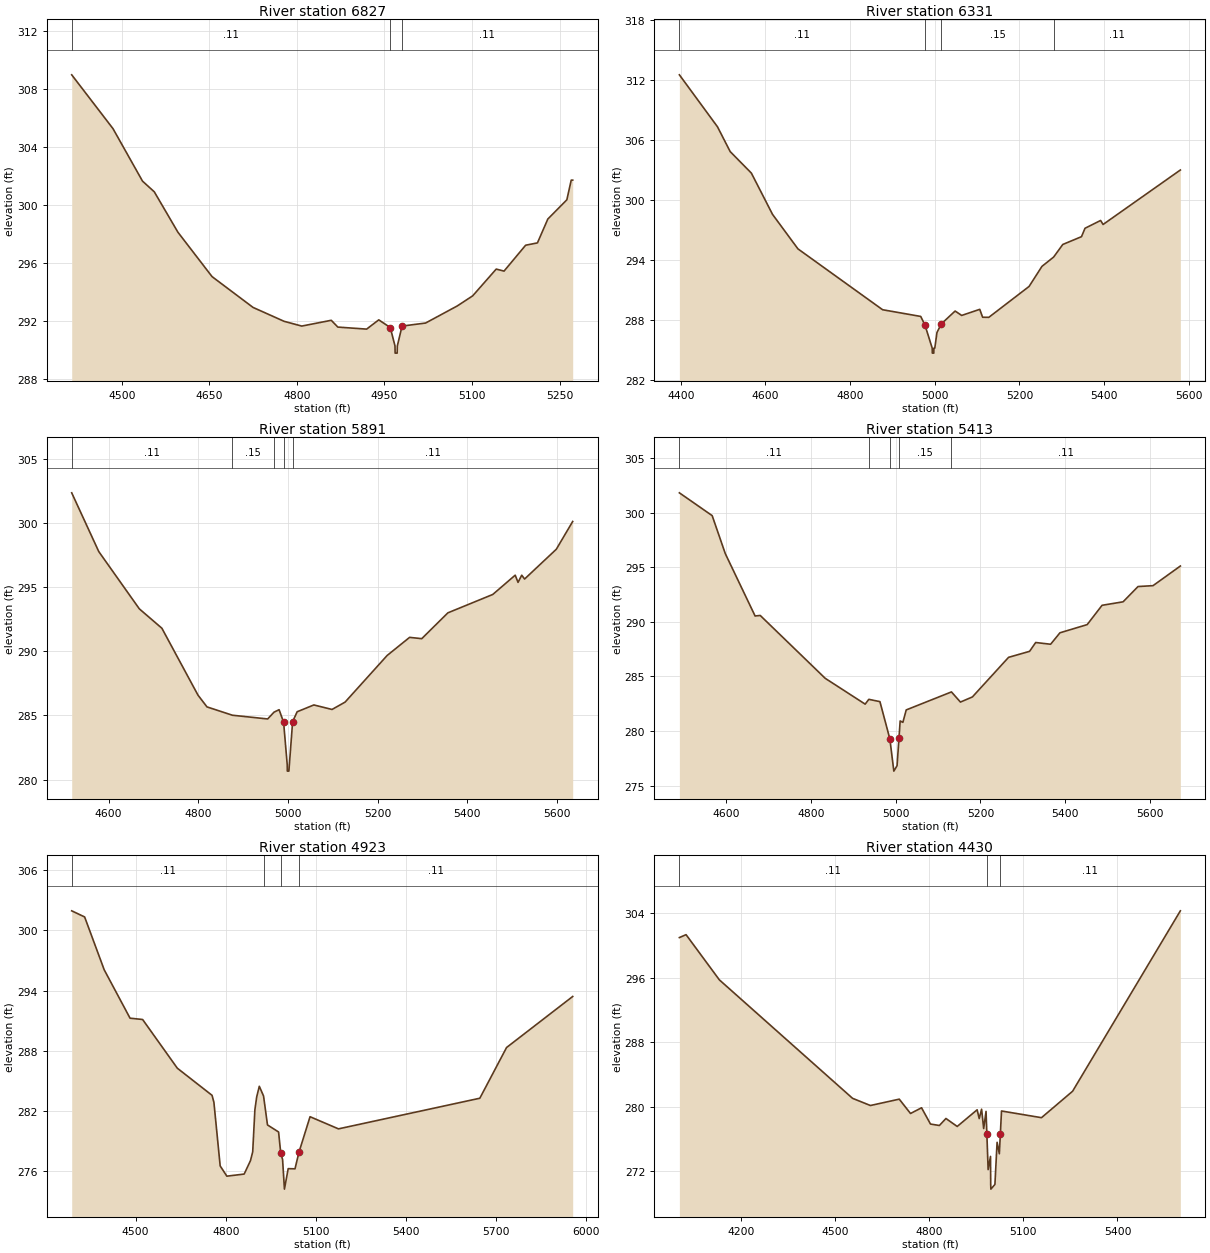
Type RM Length L Ch R = 1 ,6827    ,496,496,496
BEGIN DESCRIPTION:
CCLC 125 14.0
END DESCRIPTION:
XS GIS Cut Line= 3
      3708317.84     10161611.07      3707738.23     10161526.84
      3707467.89     10161561.07
#Sta/Elev= 30
  4414.3     309    4485  305.28  4535.6  301.65  4555.8  300.91  4596.2  298.12
  4654.7  295.05  4724.9  292.92  4778.1  291.96  4808.4  291.63  4858.9  292.03
  4870.2  291.56  4919.5  291.42  4940.3  292.06    4960  291.53  4968.1  290.26
  4968.3  289.76  4971.8  289.76  4972.1  290.26  4980.2  291.63  5020.5  291.84
  5074.7  293.02  5101.2  293.72  5141.5  295.57  5154.9  295.43  5191.9  297.22
  5212.1  297.38  5229.9  299.03  5262.5  300.36    5270  301.72  5272.5  301.72
#Mann= 3 , 0 , 0
  4414.3     .11       0    4960     .06       0  4980.2     .11       0
Bank Sta=4960,4980.2
XS Rating Curve= 0 ,0
Exp/Cntr=0.3,0.1

Type RM Length L Ch R = 1 ,6331    ,440,440,440
BEGIN DESCRIPTION:
CCLC 125 13.0
END DESCRIPTION:
XS GIS Cut Line= 3
      3708417.86     10161061.07      3707814.66     10161061.76
      3707317.85     10161361.07
#Sta/Elev= 30
  4396.8  312.52  4486.8  307.32  4516.8  304.84  4566.8  302.69  4616.8  298.56
  4676.8  295.11  4876.8  289.02  4966.8  288.35  4976.8  287.49  4993.9  285.18
  4994.2  284.68  4997.7  284.68  4997.9  285.18    5000  285.18  5005.2  286.75
 5015.44287.6057    5048  288.89  5063.5  288.45  5106.2  289.06    5113  288.27
  5127.6  288.26  5222.7  291.35  5253.1  293.36  5280.7  294.29  5302.3  295.55
  5346.5  296.33  5354.8  297.17  5391.6  297.95  5397.5  297.55    5580     303
#Mann= 4 ,-1 , 0
  4396.8     .11       0  4976.8     .06       0 5015.44     .15       0
  5280.7     .11       0
Bank Sta=4976.8,5015.44
XS Rating Curve= 0 ,0
Exp/Cntr=0.3,0.1

Type RM Length L Ch R = 1 ,5891    ,478,478,478
BEGIN DESCRIPTION:
CCLC 125 12.0
END DESCRIPTION:
XS GIS Cut Line= 3
      3708267.86     10160661.07      3707728.64     10160716.93
      3707267.87     10161061.06
#Sta/Elev= 30
  4517.8  302.33  4578.1  297.76  4668.6   293.3  4718.9  291.79  4799.3  286.59
  4819.4  285.67  4876.2  285.02  4954.8  284.73    4969  285.26  4980.3  285.45
  4990.3  284.48  4998.4  281.17  4998.6  280.67  5002.1  280.67  5010.4  284.51
  5020.5  285.29  5057.8  285.82  5098.3  285.47  5127.4  286.04  5221.2  289.67
  5271.3  291.08  5298.4  290.98  5356.7  292.99  5456.8  294.42  5506.8  295.92
  5513.1  295.36  5521.4  295.92  5527.7  295.62  5598.5  297.94    5635   300.1
#Mann= 5 ,-1 , 0
  4517.8     .11       0  4876.2     .15       0    4969     .11       0
  4990.3     .06       0  5010.4     .11       0
Bank Sta=4990.3,5010.4
XS Rating Curve= 0 ,0
Exp/Cntr=0.3,0.1

Type RM Length L Ch R = 1 ,5413    ,490,490,490
BEGIN DESCRIPTION:
CCLC 125 11.0
END DESCRIPTION:
XS GIS Cut Line= 3
      3708332.83     10160459.99      3707838.23     10160336.84
      3707317.84     10160761.08
#Sta/Elev= 30
  4490.3  301.83  4567.6  299.74  4598.5  296.26  4668.8  290.54  4680.9  290.59
    4834  284.83  4928.3  282.46  4936.9   282.9  4963.1  282.69 4986.49279.2759
  4995.9  276.32  5003.5  276.82 5008.09279.3979  5010.8  280.92  5017.2  280.79
  5025.1  281.93  5131.7  283.58  5152.9  282.65  5181.1  283.12  5266.4  286.75
  5315.9   287.3  5330.3  288.11  5365.5  287.95  5387.5     289  5451.7  289.75
  5486.8  291.52  5536.4  291.84  5571.6  293.24  5606.9  293.32  5671.4  295.12
#Mann= 5 ,-1 , 0
  4490.3     .11       0  4936.9     .15       0 4986.49     .09       0
 5008.09     .15       0  5131.7     .11       0
Bank Sta=4986.49,5008.09
XS Rating Curve= 0 ,0
Exp/Cntr=0.3,0.1

Type RM Length L Ch R = 1 ,4923    ,493,493,493
BEGIN DESCRIPTION:
CCLC 125 10.0
END DESCRIPTION:
XS GIS Cut Line= 4
      3708367.83     10160361.06      3707788.23     10159946.84
      3707642.85     10159936.07      3707337.16     10160684.79
#Sta/Elev= 30
  4287.6  301.94  4330.6  301.33  4395.7  296.07  4481.7  291.25  4523.5  291.12
    4639  286.27  4754.5  283.57  4760.7  282.88  4781.6  276.54  4803.8  275.52
  4861.4  275.73  4882.3  277.06  4889.8  277.94  4897.1  282.14  4903.2  283.43
  4911.8  284.47  4925.9   283.5    4939  280.62  4975.9  279.92  4983.1  277.82
  4989.2  277.18  4995.4  274.23  5007.9  276.27  5030.5  276.25  5043.8277.9091
  5080.6  281.44  5175.2  280.23  5645.5  283.28  5734.5  288.33  5954.5  293.41
#Mann= 4 ,-1 , 0
  4287.6     .11       0  4925.9     .17       0  4983.1     .09       0
  5043.8     .11       0
#Block Obstruct= 2 , 0
         4911.34  284.32
Bank Sta=4983.1,5043.8
XS Rating Curve= 0 ,0
Exp/Cntr=0.3,0.1

Type RM Length L Ch R = 1 ,4430    ,496,496,496
BEGIN DESCRIPTION:
CCLC 125 9.0
END DESCRIPTION:
XS GIS Cut Line= 3
      3708417.82     10160261.04      3707752.16     10159519.88
      3707338.09     10159085.11
#Sta/Elev= 30
  4003.8  301.01  4025.1  301.37  4131.2  295.76  4555.8  281.05  4612.6  280.16
  4704.5  280.95  4740.4  279.17  4775.6  279.88    4804  277.86  4832.4  277.68
  4853.3  278.55  4889.2  277.56  4952.7  279.63  4959.4  278.54  4966.9   279.7
  4973.6   277.3  4981.1  279.43 4983.75276.5703  4987.8   272.2  4995.3  273.84
    4996  270.28  4996.5  269.78  5009.4  270.36  5016.3  275.59  5023.5  274.17
  5026.7276.6328  5030.4  279.48  5157.8  278.65  5256.9  281.93  5600.4  304.33
#Mann= 3 , 0 , 0
  4003.8     .11       0 4983.75     .06       0  5026.7     .11       0
Bank Sta=4983.75,5026.7
XS Rating Curve= 0 ,0
Exp/Cntr=0.3,0.1

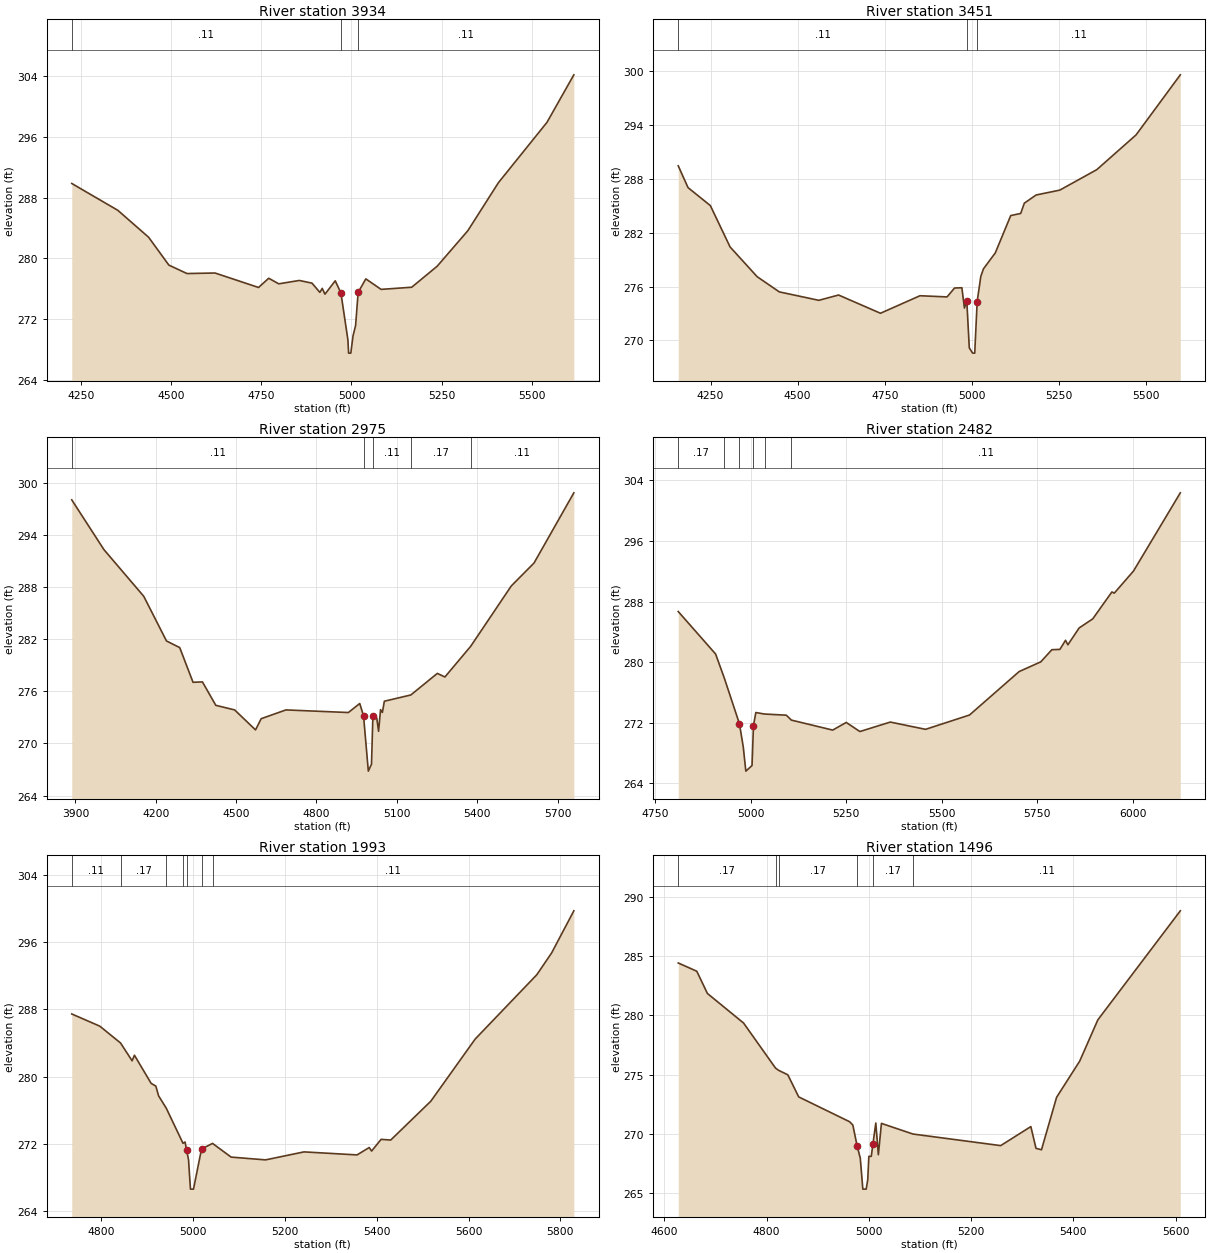
Type RM Length L Ch R = 1 ,3934    ,483,483,483
BEGIN DESCRIPTION:
CCLC 125 8.0
END DESCRIPTION:
XS GIS Cut Line= 3
      3708517.88      10159761.1      3708006.34     10159178.77
      3707566.28     10158747.28
#Sta/Elev= 30
  4224.9  289.86  4352.6  286.33  4437.9  282.79    4494  279.13  4544.2  278.02
    4622  278.09  4742.5  276.19  4770.7   277.4  4798.5  276.67  4855.5  277.11
  4890.6  276.76  4912.4  275.55    4919  276.07  4926.6  275.31  4955.1  277.07
 4970.86275.4553  4990.2   269.3  4992.1  267.56  4998.2  267.56  5004.4  269.84
  5011.5   271.2  5018.5  275.54  5039.8  277.32  5082.1  275.94    5167  276.22
  5237.7  278.99  5322.5  283.65  5407.4  289.97  5541.8  297.89  5616.3  304.14
#Mann= 3 , 0 , 0
  4224.9     .11       0 4970.86     .06       0  5018.5     .11       0
Bank Sta=4970.86,5018.5
XS Rating Curve= 0 ,0
Exp/Cntr=0.3,0.1

Type RM Length L Ch R = 1 ,3451    ,476,476,476
BEGIN DESCRIPTION:
CCLC 125 7.0
END DESCRIPTION:
XS GIS Cut Line= 3
      3708867.85     10159361.07      3708252.21     10158785.79
       3707677.4     10158622.31
#Sta/Elev= 30
  4157.4  289.45  4185.5  287.02  4249.5  285.02  4306.2  280.41  4383.8   277.1
  4447.3  275.41  4560.7  274.47  4617.3  275.06  4737.5  273.03  4850.8  274.98
  4928.5  274.85    4950  275.84    4971  275.87  4978.3  273.61  4985.2  274.37
  4992.3  269.18  5001.8  268.59  5007.9  268.59  5014.9  274.32  5025.3  277.13
    5033  277.98  5066.9  279.75  5111.2  283.91  5139.7  284.14  5150.2  285.29
  5184.1   286.2  5251.8  286.74    5358  289.02  5470.7  292.89  5597.6  299.58
#Mann= 3 , 0 , 0
  4157.4     .11       0  4985.2     .06       0  5014.9     .11       0
Bank Sta=4985.2,5014.9
XS Rating Curve= 0 ,0
Exp/Cntr=0.3,0.1

Type RM Length L Ch R = 1 ,2975    ,493,493,493
BEGIN DESCRIPTION:
CCLC 125 6.0
END DESCRIPTION:
XS GIS Cut Line= 3
      3709267.87     10159161.08      3708460.37     10158393.95
      3707942.82     10157836.04
#Sta/Elev= 30
  3886.2  298.02  4006.5  292.29    4155  286.93  4239.9  281.79  4289.3  281.03
    4339  277.04  4374.2  277.08    4424  274.39  4494.4  273.86  4572.4  271.56
  4593.5  272.85  4685.7  273.86  4919.1  273.56  4961.5   274.6  4975.7  273.19
  4993.6  266.82  5005.4  267.62  5010.6273.1417  5025.1  272.93  5031.9   271.4
  5039.2  273.89  5046.1  273.57  5053.4  274.86  5152.3  275.58  5251.3  278.06
  5279.6  277.65  5375.9  281.18  5527.4  288.12  5612.4  290.76    5761  298.83
#Mann= 5 ,-1 , 0
  3886.2     .11       0  4975.7     .06       0  5010.6     .11       0
  5152.3     .17       0  5375.9     .11       0
Bank Sta=4975.7,5010.6
XS Rating Curve= 0 ,0
Exp/Cntr=0.3,0.1

Type RM Length L Ch R = 1 ,2482    ,489,489,489
BEGIN DESCRIPTION:
CCLC 125 5.0
END DESCRIPTION:
XS GIS Cut Line= 3
      3709117.81     10158361.07      3708928.25     10158370.51
      3708017.88     10157711.09
#Sta/Elev= 30
  4810.2  286.68    4908  281.07  4931.2  277.83  4970.4  271.85  4980.4  268.79
  4987.1   265.6  5003.3  266.34  5007.1  271.62  5013.3  273.34  5036.1  273.14
    5093  272.99  5106.3  272.34  5214.4  271.02  5249.9  272.03  5285.5  270.83
  5365.2  272.08  5457.4  271.12  5572.4  273.01  5702.3  278.75  5758.8  280.03
  5788.1  281.64    5809  281.68  5823.7  282.88  5829.9  282.29  5859.3  284.51
  5894.9  285.71  5945.1  289.27  5951.3  289.11  6001.6  292.03  6124.1  302.36
#Mann= 6 ,-1 , 0
  4810.2     .17       0  4931.2     .15       0  4970.4     .09       0
  5007.1     .15       0  5036.1     .17       0  5106.3     .11       0
Bank Sta=4970.4,5007.1
XS Rating Curve= 0 ,0
Exp/Cntr=0.3,0.1

Type RM Length L Ch R = 1 ,1993    ,497,497,497
BEGIN DESCRIPTION:
CCLC 125 4.0
END DESCRIPTION:
XS GIS Cut Line= 3
      3709117.81     10157961.06      3708858.13     10157912.39
      3708067.83     10157661.07
#Sta/Elev= 30
  4735.8  287.45  4796.8     286    4842     284  4867.2  281.88  4872.3  282.54
  4908.7  279.19  4918.9  278.87  4924.9  277.71  4941.7  276.23  4978.1  272.06
  4982.5  272.22 4985.77271.3122  4990.1  270.11  4994.3  266.61  5000.9  266.61
  5018.4  271.38  5042.4  272.05  5082.9  270.42  5157.9  270.09  5241.6  271.04
  5357.1  270.68  5383.6  271.56  5388.8  271.14  5409.5  272.53  5430.5  272.45
  5517.8  277.07  5614.5  284.47  5748.7  292.12  5780.9  294.71  5829.3  299.72
#Mann= 7 ,-1 , 0
  4735.8     .11       0    4842     .17       0  4941.7     .11       0
  4978.1     .17       0 4985.77     .09       0  5018.4     .17       0
  5042.4     .11       0
Bank Sta=4985.77,5018.4
XS Rating Curve= 0 ,0
Exp/Cntr=0.3,0.1

Type RM Length L Ch R = 1 ,1496    ,499,499,499
BEGIN DESCRIPTION:
CCLC 125 3.0
END DESCRIPTION:
XS GIS Cut Line= 3
      3709117.87     10157661.09      3708822.22     10157433.83
      3708217.84     10157511.07
#Sta/Elev= 30
  4627.1  284.44  4663.4  283.74  4684.2  281.86  4754.9  279.36  4817.4  275.55
  4823.4  275.36  4841.5  274.98  4862.8  273.11  4962.4  271.01  4968.7  270.73
  4976.9     269  4983.3  267.92  4988.2  265.31  4994.8  265.31  4997.8  266.09
    5000  268.08  5004.7  268.08    5008269.1255  5013.6   270.9  5018.6  268.22
  5024.6  270.87  5086.3  269.97  5257.9  268.99  5316.9   270.6    5327  268.76
  5337.7  268.64  5367.3  273.08  5412.4  276.13    5448  279.63  5609.3  288.85
#Mann= 6 ,-1 , 0
  4627.1     .17       0  4817.4     .15       0  4823.4     .17       0
  4976.9     .09       0    5008     .17       0  5086.3     .11       0
Bank Sta=4976.9,5008
XS Rating Curve= 0 ,0
Exp/Cntr=0.3,0.1

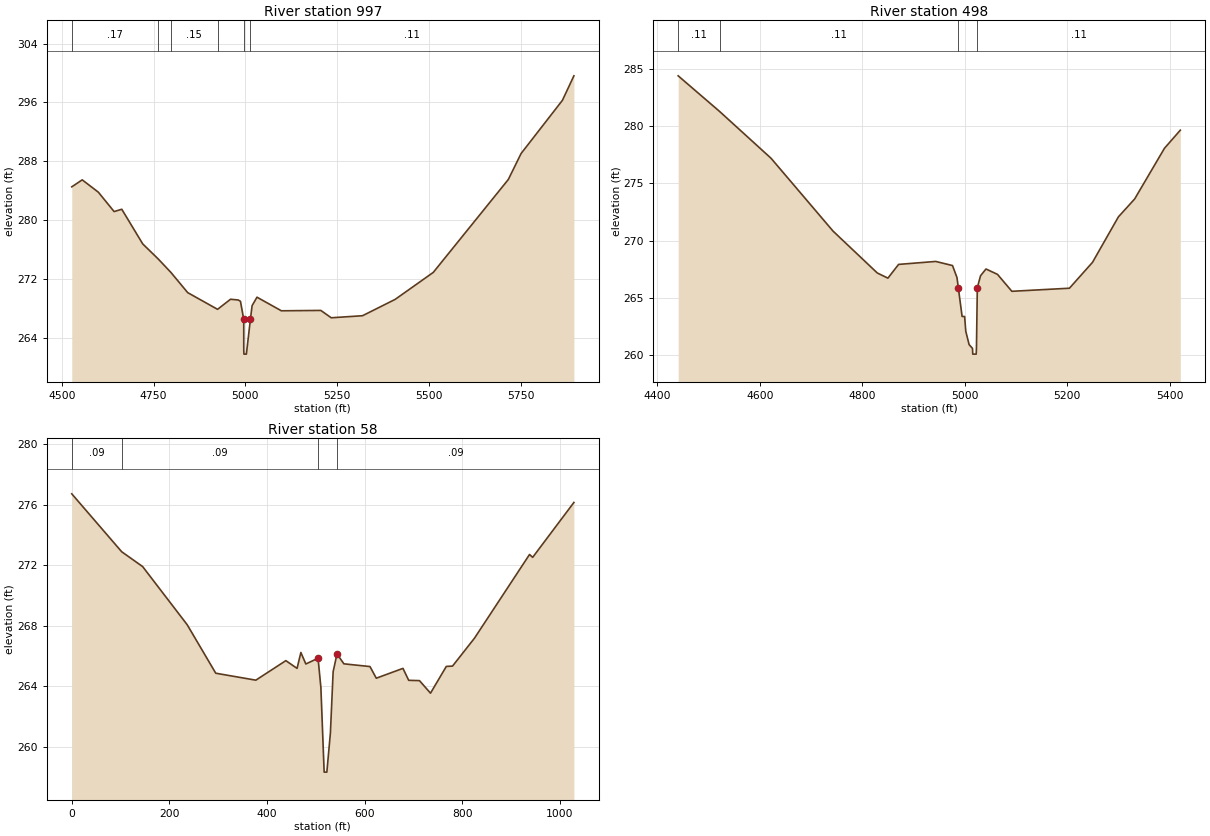
Type RM Length L Ch R = 1 ,997     ,499,499,499
BEGIN DESCRIPTION:
CCLC 125 2.0
END DESCRIPTION:
XS GIS Cut Line= 3
      3709367.85     10157261.07      3708976.41     10156995.35
      3708167.88     10156611.09
#Sta/Elev= 30
  4526.9  284.53  4555.4  285.48  4599.4   283.8  4642.2  281.17  4663.2  281.48
  4720.3  276.77    4762  274.75    4797   272.9  4842.8  270.15  4924.2  267.88
  4959.5  269.25  4980.5  269.15  4986.6  268.97  4995.5  266.53  4995.6  262.29
  4996.1  261.79  5002.7  261.79 5013.91266.6241  5018.3  268.38  5031.6  269.53
  5098.1  267.68  5205.6  267.73  5233.9  266.73  5319.2  267.01  5408.1  269.23
    5512   272.9  5716.5  285.53  5751.3  289.06  5863.9  296.29  5895.2  299.62
#Mann= 6 ,-1 , 0
  4526.9     .17       0    4762     .11       0    4797     .15       0
  4924.2     .11       0  4995.5     .06       0 5013.91     .11       0
Bank Sta=4995.5,5013.91
XS Rating Curve= 0 ,0
Exp/Cntr=0.3,0.1

Type RM Length L Ch R = 1 ,498     ,440,440,440
BEGIN DESCRIPTION:
CCLC 125 1.0
END DESCRIPTION:
XS GIS Cut Line= 3
      3709392.85     10157186.08      3709245.73     10156646.68
      3708867.86     10156461.07
#Sta/Elev= 30
  4440.9   284.4  4521.7  281.29  4622.3  277.19  4743.2  270.83  4829.6  267.17
  4850.3  266.72  4871.1  267.92  4943.6  268.18  4976.4  267.82  4985.1  266.77
 4987.82265.8453  4995.1  263.37    5000  263.37  5002.3  262.07  5008.8  260.91
  5015.4  260.58  5015.9  260.08  5022.6  260.08  5023.1  260.58  5024.8  265.89
  5031.1  266.93  5041.7  267.52  5064.2  267.05  5092.2  265.57  5204.6  265.84
  5249.6   268.1  5300.1  272.07  5331.9  273.64  5390.1  278.07    5421  279.65
#Mann= 4 ,-1 , 0
  4440.9     .11       0  4521.7     .11       0 4987.82     .06       0
  5024.8     .11       0
Bank Sta=4987.82,5024.8
XS Rating Curve= 0 ,0
Exp/Cntr=0.3,0.1

Type RM Length L Ch R = 1 ,58      ,0,0,0
BEGIN DESCRIPTION:
CCLC 125 1.0
END DESCRIPTION:
XS GIS Cut Line= 3
      3710095.46     10156508.15      3709589.73     10156392.78
      3709137.13     10156157.45
#Sta/Elev= 30
       0  276.72   102.3  272.89   145.2  271.91   236.4  268.07     295  264.86
   377.1   264.4   438.6  265.69   461.6  265.18   469.4  266.23   479.6  265.47
   504.6  265.85   510.4  263.92   517.1  258.32   522.6  258.32   529.9  260.91
   535.5  264.96   543.4  266.13   557.6  265.48     611   265.3   623.9  264.53
   678.6  265.18   690.3  264.39   712.4  264.37     735  263.54   767.4  265.31
   780.1  265.33   825.2  267.18   937.9  272.71   944.3  272.52  1028.8  276.15
#Mann= 4 ,-1 , 0
       0     .09       0   102.3     .09       0   504.6     .06       0
   543.4     .09       0
Bank Sta=504.6,543.4
XS Rating Curve= 0 ,0
Exp/Cntr=0.3,0.1

Chan Stop Cuts=-1
Use User Specified Reach Order=0
Composite Channel Slope=5