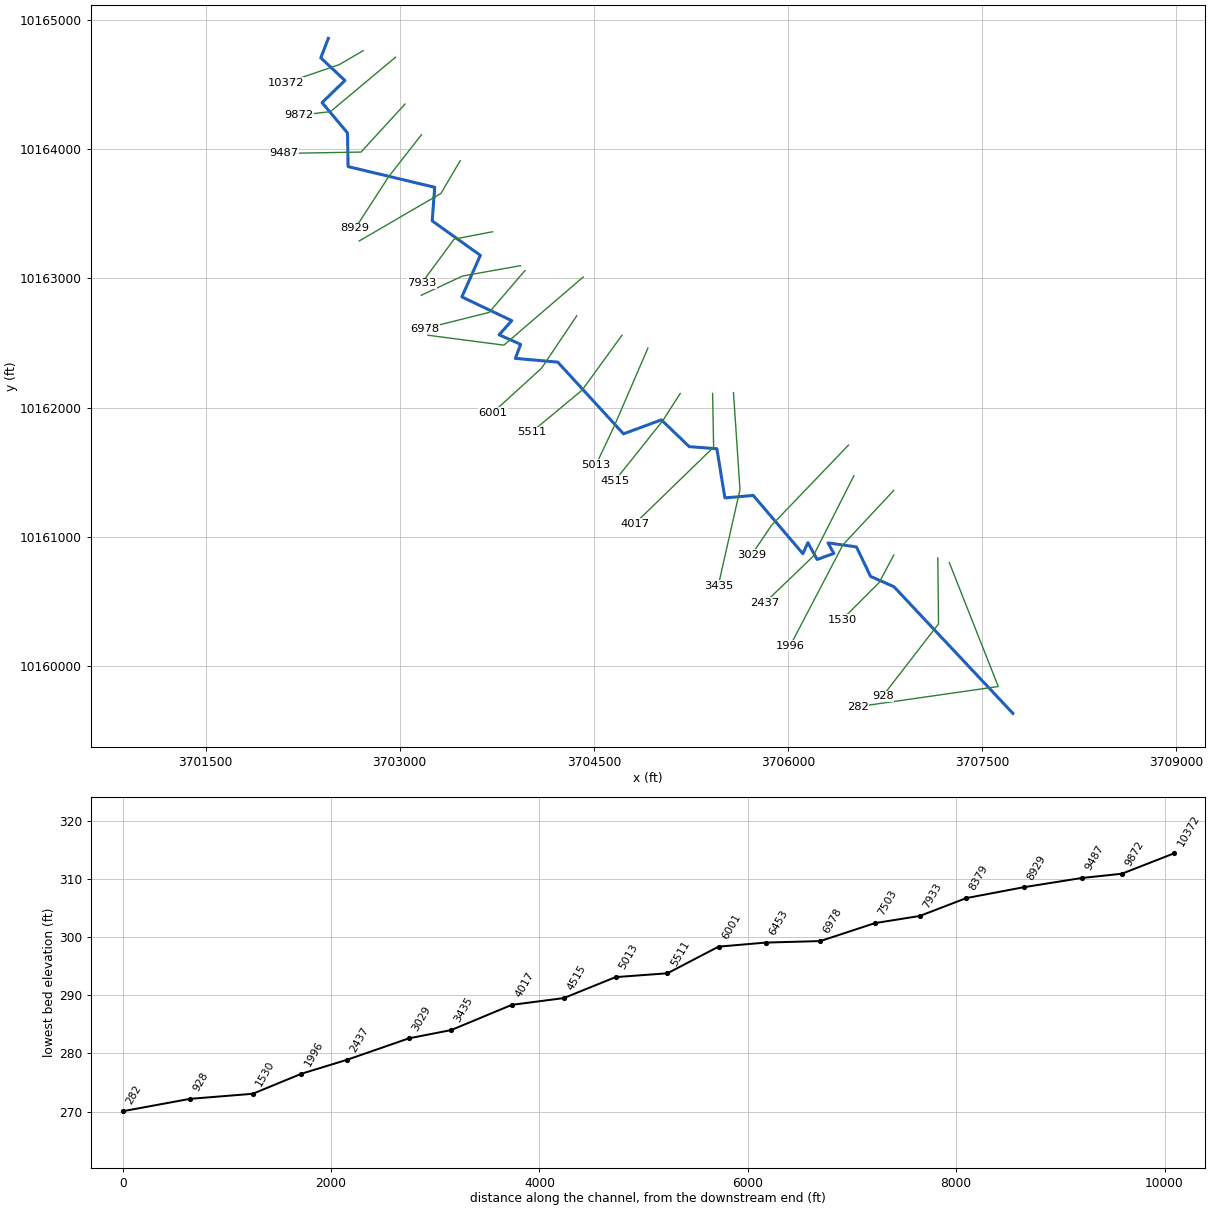
--- CCLC 126.prj (project) ---

Proj Title=CCLC 126 Base Level Engineering
Current Plan=p01
Default Exp/Contr=0.3,0.1
English Units
Geom File=g01
Flow File=f01
Flow File=f02
Plan File=p01
Y Axis Title=Elevation
X Axis Title(PF)=Main Channel Distance
X Axis Title(XS)=Station
BEGIN DESCRIPTION:
CCLC 126
END DESCRIPTION:
DSS Export Rating Curves= 0
DSS Export Rating Curve Sorted= 0
DSS Export Volume Flow Curves= 0
DXF OffsetX= 0
DXF OffsetY= 0
DXF ScaleX= 1
DXF ScaleY= 10

--- CCLC 126.p01 (plan) ---

Plan Title=Multiple Run
Short Identifier=Multiple
Geom File=g01
Flow File=f01
Subcritical Flow
K Sum by GR= 0
Std Step Tol= 0.01
Critical Tol= 0.01
Num of Std Step Trials= 20
Max Error Tol= 0.3
Flow Tol Ratio= 0.001
Split Flow NTrial= 30
Split Flow Tol= 0.02
Split Flow Ratio= 0.02
Log Output Level= 0
Friction Slope Method= 1
Unsteady Friction Slope Method= 2
Unsteady Bridges Friction Slope Method= 1
Parabolic Critical Depth
Global Vel Dist=  1 , 1 , 1
Global Log Level= 0
CheckData=True
Encroach Param= -1, 0, 0, 0
BEGIN DESCRIPTION:
Multiple Run
END DESCRIPTION:

--- CCLC 126.f01 (steady flow) ---

Flow Title=Multiple
Program Version=4.10
Number of Profiles= 7
Profile Names=10-year,25-year,50-year,1pct_min,100-year,1pct_plu,500-year
River Rch & RM=CCLC 126,Reach-1         ,10372
     695     950    1289     576    1739    5252    3275
River Rch & RM=CCLC 126,Reach-1         ,5511
     956    1323    1815     817    2467    7450    4721
Boundary for River Rch & Prof#=CCLC 126,Reach-1         , 1
Up Type= 0
Dn Type= 3
Dn Slope=0.005
Boundary for River Rch & Prof#=CCLC 126,Reach-1         , 2
Up Type= 0
Dn Type= 3
Dn Slope=0.005
Boundary for River Rch & Prof#=CCLC 126,Reach-1         , 3
Up Type= 0
Dn Type= 3
Dn Slope=0.005
Boundary for River Rch & Prof#=CCLC 126,Reach-1         , 4
Up Type= 0
Dn Type= 3
Dn Slope=0.005
Boundary for River Rch & Prof#=CCLC 126,Reach-1         , 5
Up Type= 0
Dn Type= 3
Dn Slope=0.005
Boundary for River Rch & Prof#=CCLC 126,Reach-1         , 6
Up Type= 0
Dn Type= 3
Dn Slope=0.005
Boundary for River Rch & Prof#=CCLC 126,Reach-1         , 7
Up Type= 0
Dn Type= 3
Dn Slope=0.005
DSS Import GetInterval= 0
DSS Import GetPeak= 0
DSS Import FillOption= 0

--- CCLC 126.f02 (steady flow) ---

Flow Title=Orig_BLE_Flows
Program Version=4.10
Number of Profiles= 7
Profile Names=10-year,25-year,50-year,1pct_min,100-year,1pct_plu,500-year
River Rch & RM=CCLC 126,Reach-1         ,10372
     695     931    1121     443    1338    4041    1904
River Rch & RM=CCLC 126,Reach-1         ,5511
     956    1297    1578     628    1898    5731    2745
Boundary for River Rch & Prof#=CCLC 126,Reach-1         , 1
Up Type= 0
Dn Type= 3
Dn Slope=0.005
Boundary for River Rch & Prof#=CCLC 126,Reach-1         , 2
Up Type= 0
Dn Type= 3
Dn Slope=0.005
Boundary for River Rch & Prof#=CCLC 126,Reach-1         , 3
Up Type= 0
Dn Type= 3
Dn Slope=0.005
Boundary for River Rch & Prof#=CCLC 126,Reach-1         , 4
Up Type= 0
Dn Type= 3
Dn Slope=0.005
Boundary for River Rch & Prof#=CCLC 126,Reach-1         , 5
Up Type= 0
Dn Type= 3
Dn Slope=0.005
Boundary for River Rch & Prof#=CCLC 126,Reach-1         , 6
Up Type= 0
Dn Type= 3
Dn Slope=0.005
Boundary for River Rch & Prof#=CCLC 126,Reach-1         , 7
Up Type= 0
Dn Type= 3
Dn Slope=0.005
DSS Import GetInterval= 0
DSS Import GetPeak= 0
DSS Import FillOption= 0

--- CCLC 126.g01 (geometry) ---

Geom Title=Existing Conditions
Program Version=4.10

River Reach=CCLC 126        ,Reach-1
Reach XY= 30
      3702448.23     10164856.84      3702390.52     10164705.94
      3702576.92     10164530.82      3702399.81     10164360.05
      3702596.62     10164125.28      3702601.18     10163865.12
      3703270.63     10163704.84      3703251.09     10163445.33
      3703623.51     10163178.67      3703480.08     10162857.43
        3703866.     10162673.65       3703768.2     10162564.98
      3703934.48     10162490.11      3703893.89     10162382.16
       3704221.4     10162352.87       3704729.3     10161798.46
      3705022.07     10161906.55      3705237.31     10161699.28
      3705450.69      10161683.4      3705513.03     10161302.99
      3705732.33     10161322.13      3706115.39     10160871.61
      3706154.21     10160956.65      3706225.85     10160827.11
      3706354.62      10160873.8      3706309.55     10160955.25
      3706529.65     10160923.93      3706638.53      10160696.2
      3706819.26     10160616.21      3707738.23     10159636.84

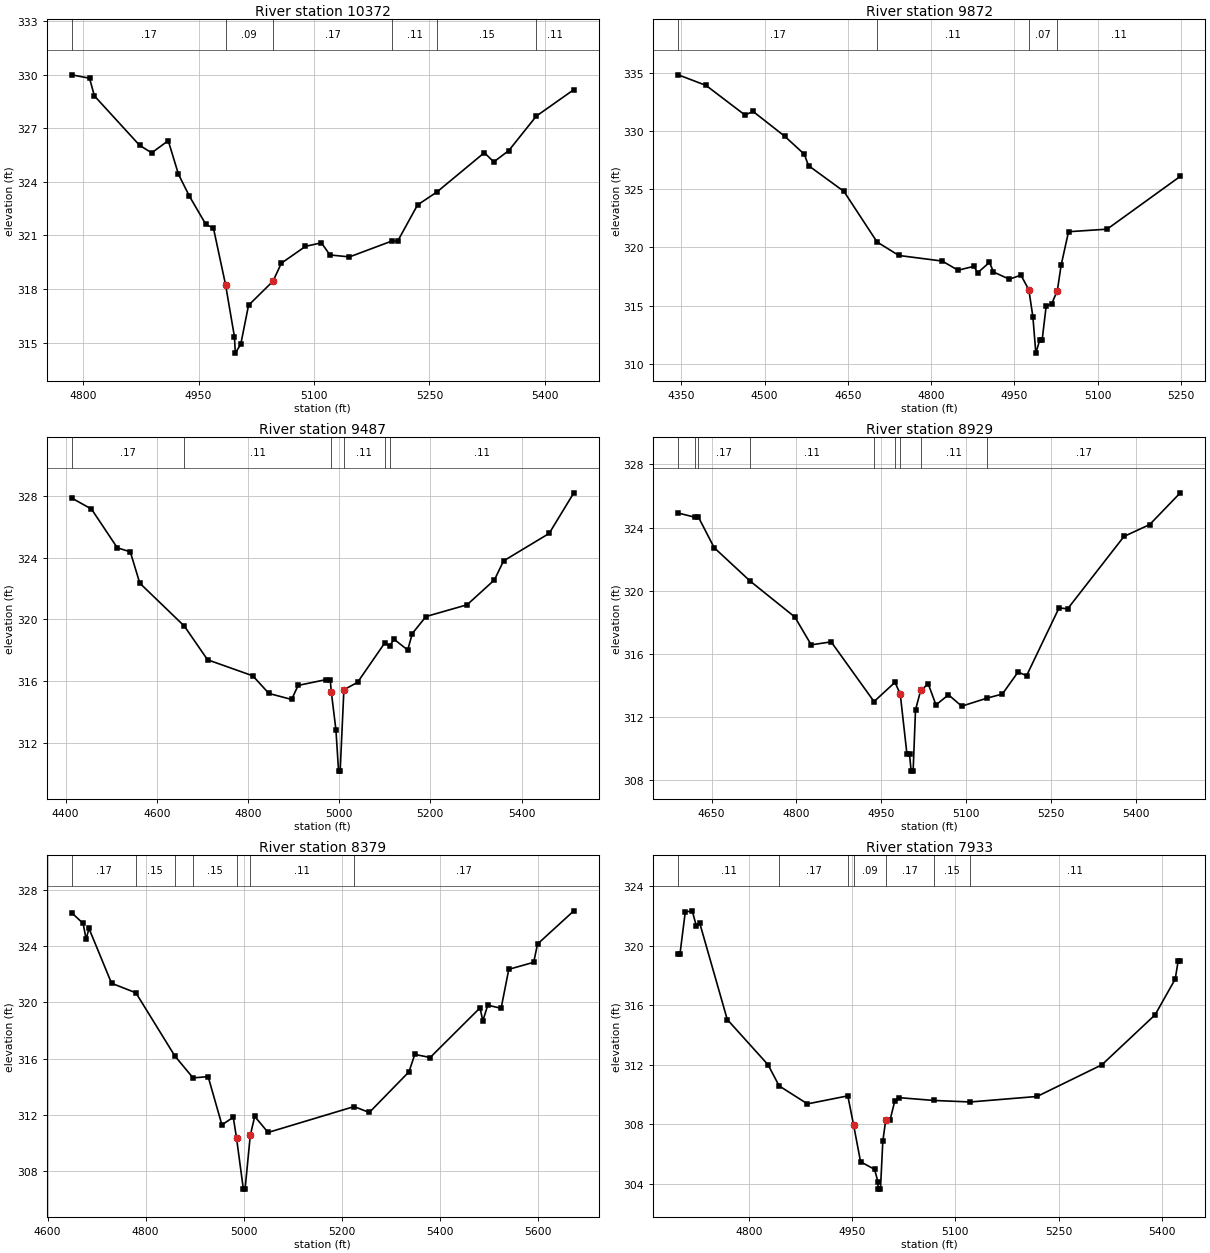
Type RM Length L Ch R = 1 ,10372   ,500,500,500
BEGIN DESCRIPTION:
CCLC 126 20.0
END DESCRIPTION:
XS GIS Cut Line= 3
      3702717.84     10164761.06      3702531.98     10164653.18
      3702117.88     10164511.08
#Sta/Elev= 30
  4785.1     330  4808.2  329.81  4814.5  328.82  4873.3  326.05    4889  325.63
  4910.5  326.31  4923.8  324.43  4937.8  323.22  4959.4  321.62  4969.3  321.41
 4985.06318.2347  4996.6  315.32  4997.7  314.41  5004.8  314.91  5014.9  317.09
  5046.7  318.44  5057.6  319.45  5088.9  320.39  5109.6  320.59  5120.7  319.91
  5146.1   319.8  5201.9   320.7  5208.6  320.67  5234.6  322.71  5259.9  323.44
  5321.5  325.64  5333.7  325.12  5353.3  325.76  5389.1  327.69  5437.8  329.17
#Mann= 6 ,-1 , 0
  4785.1     .17       0 4985.06     .09       0  5046.7     .17       0
  5201.9     .11       0  5259.9     .15       0  5389.1     .11       0
Bank Sta=4985.06,5046.7
XS Rating Curve= 0 ,0
Exp/Cntr=0.3,0.1

Type RM Length L Ch R = 1 ,9872    ,385,385,385
BEGIN DESCRIPTION:
CCLC 126 19.0
END DESCRIPTION:
XS GIS Cut Line= 3
      3702967.86     10164711.08      3702465.13     10164290.28
      3702217.85     10164261.07
#Sta/Elev= 30
  4344.4  334.82  4394.5  333.91  4464.8  331.36  4479.1  331.68  4536.3  329.54
  4571.5     328  4579.1  327.02    4643   324.8  4702.6  320.46  4741.9   319.3
    4820  318.82  4848.6  318.03  4877.2  318.37  4883.8  317.81  4905.2  318.71
  4912.4  317.88    4941  317.26  4961.8  317.61  4976.1  316.35  4983.4  314.02
  4988.7  310.91  4995.5  312.01    5000  312.01  5007.3  314.95  5017.4  315.16
  5027.5  316.29  5034.2  318.45  5047.6  321.34  5117.1  321.56    5249   326.1
#Mann= 4 ,-1 , 0
  4344.4     .17       0  4702.6     .11       0  4976.1     .07       0
  5027.5     .11       0
Bank Sta=4976.1,5027.5
XS Rating Curve= 0 ,0
Exp/Cntr=0.3,0.1

Type RM Length L Ch R = 1 ,9487    ,558,558,558
BEGIN DESCRIPTION:
CCLC 126 18.0
END DESCRIPTION:
XS GIS Cut Line= 3
      3703041.13     10164348.87      3702700.86     10163977.35
      3702103.65     10163966.93
#Sta/Elev= 30
  4413.6  327.86  4456.8  327.15  4513.5  324.64  4541.9  324.38  4562.8  322.35
  4660.5  319.57  4711.4  317.39  4810.7  316.35  4845.9  315.21  4895.8  314.82
    4910  315.73  4970.4   316.1  4980.4   316.1  4982.7315.3343    4993  312.83
  4998.7  310.18  5002.2  310.18  5010.4  315.45  5040.4  315.93    5100  318.48
  5110.8  318.29  5120.4  318.72  5150.4  318.02  5160.4  319.09  5190.4  320.19
  5280.5  320.95  5340.5  322.56  5360.5  323.79  5460.5  325.57  5514.7   328.2
#Mann= 6 ,-1 , 0
  4413.6     .17       0  4660.5     .11       0  4982.7     .07       0
  5010.4     .11       0    5100     .17       0  5110.8     .11       0
Bank Sta=4982.7,5010.4
XS Rating Curve= 0 ,0
Exp/Cntr=0.3,0.1

Type RM Length L Ch R = 1 ,8929    ,550,550,550
BEGIN DESCRIPTION:
CCLC 126 17.0
END DESCRIPTION:
XS GIS Cut Line= 3
      3703167.85     10164111.06      3702916.03      10163788.9
      3702655.71     10163387.05
#Sta/Elev= 30
  4591.1  324.92  4620.2  324.66  4626.4  324.69  4654.6  322.73  4718.4  320.61
  4797.3  318.34  4826.2  316.58  4861.5  316.77  4937.3  312.99  4974.3  314.21
  4983.6  313.47  4995.5  309.66    5000  309.66  5002.9  308.59  5006.4  308.59
  5010.6  312.46  5019.8  313.71  5033.2   314.1  5046.8  312.78  5068.9  313.42
  5092.3   312.7  5136.3   313.2  5164.2  313.47  5191.9  314.86    5207  314.63
  5264.4  318.92  5279.6  318.86  5379.2  323.44  5424.6  324.19  5478.8   326.2
#Mann= 9 ,-1 , 0
  4591.1     .17       0  4620.2     .11       0  4626.4     .17       0
  4718.4     .11       0  4937.3     .17       0  4974.3     .11       0
  4983.6     .07       0  5019.8     .11       0  5136.3     .17       0
Bank Sta=4983.6,5019.8
XS Rating Curve= 0 ,0
Exp/Cntr=0.3,0.1

Type RM Length L Ch R = 1 ,8379    ,446,446,446
BEGIN DESCRIPTION:
CCLC 126 16.0
END DESCRIPTION:
XS GIS Cut Line= 3
      3703467.85     10163911.07      3703318.92      10163657.9
      3702687.01     10163289.87
#Sta/Elev= 30
  4649.2  326.37  4672.4  325.61  4678.5  324.49  4684.3  325.26  4730.4  321.36
  4780.1  320.68  4859.6  316.19  4896.8  314.63  4927.6  314.72  4955.7  311.29
  4978.9  311.83  4985.5  310.37  4999.5  306.72    5003  306.72  5013.6  310.54
  5022.7  311.89    5050  310.75  5225.6  312.59  5256.6  312.17  5337.6  315.06
  5349.5   316.3  5380.9  316.08  5482.7  319.61  5488.4  318.68  5498.4   319.8
  5525.7  319.58  5541.4  322.35  5592.2  322.85  5600.1  324.15  5674.2  326.51
#Mann= 7 ,-1 , 0
  4649.2     .17       0  4780.1     .15       0  4859.6     .11       0
  4896.8     .15       0  4985.5     .09       0  5013.6     .11       0
  5225.6     .17       0
Bank Sta=4985.5,5013.6
XS Rating Curve= 0 ,0
Exp/Cntr=0.3,0.1

Type RM Length L Ch R = 1 ,7933    ,430,430,430
BEGIN DESCRIPTION:
CCLC 126 15.0
END DESCRIPTION:
XS GIS Cut Line= 3
      3703717.83     10163361.07      3703420.78     10163304.44
      3703167.83     10162961.04
#Sta/Elev= 30
  4697.6  319.45  4700.1  319.45  4707.8  322.28  4717.9  322.36  4723.7  321.37
  4728.7  321.55  4768.8  315.05    4828  312.01  4844.1  310.59  4885.2  309.38
  4943.8  309.92  4952.1  307.98  4962.3  305.49  4982.6  304.98  4987.5  304.15
  4987.7  303.65  4991.2  303.65  4994.6  306.87  4998.9  308.31  5005.2  308.31
  5011.9  309.56  5018.1   309.8    5069  309.61  5121.7  309.51  5218.6  309.88
  5312.7  312.01  5389.9  315.37  5419.1  317.77  5423.4     319  5426.5     319
#Mann= 7 ,-1 , 0
  4697.6     .11       0  4844.1     .17       0  4943.8     .15       0
  4952.1     .09       0  4998.9     .17       0    5069     .15       0
  5121.7     .11       0
Bank Sta=4952.1,4998.9
XS Rating Curve= 0 ,0
Exp/Cntr=0.3,0.1

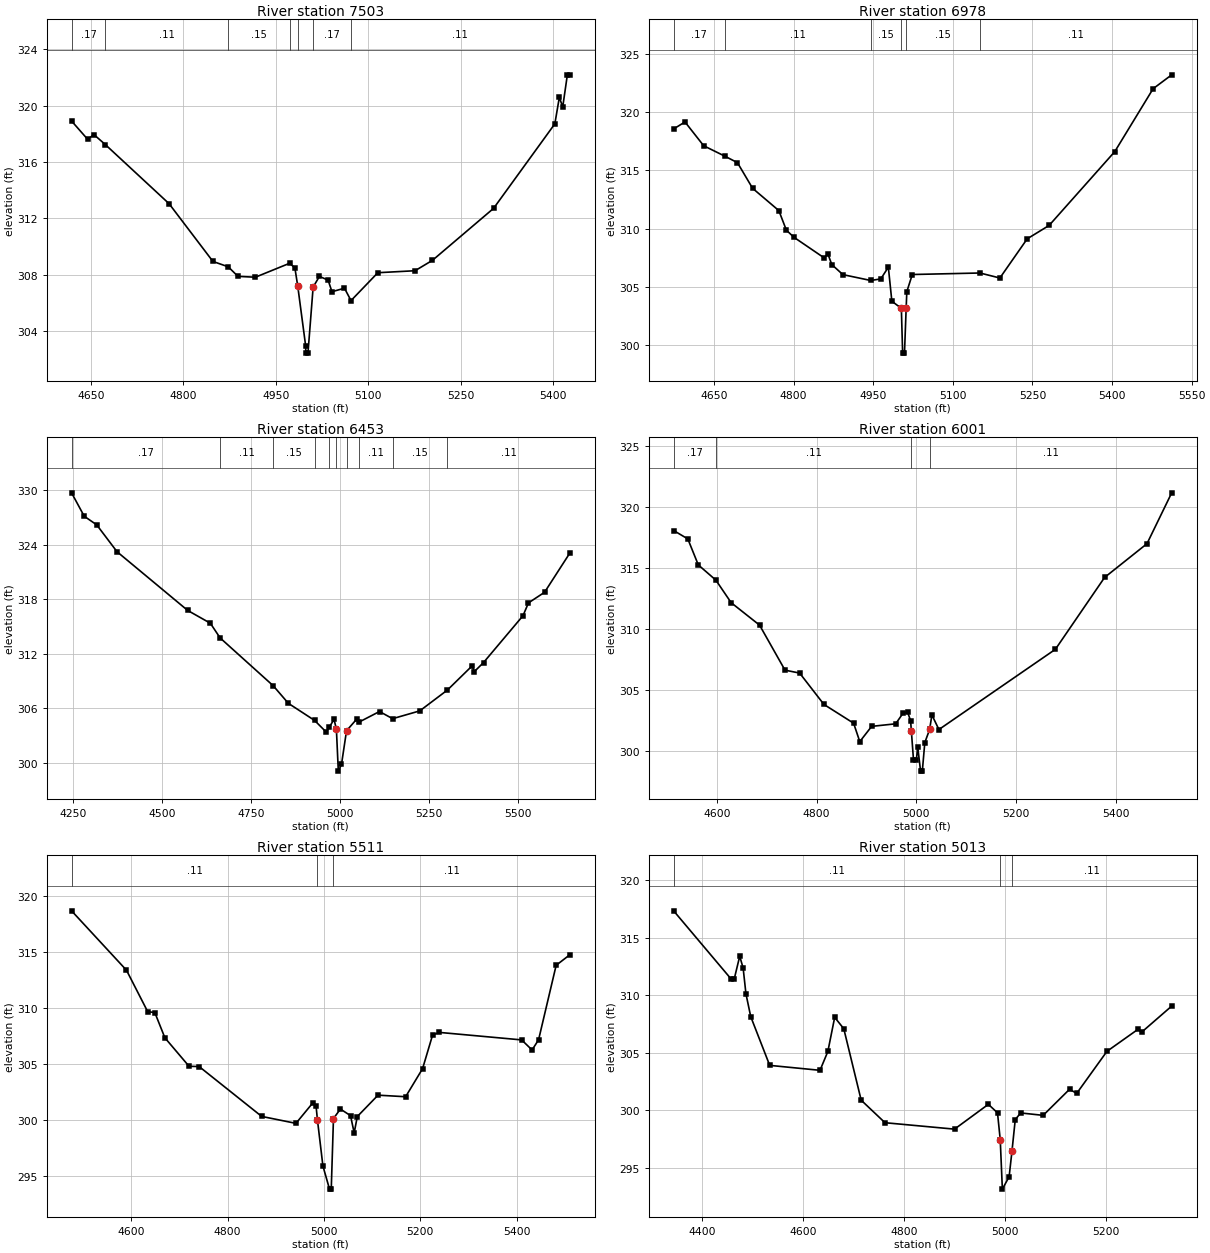
Type RM Length L Ch R = 1 ,7503    ,525,525,525
BEGIN DESCRIPTION:
CCLC 126 14.0
END DESCRIPTION:
XS GIS Cut Line= 3
      3703933.51     10163098.88      3703485.58     10163019.01
      3703166.14     10162869.71
#Sta/Elev= 30
  4618.7   318.9  4644.8   317.6  4654.9  317.94  4673.6  317.22  4776.8  313.03
  4847.9  308.93  4872.7  308.55  4888.5  307.87  4916.7  307.81  4972.3   308.8
  4980.8  308.47 4985.41307.1861  4998.3  302.92  4998.5  302.42    5002  302.42
  5010.4  307.11  5020.6  307.87  5034.7   307.6  5040.9  306.78  5061.2  307.03
  5071.8  306.15  5115.3  308.13  5175.6  308.27  5203.9  309.01    5303   312.7
  5402.3   318.7  5409.6  320.58  5415.1   319.9  5422.6  322.18  5426.3  322.18
#Mann= 7 ,-1 , 0
  4618.7     .17       0  4673.6     .11       0  4872.7     .15       0
  4972.3     .17       0 4985.41     .09       0  5010.4     .17       0
  5071.8     .11       0
Bank Sta=4985.41,5010.4
XS Rating Curve= 0 ,0
Exp/Cntr=0.3,0.1

Type RM Length L Ch R = 1 ,6978    ,525,525,525
BEGIN DESCRIPTION:
CCLC 126 13.0
END DESCRIPTION:
XS GIS Cut Line= 3
      3703967.87     10163061.09      3703690.86     10162737.58
       3703193.9     10162612.76
#Sta/Elev= 30
  4574.1  318.55  4595.5  319.15  4630.7  317.11  4670.4  316.22  4694.3  315.66
  4722.9  313.46  4772.3  311.55  4786.5  309.87  4800.8  309.26  4857.9  307.49
  4864.5  307.86  4872.1  306.92    4893  306.06  4945.3  305.56  4964.3  305.69
  4978.6   306.7  4985.2  303.78  5003.1  303.17  5005.5  299.33    5009  299.33
 5012.18303.2146  5013.4   304.6  5023.7  306.07  5151.2   306.2  5188.7  305.77
  5240.2  309.13  5281.5  310.28  5405.2  316.61  5477.4     322  5512.4  323.19
#Mann= 6 ,-1 , 0
  4574.1     .17       0  4670.4     .11       0  4945.3     .15       0
  5003.1     .09       0 5012.18     .15       0  5151.2     .11       0
Bank Sta=5003.1,5012.18
XS Rating Curve= 0 ,0
Exp/Cntr=0.3,0.1

Type RM Length L Ch R = 1 ,6453    ,452,452,452
BEGIN DESCRIPTION:
CCLC 126 12.0
END DESCRIPTION:
XS GIS Cut Line= 3
      3704417.82     10163011.04      3703805.03     10162484.29
       3703217.9     10162561.07
#Sta/Elev= 30
  4245.3  329.74  4280.9  327.16    4316  326.21  4373.1  323.25  4571.7  316.78
  4635.4  315.37  4662.9  313.75  4812.2  308.48  4854.8  306.54  4928.4  304.66
  4961.3  303.37  4970.1  303.94  4983.2  304.77  4989.8  303.68  4995.2  299.07
  5004.1  299.81  5018.3  303.52  5046.8   304.8  5054.2  304.49    5111  305.64
  5147.8  304.85  5224.2  305.71    5302  308.01  5371.9  310.69  5376.9  310.01
  5403.5  311.04  5514.4   316.2  5529.7  317.61    5575  318.78  5645.5  323.07
#Mann= 10 ,-1 , 0
  4245.3     .17       0  4662.9     .11       0  4812.2     .15       0
  4928.4     .11       0  4970.1     .15       0  4989.8     .09       0
  5018.3     .15       0  5054.2     .11       0  5147.8     .15       0
    5302     .11       0
Bank Sta=4989.8,5018.3
XS Rating Curve= 0 ,0
Exp/Cntr=0.3,0.1

Type RM Length L Ch R = 1 ,6001    ,490,490,490
BEGIN DESCRIPTION:
CCLC 126 11.0
END DESCRIPTION:
XS GIS Cut Line= 3
      3704367.83     10162711.04      3704096.44     10162306.56
      3703717.87     10161961.09
#Sta/Elev= 30
  4512.9   318.1  4541.4  317.41  4562.4  315.28  4597.7  314.03  4628.4  312.18
  4685.4  310.34  4736.4  306.65  4765.8  306.41  4814.5  303.84  4874.1   302.3
  4886.5  300.79  4910.3  302.04  4958.5  302.25  4973.5  303.13  4982.5   303.2
  4988.5   302.5 4989.96301.6894  4994.3  299.28    5000  299.28  5002.8  300.34
  5008.5  298.37    5012  298.37    5017  300.71 5026.71301.7915  5031.2  302.98
  5045.3  301.78  5279.1  308.36  5377.8  314.25  5462.9  317.02  5512.5  321.19
#Mann= 4 ,-1 , 0
  4512.9     .17       0  4597.7     .11       0 4989.96     .07       0
 5026.71     .11       0
Bank Sta=4989.96,5026.71
XS Rating Curve= 0 ,0
Exp/Cntr=0.3,0.1

Type RM Length L Ch R = 1 ,5511    ,498,498,498
BEGIN DESCRIPTION:
CCLC 126 10.0
END DESCRIPTION:
XS GIS Cut Line= 3
      3704717.85     10162561.07      3704410.16     10162136.81
      3704017.86     10161811.08
#Sta/Elev= 30
  4475.9  318.67  4589.9  313.36    4634  309.65  4648.7  309.58  4669.6  307.32
  4719.8  304.77  4740.7  304.75  4870.6  300.29  4941.7  299.67  4977.3  301.53
  4983.5  301.21 4986.31299.9835  4997.7  295.86  5011.4  293.79    5015  293.79
  5019.6   300.1    5034  300.95    5055  300.36  5062.6  298.82  5069.1  300.28
  5112.1  302.19  5169.4  302.05  5204.6  304.56  5225.4  307.57  5239.7   307.8
  5410.3  307.13  5431.9  306.23  5445.4  307.14  5481.9   313.8  5509.9  314.73
#Mann= 3 , 0 , 0
  4475.9     .11       0 4986.31     .06       0  5019.6     .11       0
Bank Sta=4986.31,5019.6
XS Rating Curve= 0 ,0
Exp/Cntr=0.3,0.1

Type RM Length L Ch R = 1 ,5013    ,498,498,498
BEGIN DESCRIPTION:
CCLC 126 9.0
END DESCRIPTION:
XS GIS Cut Line= 3
      3704917.86      10162461.1       3704658.1     10161858.94
      3704517.87      10161561.1
#Sta/Elev= 30
  4344.2  317.35  4458.2   311.4    4464  311.41  4474.9   313.4  4481.7  312.36
  4487.2  310.13  4496.7  308.14  4534.2   303.9  4633.7  303.47  4649.2  305.11
  4662.7  308.08  4680.7  307.09  4715.1  300.87  4762.2  298.91  4899.7  298.35
  4966.6  300.51  4984.7  299.77  4990.1  297.44  4994.3  293.13  5007.7  294.21
  5013.3  296.43  5019.8  299.18  5030.5  299.76    5075  299.55  5127.2  301.82
  5141.3  301.46  5201.1  305.12  5262.9  307.05  5269.5  306.78  5329.2  309.06
#Mann= 3 , 0 , 0
  4344.2     .11       0  4990.1     .06       0  5013.3     .11       0
Bank Sta=4990.1,5013.3
XS Rating Curve= 0 ,0
Exp/Cntr=0.3,0.1

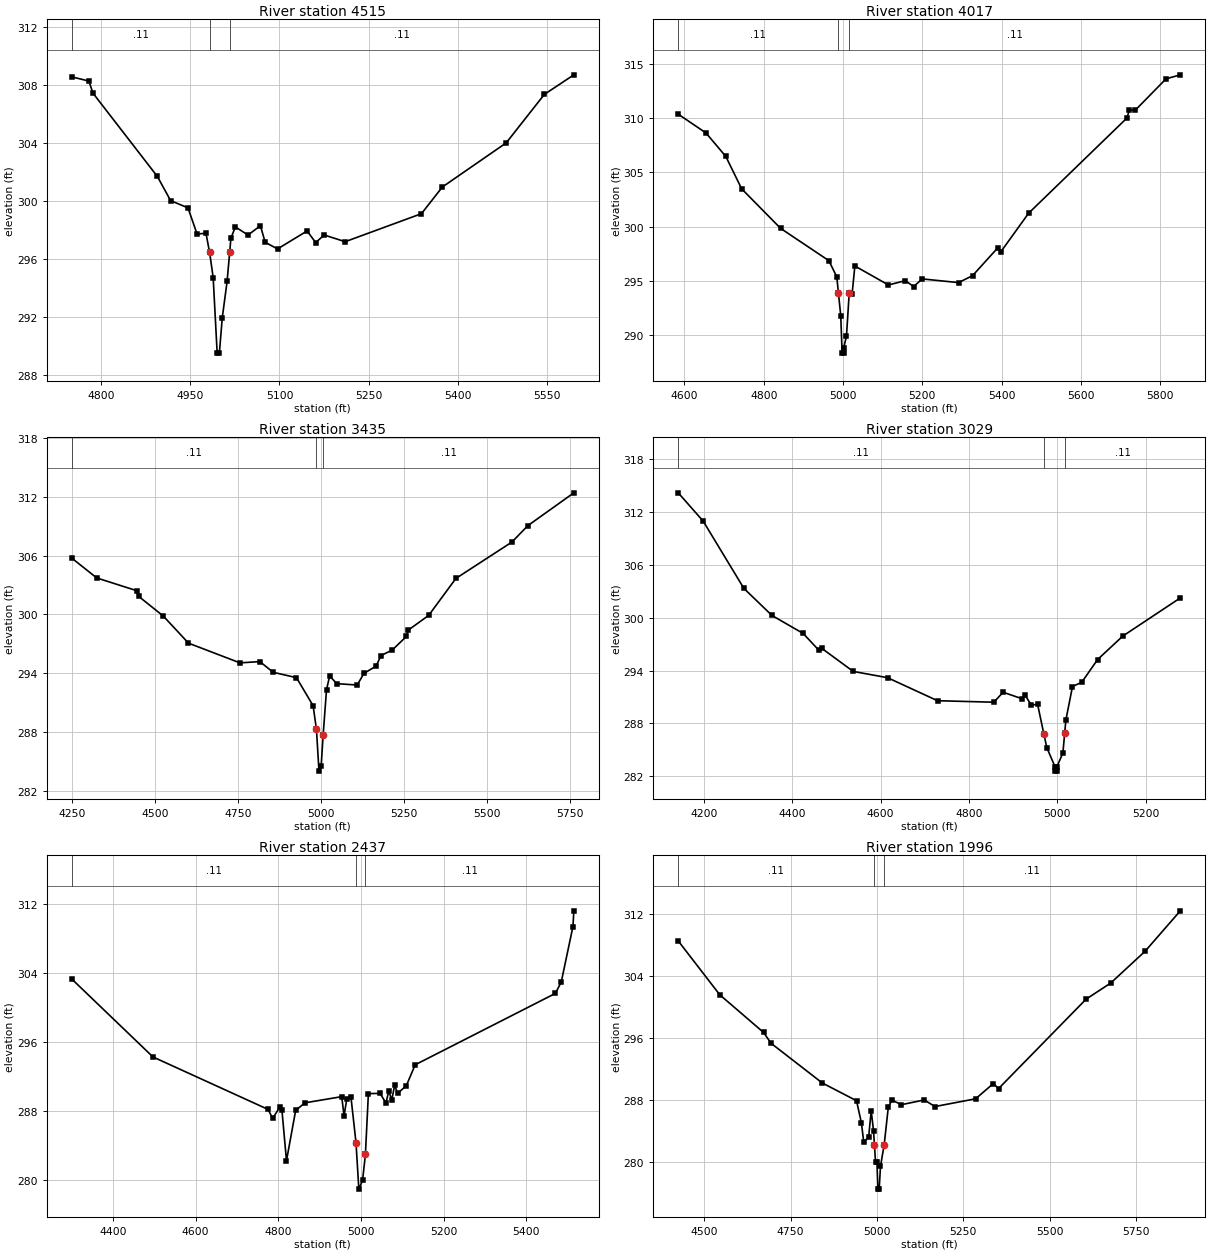
Type RM Length L Ch R = 1 ,4515    ,498,498,498
BEGIN DESCRIPTION:
CCLC 126 8.0
END DESCRIPTION:
XS GIS Cut Line= 3
      3705167.87      10162111.1      3705033.62     10161901.27
      3704662.92     10161435.99
#Sta/Elev= 30
  4750.9  308.56  4779.7  308.27  4786.5  307.44  4894.7   301.7  4917.1  300.03
  4946.3  299.53  4961.5  297.73  4976.5  297.78  4982.6  296.46  4988.6  294.73
  4995.3  289.52    4999  289.52  5003.9  291.96    5012  294.46 5016.36296.4833
  5018.4  297.43  5025.8  298.22  5047.2  297.66    5068   298.3    5076  297.16
  5096.8   296.7  5146.5  297.94  5160.9  297.14  5175.3  297.66  5210.5   297.2
  5338.7  299.13  5373.9  300.97  5481.2  304.01  5545.3  307.35  5594.9   308.7
#Mann= 3 , 0 , 0
  4750.9     .11       0  4982.6     .06       0 5016.36     .11       0
Bank Sta=4982.6,5016.36
XS Rating Curve= 0 ,0
Exp/Cntr=0.3,0.1

Type RM Length L Ch R = 1 ,4017    ,582,582,582
BEGIN DESCRIPTION:
CCLC 126 7.0
END DESCRIPTION:
XS GIS Cut Line= 3
      3705417.85     10162111.02       3705425.8      10161695.4
      3704815.19     10161102.64
#Sta/Elev= 30
  4584.3  310.35  4654.3  308.62  4704.3  306.46  4744.3  303.48  4842.6  299.84
  4964.3  296.87  4984.3  295.38 4988.51 293.877  4994.3  291.81  4997.8  288.36
  5001.5  288.36  5001.8  288.86  5008.7  289.91  5015.7   293.9  5022.9  293.78
  5029.9  296.38  5114.7  294.63  5157.2  295.03  5178.3  294.48  5199.6  295.19
  5291.5  294.85  5326.9  295.49  5390.5  298.05  5397.7  297.66  5468.4  301.24
  5715.9  309.98  5722.8  310.75    5737   310.7  5814.9   313.6    5851  313.97
#Mann= 3 , 0 , 0
  4584.3     .11       0 4988.51     .06       0  5015.7     .11       0
Bank Sta=4988.51,5015.7
XS Rating Curve= 0 ,0
Exp/Cntr=0.3,0.1

Type RM Length L Ch R = 1 ,3435    ,406,406,406
BEGIN DESCRIPTION:
CCLC 126 6.0
END DESCRIPTION:
XS GIS Cut Line= 3
      3705579.33     10162116.24       3705629.5     10161366.92
      3705461.62     10160624.67
#Sta/Elev= 30
    4249  305.74  4324.3  303.72  4444.6  302.42  4450.5  301.84  4524.8  299.83
  4600.5  297.07  4755.5  295.06  4815.4  295.19  4855.5   294.1  4925.7  293.55
  4975.8  290.69  4985.8  288.29  4993.5  284.02    5000  284.52    5006   287.7
  5016.2  292.33  5025.7  293.72    5047  292.94  5108.5   292.8    5129  293.99
  5165.5  294.73  5180.3  295.81  5213.8  296.36    5257  297.76  5262.3   298.4
  5323.8   299.9  5405.8  303.67  5574.5  307.38  5622.8  309.06    5761   312.4
#Mann= 3 , 0 , 0
    4249     .11       0  4985.8     .06       0    5006     .11       0
Bank Sta=4985.8,5006
XS Rating Curve= 0 ,0
Exp/Cntr=0.3,0.1

Type RM Length L Ch R = 1 ,3029    ,592,592,592
BEGIN DESCRIPTION:
CCLC 126 5.0
END DESCRIPTION:
XS GIS Cut Line= 3
      3706467.88      10161711.1        3705874.     10161091.44
      3705717.85     10160861.07
#Sta/Elev= 30
  4141.7  314.14  4198.2  310.93  4290.3  303.31  4353.9  300.24  4424.6   298.2
  4460.2  296.29  4467.1   296.5  4537.8   293.9  4615.5  293.19  4728.7  290.58
  4856.1  290.41  4877.2  291.54  4919.6  290.81  4926.9  291.22    4941  290.07
  4955.2  290.18  4969.3  286.82  4976.2  285.25  4994.6   283.1  4994.9   282.6
  4998.7   282.6    4999   283.1  5012.5  284.66 5016.66286.9698  5019.2  288.38
  5034.2  292.19  5055.2  292.67  5091.1  295.25    5148   297.9  5278.3  302.23
#Mann= 3 , 0 , 0
  4141.7     .11       0  4969.3     .06       0 5016.66     .11       0
Bank Sta=4969.3,5016.66
XS Rating Curve= 0 ,0
Exp/Cntr=0.3,0.1

Type RM Length L Ch R = 1 ,2437    ,441,441,441
BEGIN DESCRIPTION:
CCLC 126 4.0
END DESCRIPTION:
XS GIS Cut Line= 3
      3706509.91     10161474.78      3706193.99     10160850.46
      3705822.63     10160493.21
#Sta/Elev= 30
  4300.3  303.32  4496.8  294.27  4775.2  288.18  4786.5  287.14  4803.2   288.4
  4808.8  288.15  4819.9  282.22  4842.1  288.06  4864.4  288.94  4953.6  289.66
  4959.2  287.44  4965.7  289.34  4975.8  289.67  4988.1  284.33    4995  278.92
    5004  279.93  5010.9  282.95  5018.1  290.01  5046.4  290.04  5060.6  288.92
  5067.5  290.32  5074.7  289.28  5081.6  290.96  5088.9  290.04  5109.9  290.93
  5131.3  293.36  5470.6  301.65  5484.8  302.97  5513.1  309.41  5515.3  311.24
#Mann= 3 , 0 , 0
  4300.3     .11       0  4988.1     .06       0  5010.9     .11       0
Bank Sta=4988.1,5010.9
XS Rating Curve= 0 ,0
Exp/Cntr=0.3,0.1

Type RM Length L Ch R = 1 ,1996    ,466,466,466
BEGIN DESCRIPTION:
CCLC 126 3.0
END DESCRIPTION:
XS GIS Cut Line= 3
      3706817.84     10161361.06      3706424.98      10160940.1
      3706017.85     10160161.07
#Sta/Elev= 30
  4424.2  308.51  4544.6  301.56  4671.6   296.7  4693.1  295.31  4841.6  290.19
  4940.8   287.9    4955  285.04  4961.8  282.54    4976  283.25  4983.3  286.62
  4990.1  284.01 4992.81 282.127  4995.9  279.98    5000  279.98  5002.6   276.5
  5006.5   276.5  5010.2  279.42    5021  282.25  5032.8  287.03  5043.1  287.99
  5070.8  287.39    5137     288  5168.2  287.15  5285.9  288.15  5337.4  290.12
  5352.2  289.46  5605.8  300.99  5677.7  303.09  5776.8  307.17    5879  312.39
#Mann= 3 , 0 , 0
  4424.2     .11       0 4992.81     .06       0    5021     .11       0
Bank Sta=4992.81,5021
XS Rating Curve= 0 ,0
Exp/Cntr=0.3,0.1

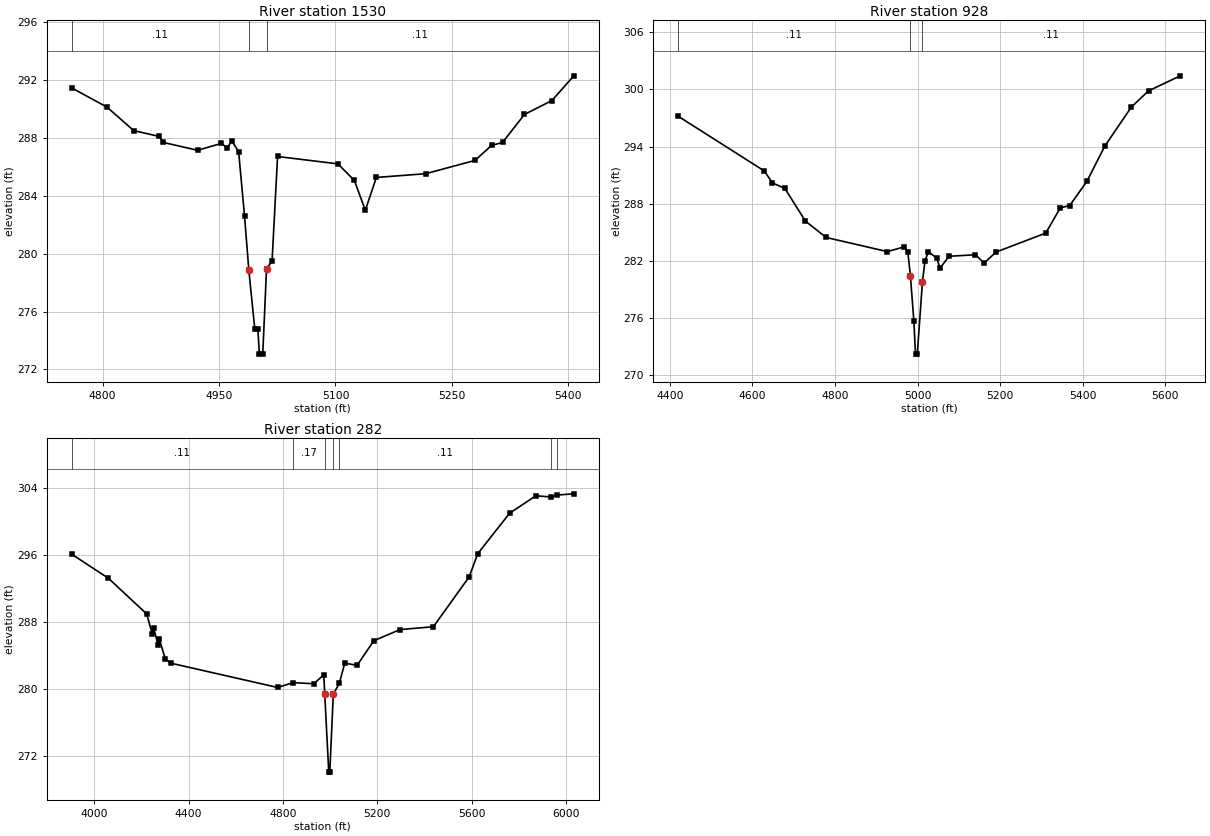
Type RM Length L Ch R = 1 ,1530    ,602,602,602
BEGIN DESCRIPTION:
CCLC 126 2.0
END DESCRIPTION:
XS GIS Cut Line= 3
      3706817.86     10160861.09      3706705.67     10160649.15
      3706417.87     10160361.09
#Sta/Elev= 30
  4760.2  291.47  4805.5  290.15  4840.1  288.52  4872.7  288.12  4878.4   287.7
  4922.4  287.16  4952.6  287.63  4960.7  287.35  4966.4   287.8  4975.2  287.07
  4982.8  282.63  4988.4  278.85  4996.1  274.77    5000  274.77    5002  273.06
  5006.3  273.06  5011.2  278.98  5018.3  279.48  5025.4  286.73  5103.2  286.22
  5124.4  285.07  5138.5  283.01  5152.7  285.28  5216.3  285.54  5279.9  286.46
  5301.2   287.5  5315.3   287.7  5343.6  289.64  5378.9   290.6  5407.2  292.31
#Mann= 3 , 0 , 0
  4760.2     .11       0  4988.4     .06       0  5011.2     .11       0
Bank Sta=4988.4,5011.2
XS Rating Curve= 0 ,0
Exp/Cntr=0.3,0.1

Type RM Length L Ch R = 1 ,928     ,646,646,646
BEGIN DESCRIPTION:
Mapping XS 0483aaa1
END DESCRIPTION:
XS GIS Cut Line= 3
      3707158.33     10160839.31      3707163.54     10160328.91
      3706732.03     10159770.04
#Sta/Elev= 30
  4420.1  297.18  4628.4  291.44  4648.4  290.18  4678.4   289.6  4728.4  286.16
  4778.4  284.45    4927  282.96  4968.2  283.47  4976.4  282.91  4982.7  280.41
  4990.9   275.7    4995  272.19  4999.3  272.19  5011.7  279.74    5018     282
  5026.2  282.95    5047  282.25  5054.1   281.2    5076  282.47  5140.3  282.63
  5161.1  281.76  5190.1  282.91  5310.6  284.91  5345.9  287.56  5368.6   287.8
  5410.2  290.34  5453.7  294.05    5518  298.15  5559.6  299.85  5636.6  301.43
#Mann= 3 , 0 , 0
  4420.1     .11       0  4982.7     .06       0  5011.7     .11       0
Bank Sta=4982.7,5011.7
XS Rating Curve= 0 ,0
Exp/Cntr=0.3,0.1

Type RM Length L Ch R = 1 ,282     ,0,0,0
BEGIN DESCRIPTION:
CCLC 126 1.0
END DESCRIPTION:
XS GIS Cut Line= 3
      3707246.88     10160802.85      3707625.34     10159844.53
      3706538.56     10159688.29
#Sta/Elev= 30
  3905.1  296.06  4060.2   293.2  4222.5  288.94  4246.9  286.51  4252.2  287.22
  4271.2  285.24  4276.6  285.92    4301   283.6  4325.3  283.06  4777.9  280.16
  4842.8  280.74  4931.2  280.61  4973.3  281.67 4977.34 279.402  4994.5  270.06
  4998.9  270.06  5013.7  279.34  5039.7  280.69  5062.2  283.06  5114.8  282.81
  5185.5  285.74  5296.6  287.07    5438  287.41  5589.6  293.36  5626.2  296.14
  5761.3  300.96  5872.5  303.04  5938.1  302.89  5960.1  303.12  6033.4  303.27
#Mann= 7 ,-1 , 0
  3905.1     .11       0  4842.8     .17       0 4977.34     .06       0
  5013.7     .17       0  5039.7     .11       0  5938.1     .15       0
  5960.1     .11       0
Bank Sta=4977.34,5013.7
XS Rating Curve= 0 ,0
Exp/Cntr=0.3,0.1

Chan Stop Cuts=-1
Use User Specified Reach Order=0
Composite Channel Slope=5