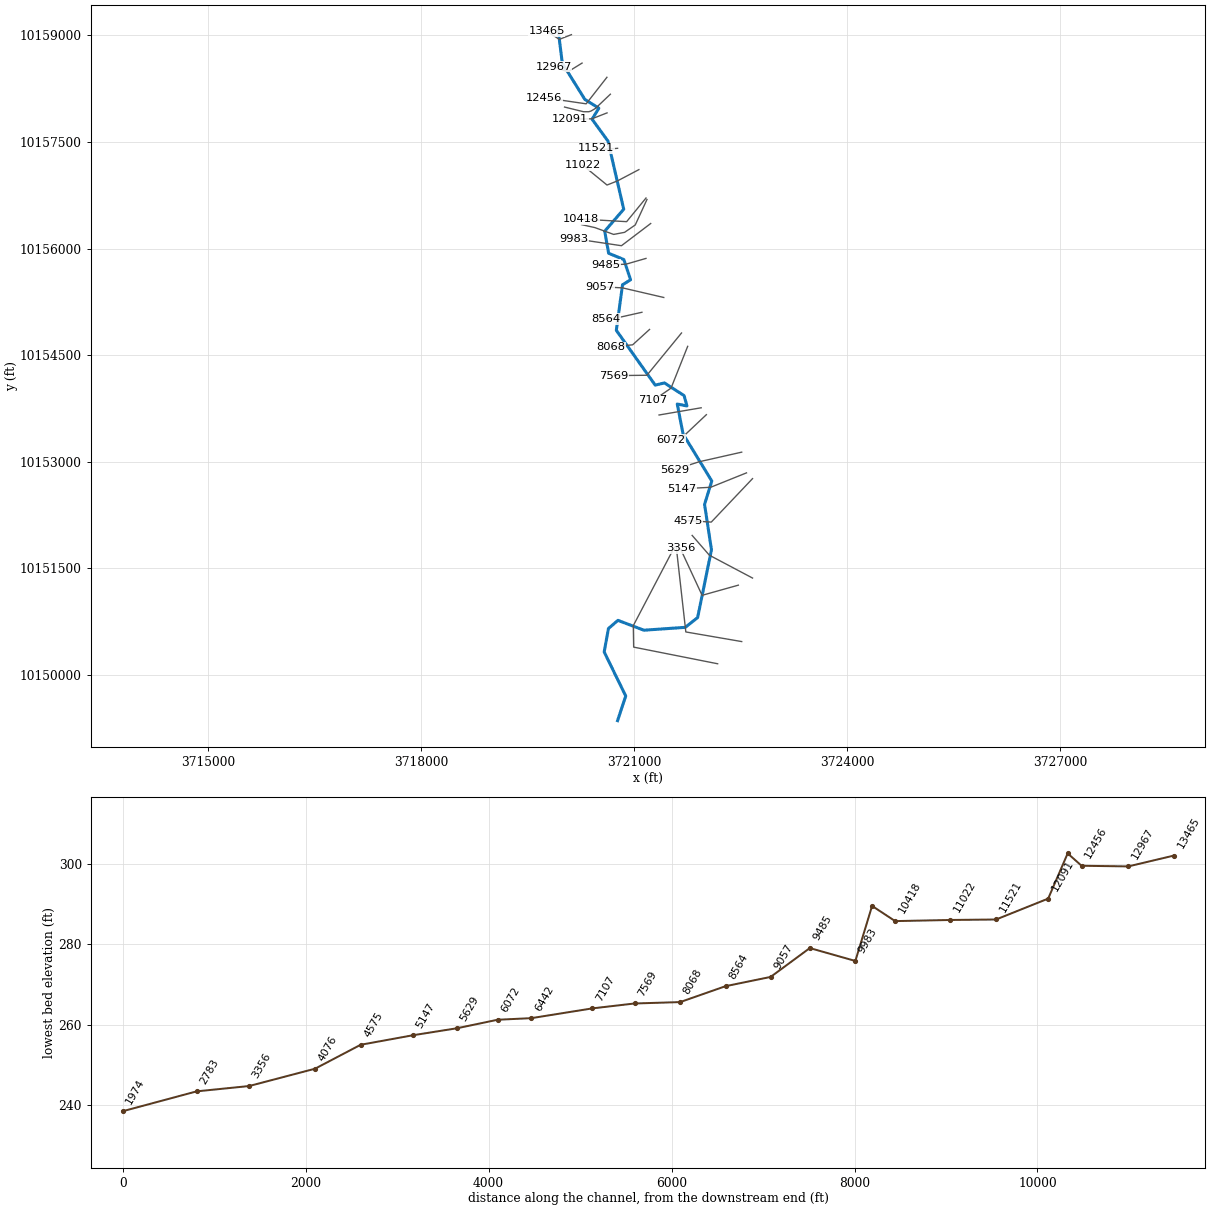
--- CCLC 127.prj (project) ---

Proj Title=CCLC 127 Base Level Engineering
Current Plan=p01
Default Exp/Contr=0.3,0.1
English Units
Geom File=g01
Flow File=f01
Flow File=f02
Plan File=p01
Y Axis Title=Elevation
X Axis Title(PF)=Main Channel Distance
X Axis Title(XS)=Station
BEGIN DESCRIPTION:
CCLC 127
END DESCRIPTION:
DSS Export Rating Curves= 0
DSS Export Rating Curve Sorted= 0
DSS Export Volume Flow Curves= 0
DXF OffsetX= 0
DXF OffsetY= 0
DXF ScaleX= 1
DXF ScaleY= 10

--- CCLC 127.p01 (plan) ---

Plan Title=Multiple Run
Short Identifier=Multiple
Geom File=g01
Flow File=f01
Subcritical Flow
K Sum by GR= 0
Std Step Tol= 0.01
Critical Tol= 0.01
Num of Std Step Trials= 20
Max Error Tol= 0.3
Flow Tol Ratio= 0.001
Split Flow NTrial= 30
Split Flow Tol= 0.02
Split Flow Ratio= 0.02
Log Output Level= 0
Friction Slope Method= 1
Unsteady Friction Slope Method= 2
Unsteady Bridges Friction Slope Method= 1
Parabolic Critical Depth
Global Vel Dist=  1 , 1 , 1
Global Log Level= 0
CheckData=True
Encroach Param= -1, 0, 0, 0
BEGIN DESCRIPTION:
Multiple Run
END DESCRIPTION:

--- CCLC 127.f01 (steady flow) ---

Flow Title=Multiple
Program Version=4.10
Number of Profiles= 7
Profile Names=10-year,25-year,50-year,1pct_min,100-year,1pct_plu,500-year
River Rch & RM=CCLC 127,Reach-1         ,13465
     198     249     320     136     411    1241     700
River Rch & RM=CCLC 127,Reach-1         ,12091
     307     399     524     228     688    2078    1218
River Rch & RM=CCLC 127,Reach-1         ,9983
     664     903    1222     545    1645    4968    3077
River Rch & RM=CCLC 127,Reach-1         ,2783
     907    1255    1719     774    2337    7058    4474
Boundary for River Rch & Prof#=CCLC 127,Reach-1         , 1
Up Type= 0
Dn Type= 3
Dn Slope=0.005
Boundary for River Rch & Prof#=CCLC 127,Reach-1         , 2
Up Type= 0
Dn Type= 3
Dn Slope=0.005
Boundary for River Rch & Prof#=CCLC 127,Reach-1         , 3
Up Type= 0
Dn Type= 3
Dn Slope=0.005
Boundary for River Rch & Prof#=CCLC 127,Reach-1         , 4
Up Type= 0
Dn Type= 3
Dn Slope=0.005
Boundary for River Rch & Prof#=CCLC 127,Reach-1         , 5
Up Type= 0
Dn Type= 3
Dn Slope=0.005
Boundary for River Rch & Prof#=CCLC 127,Reach-1         , 6
Up Type= 0
Dn Type= 3
Dn Slope=0.005
Boundary for River Rch & Prof#=CCLC 127,Reach-1         , 7
Up Type= 0
Dn Type= 3
Dn Slope=0.005
DSS Import GetInterval= 0
DSS Import GetPeak= 0
DSS Import FillOption= 0

--- CCLC 127.f02 (steady flow) ---

Flow Title=Orig_BLE_Flows
Program Version=4.10
Number of Profiles= 7
Profile Names=10-year,25-year,50-year,1pct_min,100-year,1pct_plu,500-year
River Rch & RM=CCLC 127,Reach-1         ,13465
     198     244     278     105     316     955     407
River Rch & RM=CCLC 127,Reach-1         ,12091
     307     391     456     175     529    1597     708
River Rch & RM=CCLC 127,Reach-1         ,9983
     664     885    1063     419    1265    3819    1789
River Rch & RM=CCLC 127,Reach-1         ,2783
     907    1230    1495     595    1798    5431    2601
Boundary for River Rch & Prof#=CCLC 127,Reach-1         , 1
Up Type= 0
Dn Type= 3
Dn Slope=0.005
Boundary for River Rch & Prof#=CCLC 127,Reach-1         , 2
Up Type= 0
Dn Type= 3
Dn Slope=0.005
Boundary for River Rch & Prof#=CCLC 127,Reach-1         , 3
Up Type= 0
Dn Type= 3
Dn Slope=0.005
Boundary for River Rch & Prof#=CCLC 127,Reach-1         , 4
Up Type= 0
Dn Type= 3
Dn Slope=0.005
Boundary for River Rch & Prof#=CCLC 127,Reach-1         , 5
Up Type= 0
Dn Type= 3
Dn Slope=0.005
Boundary for River Rch & Prof#=CCLC 127,Reach-1         , 6
Up Type= 0
Dn Type= 3
Dn Slope=0.005
Boundary for River Rch & Prof#=CCLC 127,Reach-1         , 7
Up Type= 0
Dn Type= 3
Dn Slope=0.005
DSS Import GetInterval= 0
DSS Import GetPeak= 0
DSS Import FillOption= 0

--- CCLC 127.g01 (geometry) ---

Geom Title=Existing Conditions
Program Version=4.10

River Reach=CCLC 127        ,Reach-1
Reach XY= 30
      3719933.23     10159061.84       3719989.8     10158608.23
      3720307.51     10158099.11      3720504.04     10157975.64
      3720408.93     10157821.11      3720633.03     10157511.87
      3720854.38     10156553.54      3720586.57     10156244.05
      3720641.91     10155933.53      3720855.83     10155845.05
      3720950.74     10155560.05      3720837.46     10155489.74
      3720749.95      10154848.5      3721297.61     10154077.07
       3721427.3     10154108.23      3721704.48     10153929.16
      3721744.28      10153783.7       3721607.9     10153811.16
      3721689.54     10153389.35      3722094.01     10152727.45
       3721992.4     10152398.05      3722089.58     10151758.92
      3721894.66     10150804.46      3721721.29     10150667.12
      3721137.98     10150626.76      3720773.08     10150765.56
      3720639.49     10150650.92      3720579.09     10150321.13
       3720882.7     10149700.78      3720767.85     10149353.46

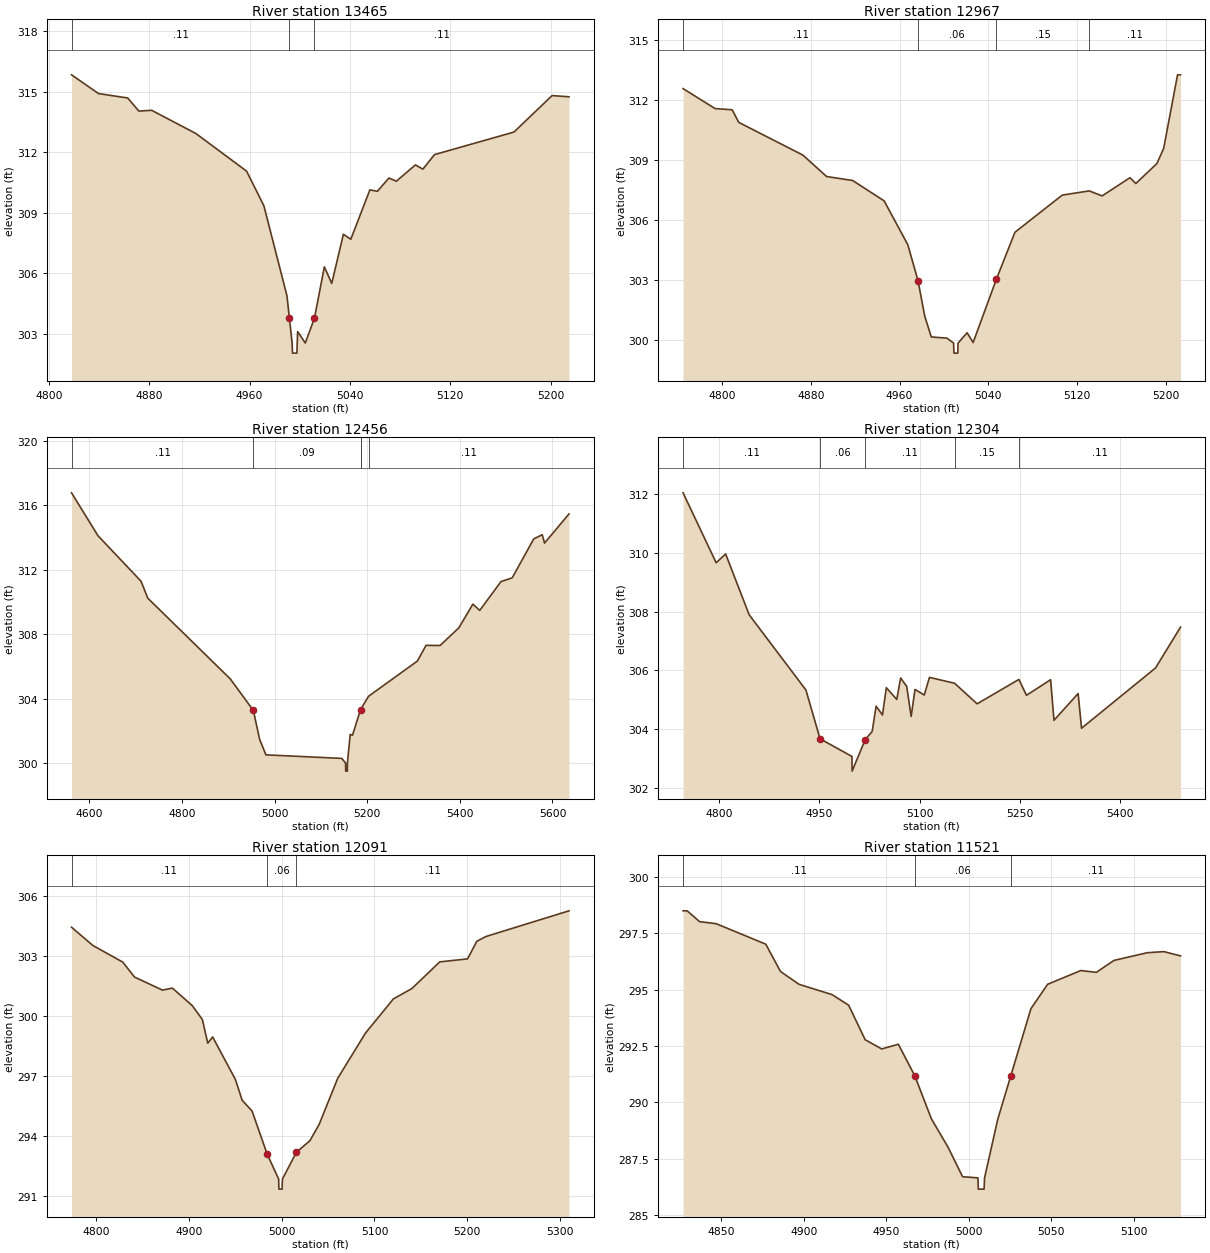
Type RM Length L Ch R = 1 ,13465   ,498,498,498
BEGIN DESCRIPTION:
CCLC 127 21.0
END DESCRIPTION:
XS GIS Cut Line= 3
      3720117.89     10159011.09      3719948.37     10158944.84
      3719767.85     10159061.07
#Sta/Elev= 30
    4818  315.84  4839.5  314.91  4862.8  314.69  4871.7  314.04  4881.9  314.08
  4917.1  312.93  4957.6  311.06  4971.4  309.34  4989.8  304.87 4991.72 303.774
  4993.9  302.53  4994.2  302.03  4997.7  302.03  4998.3   303.1  5004.4  302.53
 5011.71303.7664  5019.6  306.31  5025.5  305.49  5034.8  307.93  5040.7  307.68
  5055.9  310.13  5061.9  310.06  5071.1  310.72    5077  310.56  5092.2  311.37
  5098.2  311.16  5107.4  311.88  5170.8     313  5201.2  314.81  5214.7  314.75
#Mann= 3 , 0 , 0
    4818     .11       0 4991.72     .06       0 5011.71     .11       0
Bank Sta=4991.72,5011.71
XS Rating Curve= 0 ,0
Exp/Cntr=0.3,0.1

Type RM Length L Ch R = 1 ,12967   ,511,511,511
BEGIN DESCRIPTION:
CCLC 127 20.0
END DESCRIPTION:
XS GIS Cut Line= 3
      3720267.83     10158611.06      3720067.92     10158487.13
      3719867.85     10158561.07
#Sta/Elev= 30
  4764.8  312.58  4793.7  311.58  4809.1  311.52    4815  310.89  4872.9  309.25
  4894.2  308.18  4917.7  307.98  4946.1  306.96  4967.4  304.77  4976.6  302.97
  4982.7  301.19  4988.6  300.15  5002.7  300.09  5008.7  299.84    5009  299.34
  5012.5  299.34  5012.7  299.84  5020.9  300.36  5026.3  299.87 5047.29303.0426
    5064  305.39  5106.7  307.25    5131  307.46  5142.6  307.21  5167.7  308.12
    5173  307.83    5192  308.83  5198.1  309.59  5210.6  313.27  5213.3  313.27
#Mann= 4 ,-1 , 0
  4764.8     .11       0  4976.6     .06       0 5047.29     .15       0
    5131     .11       0
Bank Sta=4976.6,5047.29
XS Rating Curve= 0 ,0
Exp/Cntr=0.3,0.1

Type RM Length L Ch R = 1 ,12456   ,152,152,152
BEGIN DESCRIPTION:
CCLC 127 19.0
END DESCRIPTION:
XS GIS Cut Line= 3
      3720617.86     10158411.08      3720325.86     10158037.24
      3719732.53     10158123.99
#Sta/Elev= 30
  4561.7  316.78  4618.7  314.12  4711.8  311.29  4726.3  310.24  4904.3  305.23
  4954.2  303.27  4967.8  301.47  4981.4  300.51  5145.2  300.29  5153.3     300
  5153.6   299.5  5157.1   299.5  5157.3     300  5163.3  301.78  5168.3  301.73
  5185.6  303.32  5186.5  303.36    5203  304.15  5308.2  306.33  5327.1  307.31
  5357.4   307.3  5397.9   308.4  5428.2  309.87    5443  309.48  5488.8  311.27
    5513   311.5  5559.6  313.92  5577.9  314.18  5582.9  313.66  5635.7  315.47
#Mann= 5 ,-1 , 0
  4561.7     .11       0  4954.2     .09       0  5185.6     .11       0
  5186.5     .15       0    5203     .11       0
Bank Sta=4954.2,5185.6
XS Rating Curve= 0 ,0
Exp/Cntr=0.3,0.1

Type RM Length L Ch R = 1 ,12304   ,213,213,213
BEGIN DESCRIPTION:
Mapping XS 7a3f063d
END DESCRIPTION:
XS GIS Cut Line= 6
      3720666.15     10158172.67      3720454.33     10157971.27
      3720395.31     10157936.55      3720364.06     10157926.13
      3720287.67     10157926.13      3720021.55      10157991.8
#Sta/Elev= 30
  4746.1  312.04  4795.6  309.66  4809.8  309.96    4845  307.89  4929.9  305.33
    4951  303.67  4998.7  303.07    4999  302.57 5018.63303.6452    5029  303.92
  5034.9  304.78  5044.4  304.48  5050.2  305.41  5065.8  305.01  5071.6  305.74
  5080.7  305.45  5087.3  304.43  5093.1  305.35  5106.9  305.16  5114.7  305.76
  5152.3  305.56    5186  304.86  5248.5  305.69  5259.8  305.15  5295.9  305.68
    5301   304.3  5337.1  305.21  5342.2  304.03  5452.9  306.08  5490.3  307.47
#Mann= 5 ,-1 , 0
  4746.1     .11       0    4951     .06       0 5018.63     .11       0
  5152.3     .15       0  5248.5     .11       0
Bank Sta=4951,5018.63
XS Rating Curve= 0 ,0
Exp/Cntr=0.3,0.1

Type RM Length L Ch R = 1 ,12091   ,570,570,570
BEGIN DESCRIPTION:
CCLC 127 18.0
END DESCRIPTION:
XS GIS Cut Line= 3
      3720619.25     10157909.63      3720405.72     10157826.31
      3720098.48      10157821.1
#Sta/Elev= 30
  4773.3  304.42  4796.3  303.51  4828.5  302.68  4841.3  301.93  4871.4  301.28
  4882.1  301.38  4903.6   300.5  4914.4  299.81  4920.2  298.63  4925.5  298.94
    4950  296.82  4957.3  295.78    4968  295.24 4984.21293.0959  4996.7  291.84
  4996.9  291.34  5000.4  291.34  5000.7  291.84  5015.8  293.18  5030.4  293.76
  5040.4  294.58  5060.4  296.88  5090.4  299.14  5120.4  300.84  5140.4  301.36
  5170.4  302.69  5200.4  302.84  5210.4  303.72  5220.4  303.96  5309.8  305.24
#Mann= 3 , 0 , 0
  4773.3     .11       0 4984.21     .06       0  5015.8     .11       0
Bank Sta=4984.21,5015.8
XS Rating Curve= 0 ,0
Exp/Cntr=0.3,0.1

Type RM Length L Ch R = 1 ,11521   ,499,499,499
BEGIN DESCRIPTION:
CCLC 127 17.0
END DESCRIPTION:
XS GIS Cut Line= 3
      3720767.82     10157411.07      3720595.27     10157397.29
      3720467.81     10157411.08
#Sta/Elev= 30
  4826.9   298.5  4829.4   298.5  4836.9  298.02  4846.9  297.93    4877  297.02
  4885.9  295.81  4897.1  295.24  4917.2  294.78  4927.2  294.31  4937.2  292.78
  4947.2  292.37  4957.3  292.58  4967.3  291.17  4977.3  289.27  4987.4  288.01
  4996.2   286.7  5005.5  286.65  5005.7  286.15  5009.2  286.15  5009.5  286.65
  5017.5  289.25  5025.3291.1553  5037.6  294.16  5047.7  295.24  5067.8  295.85
  5077.2  295.77  5087.9   296.3    5108  296.64  5118.1  296.69  5128.2   296.5
#Mann= 3 , 0 , 0
  4826.9     .11       0  4967.3     .06       0  5025.3     .11       0
Bank Sta=4967.3,5025.3
XS Rating Curve= 0 ,0
Exp/Cntr=0.3,0.1

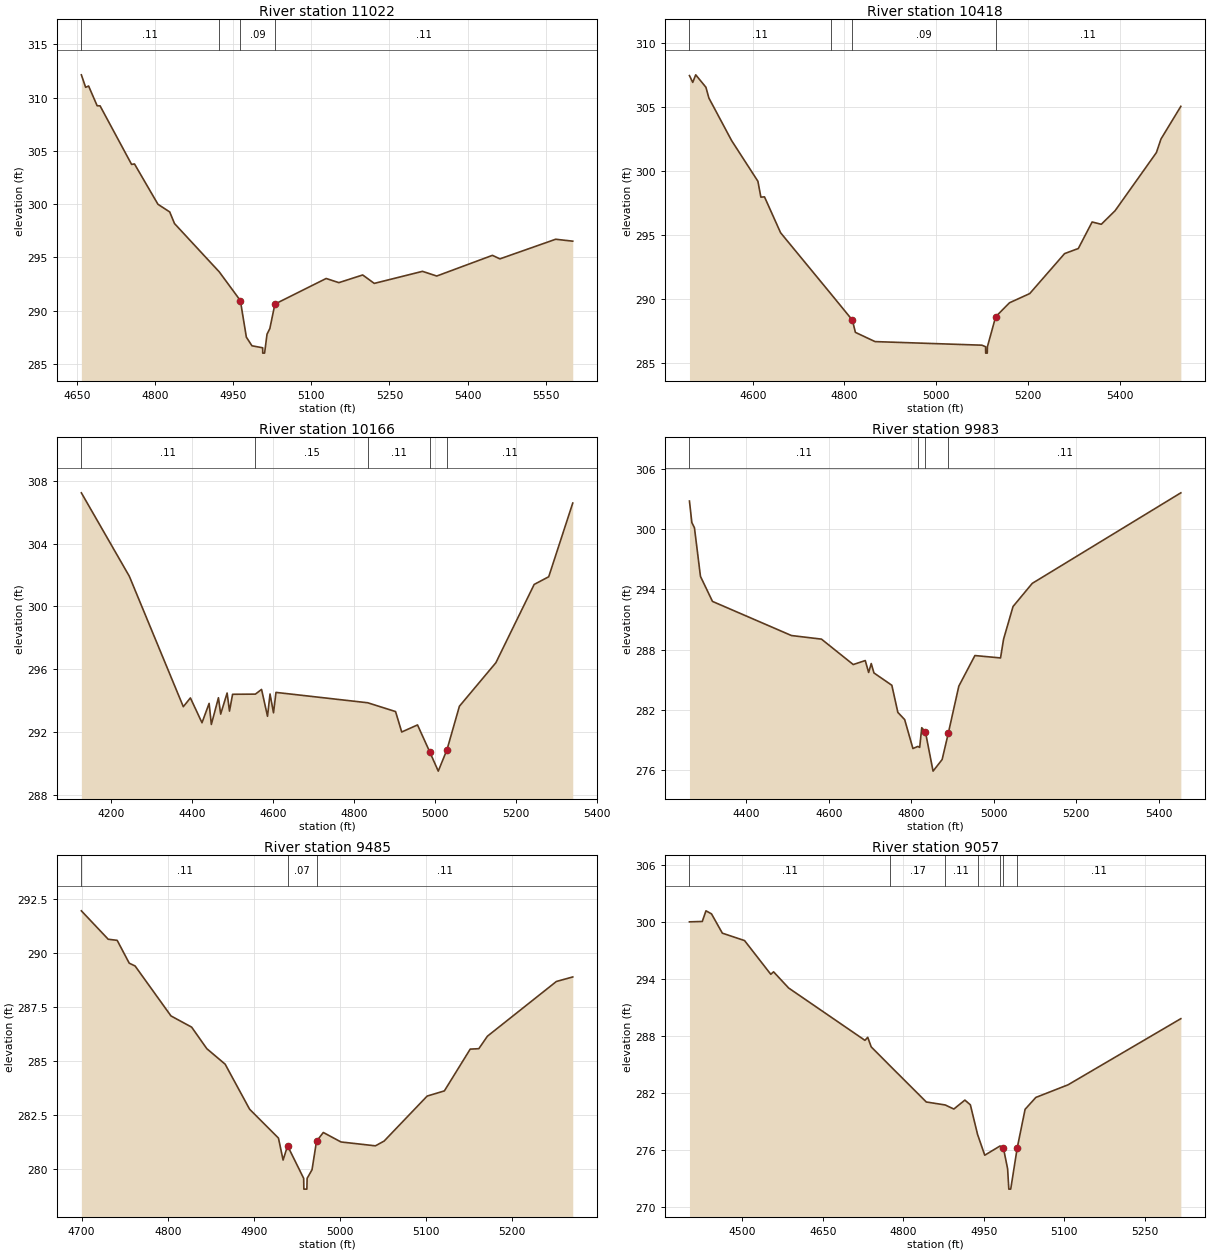
Type RM Length L Ch R = 1 ,11022   ,604,604,604
BEGIN DESCRIPTION:
CCLC 127 16.0
END DESCRIPTION:
XS GIS Cut Line= 4
      3721067.89     10157111.09      3720765.84     10156951.98
      3720619.27     10156894.01      3720275.49     10157175.28
#Sta/Elev= 30
  4658.6  312.13  4666.8  310.96  4672.5  311.08  4688.9  309.23  4694.5  309.22
    4755  303.73  4760.6  303.77  4805.6  299.99  4828.2  299.27  4837.4  298.18
  4923.3  293.65  4963.8  290.96  4975.3  287.53    4986  286.72  5006.6  286.53
  5006.8  286.03  5010.3  286.03    5015  287.81  5020.4  288.34  5030.1  290.63
  5128.5  293.03  5152.9  292.64  5198.6  293.36  5220.8  292.57  5313.4   293.7
  5340.7  293.26  5447.6   295.2    5462  294.87    5569  296.71  5601.8  296.53
#Mann= 4 ,-1 , 0
  4658.6     .11       0  4923.3     .15       0  4963.8     .09       0
  5030.1     .11       0
Bank Sta=4963.8,5030.1
XS Rating Curve= 0 ,0
Exp/Cntr=0.3,0.1

Type RM Length L Ch R = 1 ,10418   ,252,252,252
BEGIN DESCRIPTION:
CCLC 127 15.0
END DESCRIPTION:
XS GIS Cut Line= 3
      3721167.87     10156711.09      3720895.31     10156378.39
      3720254.63     10156414.85
#Sta/Elev= 30
    4462  307.42  4469.2  306.89  4475.7  307.48  4497.9  306.51  4504.4  305.67
  4553.9  302.35  4611.3  299.17  4617.8  297.93  4625.7  297.95  4660.8  295.15
  4770.5  290.38  4817.3  288.33    4824  287.37  4866.8  286.65  5099.9  286.37
  5107.9  286.25  5108.1  285.75  5111.6  285.75  5111.9  286.25  5129.9  288.59
    5160  289.68  5204.2   290.4  5280.2  293.52  5310.2  293.92  5340.3  295.99
  5360.3  295.81  5390.4  296.87  5480.5  301.41  5490.5  302.47  5533.8  305.02
#Mann= 4 ,-1 , 0
    4462     .11       0  4770.5     .15       0  4817.3     .09       0
  5129.9     .11       0
Bank Sta=4817.3,5129.9
XS Rating Curve= 0 ,0
Exp/Cntr=0.3,0.1

Type RM Length L Ch R = 1 ,10166   ,183,183,183
BEGIN DESCRIPTION:
Mapping XS 1e966b09
END DESCRIPTION:
XS GIS Cut Line= 6
      3721181.78     10156690.93       3721016.8     10156332.17
      3720866.11       10156228.      3720712.63     10156198.84
      3720447.39     10156295.06      3720259.92     10156336.72
#Sta/Elev= 30
  4127.6  307.23    4246  301.92  4379.2  293.62  4396.7  294.18  4425.3   292.6
  4442.9  293.83  4448.4  292.49  4465.9  294.19  4471.4  293.15  4487.3  294.49
  4493.2  293.34  4500.8  294.41  4557.1  294.42  4572.3  294.72    4587  293.01
  4593.2  294.43  4601.8  293.23  4607.9  294.53  4834.4  293.87    4903  293.31
  4918.2  292.01  4957.2  292.46    4988  290.71  5008.4  289.52    5030  290.89
  5060.6  293.65  5150.6  296.42  5245.1   301.4    5281  301.89  5340.3  306.58
#Mann= 5 ,-1 , 0
  4127.6     .11       0  4557.1     .15       0  4834.4     .11       0
    4988     .06       0    5030     .11       0
Bank Sta=4988,5030
XS Rating Curve= 0 ,0
Exp/Cntr=0.3,0.1

Type RM Length L Ch R = 1 ,9983    ,498,498,498
BEGIN DESCRIPTION:
CCLC 127 14.0
END DESCRIPTION:
XS GIS Cut Line= 3
      3721233.87     10156352.36      3720822.39     10156039.85
       3720155.7     10156138.81
#Sta/Elev= 30
  4262.6  302.84  4268.4  300.69  4274.7  300.17  4289.3  295.31  4318.4  292.81
  4509.7   289.4  4582.5  289.04  4659.5   286.5  4688.6   286.9  4696.8  285.71
  4703.1   286.6  4709.7  285.66    4753  284.43  4767.6  281.72  4784.1     281
  4804.1  278.11  4816.1  278.32  4820.5  278.22  4825.5  280.19  4834.4  279.77
  4852.9  275.85  4874.9  277.01  4889.9  279.65  4915.3  284.34  4954.3   287.4
  5016.4  287.16  5023.7  289.03  5046.7   292.3  5093.2  294.61  5453.3  303.66
#Mann= 4 ,-1 , 0
  4262.6     .11       0  4816.1     .15       0  4834.4     .06       0
  4889.9     .11       0
Bank Sta=4834.4,4889.9
XS Rating Curve= 0 ,0
Exp/Cntr=0.3,0.1

Type RM Length L Ch R = 1 ,9485    ,428,428,428
BEGIN DESCRIPTION:
CCLC 127 13.0
END DESCRIPTION:
XS GIS Cut Line= 3
      3721167.82     10155861.06      3720884.89     10155779.43
      3720608.86     10155769.01
#Sta/Elev= 30
  4699.7  291.97  4730.9  290.65  4741.3   290.6  4755.3  289.54  4762.1  289.41
  4803.8  287.09  4827.8  286.57  4845.4  285.57  4866.7  284.85  4895.1  282.76
  4928.6  281.42    4934   280.4  4939.2  281.06  4957.9  279.55  4958.1  279.05
  4961.6  279.05  4961.9  279.55  4967.6  279.95  4972.8  281.27  4980.7  281.68
  5001.2  281.24  5041.2  281.06  5051.3  281.28  5101.3  283.37  5121.3  283.61
  5151.3  285.55  5161.3  285.57  5171.3  286.15  5251.4  288.69  5270.4   288.9
#Mann= 3 ,-1 , 0
  4699.7     .11       0  4939.2     .07       0  4972.8     .11       0
Bank Sta=4939.2,4972.8
XS Rating Curve= 0 ,0
Exp/Cntr=0.3,0.1

Type RM Length L Ch R = 1 ,9057    ,493,493,493
BEGIN DESCRIPTION:
CCLC 127 12.0
END DESCRIPTION:
XS GIS Cut Line= 3
      3721417.87     10155311.07      3720834.85     10155446.77
      3720517.87     10155461.07
#Sta/Elev= 30
  4401.4  300.01  4425.3  300.05  4432.2  301.17  4442.5  300.85  4462.7  298.82
  4504.1  298.04    4553  294.49  4558.2  294.75  4586.2  293.05  4728.5  287.54
  4733.7  287.86  4740.2  286.85  4775.8  284.83  4842.9  281.05    4878  280.74
  4894.2  280.31  4914.8  281.25    4925  280.75  4938.4  277.64  4951.8  275.45
  4980.3  276.42  4986.7  276.17  4994.4  274.03  4996.7  271.88  5000.2  271.88
 5012.31276.2095    5027  280.28    5047  281.53  5107.1  282.86  5317.3  289.82
#Mann= 7 ,-1 , 0
  4401.4     .11       0  4775.8     .17       0    4878     .11       0
  4938.4     .17       0  4980.3     .11       0  4986.7     .07       0
 5012.31     .11       0
Bank Sta=4986.7,5012.31
XS Rating Curve= 0 ,0
Exp/Cntr=0.3,0.1

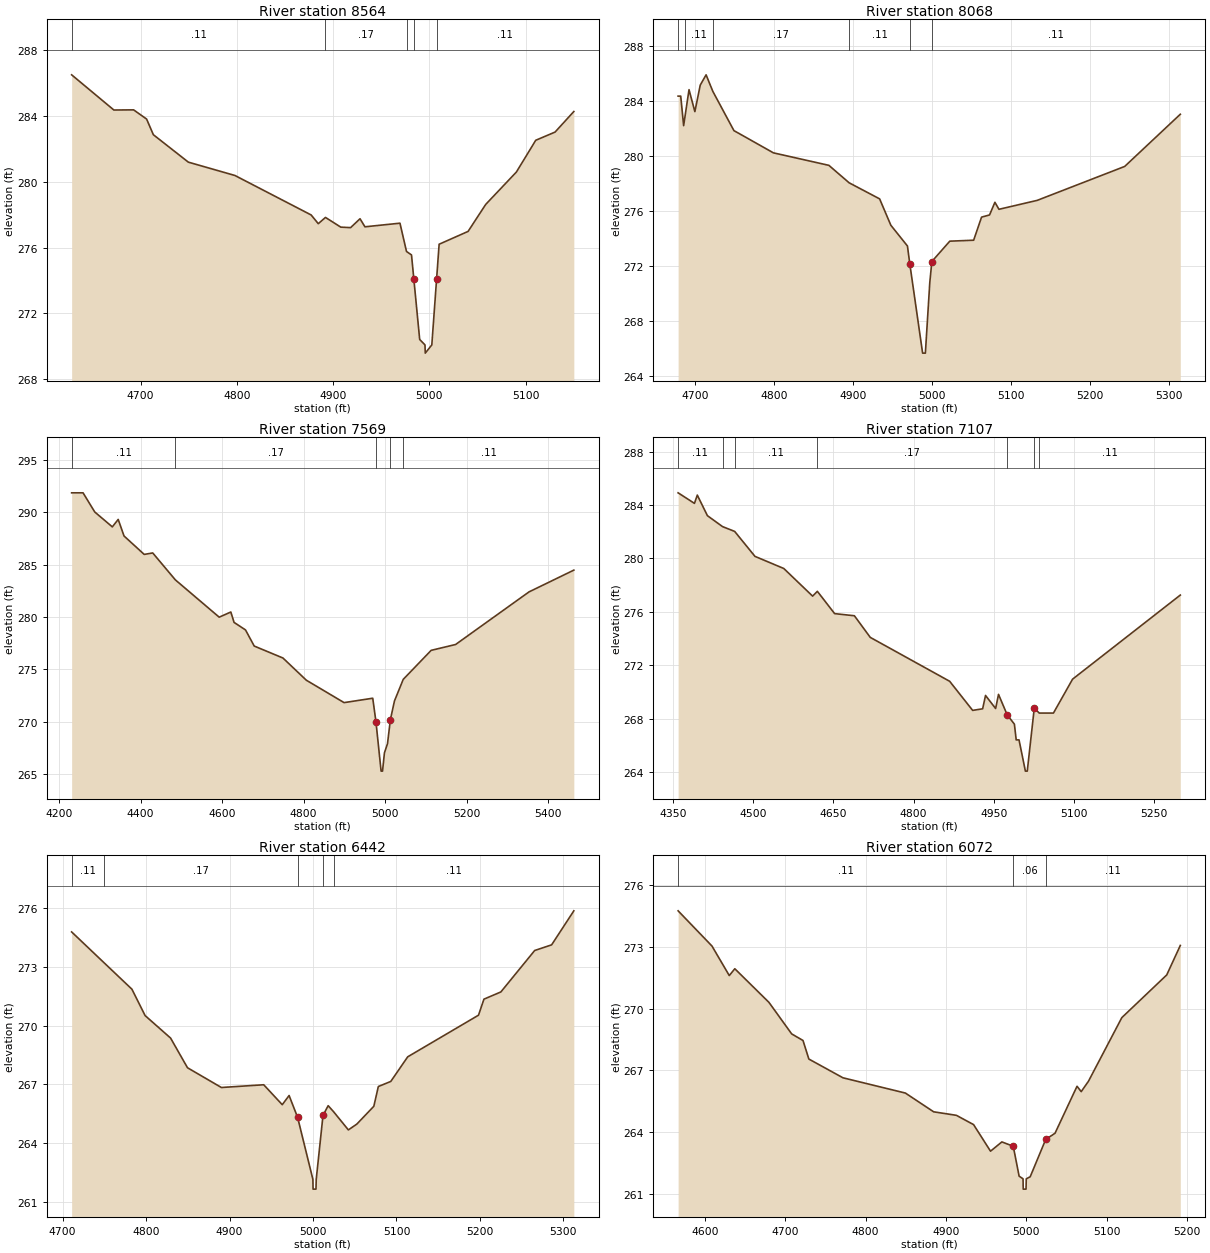
Type RM Length L Ch R = 1 ,8564    ,496,496,496
BEGIN DESCRIPTION:
CCLC 127 11.0
END DESCRIPTION:
XS GIS Cut Line= 3
      3721110.71     10155102.74      3720748.05      10155021.3
      3720598.38     10155008.59
#Sta/Elev= 30
  4628.3   286.5  4672.2  284.36  4692.7  284.37  4706.2  283.81  4713.2  282.86
  4749.6  281.19    4798  280.38  4877.2  277.98  4884.6  277.45  4892.1  277.83
    4908  277.24  4918.2  277.21    4928  277.75  4933.1  277.26  4969.5  277.48
  4976.3  275.76  4981.5  275.55 4983.88274.1109    4990  270.41  4995.5  270.08
  4995.8  269.58  5002.6  270.08 5007.58274.0901  5010.2   276.2  5040.3  276.98
  5058.6  278.62  5090.5  280.59  5110.6  282.52  5130.7  283.02  5150.2  284.27
#Mann= 5 ,-1 , 0
  4628.3     .11       0  4892.1     .17       0  4976.3     .11       0
 4983.88     .07       0 5007.58     .11       0
Bank Sta=4983.88,5007.58
XS Rating Curve= 0 ,0
Exp/Cntr=0.3,0.1

Type RM Length L Ch R = 1 ,8068    ,499,499,499
BEGIN DESCRIPTION:
CCLC 127 10.0
END DESCRIPTION:
XS GIS Cut Line= 3
      3721217.82     10154861.04       3720980.4     10154644.85
      3720667.82     10154611.07
#Sta/Elev= 30
  4678.9  284.34  4682.2  284.34  4685.9  282.19  4687.5  282.81  4692.7  284.81
  4700.1  283.21  4706.9  285.14  4714.3  285.89  4722.8  284.69  4749.5  281.83
  4799.5  280.21  4869.7   279.3  4895.3  278.03  4933.9  276.86  4948.1  274.94
  4969.1  273.43 4972.05272.1491  4988.3  265.63  4991.8  265.63  4997.4  270.78
    5000   272.3  5022.7  273.78  5052.9  273.85  5062.9  275.53    5073  275.69
  5079.8  276.61  5084.9   276.1  5133.3  276.75    5244  279.22  5314.4  283.02
#Mann= 6 ,-1 , 0
  4678.9     .17       0  4687.5     .11       0  4722.8     .17       0
  4895.3     .11       0 4972.05     .06       0    5000     .11       0
Bank Sta=4972.05,5000
XS Rating Curve= 0 ,0
Exp/Cntr=0.3,0.1

Type RM Length L Ch R = 1 ,7569    ,462,462,462
BEGIN DESCRIPTION:
CCLC 127 9.0
END DESCRIPTION:
XS GIS Cut Line= 3
      3721667.87     10154811.09      3721180.83     10154216.11
      3720717.85     10154211.07
#Sta/Elev= 30
  4231.1  291.85  4259.1  291.85  4287.8  290.02  4330.9   288.6  4345.3  289.31
  4359.6  287.73  4409.1  285.97    4430  286.11  4485.5  283.54    4593  279.98
  4621.6  280.47  4629.5  279.48  4657.6  278.76    4679  277.22  4749.4  276.08
  4806.8  273.96  4899.4  271.82  4969.7  272.24  4977.6  269.99  4990.2  265.28
  4993.7  265.28  4998.4  267.03  5005.9   267.9    5013   270.2    5023  271.98
  5044.5  274.04    5113  276.81    5173  277.37    5353  282.39    5463  284.47
#Mann= 5 ,-1 , 0
  4231.1     .11       0  4485.5     .17       0  4977.6     .09       0
    5013     .17       0  5044.5     .11       0
Bank Sta=4977.6,5013
XS Rating Curve= 0 ,0
Exp/Cntr=0.3,0.1

Type RM Length L Ch R = 1 ,7107    ,665,665,665
BEGIN DESCRIPTION:
CCLC 127 8.0
END DESCRIPTION:
XS GIS Cut Line= 3
      3721754.68     10154623.17      3721520.31     10154034.64
      3721267.89      10153861.1
#Sta/Elev= 30
  4359.3  284.91  4389.9  284.12  4395.2  284.74  4414.1   283.2  4442.4  282.38
  4465.1  282.02  4503.1  280.15  4557.1  279.24    4611  277.17  4619.9  277.53
  4652.2  275.86  4689.2   275.7  4718.9  274.08  4867.5  270.79  4910.5  268.61
  4929.2  268.73  4934.6  269.73  4953.5  268.75  4958.9  269.81  4975.1  268.28
  4988.6  267.58    4992   266.4  4997.3   266.4  5009.2  264.06  5012.7  264.06
  5025.8  268.77  5035.2  268.41  5061.7  268.41  5097.5  270.95  5299.1  277.25
#Mann= 7 ,-1 , 0
  4359.3     .11       0  4442.4     .17       0  4465.1     .11       0
  4619.9     .17       0  4975.1     .09       0  5025.8     .17       0
  5035.2     .11       0
Bank Sta=4975.1,5025.8
XS Rating Curve= 0 ,0
Exp/Cntr=0.3,0.1

Type RM Length L Ch R = 1 ,6442    ,370,370,370
BEGIN DESCRIPTION:
Mapping XS dfc31dee
END DESCRIPTION:
XS GIS Cut Line= 2
      3721944.63     10153758.16      3721351.67     10153656.57
#Sta/Elev= 30
  4710.9   274.8  4749.8  273.22  4783.1  271.87  4798.9  270.52  4829.4  269.37
  4849.7  267.85  4890.3  266.84    4941  266.98  4963.2  265.96  4971.4  266.43
  4981.6  265.31  4999.9  262.14  5000.1  261.64  5003.6  261.64  5003.9  262.14
    5012  265.41  5018.2  265.91  5024.7   265.6  5042.4  264.67  5052.6  264.97
  5072.9  265.88  5078.3  266.89  5093.2  267.15  5113.5  268.41  5198.3  270.54
  5204.8  271.36  5225.1  271.73  5265.6  273.85  5285.9  274.14  5312.5  275.88
#Mann= 5 ,-1 , 0
  4710.9     .11       0  4749.8     .17       0  4981.6     .09       0
    5012     .17       0  5024.7     .11       0
Bank Sta=4981.6,5012
XS Rating Curve= 0 ,0
Exp/Cntr=0.3,0.1

Type RM Length L Ch R = 1 ,6072    ,443,443,443
BEGIN DESCRIPTION:
CCLC 127 7.0
END DESCRIPTION:
XS GIS Cut Line= 3
      3722017.83     10153661.05      3721702.39     10153363.85
      3721517.89     10153311.08
#Sta/Elev= 30
  4566.6  274.74  4608.8  273.03  4630.3   271.6  4637.2  271.93  4679.7   270.3
    4708  268.77  4722.1  268.45  4729.4  267.55  4771.9  266.64  4849.6   265.9
  4884.8  264.99  4913.1  264.82  4934.5  264.37  4955.6  263.08  4969.7  263.53
  4983.9  263.32  4991.2  261.87  4996.1  261.74  4996.3  261.24  4999.8  261.24
  5000.1  261.74    5005  261.84  5024.3  263.65  5035.9  263.95  5063.3  266.23
  5068.5  265.97  5077.5  266.47  5119.1  269.56    5175  271.63  5191.9  273.06
#Mann= 3 , 0 , 0
  4566.6     .11       0  4983.9     .06       0  5024.3     .11       0
Bank Sta=4983.9,5024.3
XS Rating Curve= 0 ,0
Exp/Cntr=0.3,0.1

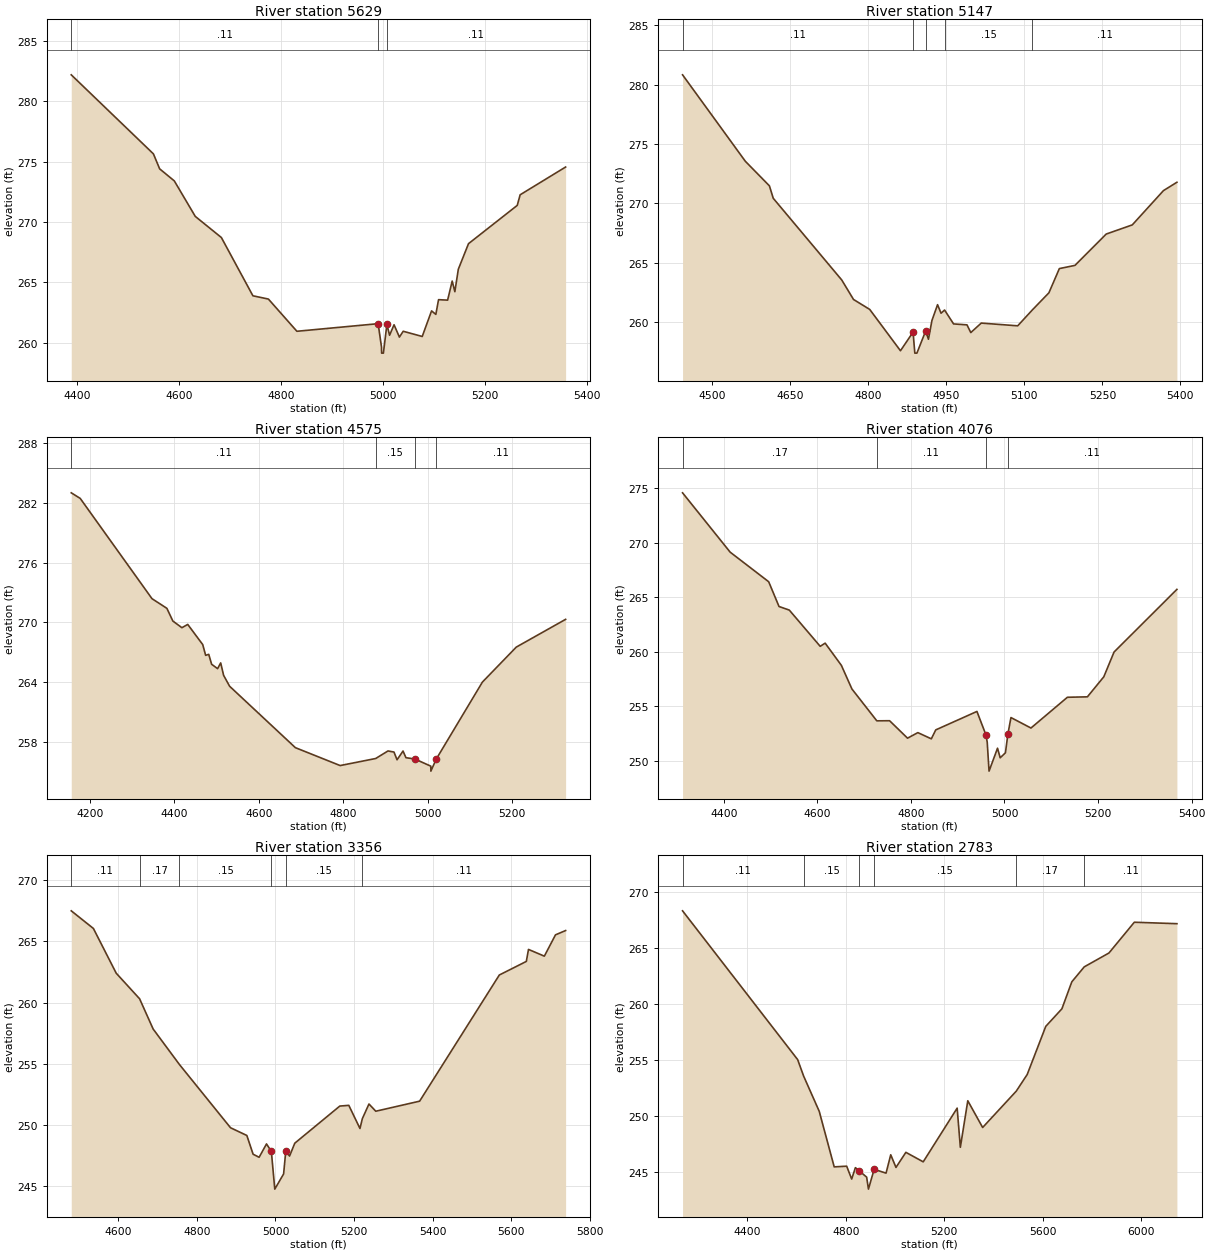
Type RM Length L Ch R = 1 ,5629    ,482,482,482
BEGIN DESCRIPTION:
CCLC 127 6.0
END DESCRIPTION:
XS GIS Cut Line= 3
      3722515.12      10153133.6      3721916.14     10152998.18
      3721577.57      10152888.8
#Sta/Elev= 30
  4388.3  282.19  4549.5  275.64  4561.7   274.4  4590.5   273.4  4631.6  270.46
  4682.8  268.71  4744.7  263.88  4775.1  263.61    4831  260.94  4990.4  261.57
    4997  259.63  4997.2  259.13  5000.7  259.13  5007.6  261.51  5012.8  260.61
  5021.6  261.48  5032.1  260.46  5039.6  260.94  5076.9  260.51  5095.2  262.63
  5103.6  262.34  5108.9  263.56  5126.7  263.52  5135.7   265.1  5140.9  264.22
  5147.7  266.08  5167.7   268.2  5263.3  271.37    5269  272.25  5358.2  274.55
#Mann= 3 , 0 , 0
  4388.3     .11       0  4990.4     .06       0  5007.6     .11       0
Bank Sta=4990.4,5007.6
XS Rating Curve= 0 ,0
Exp/Cntr=0.3,0.1

Type RM Length L Ch R = 1 ,5147    ,572,572,572
BEGIN DESCRIPTION:
CCLC 127 5.0
END DESCRIPTION:
XS GIS Cut Line= 3
      3722582.78     10152841.92       3722077.6     10152638.81
      3721672.12     10152618.01
#Sta/Elev= 30
  4442.8  280.83  4563.5  273.55  4609.8  271.48  4617.2  270.43  4748.9  263.55
  4771.5  261.91  4802.7  261.07  4861.8  257.59    4886  259.16  4889.4  257.39
  4893.4  257.39  4910.2  259.25  4915.6  258.56  4922.3  260.14  4933.1  261.47
  4939.8  260.75  4946.6  261.02  4963.9  259.85  4989.7  259.77    4997  259.12
  5017.1  259.92  5087.2  259.69  5115.4  261.03  5147.2  262.47  5167.3  264.51
  5197.3  264.78  5257.4  267.42  5307.5  268.19  5367.5  271.08  5393.3  271.78
#Mann= 5 ,-1 , 0
  4442.8     .11       0    4886     .09       0  4910.2     .11       0
  4946.6     .15       0  5115.4     .11       0
Bank Sta=4886,4910.2
XS Rating Curve= 0 ,0
Exp/Cntr=0.3,0.1

Type RM Length L Ch R = 1 ,4575    ,499,499,499
BEGIN DESCRIPTION:
CCLC 127 4.0
END DESCRIPTION:
XS GIS Cut Line= 3
      3722667.84     10152761.06      3722086.83     10152148.88
      3721761.41     10152169.96
#Sta/Elev= 30
    4156  283.02  4177.2  282.46  4347.1  272.37  4382.3   271.4  4396.5  270.12
  4417.9  269.45  4431.7  269.78  4467.2  267.75  4474.1  266.67  4481.4  266.77
  4488.3  265.77  4502.4  265.33  4509.7  265.91  4516.6  264.66  4530.8  263.56
  4686.5  257.38  4792.5  255.58  4876.6  256.29  4905.7  257.05  4919.9  256.94
  4927.1  256.16  4941.3  257.04  4948.2  256.37  4969.4  256.24    5007  255.52
  5007.2  255.02  5019.9  256.23  5129.2  263.98  5209.4   267.5  5326.1  270.29
#Mann= 4 ,-1 , 0
    4156     .11       0  4876.6     .15       0  4969.4     .09       0
  5019.9     .11       0
Bank Sta=4969.4,5019.9
XS Rating Curve= 0 ,0
Exp/Cntr=0.3,0.1

Type RM Length L Ch R = 1 ,4076    ,720,720,720
BEGIN DESCRIPTION:
CCLC 127 3.0
END DESCRIPTION:
XS GIS Cut Line= 3
      3722667.81     10151361.09      3722059.65     10151682.99
      3721817.85     10151961.07
#Sta/Elev= 30
  4311.9  274.58  4413.7  269.14    4496  266.43  4518.1  264.16  4540.1  263.83
  4606.1  260.51  4616.7   260.8  4651.3  258.77  4673.9   256.6  4727.1  253.68
  4754.4  253.69  4792.8  252.09  4814.8   252.6  4843.6  252.03  4853.1  252.85
  4941.1  254.54 4960.38252.3879  4963.1  251.71    4967  249.07  4985.1  251.17
  4990.8  250.29    5002  250.75  5007.2  252.44  5013.8  253.98  5056.6  253.02
  5134.4  255.84  5177.2  255.88  5212.3  257.72  5234.2  259.99  5368.5  265.73
#Mann= 4 ,-1 , 0
  4311.9     .17       0  4727.1     .11       0 4960.38     .06       0
  5007.2     .11       0
Bank Sta=4960.38,5007.2
XS Rating Curve= 0 ,0
Exp/Cntr=0.3,0.1

Type RM Length L Ch R = 1 ,3356    ,573,573,573
BEGIN DESCRIPTION:
CCLC 127 2.0
END DESCRIPTION:
XS GIS Cut Line= 3
      3722467.86     10151261.07      3721957.81     10151117.97
      3721651.27      10151777.8
#Sta/Elev= 30
  4480.6  267.49  4536.9  266.05  4594.9   262.4  4654.4  260.31  4688.9  257.84
  4755.8  254.94  4885.7  249.78  4927.2  249.15  4943.1  247.62  4958.4  247.37
  4977.2  248.46  4989.5  247.85  4998.2  244.77  5020.7  246.01  5026.2  247.88
  5035.8  247.47  5049.1  248.52  5163.6  251.55  5186.5  251.61  5214.9  249.72
  5220.9  250.52  5237.8  251.72  5255.1  251.13  5366.6  251.95  5569.3  262.25
    5638  263.36  5643.5  264.34  5683.8  263.79  5712.2  265.53  5737.9  265.88
#Mann= 6 ,-1 , 0
  4480.6     .11       0  4654.4     .17       0  4755.8     .15       0
  4989.5     .09       0  5026.2     .15       0  5220.9     .11       0
Bank Sta=4989.5,5026.2
XS Rating Curve= 0 ,0
Exp/Cntr=0.3,0.1

Type RM Length L Ch R = 1 ,2783    ,809,809,809
BEGIN DESCRIPTION:
Mapping XS 76b0c311
END DESCRIPTION:
XS GIS Cut Line= 3
      3722515.07     10150466.93      3721728.64     10150602.35
      3721593.23     10151805.44
#Sta/Elev= 30
  4136.8  268.33  4604.5  255.03  4628.9  253.55  4692.1  250.41    4753  245.44
  4803.7   245.5    4824  244.35  4839.1  245.37  4854.4  245.09  4884.9  244.52
  4892.1  243.45  4915.3  245.22  4963.7  244.88  4982.7  246.52    5004  245.39
  5044.2  246.74  5114.7  245.89  5252.6  250.69  5265.6  247.19  5295.8  251.35
  5356.2  248.96  5492.8  252.21  5537.3   253.7  5612.6     258  5678.2  259.57
  5718.4  261.98    5769  263.32  5869.4  264.56  5972.5  267.31  6145.5  267.18
#Mann= 6 ,-1 , 0
  4136.8     .11       0  4628.9     .15       0  4854.4     .09       0
  4915.3     .15       0  5492.8     .17       0    5769     .11       0
Bank Sta=4854.4,4915.3
XS Rating Curve= 0 ,0
Exp/Cntr=0.3,0.1

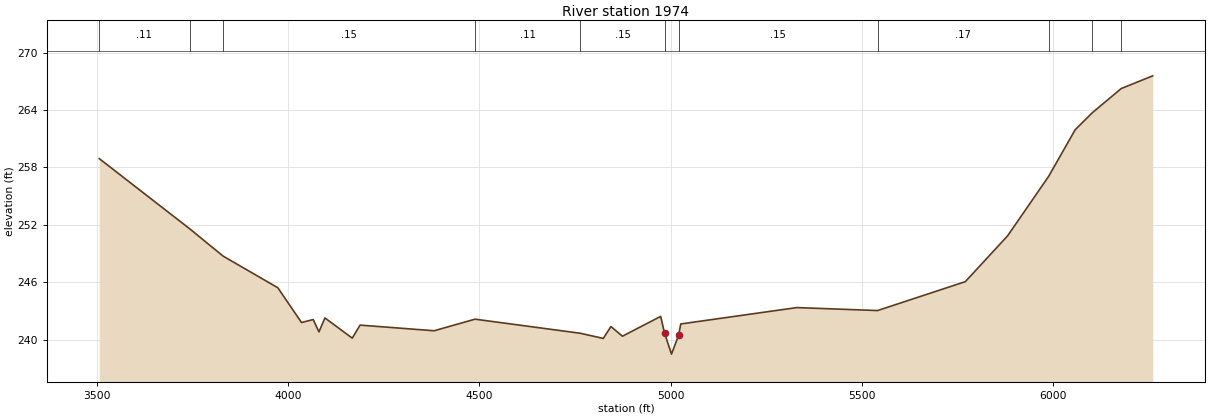
Type RM Length L Ch R = 1 ,1974    ,0,0,0
BEGIN DESCRIPTION:
CCLC 127 1.0
END DESCRIPTION:
XS GIS Cut Line= 4
      3722176.59     10150154.42      3720994.27     10150388.81
      3720989.06     10150690.89      3721567.17     10151795.03
#Sta/Elev= 30
  3506.7  258.93  3742.8  251.61  3830.4  248.75  3973.6  245.44  4035.5  241.81
  4066.1  242.12  4081.1  240.83  4096.7  242.29  4168.1  240.18  4188.6  241.54
  4382.2  240.95    4489  242.16  4764.1  240.69  4824.3  240.15  4844.3  241.39
  4874.3  240.38  4974.3  242.45  4984.3  240.72  5002.6  238.51  5021.2  240.48
  5026.8  241.66  5330.4  243.37  5541.3  243.06  5770.7  246.08  5881.3  250.87
  5988.7  257.09  6057.8  261.94  6102.7  263.72  6178.1  266.24  6260.5  267.57
#Mann= 11 ,-1 , 0
  3506.7     .11       0  3742.8     .17       0  3830.4     .15       0
    4489     .11       0  4764.1     .15       0  4984.3     .09       0
  5021.2     .15       0  5541.3     .17       0  5988.7     .11       0
  6102.7     .17       0  6178.1     .11       0
Bank Sta=4984.3,5021.2
XS Rating Curve= 0 ,0
Exp/Cntr=0.3,0.1

Chan Stop Cuts=-1
Use User Specified Reach Order=0
Composite Channel Slope=5