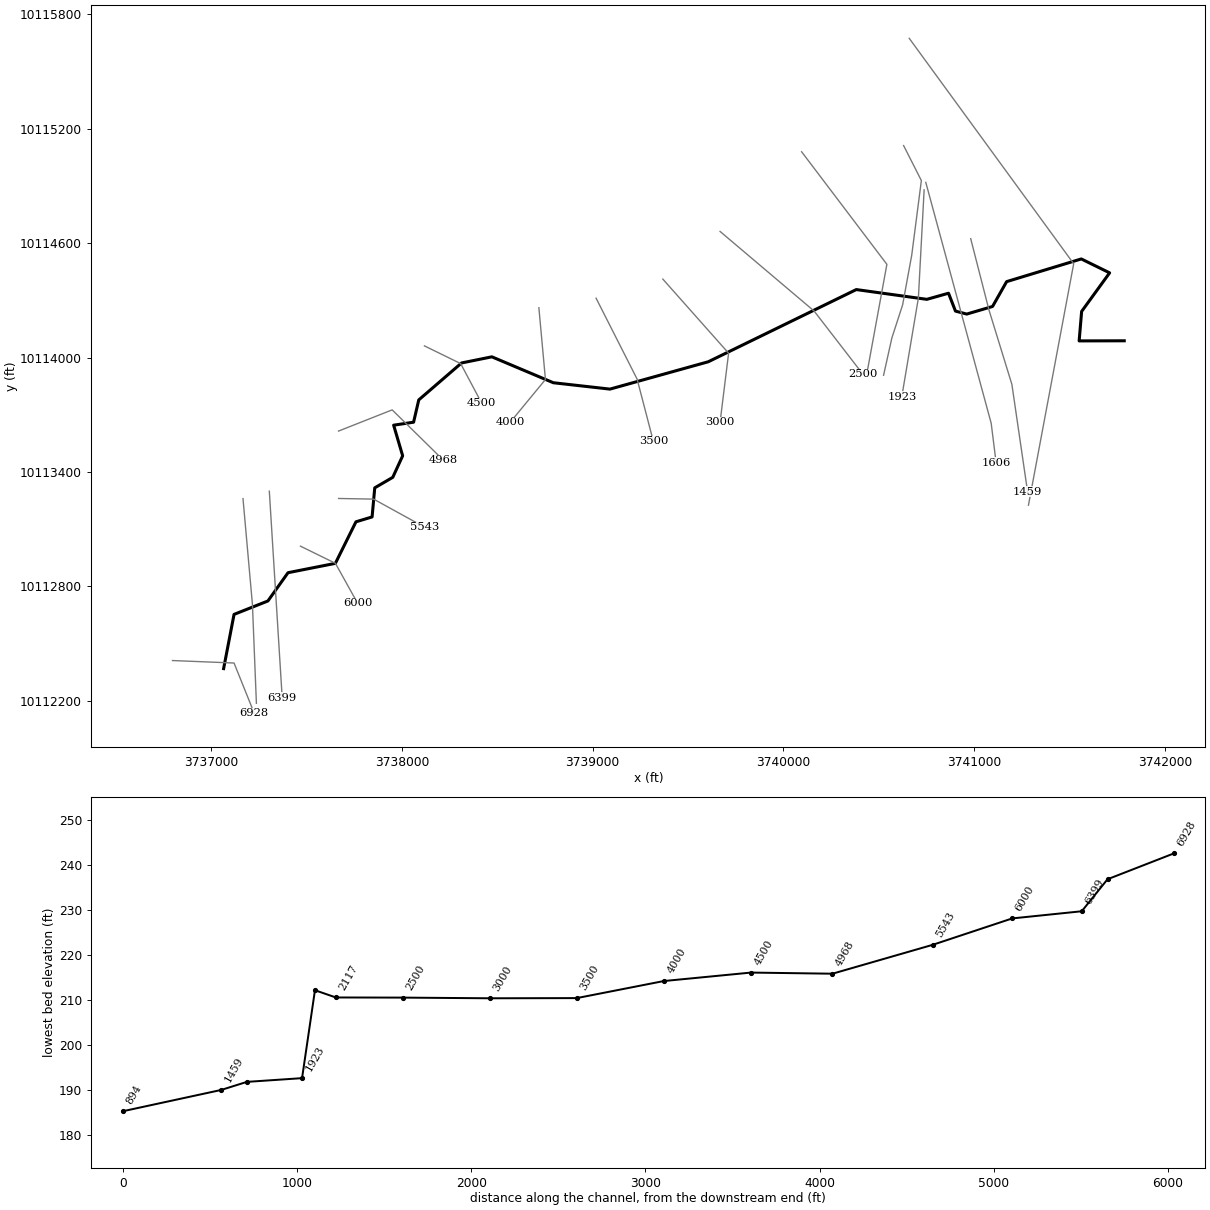
--- CCLC 128.prj (project) ---

Proj Title=CCLC 128 Base Level Engineering
Current Plan=p01
Default Exp/Contr=0.3,0.1
English Units
Geom File=g01
Flow File=f01
Flow File=f02
Plan File=p01
Y Axis Title=Elevation
X Axis Title(PF)=Main Channel Distance
X Axis Title(XS)=Station
BEGIN DESCRIPTION:
CCLC 128
END DESCRIPTION:
DSS Export Rating Curves= 0
DSS Export Rating Curve Sorted= 0
DSS Export Volume Flow Curves= 0
DXF OffsetX= 0
DXF OffsetY= 0
DXF ScaleX= 1
DXF ScaleY= 10

--- CCLC 128.p01 (plan) ---

Plan Title=Multiple Run
Short Identifier=Multiple
Geom File=g01
Flow File=f01
Subcritical Flow
K Sum by GR= 0
Std Step Tol= 0.01
Critical Tol= 0.01
Num of Std Step Trials= 20
Max Error Tol= 0.3
Flow Tol Ratio= 0.001
Split Flow NTrial= 30
Split Flow Tol= 0.02
Split Flow Ratio= 0.02
Log Output Level= 0
Friction Slope Method= 1
Unsteady Friction Slope Method= 2
Unsteady Bridges Friction Slope Method= 1
Parabolic Critical Depth
Global Vel Dist=  1 , 1 , 1
Global Log Level= 0
CheckData=True
Encroach Param= -1, 0, 0, 0
BEGIN DESCRIPTION:
Multiple Run
END DESCRIPTION:

--- CCLC 128.f01 (steady flow) ---

Flow Title=Multiple
Program Version=4.10
Number of Profiles= 7
Profile Names=10-year,25-year,50-year,1pct_min,100-year,1pct_plu,500-year
River Rch & RM=CCLC 128,Reach-1         ,6928
     598     814    1105     494    1492    4506    2812
River Rch & RM=CCLC 128,Reach-1         ,1923
     808    1119    1535     693    2094    6324    4032
Boundary for River Rch & Prof#=CCLC 128,Reach-1         , 1
Up Type= 0
Dn Type= 3
Dn Slope=0.005
Boundary for River Rch & Prof#=CCLC 128,Reach-1         , 2
Up Type= 0
Dn Type= 3
Dn Slope=0.005
Boundary for River Rch & Prof#=CCLC 128,Reach-1         , 3
Up Type= 0
Dn Type= 3
Dn Slope=0.005
Boundary for River Rch & Prof#=CCLC 128,Reach-1         , 4
Up Type= 0
Dn Type= 3
Dn Slope=0.005
Boundary for River Rch & Prof#=CCLC 128,Reach-1         , 5
Up Type= 0
Dn Type= 3
Dn Slope=0.005
Boundary for River Rch & Prof#=CCLC 128,Reach-1         , 6
Up Type= 0
Dn Type= 3
Dn Slope=0.005
Boundary for River Rch & Prof#=CCLC 128,Reach-1         , 7
Up Type= 0
Dn Type= 3
Dn Slope=0.005
DSS Import GetInterval= 0
DSS Import GetPeak= 0
DSS Import FillOption= 0

--- CCLC 128.f02 (steady flow) ---

Flow Title=Orig_BLE_Flows
Program Version=4.10
Number of Profiles= 7
Profile Names=10-year,25-year,50-year,1pct_min,100-year,1pct_plu,500-year
River Rch & RM=CCLC 128,Reach-1         ,6928
     598     798     961     380    1148    3467    1635
River Rch & RM=CCLC 128,Reach-1         ,1923
     808    1097    1335     534    1611    4866    2344
Boundary for River Rch & Prof#=CCLC 128,Reach-1         , 1
Up Type= 0
Dn Type= 3
Dn Slope=0.005
Boundary for River Rch & Prof#=CCLC 128,Reach-1         , 2
Up Type= 0
Dn Type= 3
Dn Slope=0.005
Boundary for River Rch & Prof#=CCLC 128,Reach-1         , 3
Up Type= 0
Dn Type= 3
Dn Slope=0.005
Boundary for River Rch & Prof#=CCLC 128,Reach-1         , 4
Up Type= 0
Dn Type= 3
Dn Slope=0.005
Boundary for River Rch & Prof#=CCLC 128,Reach-1         , 5
Up Type= 0
Dn Type= 3
Dn Slope=0.005
Boundary for River Rch & Prof#=CCLC 128,Reach-1         , 6
Up Type= 0
Dn Type= 3
Dn Slope=0.005
Boundary for River Rch & Prof#=CCLC 128,Reach-1         , 7
Up Type= 0
Dn Type= 3
Dn Slope=0.005
DSS Import GetInterval= 0
DSS Import GetPeak= 0
DSS Import FillOption= 0

--- CCLC 128.g01 (geometry) ---

Geom Title=Existing Conditions
Program Version=4.10

River Reach=CCLC 128        ,Reach-1
Reach XY= 30
      3737064.98     10112369.11      3737119.63     10112653.33
      3737297.19     10112723.66      3737402.63     10112871.93
      3737650.88     10112920.94      3737758.76      10113138.7
       3737843.4     10113164.33      3737857.35     10113316.84
      3737951.74     10113371.92      3738003.69      10113484.8
      3737956.39     10113645.29      3738060.97       10113661.
      3738088.08     10113777.87      3738312.54     10113971.56
      3738471.44     10114003.72      3738793.67     10113867.84
      3739090.51     10113834.47      3739605.99     10113977.85
      3740382.03     10114356.32      3740751.82      10114305.1
      3740865.53     10114337.22      3740901.99     10114243.47
      3740961.02     10114227.85      3741096.44     10114267.78
      3741170.22     10114397.98      3741561.71     10114516.91
      3741710.15     10114443.99      3741563.45     10114241.73
      3741550.43     10114087.22      3741786.91     10114087.77

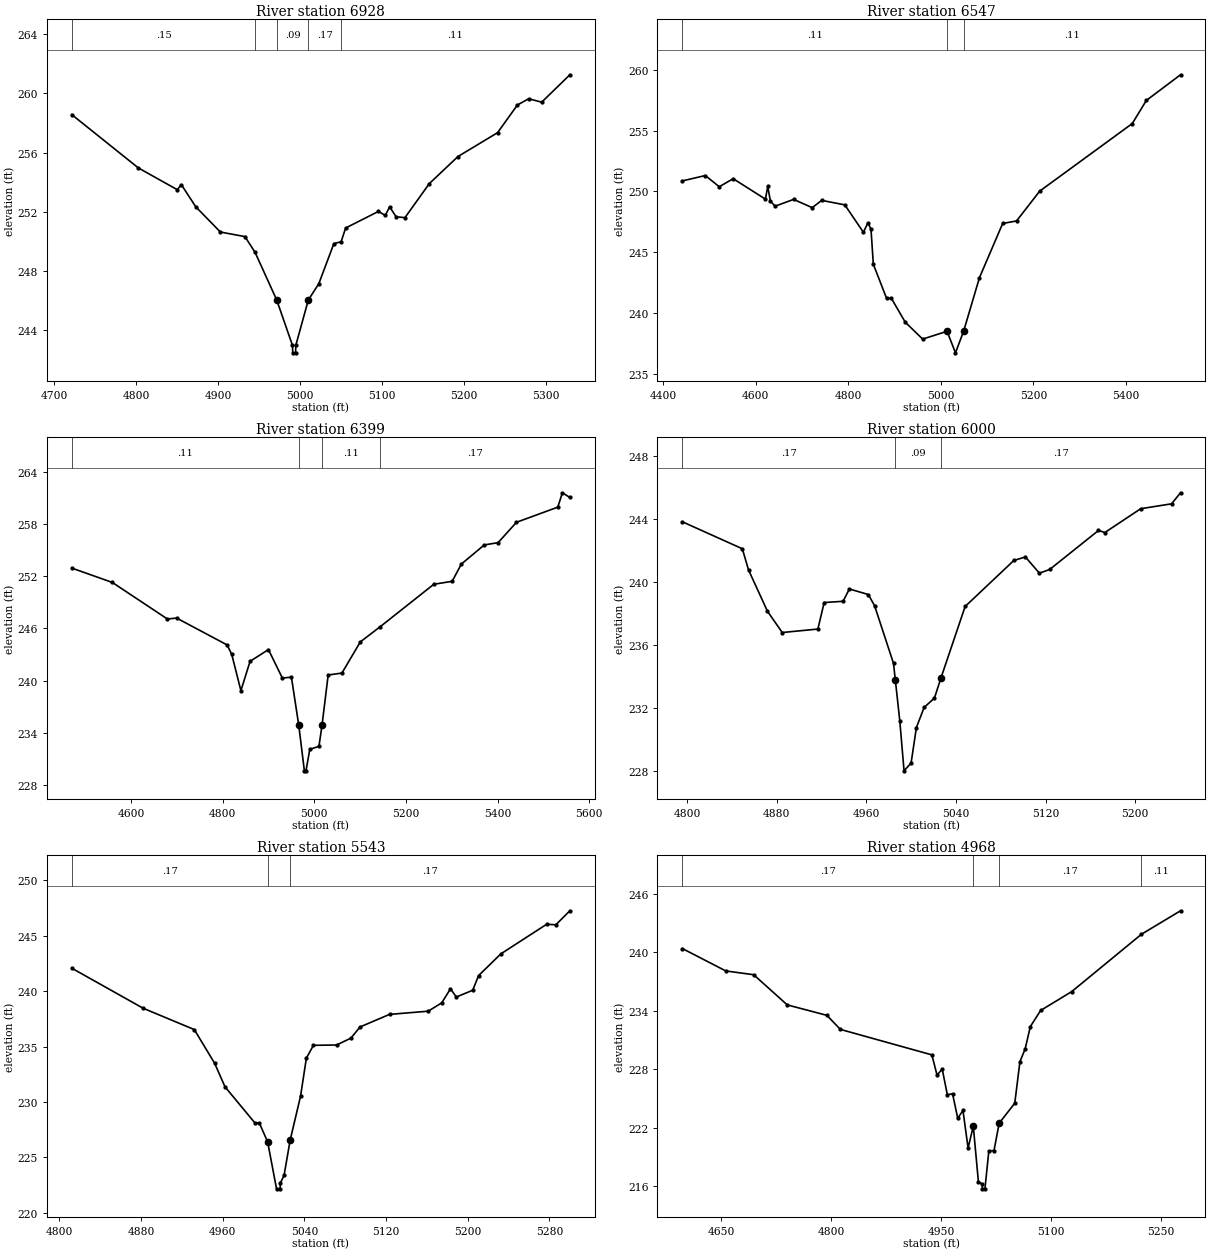
Type RM Length L Ch R = 1 ,6928    ,381,381,381
BEGIN DESCRIPTION:
CCLC 128 14.0
END DESCRIPTION:
XS GIS Cut Line= 3
      3736796.73     10112411.36      3737119.66     10112398.34
      3737225.77     10112134.37
#Sta/Elev= 30
  4721.5  258.57  4802.7  254.97  4850.2   253.5  4855.2  253.84  4872.7  252.35
  4902.8  250.64  4932.8  250.33  4945.2  249.26 4971.53246.0512  4990.8  242.98
  4991.1  242.48  4994.6  242.48  4994.8  242.98 5010.08246.0458  5022.9  247.15
  5041.3  249.86  5050.1  249.98  5055.6  250.91  5095.6  252.03    5104  251.76
  5109.3  252.34  5117.2  251.67    5128  251.61  5157.7  253.91  5192.7  255.74
    5241  257.35  5265.2  259.22  5278.9  259.64  5294.8  259.41  5329.2  261.26
#Mann= 5 ,-1 , 0
  4721.5     .15       0  4945.2     .17       0 4971.53     .09       0
 5010.08     .17       0  5050.1     .11       0
Bank Sta=4971.53,5010.08
XS Rating Curve= 0 ,0
Exp/Cntr=0.3,0.1

Type RM Length L Ch R = 1 ,6547    ,148,148,148
BEGIN DESCRIPTION:
CCLC 128 13.0
END DESCRIPTION:
XS GIS Cut Line= 3
      3737166.54     10113260.34      3737216.02     10112705.63
      3737236.85     10112187.36
#Sta/Elev= 30
  4441.9  250.87  4491.4  251.31  4521.5  250.39  4551.6  251.05  4621.2  249.37
  4626.2  250.42  4631.9  249.22    4642  248.79  4682.1  249.35  4722.3  248.67
  4742.7  249.27  4792.6   248.9  4832.7  246.65  4842.8  247.43  4849.2  246.88
  4854.2  244.02  4882.9  241.21    4893  241.23  4923.1  239.26  4960.7  237.87
  5013.4  238.51  5031.6  236.74 5049.23238.5272  5083.4  242.92  5133.5  247.37
  5163.5  247.58  5213.5  250.03  5413.3  255.58  5443.7  257.48  5517.5  259.59
#Mann= 3 , 0 , 0
  4441.9     .11       0  5013.4     .06       0 5049.23     .11       0
Bank Sta=5013.4,5049.23
XS Rating Curve= 0 ,0
Exp/Cntr=0.3,0.1

Type RM Length L Ch R = 1 ,6399    ,399,399,399
BEGIN DESCRIPTION:
Mapping XS aebf0c3b
END DESCRIPTION:
XS GIS Cut Line= 2
      3737304.56     10113299.37      3737372.19     10112214.77
#Sta/Elev= 30
  4470.8  252.92  4559.3  251.27  4679.5  247.07  4699.5  247.18  4809.8  244.09
  4819.8  243.01  4839.8  238.84  4859.8  242.21  4899.9  243.56  4930.2  240.29
    4950  240.39 4966.02234.8656  4978.3  229.63  4981.8  229.63  4990.1   232.1
  5010.1  232.44  5016.9234.9243  5030.2  240.64  5060.2  240.86  5100.3  244.44
  5142.6  246.14  5260.6  251.06  5300.7   251.4  5320.7  253.38  5370.8  255.58
  5400.9  255.84    5441  258.18  5531.1  259.92  5541.2  261.57  5557.5  261.03
#Mann= 4 ,-1 , 0
  4470.8     .11       0 4966.02     .06       0  5016.9     .11       0
  5142.6     .17       0
Bank Sta=4966.02,5016.9
XS Rating Curve= 0 ,0
Exp/Cntr=0.3,0.1

Type RM Length L Ch R = 1 ,6000    ,457,457,457
BEGIN DESCRIPTION:
CCLC 128 12.0
END DESCRIPTION:
XS GIS Cut Line= 3
      3737467.84     10113011.08      3737651.08     10112921.19
      3737767.86     10112711.06
#Sta/Elev= 30
  4795.9  243.83  4849.4  242.12  4854.9  240.78  4871.8  238.16    4885  236.81
  4916.8  237.03  4922.4  238.71  4939.3  238.79  4944.9  239.57  4961.8  239.22
  4967.4  238.51  4984.3  234.85 4985.91233.8033  4989.9  231.21  4993.7  228.04
    5000  228.54  5004.7  230.78  5011.6  232.06  5020.8  232.65  5026.5   233.9
  5048.2  238.46  5091.7  241.38    5102   241.6  5114.5  240.57  5123.7  240.81
  5167.2  243.28  5172.9  243.15  5204.9  244.66  5232.4  244.97  5240.4  245.67
#Mann= 3 , 0 , 0
  4795.9     .17       0 4985.91     .09       0  5026.5     .17       0
Bank Sta=4985.91,5026.5
XS Rating Curve= 0 ,0
Exp/Cntr=0.3,0.1

Type RM Length L Ch R = 1 ,5543    ,575,575,575
BEGIN DESCRIPTION:
CCLC 128 11.0
END DESCRIPTION:
XS GIS Cut Line= 3
      3737667.84     10113261.07      3737851.43     10113257.71
      3738117.82     10113111.09
#Sta/Elev= 30
  4812.3  242.08  4882.3  238.46  4932.3  236.54  4952.3  233.48  4962.3  231.38
  4991.6  228.12  4995.9  228.12  5004.1   226.4  5012.8  222.17  5016.3  222.17
  5016.5  222.67  5020.2   223.4  5026.1  226.55  5036.3  230.53    5042  233.96
  5048.9  235.12  5071.7  235.15  5085.6  235.77  5094.6  236.78  5123.4  237.91
  5161.3   238.2  5174.5  238.95  5183.1  240.22  5188.8  239.48  5204.9  240.09
  5210.6  241.41  5232.4  243.37  5277.2  246.04  5286.3     246    5300  247.26
#Mann= 3 , 0 , 0
  4812.3     .17       0  5004.1     .09       0  5026.1     .17       0
Bank Sta=5004.1,5026.1
XS Rating Curve= 0 ,0
Exp/Cntr=0.3,0.1

Type RM Length L Ch R = 1 ,4968    ,468,468,468
BEGIN DESCRIPTION:
CCLC 128 10.0
END DESCRIPTION:
XS GIS Cut Line= 3
      3737667.37     10113614.47      3737948.66     10113725.59
      3738217.82     10113461.11
#Sta/Elev= 30
    4597  240.37  4656.2  238.08  4694.3  237.69  4740.1   234.6  4794.2  233.53
  4812.6  232.09  4937.5  229.48  4944.5  227.41  4951.6  228.02  4958.6   225.4
  4965.7   225.5  4972.8  222.98  4979.9  223.79  4986.9  219.94    4994  222.17
    5001  216.47  5006.2  216.26  5006.4  215.76  5009.9  215.76  5015.2  219.64
  5022.3  219.68  5029.3  222.48  5050.6  224.53  5057.6  228.77  5064.8   230.1
  5071.8  232.37  5085.9  234.03  5128.3  235.96  5223.4  241.83  5276.8  244.24
#Mann= 4 ,-1 , 0
    4597     .17       0    4994     .09       0  5029.3     .17       0
  5223.4     .11       0
Bank Sta=4994,5029.3
XS Rating Curve= 0 ,0
Exp/Cntr=0.3,0.1

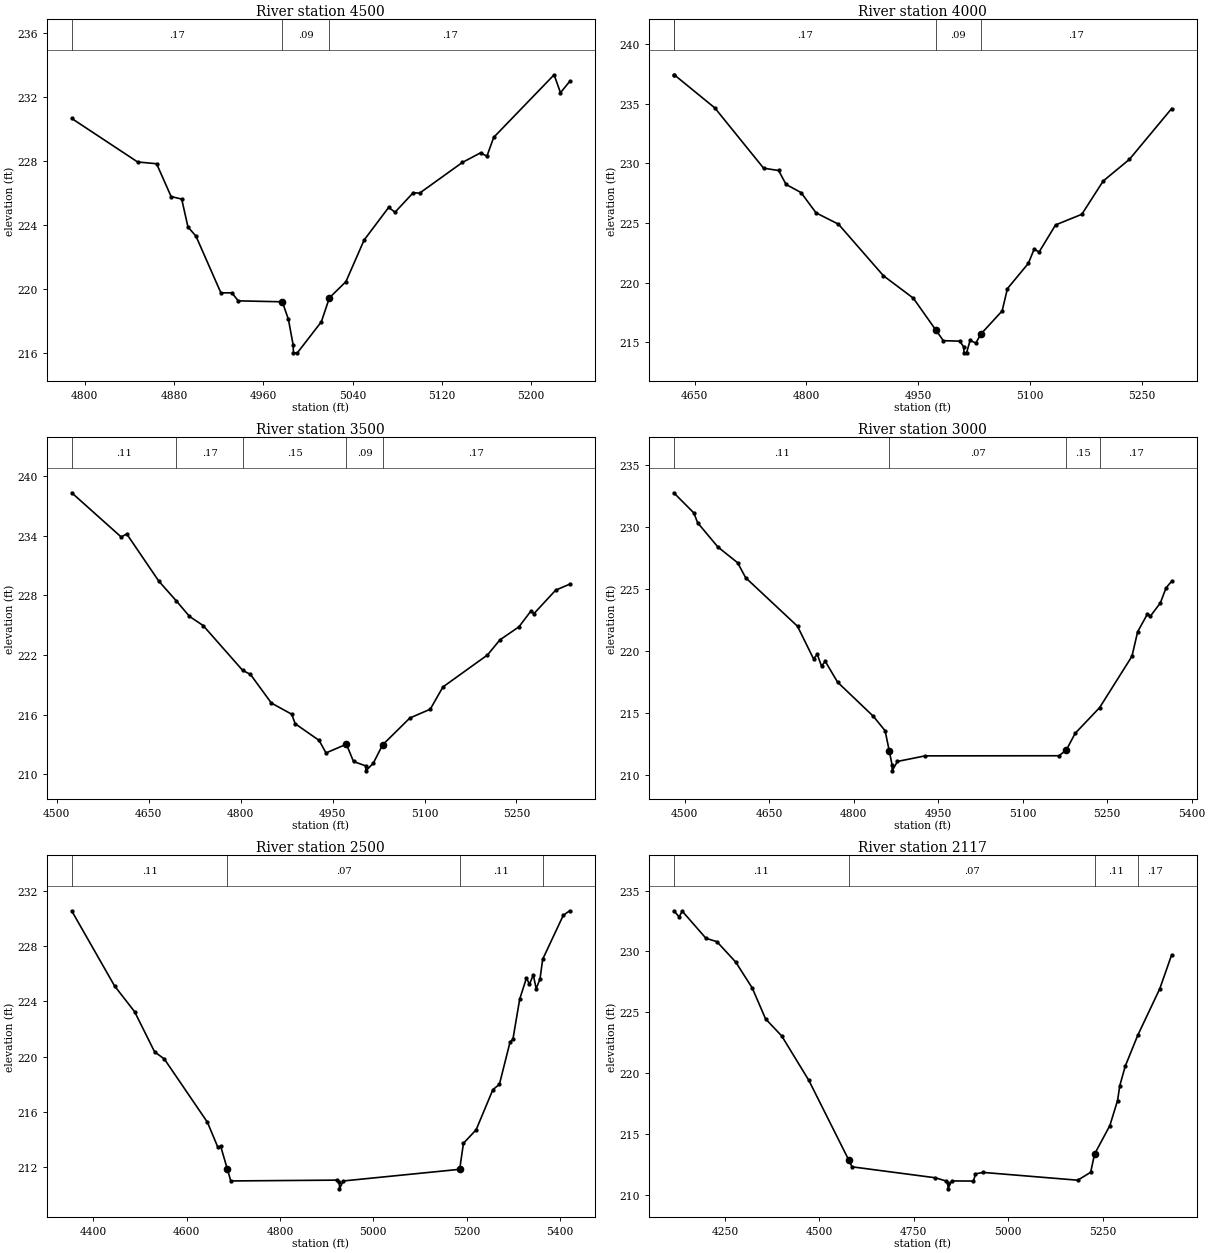
Type RM Length L Ch R = 1 ,4500    ,500,500,500
BEGIN DESCRIPTION:
CCLC 128 9.0
END DESCRIPTION:
XS GIS Cut Line= 3
      3738117.88     10114061.06      3738307.88     10113968.15
      3738417.87     10113761.04
#Sta/Elev= 30
  4788.5  230.66  4847.5  227.94  4864.5  227.83  4877.5  225.78    4887  225.62
  4892.6  223.88  4899.8   223.3  4922.1  219.76    4932  219.76  4937.6  219.26
  4977.1   219.2  4982.6   218.1  4986.8  216.51  4987.1  216.01  4990.6  216.01
  5012.1  217.95  5019.3  219.45  5034.1  220.46  5050.4  223.06  5072.4   225.1
  5078.1   224.8  5094.4  226.02  5100.1  225.99  5138.4  227.91  5154.7  228.51
  5160.4   228.3  5166.5  229.48  5220.6  233.39  5226.3  232.27  5234.5  232.97
#Mann= 3 , 0 , 0
  4788.5     .17       0  4977.1     .09       0  5019.3     .17       0
Bank Sta=4977.1,5019.3
XS Rating Curve= 0 ,0
Exp/Cntr=0.3,0.1

Type RM Length L Ch R = 1 ,4000    ,500,500,500
BEGIN DESCRIPTION:
CCLC 128 8.0
END DESCRIPTION:
XS GIS Cut Line= 3
      3738717.85     10114261.07      3738752.26     10113884.74
      3738567.84     10113661.06
#Sta/Elev= 30
  4622.1  237.43  4622.7  237.43  4677.2  234.65  4742.6   229.6  4762.7  229.41
  4772.7  228.24  4792.8  227.56  4812.9  225.86    4843  224.91  4903.3  220.59
  4943.4  218.71  4973.6  216.04  4983.6  215.15  5005.6  215.11    5011  214.63
  5011.3  214.13  5014.8  214.13  5019.5  215.17  5027.3  214.95  5033.8  215.69
  5062.5  217.64  5069.6  219.51  5097.7  221.63  5105.5  222.83    5112  222.57
  5134.2  224.85  5169.4  225.74  5198.1  228.53  5233.2  230.34  5289.9   234.6
#Mann= 4 ,-1 , 0
  4622.1     .11       0  4622.7     .17       0  4973.6     .09       0
  5033.8     .17       0
Bank Sta=4973.6,5033.8
XS Rating Curve= 0 ,0
Exp/Cntr=0.3,0.1

Type RM Length L Ch R = 1 ,3500    ,500,500,500
BEGIN DESCRIPTION:
CCLC 128 7.0
END DESCRIPTION:
XS GIS Cut Line= 3
      3739017.85     10114311.07      3739232.91     10113886.87
      3739317.86     10113561.06
#Sta/Elev= 30
  4524.4  238.32  4605.1  233.87  4614.1  234.18  4666.3  229.44  4695.3  227.42
  4716.5  225.88  4738.8  224.96  4803.4  220.44  4815.9  220.05  4850.1  217.16
  4883.2  216.04    4889  215.08    4928   213.4  4939.2  212.14  4972.5  213.02
  4984.1  211.28    5004  210.84  5004.2  210.34  5016.3   211.1  5031.5212.9472
  5076.1  215.66  5109.3  216.54    5130  218.78  5202.7     222    5223  223.52
    5254  224.83  5273.4  226.41  5278.5  226.16  5313.9  228.52  5336.7  229.12
#Mann= 5 ,-1 , 0
  4524.4     .11       0  4695.3     .17       0  4803.4     .15       0
  4972.5     .09       0  5031.5     .17       0
Bank Sta=4972.5,5031.5
XS Rating Curve= 0 ,0
Exp/Cntr=0.3,0.1

Type RM Length L Ch R = 1 ,3000    ,500,500,500
BEGIN DESCRIPTION:
CCLC 128 6.0
END DESCRIPTION:
XS GIS Cut Line= 3
      3739367.82      10114411.1      3739712.58     10114022.75
      3739667.86     10113661.11
#Sta/Elev= 30
  4480.7  232.78  4516.3  231.15    4523  230.36  4558.9   228.4  4594.1  227.12
  4608.3  225.91  4700.3  221.99  4728.7  219.36  4735.4  219.71  4742.9  218.77
  4749.6  219.15  4771.4  217.47  4834.9  214.71  4855.8  213.54  4863.3  211.88
    4868   210.8  4868.3   210.3  4877.6  211.06  4926.9  211.51  5164.3  211.52
 5177.13211.9634  5193.1  213.33  5236.5  215.41  5293.9  219.56    5304  221.54
  5321.4  222.98  5326.4  222.79  5344.3  223.87  5354.4  225.09  5364.4  225.63
#Mann= 4 ,-1 , 0
  4480.7     .11       0  4863.3     .07       0 5177.13     .15       0
  5236.5     .17       0
Bank Sta=4863.3,5177.13
XS Rating Curve= 0 ,0
Exp/Cntr=0.3,0.1

Type RM Length L Ch R = 1 ,2500    ,383,383,383
BEGIN DESCRIPTION:
CCLC 128 5.0
END DESCRIPTION:
XS GIS Cut Line= 3
      3739667.86     10114661.07      3740160.86     10114243.78
      3740417.85     10113911.07
#Sta/Elev= 30
  4354.1  230.53  4445.8  225.11  4488.7  223.25  4531.5  220.35  4552.4  219.83
  4644.7  215.26  4666.7  213.48  4673.2  213.51  4687.5  211.86  4694.7  211.02
  4921.5  211.08  4927.3  210.95  4927.5  210.45  4935.8  211.02  5184.9  211.86
    5193  213.74  5220.2  214.72  5256.1  217.62    5270     218  5292.7  221.04
    5299  221.27  5313.5  224.16    5328  225.69  5334.3  225.22  5342.5  225.91
  5348.8  224.91    5357  225.62  5362.7  227.04  5406.8  230.21  5420.4  230.54
#Mann= 4 ,-1 , 0
  4354.1     .11       0  4687.5     .07       0  5184.9     .11       0
  5362.7     .17       0
Bank Sta=4687.5,5184.9
XS Rating Curve= 0 ,0
Exp/Cntr=0.3,0.1

Type RM Length L Ch R = 1 ,2117    ,120,120,120
BEGIN DESCRIPTION:
CCLC 128 4.0
END DESCRIPTION:
XS GIS Cut Line= 3
      3740095.33     10115078.93      3740542.41     10114488.62
      3740438.25     10113920.08
#Sta/Elev= 30
  4114.3  233.34  4128.6  232.84  4136.7  233.31  4199.4  231.08  4228.5   230.8
  4278.4  229.12  4322.1  226.99  4357.4  224.45  4400.1  223.05  4471.9   219.4
    4578  212.83  4586.3  212.29  4806.8  211.39  4835.9  211.12  4840.2  210.98
  4840.5  210.48  4850.1  211.13    4908  211.12  4913.3  211.71  4933.6  211.83
    5184  211.19  5218.3  211.84  5228.5  213.33  5269.1  215.68  5289.5  217.74
  5295.4  218.96  5309.8  220.56  5342.8  223.09  5401.3  226.93  5432.8  229.72
#Mann= 4 ,-1 , 0
  4114.3     .11       0    4578     .07       0  5228.5     .11       0
  5342.8     .17       0
Bank Sta=4578,5228.5
XS Rating Curve= 0 ,0
Exp/Cntr=0.3,0.1

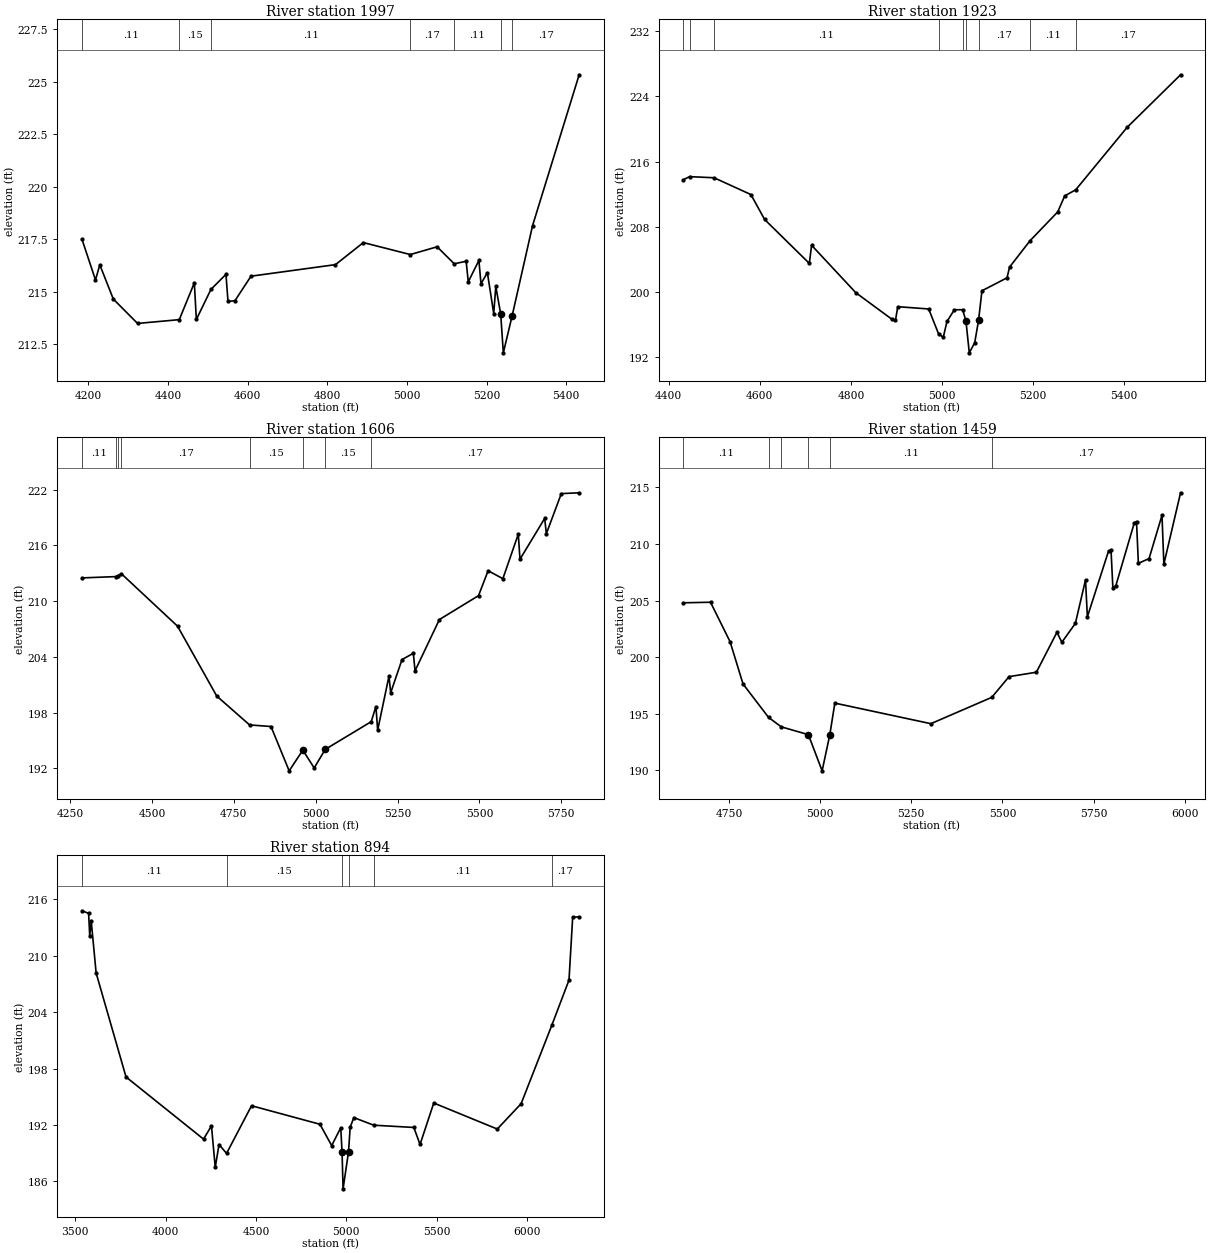
Type RM Length L Ch R = 1 ,1997    ,74,74,74
BEGIN DESCRIPTION:
Mapping XS a6cb2c74
END DESCRIPTION:
XS GIS Cut Line= 6
      3740630.13     10115111.26      3740723.15     10114927.97
      3740672.62     10114536.36      3740624.87     10114275.94
      3740568.45     10114102.33      3740525.04       10113907.
#Sta/Elev= 30
  4184.5   217.5  4218.4  215.56  4229.3  216.28  4263.2  214.65    4324  213.49
  4428.7  213.67  4466.5  215.42  4471.6  213.68  4508.2  215.11  4545.9  215.83
    4551  214.54  4568.4  214.57  4608.7  215.74  4820.8  216.29  4890.7  217.34
  5008.6  216.77  5075.8  217.14  5118.8  216.33  5148.7  216.45    5154  215.47
  5180.7  216.49  5185.9  215.38    5202  215.91  5217.9  213.96  5223.1  215.25
  5235.4  213.94    5242  212.09  5264.2  213.86  5315.4  218.15  5432.3  225.33
#Mann= 7 ,-1 , 0
  4184.5     .11       0  4428.7     .15       0  4508.2     .11       0
  5008.6     .17       0  5118.8     .11       0  5235.4     .06       0
  5264.2     .17       0
Bank Sta=5235.4,5264.2
XS Rating Curve= 0 ,0
Exp/Cntr=0.3,0.1

Type RM Length L Ch R = 1 ,1923    ,317,317,317
BEGIN DESCRIPTION:
CCLC 128 3.0
END DESCRIPTION:
XS GIS Cut Line= 3
      3740737.72     10114879.25      3740707.55     10114312.05
      3740620.69     10113795.09
#Sta/Elev= 30
    4432  213.79  4445.7  214.17  4499.5  214.03  4580.4  211.97  4610.4  208.92
  4708.7  203.53  4713.7  205.75  4810.7  199.94  4890.8  196.65    4898  196.57
    4903  198.22  4970.9  197.94  4992.8  194.86    5003  194.48  5011.1  196.41
  5027.3  197.84  5045.6  197.85 5052.82196.4381  5060.1  192.56    5072   193.8
 5080.43196.5294  5087.9  200.17    5143  201.76  5148.5  203.07  5193.4   206.3
  5254.5  209.85  5269.7  211.81  5293.8  212.55  5406.6   220.2  5524.2  226.66
#Mann= 9 ,-1 , 0
    4432     .11       0  4445.7     .15       0  4499.5     .11       0
  4992.8     .15       0  5045.6     .17       0 5052.82     .09       0
 5080.43     .17       0  5193.4     .11       0  5293.8     .17       0
Bank Sta=5052.82,5080.43
XS Rating Curve= 0 ,0
Exp/Cntr=0.3,0.1

Type RM Length L Ch R = 1 ,1606    ,147,147,147
BEGIN DESCRIPTION:
Mapping XS 108e7b63
END DESCRIPTION:
XS GIS Cut Line= 3
       3740746.4     10114918.32      3741089.28     10113655.28
      3741115.32     10113446.96
#Sta/Elev= 30
    4286  212.49  4389.1  212.63  4394.7  212.72  4406.7  212.93  4578.1  207.29
  4697.6  199.78    4798  196.67  4863.4   196.5  4918.9  191.73  4960.7  193.96
  4995.3  192.04  5029.2  194.04  5169.5  197.02    5184  198.65  5189.2   196.1
  5223.8  201.92    5229  200.13  5263.6   203.7  5298.2  204.38  5303.4  202.49
  5377.8  208.01  5497.3  210.58  5526.6  213.26  5571.7  212.41  5618.8   217.2
  5623.9   214.5  5699.4  218.89  5704.5  217.25  5750.2  221.56  5804.7  221.65
#Mann= 8 ,-1 , 0
    4286     .11       0  4389.1     .15       0  4394.7     .11       0
  4406.7     .17       0    4798     .15       0  4960.7     .09       0
  5029.2     .15       0  5169.5     .17       0
Bank Sta=4960.7,5029.2
XS Rating Curve= 0 ,0
Exp/Cntr=0.3,0.1

Type RM Length L Ch R = 1 ,1459    ,565,565,565
BEGIN DESCRIPTION:
CCLC 128 2.0
END DESCRIPTION:
XS GIS Cut Line= 4
      3740981.83     10114623.21      3741077.61     10114249.56
      3741197.79     10113859.28      3741280.18     10113295.56
#Sta/Elev= 30
  4624.9   204.8  4699.4  204.85    4753  201.36  4788.6  197.62  4858.7  194.66
  4893.5  193.83  4967.8  193.14  5005.5  189.94  5026.6  193.13  5040.4  195.93
  5303.8  194.11  5470.9  196.44  5518.2  198.27  5593.2  198.66  5649.6  202.19
  5663.1  201.31  5700.2  202.98    5728  206.83  5733.1  203.56  5791.1  209.37
    5798  209.46    5803  206.13  5811.3  206.33  5861.9  211.88  5867.9  211.99
    5873  208.29  5902.3  208.71  5937.8  212.54  5942.9  208.22  5988.7  214.53
#Mann= 6 ,-1 , 0
  4624.9     .11       0  4858.7     .15       0  4893.5     .11       0
  4967.8     .06       0  5026.6     .11       0  5470.9     .17       0
Bank Sta=4967.8,5026.6
XS Rating Curve= 0 ,0
Exp/Cntr=0.3,0.1

Type RM Length L Ch R = 1 ,894     ,0,0,0
BEGIN DESCRIPTION:
CCLC 128 1.0
END DESCRIPTION:
XS GIS Cut Line= 3
      3740659.57     10115673.54      3741521.78     10114491.73
      3741284.64     10113225.85
#Sta/Elev= 30
  3537.1  214.79  3573.9  214.52    3580  212.15  3588.5  213.66  3615.6  208.16
  3780.9  197.11  4209.6   190.5  4253.6  191.91  4274.5  187.49  4295.3  189.92
  4337.2  188.98  4475.3  194.05  4853.8  192.08  4918.7  189.81  4968.9  191.71
  4976.1  189.12  4981.8  185.21  5011.9189.1456    5021  191.77  5041.4  192.79
  5151.3  191.98  5373.2  191.74  5407.6  189.93  5483.5  194.34  5834.9  191.57
  5966.9  194.27  6136.6  202.61  6231.7  207.42  6252.1   214.1  6287.9  214.15
#Mann= 6 ,-1 , 0
  3537.1     .11       0  4337.2     .15       0  4976.1     .12       0
  5011.9     .15       0  5151.3     .11       0  6136.6     .17       0
Bank Sta=4976.1,5011.9
XS Rating Curve= 0 ,0
Exp/Cntr=0.3,0.1

Chan Stop Cuts=-1
Use User Specified Reach Order=0
Composite Channel Slope=5