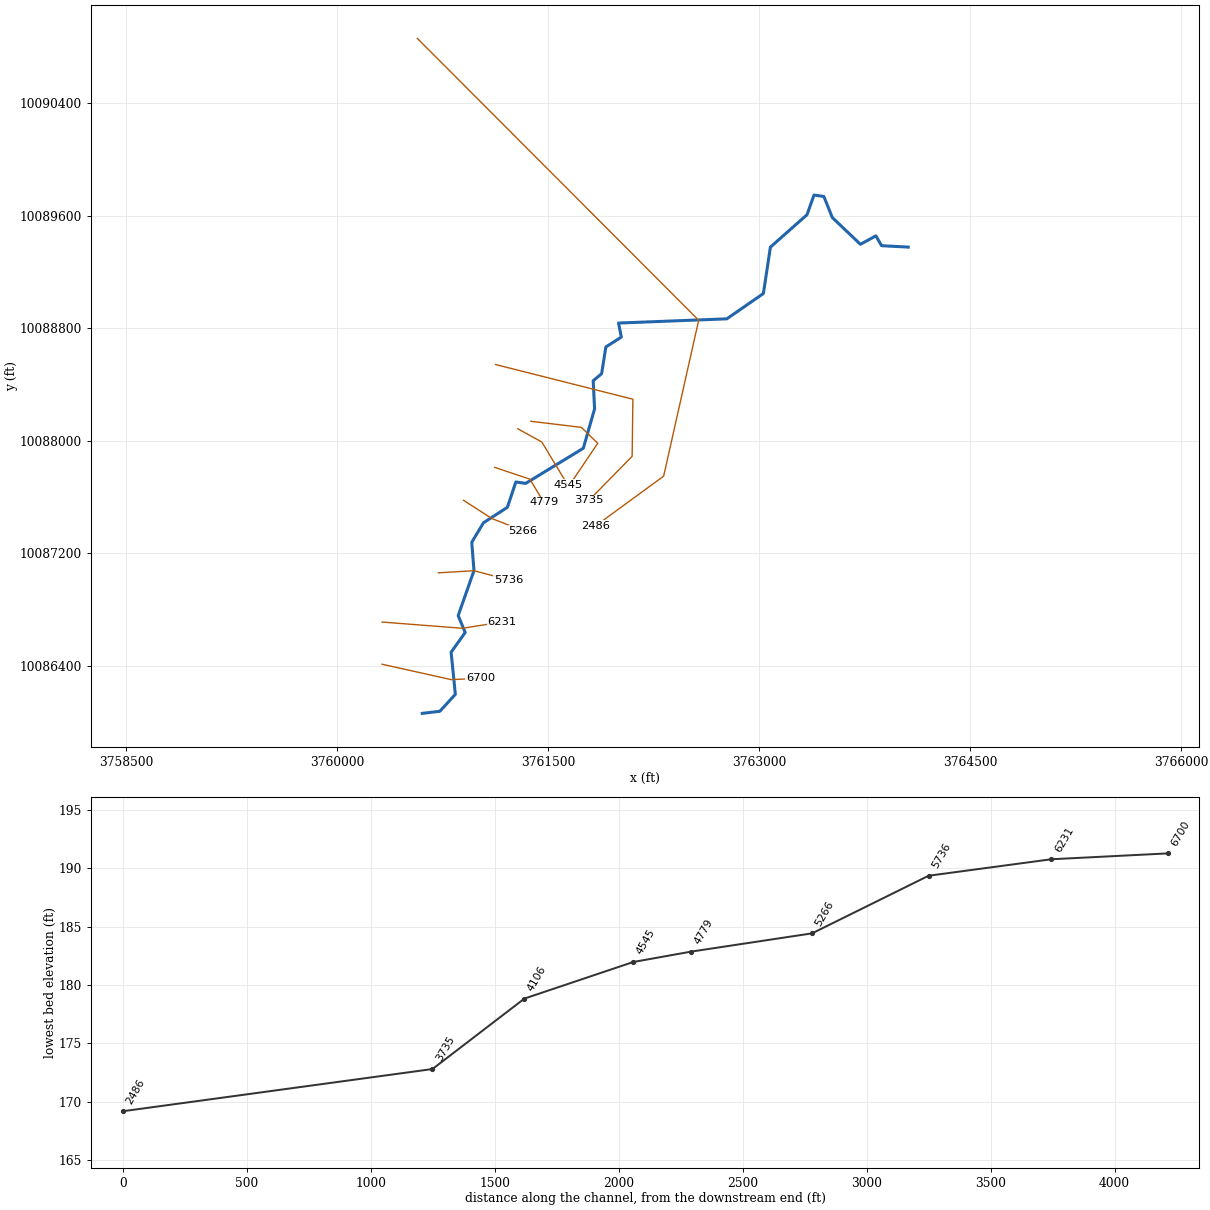
--- CCLC 135.prj (project) ---

Proj Title=CCLC 135 Base Level Engineering
Current Plan=p01
Default Exp/Contr=0.3,0.1
English Units
Geom File=g01
Flow File=f01
Flow File=f02
Plan File=p01
Y Axis Title=Elevation
X Axis Title(PF)=Main Channel Distance
X Axis Title(XS)=Station
BEGIN DESCRIPTION:
CCLC 135
END DESCRIPTION:
DSS Export Rating Curves= 0
DSS Export Rating Curve Sorted= 0
DSS Export Volume Flow Curves= 0
DXF OffsetX= 0
DXF OffsetY= 0
DXF ScaleX= 1
DXF ScaleY= 10

--- CCLC 135.p01 (plan) ---

Plan Title=Multiple Run
Short Identifier=Multiple
Geom File=g01
Flow File=f01
Subcritical Flow
K Sum by GR= 0
Std Step Tol= 0.01
Critical Tol= 0.01
Num of Std Step Trials= 20
Max Error Tol= 0.3
Flow Tol Ratio= 0.001
Split Flow NTrial= 30
Split Flow Tol= 0.02
Split Flow Ratio= 0.02
Log Output Level= 0
Friction Slope Method= 1
Unsteady Friction Slope Method= 2
Unsteady Bridges Friction Slope Method= 1
Parabolic Critical Depth
Global Vel Dist=  1 , 1 , 1
Global Log Level= 0
CheckData=True
Encroach Param= -1, 0, 0, 0
BEGIN DESCRIPTION:
Multiple Run
END DESCRIPTION:

--- CCLC 135.f01 (steady flow) ---

Flow Title=Multiple
Program Version=4.10
Number of Profiles= 7
Profile Names=10-year,25-year,50-year,1pct_min,100-year,1pct_plu,500-year
River Rch & RM=CCLC 135,Reach-1         ,6700
     741    1010    1372     613    1850    5587    3481
River Rch & RM=CCLC 135,Reach-1         ,2486
    1045    1449    1990     897    2709    8181    5194
Boundary for River Rch & Prof#=CCLC 135,Reach-1         , 1
Up Type= 0
Dn Type= 3
Dn Slope=0.005
Boundary for River Rch & Prof#=CCLC 135,Reach-1         , 2
Up Type= 0
Dn Type= 3
Dn Slope=0.005
Boundary for River Rch & Prof#=CCLC 135,Reach-1         , 3
Up Type= 0
Dn Type= 3
Dn Slope=0.005
Boundary for River Rch & Prof#=CCLC 135,Reach-1         , 4
Up Type= 0
Dn Type= 3
Dn Slope=0.005
Boundary for River Rch & Prof#=CCLC 135,Reach-1         , 5
Up Type= 0
Dn Type= 3
Dn Slope=0.005
Boundary for River Rch & Prof#=CCLC 135,Reach-1         , 6
Up Type= 0
Dn Type= 3
Dn Slope=0.005
Boundary for River Rch & Prof#=CCLC 135,Reach-1         , 7
Up Type= 0
Dn Type= 3
Dn Slope=0.005
DSS Import GetInterval= 0
DSS Import GetPeak= 0
DSS Import FillOption= 0

--- CCLC 135.f02 (steady flow) ---

Flow Title=Orig_BLE_Flows
Program Version=4.10
Number of Profiles= 7
Profile Names=10-year,25-year,50-year,1pct_min,100-year,1pct_plu,500-year
River Rch & RM=CCLC 135,Reach-1         ,6700
     741     990    1193     471    1423    4299    2024
River Rch & RM=CCLC 135,Reach-1         ,2486
    1045    1421    1730     690    2084    6293    3020
Boundary for River Rch & Prof#=CCLC 135,Reach-1         , 1
Up Type= 0
Dn Type= 3
Dn Slope=0.005
Boundary for River Rch & Prof#=CCLC 135,Reach-1         , 2
Up Type= 0
Dn Type= 3
Dn Slope=0.005
Boundary for River Rch & Prof#=CCLC 135,Reach-1         , 3
Up Type= 0
Dn Type= 3
Dn Slope=0.005
Boundary for River Rch & Prof#=CCLC 135,Reach-1         , 4
Up Type= 0
Dn Type= 3
Dn Slope=0.005
Boundary for River Rch & Prof#=CCLC 135,Reach-1         , 5
Up Type= 0
Dn Type= 3
Dn Slope=0.005
Boundary for River Rch & Prof#=CCLC 135,Reach-1         , 6
Up Type= 0
Dn Type= 3
Dn Slope=0.005
Boundary for River Rch & Prof#=CCLC 135,Reach-1         , 7
Up Type= 0
Dn Type= 3
Dn Slope=0.005
DSS Import GetInterval= 0
DSS Import GetPeak= 0
DSS Import FillOption= 0

--- CCLC 135.g01 (geometry) ---

Geom Title=Existing Conditions
Program Version=4.10

River Reach=CCLC 135        ,Reach-1
Reach XY= 30
      3760603.23     10086061.84      3760728.23     10086076.84
      3760838.23     10086196.84      3760808.23     10086496.84
      3760908.23     10086636.84      3760858.23     10086756.84
      3760970.58     10087076.17      3760955.09     10087278.91
      3761038.23     10087416.84      3761208.23     10087526.84
      3761268.23     10087706.84      3761338.23     10087696.84
      3761748.23     10087946.84      3761828.23     10088226.84
      3761818.23     10088426.84      3761878.23     10088476.84
      3761908.23     10088666.84      3762018.23     10088736.84
      3761998.23     10088836.84      3762768.23     10088866.84
      3763028.23     10089046.84      3763078.23     10089376.84
      3763338.23     10089606.84      3763388.23     10089746.84
      3763458.23     10089736.84      3763518.23     10089586.84
      3763718.23     10089396.84      3763828.23     10089456.84
      3763868.23     10089386.84      3764058.23     10089376.84

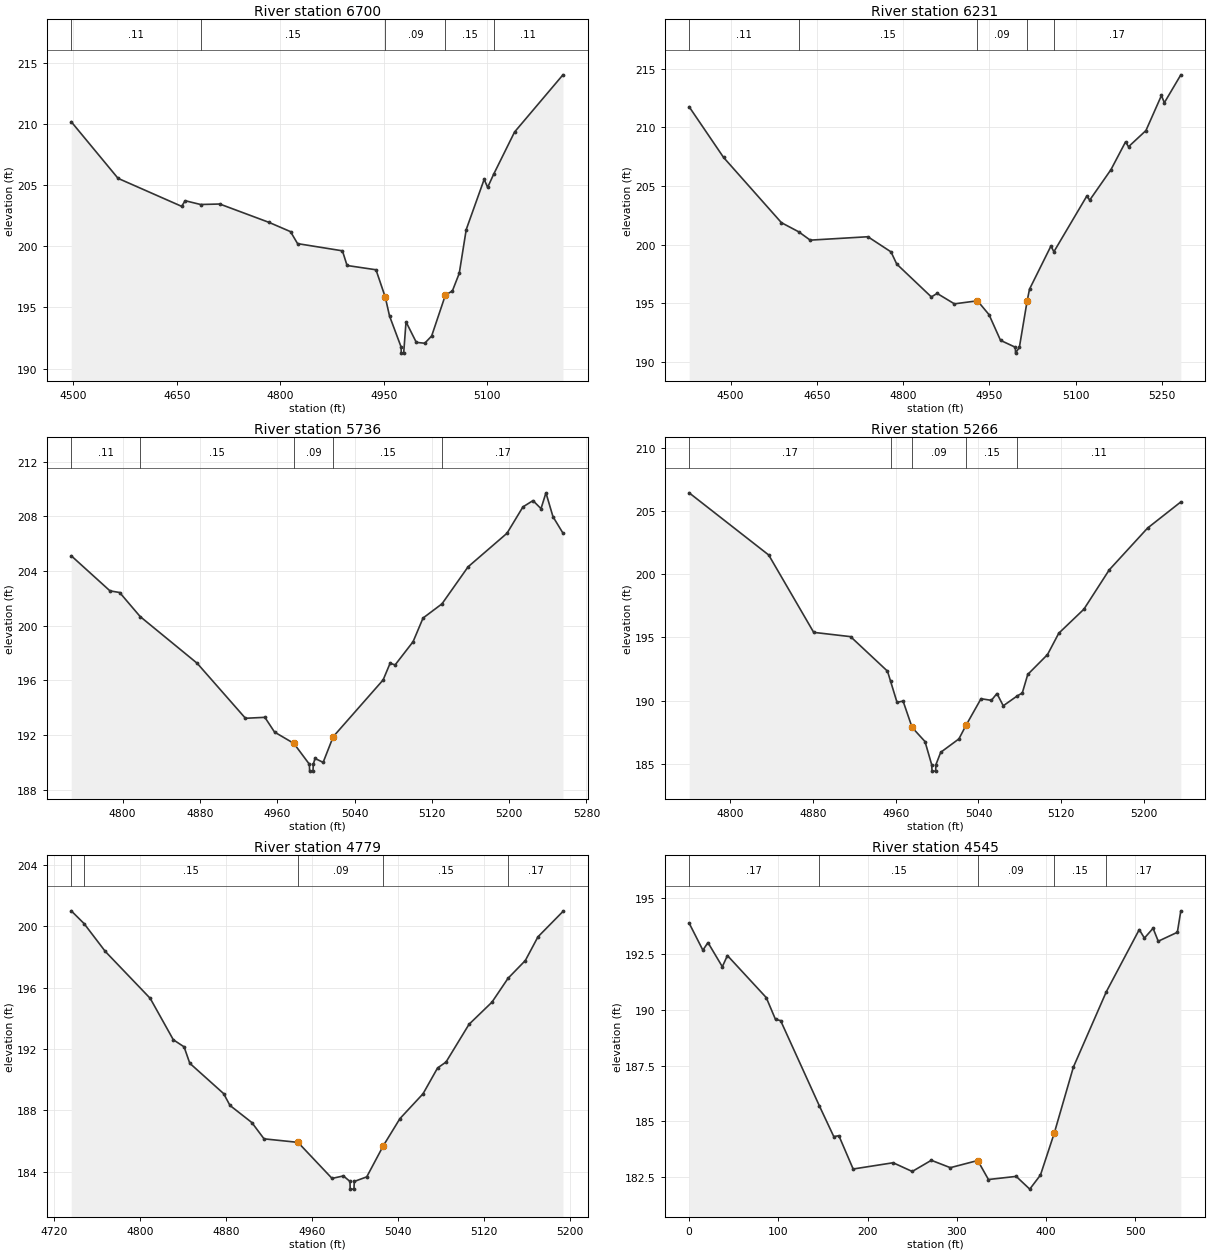
Type RM Length L Ch R = 1 ,6700    ,469,469,469
BEGIN DESCRIPTION:
CCLC 135 7.0
END DESCRIPTION:
XS GIS Cut Line= 3
      3760317.88     10086411.07      3760808.67     10086301.81
      3761017.86     10086311.07
#Sta/Elev= 30
  4497.2  210.19    4565  205.56  4657.1  203.27  4662.2  203.73  4684.6  203.42
  4712.3  203.46    4784  201.95  4814.8   201.2    4825  200.22    4890  199.63
  4896.7  198.43  4938.6  198.08 4952.08 195.833  4958.2   194.3    4975  191.76
  4975.2  191.26  4978.7  191.26  4982.1  193.82    4997  192.14  5009.2  192.07
  5019.2  192.66  5039.2  196.02  5049.2  196.34  5059.2  197.79  5069.3  201.37
  5095.3  205.48  5100.3  204.82  5108.9  205.88  5139.3  209.35  5209.4  214.03
#Mann= 5 ,-1 , 0
  4497.2     .11       0  4684.6     .15       0 4952.08     .09       0
  5039.2     .15       0  5108.9     .11       0
Bank Sta=4952.08,5039.2
XS Rating Curve= 0 ,0
Exp/Cntr=0.3,0.1

Type RM Length L Ch R = 1 ,6231    ,495,495,495
BEGIN DESCRIPTION:
CCLC 135 6.0
END DESCRIPTION:
XS GIS Cut Line= 3
      3760317.84     10086711.07      3760888.23     10086666.84
      3761167.85     10086711.07
#Sta/Elev= 30
  4427.9  211.76  4487.8  207.44  4588.4  201.88  4618.5   201.1  4638.5  200.39
  4738.8  200.68    4779  199.39    4789  198.35  4849.2  195.55  4859.2  195.85
  4889.3  194.96  4929.4  195.22  4949.5  194.04  4969.5  191.85  4995.3  191.26
  4995.6  190.76  5002.3  191.26 5015.72195.1855  5019.9  196.21  5057.2  199.89
  5062.3   199.4  5119.6  204.15  5124.6   203.8  5161.6   206.4    5187  208.77
  5192.1  208.35  5222.4  209.73  5249.4  212.72  5254.4   212.1  5283.1  214.48
#Mann= 5 ,-1 , 0
  4427.9     .11       0  4618.5     .15       0  4929.4     .09       0
 5015.72     .15       0  5062.3     .17       0
Bank Sta=4929.4,5015.72
XS Rating Curve= 0 ,0
Exp/Cntr=0.3,0.1

Type RM Length L Ch R = 1 ,5736    ,470,470,470
BEGIN DESCRIPTION:
CCLC 135 5.0
END DESCRIPTION:
XS GIS Cut Line= 3
      3760717.83     10087061.07      3760970.58     10087076.17
      3761217.85     10087011.07
#Sta/Elev= 30
  4746.8  205.12  4786.9  202.55  4796.9  202.43  4818.1  200.67  4877.1  197.25
  4927.1  193.22  4947.2  193.29  4957.2  192.21  4977.2  191.38  4993.3  189.85
  4993.5  189.35    4997  189.35  4997.3  189.85  4999.1  190.28  5007.5  189.99
  5017.9  191.87  5069.6  196.03  5076.8  197.25    5082  197.13  5100.6  198.83
  5110.9  200.56  5130.5   201.6  5157.5  204.31  5197.8  206.77  5214.3   208.7
  5224.7  209.16    5233  208.57  5238.1  209.73  5245.4  207.98  5255.7  206.78
#Mann= 5 ,-1 , 0
  4746.8     .11       0  4818.1     .15       0  4977.2     .09       0
  5017.9     .15       0  5130.5     .17       0
Bank Sta=4977.2,5017.9
XS Rating Curve= 0 ,0
Exp/Cntr=0.3,0.1

Type RM Length L Ch R = 1 ,5266    ,487,487,487
BEGIN DESCRIPTION:
CCLC 135 4.0
END DESCRIPTION:
XS GIS Cut Line= 3
      3760896.47     10087576.64      3761098.23     10087446.84
      3761317.87     10087361.06
#Sta/Elev= 30
  4760.1  206.44  4837.1  201.52  4880.6   195.4  4916.3  195.06    4952  192.33
    4955  191.53  4961.2  189.87  4967.1  189.96  4975.8  187.88  4988.3  186.76
  4994.8  184.92  4995.1  184.42  4998.6  184.42  4998.8  184.92  5003.5  185.91
  5021.1  186.97    5028  188.05  5042.5  190.15  5052.5  190.02  5057.9  190.56
    5064  189.59  5077.7  190.38  5082.4   190.6  5087.7  192.07  5106.8  193.64
  5117.7  195.33    5142  197.23  5166.5  200.34  5203.6  203.65  5235.8  205.72
#Mann= 5 ,-1 , 0
  4760.1     .17       0    4955     .15       0  4975.8     .09       0
    5028     .15       0  5077.7     .11       0
Bank Sta=4975.8,5028
XS Rating Curve= 0 ,0
Exp/Cntr=0.3,0.1

Type RM Length L Ch R = 1 ,4779    ,234,234,234
BEGIN DESCRIPTION:
CCLC 135 3.0
END DESCRIPTION:
XS GIS Cut Line= 3
      3761117.82     10087811.08      3761368.23     10087726.84
      3761467.85     10087561.08
#Sta/Elev= 30
  4735.8  201.01  4747.7  200.18  4767.5  198.36  4809.3   195.3  4830.8   192.6
  4840.8  192.14  4846.1  191.07  4877.6  189.09  4883.5  188.32  4903.9   187.2
  4915.2  186.14  4946.8  185.91  4978.5  183.56  4989.1  183.72  4995.2  183.36
  4995.4  182.86  4998.9  182.86  4999.2  183.36  5010.8  183.66  5026.3   185.7
  5041.7  187.46  5063.2  189.08  5076.7  190.76  5084.6  191.15    5106  193.61
  5127.3  195.05  5142.3  196.61  5158.4  197.77  5170.1  199.31  5193.4  200.97
#Mann= 5 ,-1 , 0
  4735.8     .17       0  4747.7     .15       0  4946.8     .09       0
  5026.3     .15       0  5142.3     .17       0
Bank Sta=4946.8,5026.3
XS Rating Curve= 0 ,0
Exp/Cntr=0.3,0.1

Type RM Length L Ch R = 1 ,4545    ,439,439,439
BEGIN DESCRIPTION:
Mapping XS cabc0d11
END DESCRIPTION:
XS GIS Cut Line= 3
      3761282.38     10088085.16      3761453.26     10087990.89
      3761636.92     10087686.02
#Sta/Elev= 30
       0  193.87    15.4  192.66    21.1     193    37.2  191.92    42.9  192.42
    86.4  190.54    96.8  189.56   102.5  189.51     146  185.69   162.1  184.32
   167.8  184.36   183.8  182.87   228.6  183.15     250  182.76   271.4  183.26
   292.7  182.93   323.4  183.25   335.4   182.4   366.5  182.54   381.7  181.97
   393.7   182.6   409.2  184.48   430.6  187.43   467.5   190.8   504.4  193.58
   510.2   193.2   519.9  193.64   525.7  193.06   547.1  193.46     551  194.42
#Mann= 5 ,-1 , 0
       0     .17       0     146     .15       0   323.4     .09       0
   409.2     .15       0   467.5     .17       0
Bank Sta=323.4,409.2
XS Rating Curve= 0 ,0
Exp/Cntr=0.3,0.1

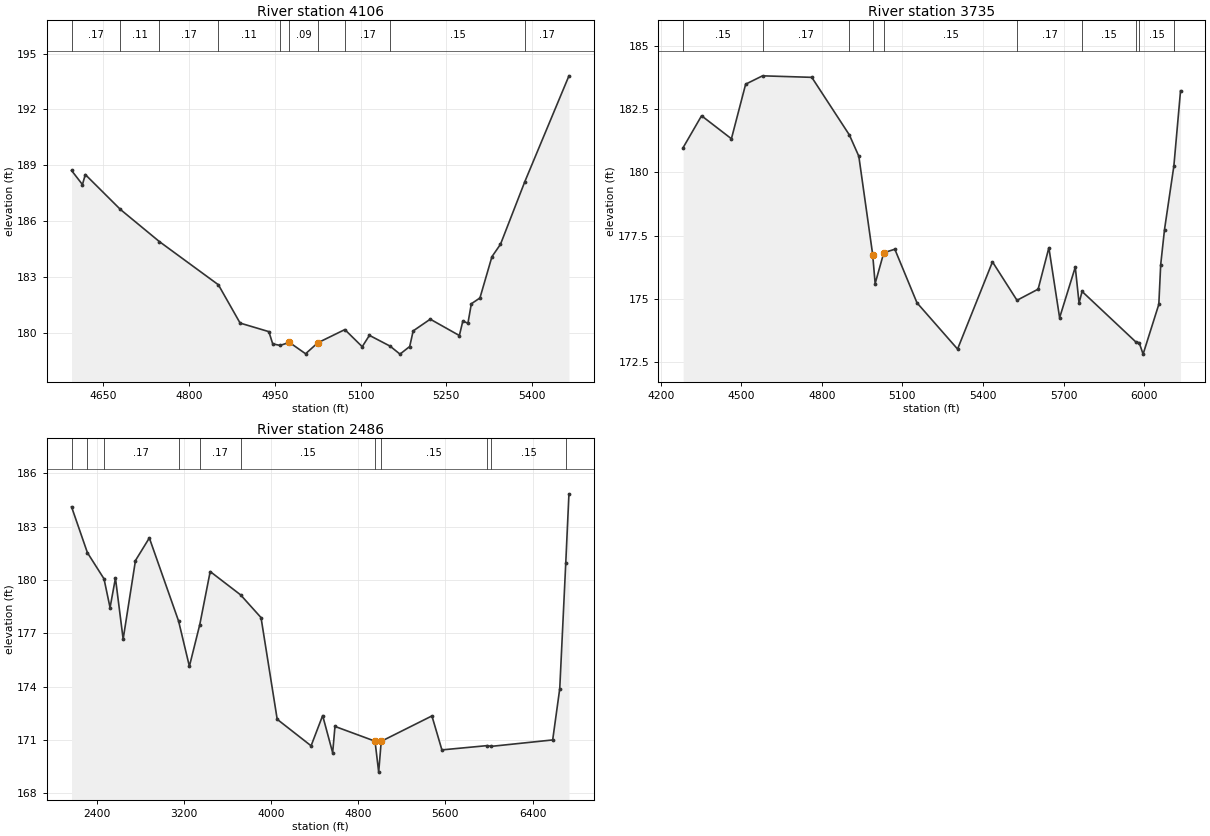
Type RM Length L Ch R = 1 ,4106    ,371,371,371
BEGIN DESCRIPTION:
Mapping XS d4ca2288
END DESCRIPTION:
XS GIS Cut Line= 4
      3761375.01     10088138.49       3761734.4     10088095.08
      3761850.72     10087982.23      3761656.97     10087695.06
#Sta/Elev= 30
  4594.1  188.72  4613.2  187.96  4618.2   188.5  4679.7  186.62    4748  184.89
  4851.1  182.57  4889.1  180.51  4939.4  180.05  4946.2  179.39  4959.1  179.31
  4975.4  179.47  5003.7  178.86  5025.1  179.45  5072.4  180.16  5102.8  179.24
  5115.4  179.85  5151.6  179.27  5168.9  178.84  5185.9  179.25    5192  180.09
  5221.9  180.72  5272.8  179.84  5278.9  180.62  5287.8   180.5  5293.8  181.55
  5308.8  181.86  5329.8  184.08  5344.8  184.75  5387.4  188.12  5464.6  193.81
#Mann= 10 ,-1 , 0
  4594.1     .17       0  4679.7     .11       0    4748     .17       0
  4851.1     .11       0  4959.1     .15       0  4975.4     .09       0
  5025.1     .15       0  5072.4     .17       0  5151.6     .15       0
  5387.4     .17       0
Bank Sta=4975.4,5025.1
XS Rating Curve= 0 ,0
Exp/Cntr=0.3,0.1

Type RM Length L Ch R = 1 ,3735    ,1249,1249,1249
BEGIN DESCRIPTION:
Mapping XS 3dcbcf30
END DESCRIPTION:
XS GIS Cut Line= 4
      3761123.56     10088542.19      3762100.46     10088295.39
      3762095.25     10087889.14      3761787.92     10087576.61
#Sta/Elev= 30
  4283.5  180.98  4352.1  182.24  4463.3  181.33  4516.3  183.49  4579.2  183.82
  4762.6  183.76  4902.6  181.48  4937.7  180.64  4989.3  176.75  4998.5   175.6
  5030.6  176.82  5071.8  176.96  5154.3  174.84  5305.4  173.01  5435.4  176.46
  5526.7  174.94  5605.4  175.38  5645.4  177.02  5685.4  174.25  5743.7  176.25
  5757.8  174.83    5769  175.29  5968.4   173.3  5981.7  173.26  5996.3  172.81
  6054.8  174.78  6061.8  176.35    6076  177.74  6110.8  180.25  6135.7  183.23
#Mann= 10 ,-1 , 0
  4283.5     .15       0  4579.2     .17       0  4902.6     .15       0
  4989.3     .09       0  5030.6     .15       0  5526.7     .17       0
    5769     .15       0  5968.4     .17       0  5981.7     .15       0
  6110.8     .17       0
Bank Sta=4989.3,5030.6
XS Rating Curve= 0 ,0
Exp/Cntr=0.3,0.1

Type RM Length L Ch R = 1 ,2486    ,0,0,0
BEGIN DESCRIPTION:
CCLC 135 2.0
END DESCRIPTION:
XS GIS Cut Line= 4
      3760567.84     10090861.08      3762568.23     10088856.84
      3762319.21     10087748.52      3761836.04     10087395.24
#Sta/Elev= 30
  2168.3  184.12    2314  181.54  2466.4  180.07  2521.9  178.45  2571.4  180.11
  2642.1  176.68  2755.2   181.1  2882.5  182.37  3151.2  177.69  3250.2  175.15
  3345.7   177.5  3441.1  180.48  3719.9  179.17  3907.8  177.89  4056.3  172.17
  4367.4  170.68  4473.5  172.38  4565.4  170.29  4586.6  171.77  4954.3  170.94
  4987.9   169.2 5011.18170.9333  5476.5  172.36  5568.2  170.45  5982.6  170.69
  6023.1  170.65  6585.2  171.01  6650.1   173.9  6705.1  180.95  6734.5  184.85
#Mann= 11 ,-1 , 0
  2168.3     .17       0    2314     .11       0  2466.4     .17       0
  3151.2     .15       0  3345.7     .17       0  3719.9     .15       0
  4954.3     .09       0 5011.18     .15       0  5982.6     .17       0
  6023.1     .15       0  6705.1     .17       0
Bank Sta=4954.3,5011.18
XS Rating Curve= 0 ,0
Exp/Cntr=0.3,0.1

Chan Stop Cuts=-1
Use User Specified Reach Order=0
Composite Channel Slope=5