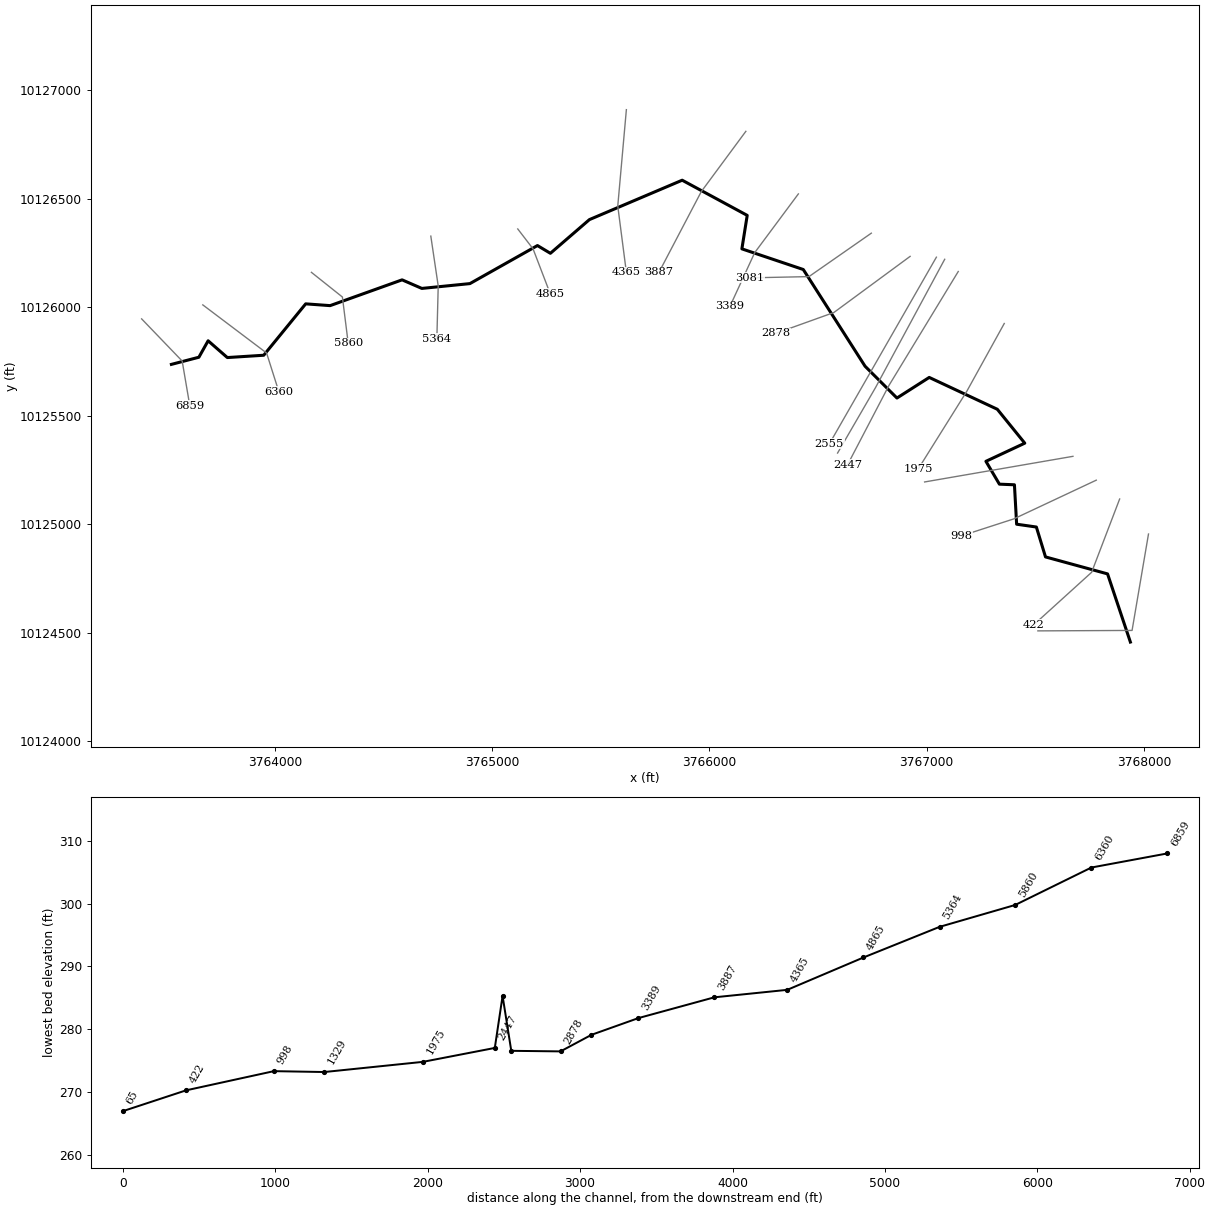
--- CCLC 145.prj (project) ---

Proj Title=CCLC 145 Base Level Engineering
Current Plan=p01
Default Exp/Contr=0.3,0.1
English Units
Geom File=g01
Flow File=f01
Flow File=f02
Plan File=p01
Y Axis Title=Elevation
X Axis Title(PF)=Main Channel Distance
X Axis Title(XS)=Station
BEGIN DESCRIPTION:
CCLC 145
END DESCRIPTION:
DSS Export Rating Curves= 0
DSS Export Rating Curve Sorted= 0
DSS Export Volume Flow Curves= 0
DXF OffsetX= 0
DXF OffsetY= 0
DXF ScaleX= 1
DXF ScaleY= 10

--- CCLC 145.p01 (plan) ---

Plan Title=Multiple Run
Short Identifier=Multiple
Geom File=g01
Flow File=f01
Subcritical Flow
K Sum by GR= 0
Std Step Tol= 0.01
Critical Tol= 0.01
Num of Std Step Trials= 20
Max Error Tol= 0.3
Flow Tol Ratio= 0.001
Split Flow NTrial= 30
Split Flow Tol= 0.02
Split Flow Ratio= 0.02
Log Output Level= 0
Friction Slope Method= 1
Unsteady Friction Slope Method= 2
Unsteady Bridges Friction Slope Method= 1
Parabolic Critical Depth
Global Vel Dist=  1 , 1 , 1
Global Log Level= 0
CheckData=True
Encroach Param= -1, 0, 0, 0
BEGIN DESCRIPTION:
Multiple Run
END DESCRIPTION:

--- CCLC 145.f01 (steady flow) ---

Flow Title=Multiple
Program Version=4.10
Number of Profiles= 7
Profile Names=10-year,25-year,50-year,1pct_min,100-year,1pct_plu,500-year
River Rch & RM=CCLC 145,Reach-1         ,6859
     461     614     820     361    1091    3295    1992
Boundary for River Rch & Prof#=CCLC 145,Reach-1         , 1
Up Type= 0
Dn Type= 3
Dn Slope=0.005
Boundary for River Rch & Prof#=CCLC 145,Reach-1         , 2
Up Type= 0
Dn Type= 3
Dn Slope=0.005
Boundary for River Rch & Prof#=CCLC 145,Reach-1         , 3
Up Type= 0
Dn Type= 3
Dn Slope=0.005
Boundary for River Rch & Prof#=CCLC 145,Reach-1         , 4
Up Type= 0
Dn Type= 3
Dn Slope=0.005
Boundary for River Rch & Prof#=CCLC 145,Reach-1         , 5
Up Type= 0
Dn Type= 3
Dn Slope=0.005
Boundary for River Rch & Prof#=CCLC 145,Reach-1         , 6
Up Type= 0
Dn Type= 3
Dn Slope=0.005
Boundary for River Rch & Prof#=CCLC 145,Reach-1         , 7
Up Type= 0
Dn Type= 3
Dn Slope=0.005
DSS Import GetInterval= 0
DSS Import GetPeak= 0
DSS Import FillOption= 0

--- CCLC 145.f02 (steady flow) ---

Flow Title=Orig_BLE_Flows
Program Version=4.10
Number of Profiles= 7
Profile Names=10-year,25-year,50-year,1pct_min,100-year,1pct_plu,500-year
River Rch & RM=CCLC 145,Reach-1         ,6859
     461     602     713     278     839    2533    1158
Boundary for River Rch & Prof#=CCLC 145,Reach-1         , 1
Up Type= 0
Dn Type= 3
Dn Slope=0.005
Boundary for River Rch & Prof#=CCLC 145,Reach-1         , 2
Up Type= 0
Dn Type= 3
Dn Slope=0.005
Boundary for River Rch & Prof#=CCLC 145,Reach-1         , 3
Up Type= 0
Dn Type= 3
Dn Slope=0.005
Boundary for River Rch & Prof#=CCLC 145,Reach-1         , 4
Up Type= 0
Dn Type= 3
Dn Slope=0.005
Boundary for River Rch & Prof#=CCLC 145,Reach-1         , 5
Up Type= 0
Dn Type= 3
Dn Slope=0.005
Boundary for River Rch & Prof#=CCLC 145,Reach-1         , 6
Up Type= 0
Dn Type= 3
Dn Slope=0.005
Boundary for River Rch & Prof#=CCLC 145,Reach-1         , 7
Up Type= 0
Dn Type= 3
Dn Slope=0.005
DSS Import GetInterval= 0
DSS Import GetPeak= 0
DSS Import FillOption= 0

--- CCLC 145.g01 (geometry) ---

Geom Title=Existing Conditions
Program Version=4.10

River Reach=CCLC 145        ,Reach-1
Reach XY= 30
      3763523.23     10125736.84       3763649.7     10125769.77
      3763692.31     10125845.62      3763780.71     10125768.29
      3763948.25     10125778.96      3764141.44     10126015.84
        3764254.     10126007.68      3764585.33      10126126.5
      3764676.21     10126086.97      3764897.46     10126109.18
      3765208.45     10126284.59      3765268.01     10126248.87
      3765447.68     10126404.17       3765874.8     10126585.78
      3766174.16     10126423.65      3766149.64     10126269.33
      3766432.33     10126174.14      3766716.74     10125728.32
      3766863.53     10125581.72      3767012.15     10125676.71
      3767325.61     10125529.95      3767452.02     10125373.67
      3767273.18     10125290.02       3767335.2     10125184.73
      3767404.43     10125181.85      3767414.52     10125000.12
      3767505.39     10124987.14      3767547.46     10124849.32
      3767833.11     10124771.12      3767938.23     10124456.84

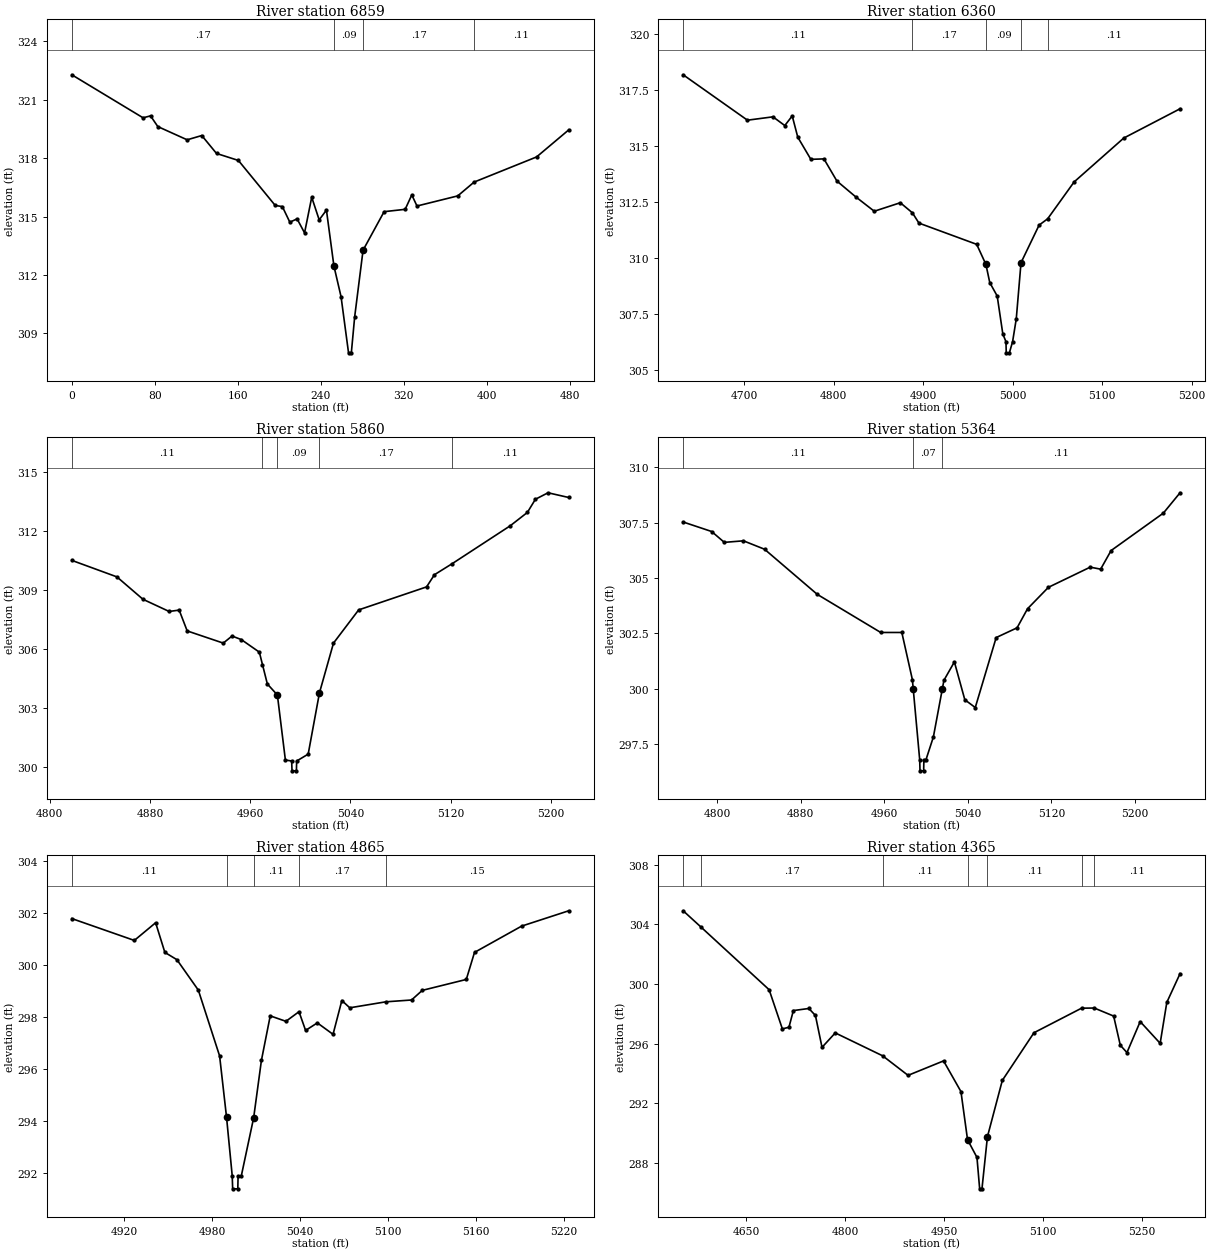
Type RM Length L Ch R = 1 ,6859    ,499,499,499
BEGIN DESCRIPTION:
CCLC 145 13.0
END DESCRIPTION:
XS GIS Cut Line= 3
      3763386.18      10125946.6      3763572.83     10125752.24
      3763608.14     10125545.16
#Sta/Elev= 30
       0  322.28    68.7  320.07    75.9  320.17    82.9  319.62   111.2  318.94
   125.3  319.16   139.5  318.24   160.6  317.88   196.1  315.57     203  315.51
   210.2  314.71   217.2  314.88   224.4  314.16   231.3  315.99   238.5  314.83
   245.5  315.33   252.7  312.46   259.6  310.88   266.8     308   269.5     308
   272.7  309.84   280.8  313.27   301.1  315.25   321.4  315.37   327.8  316.11
   332.8  315.54   372.1  316.06   387.9  316.77   448.1  318.06   479.1  319.45
#Mann= 4 ,-1 , 0
       0     .17       0   252.7     .09       0   280.8     .17       0
   387.9     .11       0
Bank Sta=252.7,280.8
XS Rating Curve= 0 ,0
Exp/Cntr=0.3,0.1

Type RM Length L Ch R = 1 ,6360    ,500,500,500
BEGIN DESCRIPTION:
CCLC 145 12.0
END DESCRIPTION:
XS GIS Cut Line= 3
      3763667.83     10126011.08      3763961.39     10125789.33
      3764017.86     10125611.06
#Sta/Elev= 30
  4632.1  318.18  4703.9  316.15  4732.4   316.3  4745.6  315.91  4753.9  316.34
  4760.1  315.39  4774.7   314.4  4789.3  314.42  4803.8  313.43  4824.6  312.73
  4845.5  312.08  4874.6  312.46  4888.1  312.01  4895.4  311.55  4959.9   310.6
  4970.2309.7022  4974.5  308.89  4982.8  308.29  4989.1  306.59  4992.6  306.25
  4992.9  305.75  4996.4  305.75    5000  306.25  5004.1  307.27  5009.4  309.78
  5029.6  311.46  5039.1  311.74  5068.7  313.39  5124.1  315.35    5187  316.66
#Mann= 5 ,-1 , 0
  4632.1     .11       0  4888.1     .17       0  4970.2     .09       0
  5009.4     .17       0  5039.1     .11       0
Bank Sta=4970.2,5009.4
XS Rating Curve= 0 ,0
Exp/Cntr=0.3,0.1

Type RM Length L Ch R = 1 ,5860    ,496,496,496
BEGIN DESCRIPTION:
CCLC 145 11.0
END DESCRIPTION:
XS GIS Cut Line= 3
      3764167.85     10126161.07      3764310.45     10126047.34
      3764337.14     10125834.71
#Sta/Elev= 30
  4817.6  310.49  4853.6  309.65  4874.4  308.51  4895.3  307.89  4903.3  307.96
  4909.7   306.9  4938.5  306.28  4945.5  306.64  4952.9  306.46  4967.3  305.82
  4969.8  305.19  4973.7   304.2  4981.7  303.64  4988.1  300.33  4993.1  300.28
  4993.4  299.78  4996.9  299.78  4997.1  300.28  5006.3  300.63  5015.3  303.75
  5026.5  306.28  5046.6  307.97  5100.8  309.14  5107.1  309.76  5121.2  310.32
  5167.6  312.25  5181.3  312.93  5187.7   313.6  5197.8  313.93  5214.3  313.69
#Mann= 5 ,-1 , 0
  4817.6     .11       0  4969.8     .17       0  4981.7     .09       0
  5015.3     .17       0  5121.2     .11       0
Bank Sta=4981.7,5015.3
XS Rating Curve= 0 ,0
Exp/Cntr=0.3,0.1

Type RM Length L Ch R = 1 ,5364    ,499,499,499
BEGIN DESCRIPTION:
CCLC 145 10.0
END DESCRIPTION:
XS GIS Cut Line= 3
      3764717.53      10126328.1      3764751.62     10126098.22
      3764745.32      10125855.1
#Sta/Elev= 30
  4767.6  307.53  4794.9   307.1    4807  306.61  4825.3  306.68  4845.5   306.3
    4896  304.26  4956.7  302.54  4976.9  302.54    4987  300.41 4987.84299.9757
    4994  296.79  4994.3  296.29  4997.8  296.29    4998  296.79    5000  296.79
  5007.1  297.82 5015.69299.9972  5017.2  300.38  5027.2  301.21  5037.2   299.5
  5047.2  299.15  5067.2  302.31  5087.2  302.75  5097.2  303.61  5117.2  304.58
  5157.2  305.49  5167.2   305.4  5177.2  306.24  5227.2  307.93  5243.2  308.85
#Mann= 3 ,-1 , 0
  4767.6     .11       0 4987.84     .07       0 5015.69     .11       0
Bank Sta=4987.84,5015.69
XS Rating Curve= 0 ,0
Exp/Cntr=0.3,0.1

Type RM Length L Ch R = 1 ,4865    ,500,500,500
BEGIN DESCRIPTION:
CCLC 145 9.0
END DESCRIPTION:
XS GIS Cut Line= 3
      3765117.84     10126361.08      3765188.15     10126269.45
      3765267.85     10126061.07
#Sta/Elev= 30
  4884.5   301.8  4927.1  300.96  4941.6  301.64  4947.9   300.5  4956.1  300.22
  4970.7  299.05  4985.2  296.52 4989.93294.1624  4993.8  291.91  4994.1  291.41
  4997.6  291.41  4997.8  291.91    5000  291.91  5008.4  294.14  5013.7  296.35
  5019.7  298.06  5030.4  297.85  5039.3  298.22  5043.8   297.5  5051.8  297.79
  5062.5  297.35  5068.5  298.65  5073.9  298.37  5098.5   298.6    5116  298.67
  5123.3  299.04  5153.3  299.46  5158.9   300.5    5191  301.51  5223.1   302.1
#Mann= 5 ,-1 , 0
  4884.5     .11       0 4989.93     .07       0  5008.4     .11       0
  5039.3     .17       0  5098.5     .15       0
Bank Sta=4989.93,5008.4
XS Rating Curve= 0 ,0
Exp/Cntr=0.3,0.1

Type RM Length L Ch R = 1 ,4365    ,478,478,478
BEGIN DESCRIPTION:
CCLC 145 8.0
END DESCRIPTION:
XS GIS Cut Line= 3
      3765617.85     10126911.08      3765578.23     10126466.84
      3765617.85      10126161.1
#Sta/Elev= 30
    4554  304.92  4580.5  303.85  4684.5  299.62  4704.6  296.99  4714.6   297.1
  4721.3  298.22  4744.8  298.36  4754.8  297.89  4764.8  295.75  4784.9  296.72
  4856.9  295.18  4895.4  293.87  4949.3  294.84  4975.7  292.78  4985.7  289.55
    5000  288.36  5004.1  286.25  5007.6  286.25  5015.9  289.75  5038.5  293.53
  5086.5  296.73  5158.8  298.38  5178.1  298.39  5207.5  297.85  5217.6  295.89
  5227.7   295.4  5247.8  297.48  5278.1  296.02  5288.2  298.77  5308.3   300.7
#Mann= 7 ,-1 , 0
    4554     .11       0  4580.5     .17       0  4856.9     .11       0
  4985.7     .06       0  5015.9     .11       0  5158.8     .17       0
  5178.1     .11       0
Bank Sta=4985.7,5015.9
XS Rating Curve= 0 ,0
Exp/Cntr=0.3,0.1

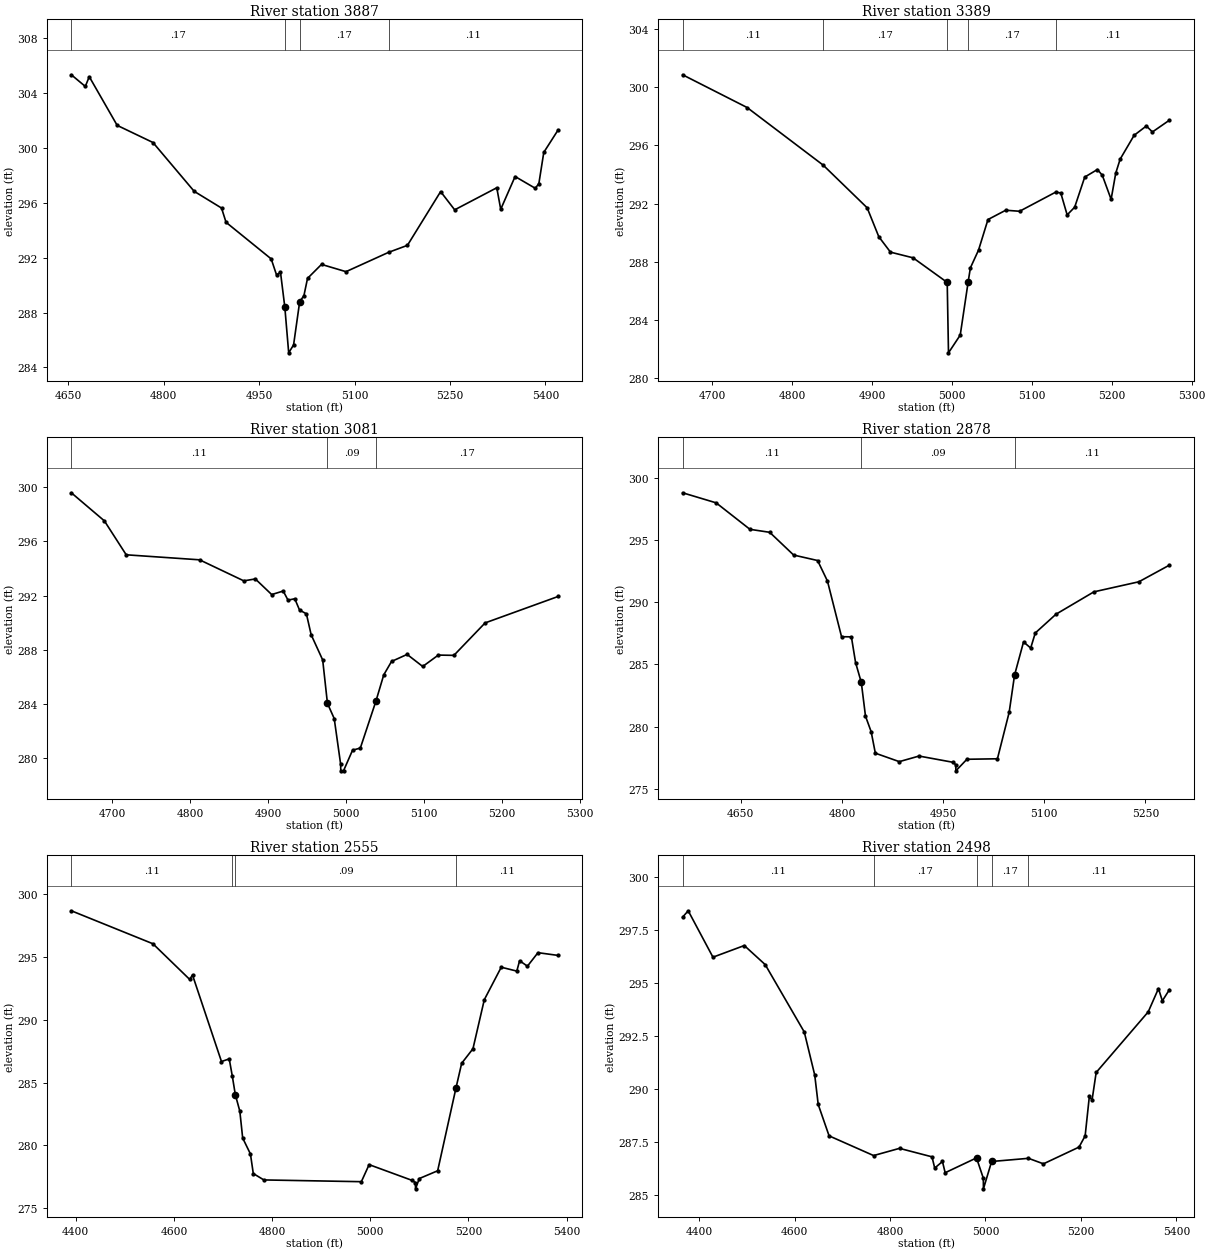
Type RM Length L Ch R = 1 ,3887    ,498,498,498
BEGIN DESCRIPTION:
CCLC 145 7.0
END DESCRIPTION:
XS GIS Cut Line= 3
      3766167.88      10126811.1      3765962.65     10126533.16
      3765767.85     10126161.07
#Sta/Elev= 30
  4654.5  305.34  4676.5  304.49  4682.7   305.2  4726.6  301.65  4782.9   300.4
  4847.7  296.84  4890.7  295.62  4897.8  294.58  4968.8  291.91  4977.2  290.74
  4983.4  290.94  4990.2   288.4  4996.3  285.06    5004  285.64  5013.6   288.8
  5020.2  289.22  5025.9  290.49  5047.9  291.51  5086.4  290.98  5153.4  292.39
    5183   292.9  5235.2  296.82  5257.3  295.49  5323.5   297.1  5329.7  295.53
  5352.3  297.92  5384.1  297.06  5389.7  297.41  5397.4  299.68    5420  301.32
#Mann= 4 ,-1 , 0
  4654.5     .17       0  4990.2     .09       0  5013.6     .17       0
  5153.4     .11       0
Bank Sta=4990.2,5013.6
XS Rating Curve= 0 ,0
Exp/Cntr=0.3,0.1

Type RM Length L Ch R = 1 ,3389    ,308,308,308
BEGIN DESCRIPTION:
CCLC 145 6.0
END DESCRIPTION:
XS GIS Cut Line= 3
      3766409.66     10126522.61      3766208.77     10126252.02
      3766094.86     10126004.81
#Sta/Elev= 30
    4663  300.86  4743.7  298.61  4838.9  294.65  4893.9  291.72  4908.5  289.73
  4923.1  288.67  4951.4  288.28  4994.1  286.59  4995.7  281.75  5010.4  282.97
 5020.37286.6459  5023.1  287.59  5033.3  288.81  5045.1  290.91  5067.3  291.55
  5084.7  291.48  5129.7  292.79  5136.2  292.74  5144.2  291.23  5153.6  291.76
  5166.2  293.83  5182.1  294.35  5188.2  293.95  5199.2   292.3    5205   294.1
  5210.5  295.06    5228   296.7  5243.3  297.34  5250.9  296.93  5272.2  297.74
#Mann= 5 ,-1 , 0
    4663     .11       0  4838.9     .17       0  4994.1     .09       0
 5020.37     .17       0  5129.7     .11       0
Bank Sta=4994.1,5020.37
XS Rating Curve= 0 ,0
Exp/Cntr=0.3,0.1

Type RM Length L Ch R = 1 ,3081    ,203,203,203
BEGIN DESCRIPTION:
Mapping XS 707510e0
END DESCRIPTION:
XS GIS Cut Line= 3
      3766745.58      10126341.7      3766458.43     10126141.43
      3766184.19     10126135.66
#Sta/Elev= 30
  4647.7  299.57  4690.1   297.5  4718.1     295  4812.2  294.63  4868.9  293.08
  4883.7  293.22  4904.7  292.07  4919.5  292.33  4925.6  291.66  4934.3  291.76
  4940.4  290.93  4949.2  290.65  4955.3  289.11  4970.1  287.25  4976.2  284.05
  4984.9  282.93  4993.1  279.58  4993.3  279.08  4996.8  279.08  5008.4   280.6
  5018.4  280.76  5038.4  284.22  5048.4  286.15  5058.4  287.14  5078.4  287.66
  5098.4  286.77  5118.4  287.61  5138.4  287.59  5178.4  289.98  5272.1  291.93
#Mann= 3 , 0 , 0
  4647.7     .11       0  4976.2     .09       0  5038.4     .17       0
Bank Sta=4976.2,5038.4
XS Rating Curve= 0 ,0
Exp/Cntr=0.3,0.1

Type RM Length L Ch R = 1 ,2878    ,323,323,323
BEGIN DESCRIPTION:
CCLC 145 5.0
END DESCRIPTION:
XS GIS Cut Line= 3
       3766924.1     10126234.64      3766573.04     10125975.92
      3766304.28     10125879.29
#Sta/Elev= 30
  4563.9  298.81  4613.6     298  4663.7  295.87    4693  295.63  4728.5   293.8
    4764  293.36  4778.6  291.71  4799.5  287.23  4814.1  287.22  4820.3  285.15
  4828.8  283.55    4835  280.84  4843.4  279.59  4849.6  277.86  4885.1  277.18
  4914.4  277.63  4964.5  277.13  4968.7  276.94    4969  276.44  4985.3  277.37
  5030.6  277.41    5048  281.15    5056  284.15  5069.3  286.81  5079.9  286.32
  5086.7  287.53  5117.4  289.04  5173.6  290.84  5240.3  291.65  5285.6  292.99
#Mann= 3 , 0 , 0
  4563.9     .11       0  4828.8     .09       0    5056     .11       0
Bank Sta=4828.8,5056
XS Rating Curve= 0 ,0
Exp/Cntr=0.3,0.1

Type RM Length L Ch R = 1 ,2555    ,57,57,57
BEGIN DESCRIPTION:
Mapping XS 657ce2b9
END DESCRIPTION:
XS GIS Cut Line= 2
      3767045.08     10126230.95      3766552.41     10125370.52
#Sta/Elev= 30
  4391.1   298.7  4557.3  296.07  4632.1  293.23  4637.9  293.58  4696.9  286.68
  4712.7  286.89  4719.1  285.49  4725.1  284.04  4734.3  282.72  4740.1  280.58
  4755.9  279.31  4761.7  277.75  4783.2  277.24  4981.8   277.1  4997.6  278.46
    5084  277.22  5091.9  277.03  5092.1  276.53  5099.8  277.35  5137.2  277.97
  5174.5  284.57  5186.1  286.54  5209.1   287.7  5232.2  291.61  5266.7   294.2
  5298.4  293.89  5304.1  294.72    5320  294.28  5341.5  295.36  5382.6  295.14
#Mann= 4 ,-1 , 0
  4391.1     .11       0  4719.1     .17       0  4725.1     .09       0
  5174.5     .11       0
Bank Sta=4725.1,5174.5
XS Rating Curve= 0 ,0
Exp/Cntr=0.3,0.1

Type RM Length L Ch R = 1 ,2498    ,51,51,51
BEGIN DESCRIPTION:
Mapping XS 85549235
END DESCRIPTION:
XS GIS Cut Line= 3
      3767083.37     10126221.34      3766764.98     10125630.04
      3766590.21     10125328.15
#Sta/Elev= 30
  4365.2   298.1  4376.9   298.4  4428.8  296.21  4494.5  296.76  4538.3  295.86
  4620.2  292.68  4642.1  290.65  4649.4  289.26  4672.2  287.78  4765.5  286.85
  4819.8  287.19  4887.9  286.79  4893.6  286.26  4909.8  286.57  4915.5  286.04
  4981.2  286.74  4995.5  285.78  4995.7  285.28  5012.9  286.57  5090.1  286.72
  5121.5  286.46  5196.1  287.25  5208.9  287.78  5217.7  289.64  5223.4  289.47
    5232  290.77  5341.1  293.63  5362.6  294.73  5370.7  294.15  5385.6  294.68
#Mann= 5 ,-1 , 0
  4365.2     .11       0  4765.5     .17       0  4981.2     .09       0
  5012.9     .17       0  5090.1     .11       0
Bank Sta=4981.2,5012.9
XS Rating Curve= 0 ,0
Exp/Cntr=0.3,0.1

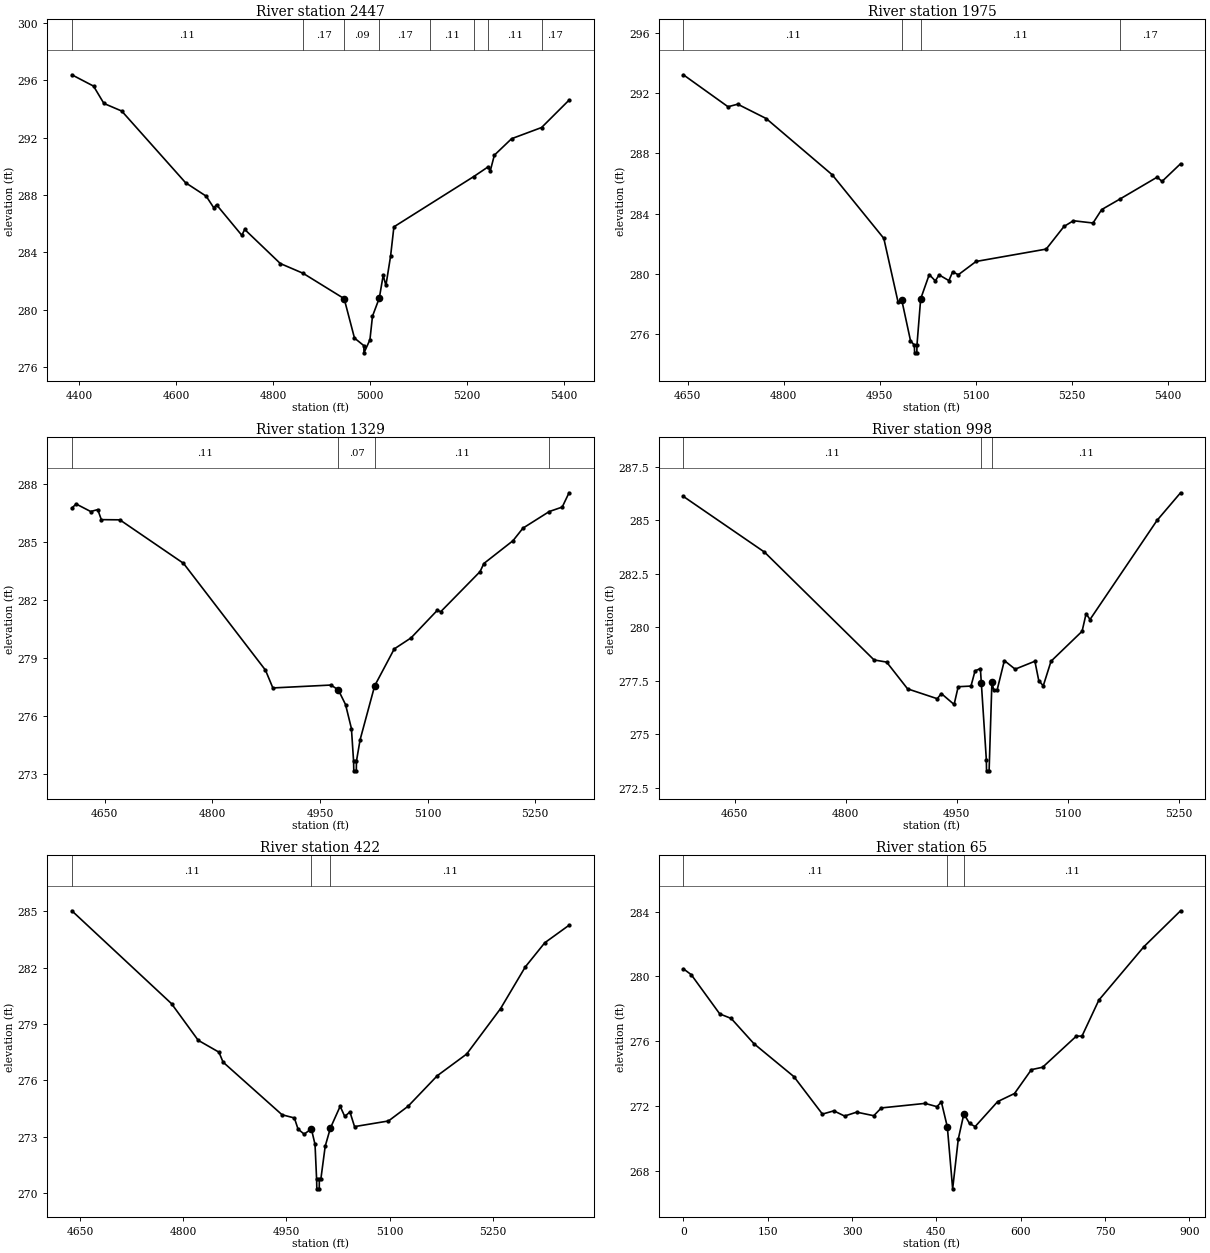
Type RM Length L Ch R = 1 ,2447    ,472,472,472
BEGIN DESCRIPTION:
CCLC 145 4.0
END DESCRIPTION:
XS GIS Cut Line= 3
      3767145.78     10126164.98      3766826.25     10125638.92
      3766636.26     10125274.35
#Sta/Elev= 30
  4384.5  296.39  4429.3   295.6  4450.7  294.39  4487.5  293.86  4619.3  288.86
  4661.9  287.92  4677.4  287.12  4683.3  287.32  4735.5  285.19  4741.4   285.6
    4815  283.22    4862  282.54  4946.8  280.77  4968.1  278.02  4987.5  277.49
  4987.7  276.99    5000   277.9  5005.3  279.55 5019.37280.8139  5027.4   282.4
    5033  281.69  5042.7  283.75  5049.5  285.78  5214.4  289.29  5244.2  289.97
  5248.3  289.66  5256.9  290.78  5292.5  291.93  5354.4  292.71  5411.1  294.62
#Mann= 8 ,-1 , 0
  4384.5     .11       0    4862     .17       0  4946.8     .09       0
 5019.37     .17       0  5124.4     .11       0  5214.4     .17       0
  5244.2     .11       0  5354.4     .17       0
Bank Sta=4946.8,5019.37
XS Rating Curve= 0 ,0
Exp/Cntr=0.3,0.1

Type RM Length L Ch R = 1 ,1975    ,646,646,646
BEGIN DESCRIPTION:
CCLC 145 3.0
END DESCRIPTION:
XS GIS Cut Line= 3
      3767357.58      10125925.4      3767185.25     10125613.09
      3766962.54     10125256.53
#Sta/Elev= 30
  4643.3  293.21  4713.1  291.09  4728.2  291.26  4772.7  290.31  4875.9  286.58
  4956.6  282.36    4979  278.11  4984.7  278.26  4998.3  275.58  5004.4  275.27
  5004.7  274.77  5008.2  274.77  5008.4  275.27  5014.2  278.35  5027.6  279.96
  5037.1  279.54    5043  279.94  5058.3  279.56  5064.2  280.14  5073.1  279.95
  5100.8  280.83  5210.4  281.65  5238.2  283.15  5252.9  283.53  5283.6  283.38
  5297.1  284.27  5325.7  284.97  5383.8  286.42  5391.5  286.14  5420.4  287.31
#Mann= 4 ,-1 , 0
  4643.3     .11       0  4984.7     .07       0  5014.2     .11       0
  5325.7     .17       0
Bank Sta=4984.7,5014.2
XS Rating Curve= 0 ,0
Exp/Cntr=0.3,0.1

Type RM Length L Ch R = 1 ,1329    ,331,331,331
BEGIN DESCRIPTION:
Mapping XS 9cd6fae7
END DESCRIPTION:
XS GIS Cut Line= 2
      3767673.78     10125313.01      3766990.92     10125194.89
#Sta/Elev= 30
  4604.2  286.75  4610.2  286.96  4630.5  286.57  4640.3  286.67  4645.3  286.15
  4671.1  286.14  4759.8  283.89  4874.1  278.36  4884.4  277.44  4965.4  277.59
  4975.6  277.34  4985.7  276.58  4993.9  275.34  4996.9  273.65  4997.2  273.15
  5000.7  273.15  5000.9  273.65    5006  274.76  5026.3  277.55  5053.6  279.46
    5077  280.03  5113.4  281.45  5118.5  281.39  5173.2  283.46  5178.5  283.88
  5219.1  285.06    5233  285.71  5269.7  286.57  5287.7   286.8  5297.2  287.54
#Mann= 4 ,-1 , 0
  4604.2     .11       0  4975.6     .07       0  5026.3     .11       0
  5269.7     .17       0
Bank Sta=4975.6,5026.3
XS Rating Curve= 0 ,0
Exp/Cntr=0.3,0.1

Type RM Length L Ch R = 1 ,998     ,576,576,576
BEGIN DESCRIPTION:
CCLC 145 2.0
END DESCRIPTION:
XS GIS Cut Line= 3
      3767781.17     10125203.15      3767401.54     10125024.64
      3767161.26     10124946.73
#Sta/Elev= 30
  4580.5  286.11  4690.1  283.51  4838.3  278.47  4855.3  278.37  4883.6  277.12
  4923.7  276.66  4929.2   276.9  4946.5  276.39    4952  277.22  4969.3  277.25
  4974.8  277.96    4982  278.07 4983.25277.4095  4990.1  273.79  4990.3  273.29
  4993.8  273.29  4997.6  277.45    5000  277.06  5004.6  277.06  5014.4  278.44
    5029  278.04  5055.7  278.41  5060.9  277.51    5067  277.26  5077.5  278.41
  5119.5  279.81  5124.9  280.63  5130.2  280.36  5220.8  284.99  5252.6  286.28
#Mann= 3 , 0 , 0
  4580.5     .11       0 4983.25     .06       0  4997.6     .11       0
Bank Sta=4983.25,4997.6
XS Rating Curve= 0 ,0
Exp/Cntr=0.3,0.1

Type RM Length L Ch R = 1 ,422     ,416,416,416
BEGIN DESCRIPTION:
CCLC 145 1.0
END DESCRIPTION:
XS GIS Cut Line= 3
      3767888.81     10125116.34       3767759.8     10124778.43
      3767492.82     10124536.04
#Sta/Elev= 30
  4638.3  285.02  4783.1  280.08  4821.9  278.13    4852   277.5    4858  276.97
  4943.7  274.17  4961.6     274  4966.9  273.41  4975.8  273.14  4986.3  273.42
  4991.6  272.59  4993.9  270.73  4994.2  270.23  4997.7  270.23  4997.9  270.73
    5000  270.73  5006.4   272.5  5013.9  273.46  5028.1  274.62  5034.8  274.08
  5042.3  274.32    5049  273.54  5098.3  273.84  5126.7  274.62  5169.3  276.25
  5211.9   277.4  5261.2  279.82    5297  282.03  5325.4  283.32  5360.6  284.25
#Mann= 3 , 0 , 0
  4638.3     .11       0  4986.3     .06       0  5013.9     .11       0
Bank Sta=4986.3,5013.9
XS Rating Curve= 0 ,0
Exp/Cntr=0.3,0.1

Type RM Length L Ch R = 1 ,65      ,0,0,0
BEGIN DESCRIPTION:
CCLC 145 1.0
END DESCRIPTION:
XS GIS Cut Line= 3
      3768021.61     10124954.86      3767945.99     10124510.49
      3767512.31     10124508.43
#Sta/Elev= 30
       0  280.47      14  280.11    64.7  277.69      85  277.41   125.6  275.85
   196.6  273.82   247.3  271.51   267.6  271.71   286.7  271.39   308.2  271.63
   338.6  271.41     352  271.89   429.9  272.17   450.8  271.97   458.9  272.25
  469.44  270.72   478.9   266.9   488.9  269.97   498.9  271.53   508.9  270.93
   518.9  270.74   558.9  272.28   588.9  272.78   618.9  274.25   638.9   274.4
   698.9  276.32   708.9  276.32   738.9  278.54   818.9  281.83   884.2  284.05
#Mann= 3 , 0 , 0
       0     .11       0  469.44     .06       0   498.9     .11       0
Bank Sta=469.44,498.9
XS Rating Curve= 0 ,0
Exp/Cntr=0.3,0.1

Chan Stop Cuts=-1
Use User Specified Reach Order=0
Composite Channel Slope=5