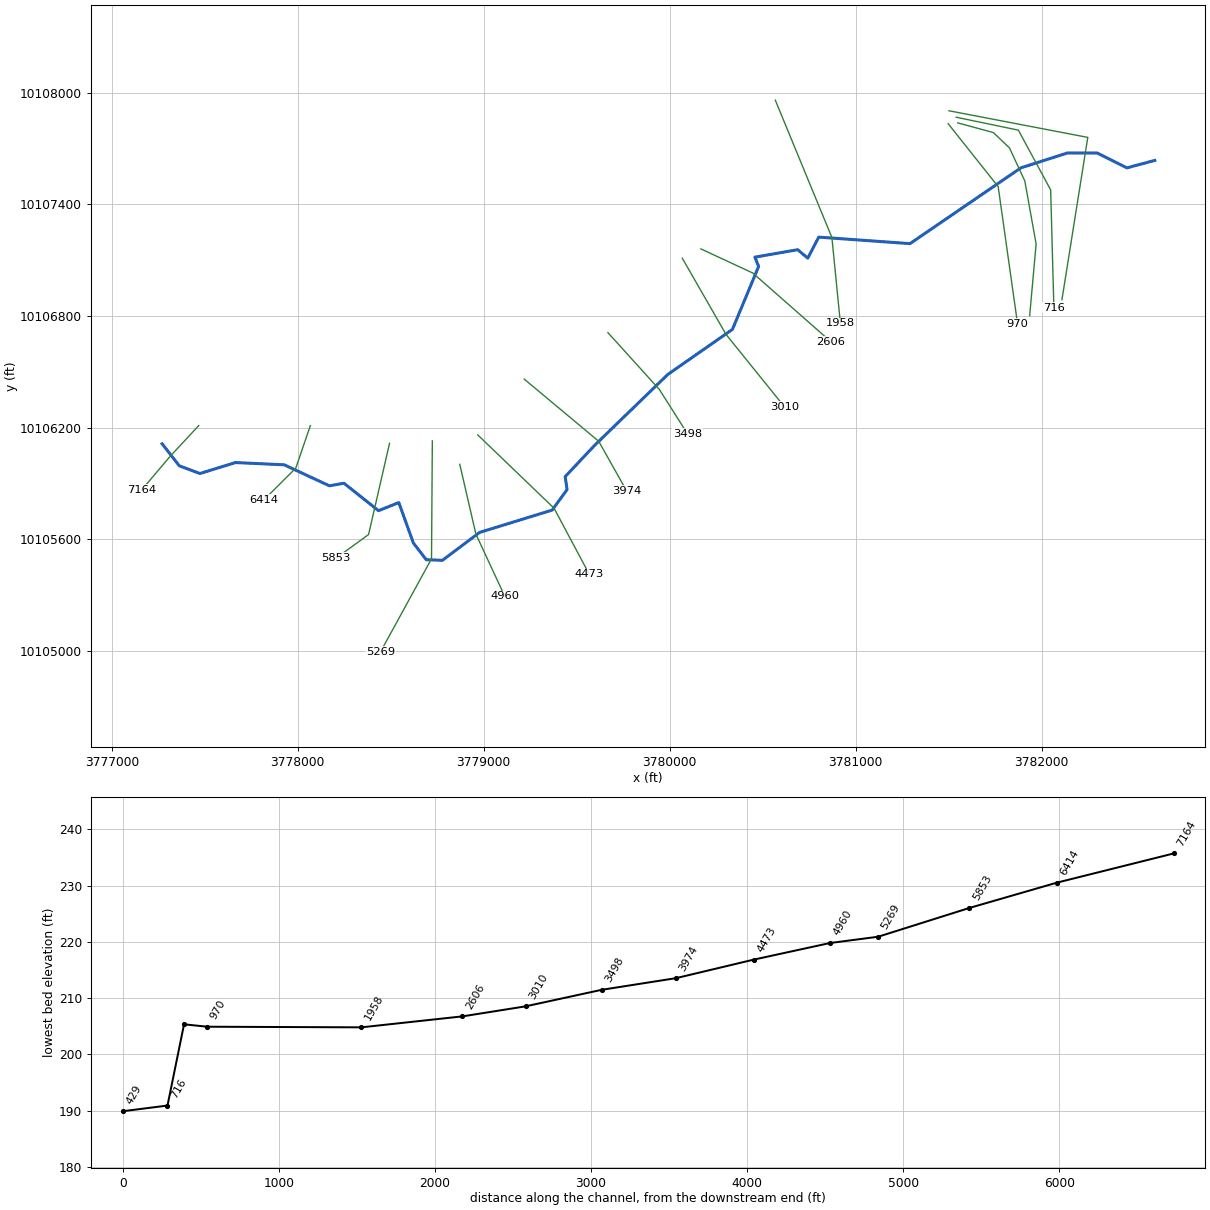
--- DEER LAKE BRANCH.prj (project) ---

Proj Title=DEER LAKE BRANCH Base Level Engineering
Current Plan=p01
Default Exp/Contr=0.3,0.1
English Units
Geom File=g01
Flow File=f01
Flow File=f02
Plan File=p01
Y Axis Title=Elevation
X Axis Title(PF)=Main Channel Distance
X Axis Title(XS)=Station
BEGIN DESCRIPTION:
DEER LAKE BRANCH
END DESCRIPTION:
DSS Export Rating Curves= 0
DSS Export Rating Curve Sorted= 0
DSS Export Volume Flow Curves= 0
DXF OffsetX= 0
DXF OffsetY= 0
DXF ScaleX= 1
DXF ScaleY= 10

--- DEER LAKE BRANCH.p01 (plan) ---

Plan Title=Multiple Run
Short Identifier=Multiple
Geom File=g01
Flow File=f01
Subcritical Flow
K Sum by GR= 0
Std Step Tol= 0.01
Critical Tol= 0.01
Num of Std Step Trials= 20
Max Error Tol= 0.3
Flow Tol Ratio= 0.001
Split Flow NTrial= 30
Split Flow Tol= 0.02
Split Flow Ratio= 0.02
Log Output Level= 0
Friction Slope Method= 1
Unsteady Friction Slope Method= 2
Unsteady Bridges Friction Slope Method= 1
Parabolic Critical Depth
Global Vel Dist=  1 , 1 , 1
Global Log Level= 0
CheckData=True
Encroach Param= -1, 0, 0, 0
BEGIN DESCRIPTION:
Multiple Run
END DESCRIPTION:

--- DEER LAKE BRANCH.f01 (steady flow) ---

Flow Title=Multiple
Program Version=4.10
Number of Profiles= 7
Profile Names=10-year,25-year,50-year,1pct_min,100-year,1pct_plu,500-year
River Rch & RM=DEER LAKE BRANCH,Reach-1         ,7164
     949    1319    1815     821    2480    7489    4788
River Rch & RM=DEER LAKE BRANCH,Reach-1         ,4960
    1173    1644    2275    1034    3123    9431    6084
River Rch & RM=DEER LAKE BRANCH,Reach-1         ,716
    1237    1739    2412    1099    3318   10020    6491
Boundary for River Rch & Prof#=DEER LAKE BRANCH,Reach-1         , 1
Up Type= 0
Dn Type= 3
Dn Slope=0.005
Boundary for River Rch & Prof#=DEER LAKE BRANCH,Reach-1         , 2
Up Type= 0
Dn Type= 3
Dn Slope=0.005
Boundary for River Rch & Prof#=DEER LAKE BRANCH,Reach-1         , 3
Up Type= 0
Dn Type= 3
Dn Slope=0.005
Boundary for River Rch & Prof#=DEER LAKE BRANCH,Reach-1         , 4
Up Type= 0
Dn Type= 3
Dn Slope=0.005
Boundary for River Rch & Prof#=DEER LAKE BRANCH,Reach-1         , 5
Up Type= 0
Dn Type= 3
Dn Slope=0.005
Boundary for River Rch & Prof#=DEER LAKE BRANCH,Reach-1         , 6
Up Type= 0
Dn Type= 3
Dn Slope=0.005
Boundary for River Rch & Prof#=DEER LAKE BRANCH,Reach-1         , 7
Up Type= 0
Dn Type= 3
Dn Slope=0.005
DSS Import GetInterval= 0
DSS Import GetPeak= 0
DSS Import FillOption= 0

--- DEER LAKE BRANCH.f02 (steady flow) ---

Flow Title=Orig_BLE_Flows
Program Version=4.10
Number of Profiles= 7
Profile Names=10-year,25-year,50-year,1pct_min,100-year,1pct_plu,500-year
River Rch & RM=DEER LAKE BRANCH,Reach-1         ,7164
     949    1293    1578     632    1908    5761    2784
River Rch & RM=DEER LAKE BRANCH,Reach-1         ,4960
    1173    1612    1978     795    2402    7253    3537
River Rch & RM=DEER LAKE BRANCH,Reach-1         ,716
    1237    1705    2097     845    2552    7706    3774
Boundary for River Rch & Prof#=DEER LAKE BRANCH,Reach-1         , 1
Up Type= 0
Dn Type= 3
Dn Slope=0.005
Boundary for River Rch & Prof#=DEER LAKE BRANCH,Reach-1         , 2
Up Type= 0
Dn Type= 3
Dn Slope=0.005
Boundary for River Rch & Prof#=DEER LAKE BRANCH,Reach-1         , 3
Up Type= 0
Dn Type= 3
Dn Slope=0.005
Boundary for River Rch & Prof#=DEER LAKE BRANCH,Reach-1         , 4
Up Type= 0
Dn Type= 3
Dn Slope=0.005
Boundary for River Rch & Prof#=DEER LAKE BRANCH,Reach-1         , 5
Up Type= 0
Dn Type= 3
Dn Slope=0.005
Boundary for River Rch & Prof#=DEER LAKE BRANCH,Reach-1         , 6
Up Type= 0
Dn Type= 3
Dn Slope=0.005
Boundary for River Rch & Prof#=DEER LAKE BRANCH,Reach-1         , 7
Up Type= 0
Dn Type= 3
Dn Slope=0.005
DSS Import GetInterval= 0
DSS Import GetPeak= 0
DSS Import FillOption= 0

--- DEER LAKE BRANCH.g01 (geometry) ---

Geom Title=Existing Conditions
Program Version=4.10

River Reach=DEER LAKE BRANCH,Reach-1
Reach XY= 30
      3777271.03     10106113.05      3777363.05     10105994.99
      3777474.16     10105953.32      3777665.13     10106012.35
      3777927.28      10106000.2      3778170.34     10105887.35
      3778248.47     10105901.24      3778434.23     10105753.67
       3778543.6     10105797.07      3778621.73     10105580.06
      3778691.17     10105489.78      3778778.23     10105486.84
      3778978.23     10105636.84      3779368.23     10105756.84
      3779448.23     10105866.84      3779438.23     10105936.84
      3779598.23     10106106.84       3779989.5     10106485.82
      3780337.34     10106728.25      3780478.23     10107066.84
      3780458.23     10107116.84      3780688.23     10107156.84
      3780742.52     10107111.42      3780801.46     10107224.52
      3781292.08     10107189.47      3781888.23     10107596.84
      3782138.23     10107676.84      3782298.23     10107676.84
      3782458.23     10107596.84      3782608.23     10107636.84

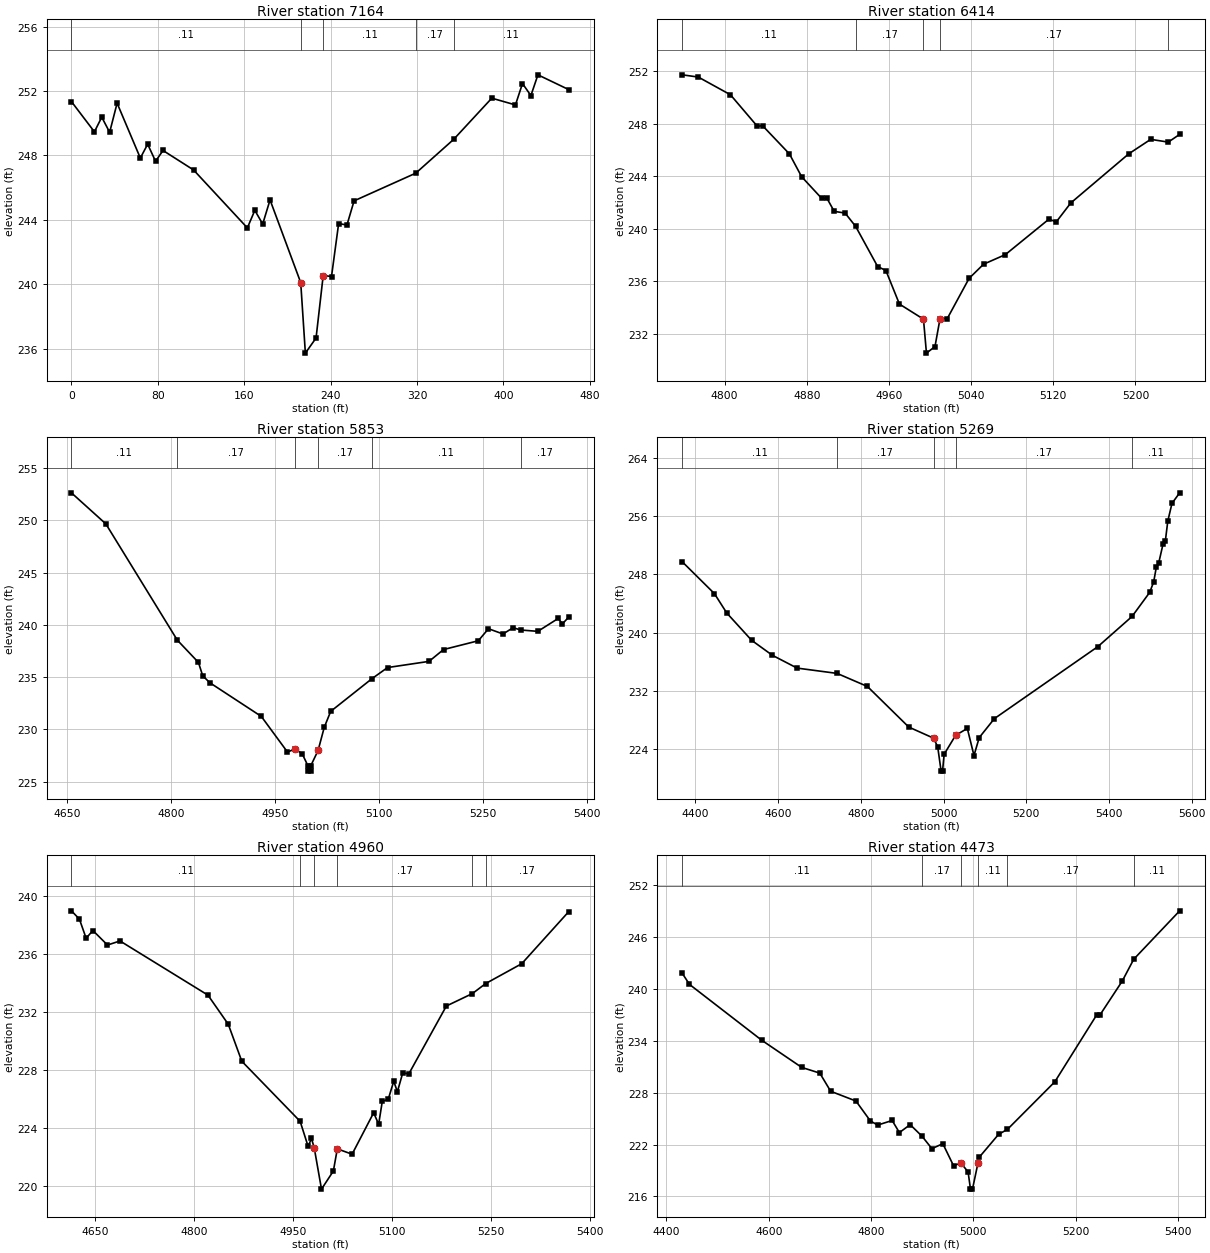
Type RM Length L Ch R = 1 ,7164    ,750,750,750
BEGIN DESCRIPTION:
DEER LAKE BRANCH 11.0
END DESCRIPTION:
XS GIS Cut Line= 3
      3777467.85     10106211.07      3777317.55     10106049.73
      3777161.68     10105866.02
#Sta/Elev= 30
       0  251.35    21.3  249.47    28.1  250.38    35.4  249.44    42.3  251.25
    63.8  247.84    70.6   248.7    77.9  247.64    84.8  248.31   113.1   247.1
   162.9   243.5   169.8  244.59   177.1  243.74   183.9  245.24   212.3   240.1
   216.6  235.72   226.5  236.66   233.1  240.54   240.8  240.48   247.4  243.77
   255.1  243.68   261.7  245.18   318.8   246.9   353.9     249   389.2  251.56
   411.1  251.14   417.6  252.47   425.4  251.72   431.9  253.01   460.5  252.09
#Mann= 5 ,-1 , 0
       0     .11       0   212.3     .07       0   233.1     .11       0
   318.8     .17       0   353.9     .11       0
Bank Sta=212.3,233.1
XS Rating Curve= 0 ,0
Exp/Cntr=0.3,0.1

Type RM Length L Ch R = 1 ,6414    ,561,561,561
BEGIN DESCRIPTION:
DEER LAKE BRANCH 10.0
END DESCRIPTION:
XS GIS Cut Line= 3
      3778067.85     10106211.06      3777989.78     10105982.84
      3777817.87     10105811.09
#Sta/Elev= 30
  4758.8  251.74  4774.4  251.57  4805.7  250.22  4831.8  247.82    4837  247.86
  4863.1  245.71    4875  243.97  4894.4  242.33  4899.6  242.33  4906.7  241.33
  4917.3   241.2  4927.6  240.18    4949  237.12    4957  236.82  4970.2  234.26
  4993.6  233.11  4996.5  230.52  5004.8  231.02  5009.7  233.14  5016.8  233.16
    5038  236.22  5052.1   237.3  5073.3  238.03  5115.8  240.74  5122.8  240.52
    5137  241.97  5193.5  245.72  5214.8  246.82  5231.9  246.61    5243   247.2
#Mann= 5 ,-1 , 0
  4758.8     .11       0  4927.6     .17       0  4993.6     .09       0
  5009.7     .17       0  5231.9     .11       0
Bank Sta=4993.6,5009.7
XS Rating Curve= 0 ,0
Exp/Cntr=0.3,0.1

Type RM Length L Ch R = 1 ,5853    ,584,584,584
BEGIN DESCRIPTION:
Mapping XS cd0a980d
END DESCRIPTION:
XS GIS Cut Line= 3
      3778493.72     10106115.66      3778380.87     10105625.22
      3778207.25     10105499.35
#Sta/Elev= 30
  4656.4  252.62  4706.1  249.65  4809.2  238.54  4839.7  236.41  4845.8  235.14
  4856.1  234.47  4930.4  231.25  4968.1  227.85  4979.2  228.13  4989.5  227.67
  4997.7  226.52    4998  226.02  5001.5  226.02  5001.7  226.52 5012.32227.9931
  5021.2   230.2  5030.5  231.73  5090.1  234.86  5112.6  235.92  5172.4  236.51
  5193.3  237.64  5243.5  238.48  5258.2  239.63  5279.1  239.13  5293.8  239.73
  5304.6  239.51  5329.4  239.38  5358.7  240.61  5364.9   240.1  5374.1  240.75
#Mann= 6 ,-1 , 0
  4656.4     .11       0  4809.2     .17       0  4979.2     .09       0
 5012.32     .17       0  5090.1     .11       0  5304.6     .17       0
Bank Sta=4979.2,5012.32
XS Rating Curve= 0 ,0
Exp/Cntr=0.3,0.1

Type RM Length L Ch R = 1 ,5269    ,309,309,309
BEGIN DESCRIPTION:
DEER LAKE BRANCH 9.0
END DESCRIPTION:
XS GIS Cut Line= 3
      3778723.75     10106128.74      3778719.41     10105495.01
      3778446.01     10104995.94
#Sta/Elev= 30
  4368.3  249.74    4446  245.36    4476  242.68    4536  238.93    4586  236.87
    4646   235.1  4742.7  234.37    4816  232.57    4916  226.98    4976  225.45
    4986  224.25  4994.2  220.91  4997.7  220.91  5001.5  223.23  5029.3  225.84
  5057.6  226.79  5073.7  223.06  5086.4  225.53    5123  228.14  5373.3  238.06
  5455.9  242.21  5498.5  245.52  5508.2  246.96  5514.6  248.99  5520.3  249.55
  5530.7  252.14  5536.4  252.58  5542.4  255.35  5552.5  257.79  5571.1  259.24
#Mann= 5 ,-1 , 0
  4368.3     .11       0  4742.7     .17       0    4976     .09       0
  5029.3     .17       0  5455.9     .11       0
Bank Sta=4976,5029.3
XS Rating Curve= 0 ,0
Exp/Cntr=0.3,0.1

Type RM Length L Ch R = 1 ,4960    ,487,487,487
BEGIN DESCRIPTION:
DEER LAKE BRANCH 8.0
END DESCRIPTION:
XS GIS Cut Line= 3
      3778871.32     10106002.83      3778958.23     10105626.84
       3779113.6      10105292.7
#Sta/Elev= 30
  4614.1     239  4626.2  238.43  4636.4  237.11  4646.7  237.64  4668.8  236.64
  4687.8  236.92  4821.2  233.18    4852  231.17  4872.5  228.62    4961  224.47
  4973.1  222.74  4978.2  223.29 4982.42222.6277  4993.4  219.79  5011.4  221.04
  5017.4  222.57  5039.8   222.2  5072.5  225.06  5080.1  224.27  5085.6  225.85
  5094.6  225.99    5103  227.24  5108.5  226.51  5116.6  227.81  5125.9  227.75
  5182.8  232.43  5222.3  233.29  5242.4  233.98  5297.1  235.35  5368.5  238.95
#Mann= 6 ,-1 , 0
  4614.1     .11       0    4961     .17       0 4982.42     .09       0
  5017.4     .17       0  5222.3     .11       0  5242.4     .17       0
Bank Sta=4982.42,5017.4
XS Rating Curve= 0 ,0
Exp/Cntr=0.3,0.1

Type RM Length L Ch R = 1 ,4473    ,499,499,499
BEGIN DESCRIPTION:
DEER LAKE BRANCH 7.0
END DESCRIPTION:
XS GIS Cut Line= 3
      3778967.82      10106161.1      3779378.23     10105766.84
      3779567.87     10105411.03
#Sta/Elev= 30
  4430.9  241.81    4445  240.53  4586.5  234.06  4664.4  230.93  4699.7  230.27
    4721  228.17  4770.4  227.04  4798.7  224.73  4812.9  224.26  4841.2  224.79
  4855.3  223.39  4876.4  224.31  4899.7  222.96  4918.9  221.53  4940.2  222.11
  4961.3  219.54  4975.5  219.88  4989.6  218.84  4994.3  216.85  4998.2  216.85
    5009219.8886    5011  220.51  5049.3  223.19  5066.5  223.76  5159.1  229.26
  5241.3  237.03  5246.9  236.95  5290.9  240.91  5313.4  243.44  5403.2  249.04
#Mann= 6 ,-1 , 0
  4430.9     .11       0  4899.7     .17       0  4975.5     .07       0
    5009     .11       0  5066.5     .17       0  5313.4     .11       0
Bank Sta=4975.5,5009
XS Rating Curve= 0 ,0
Exp/Cntr=0.3,0.1

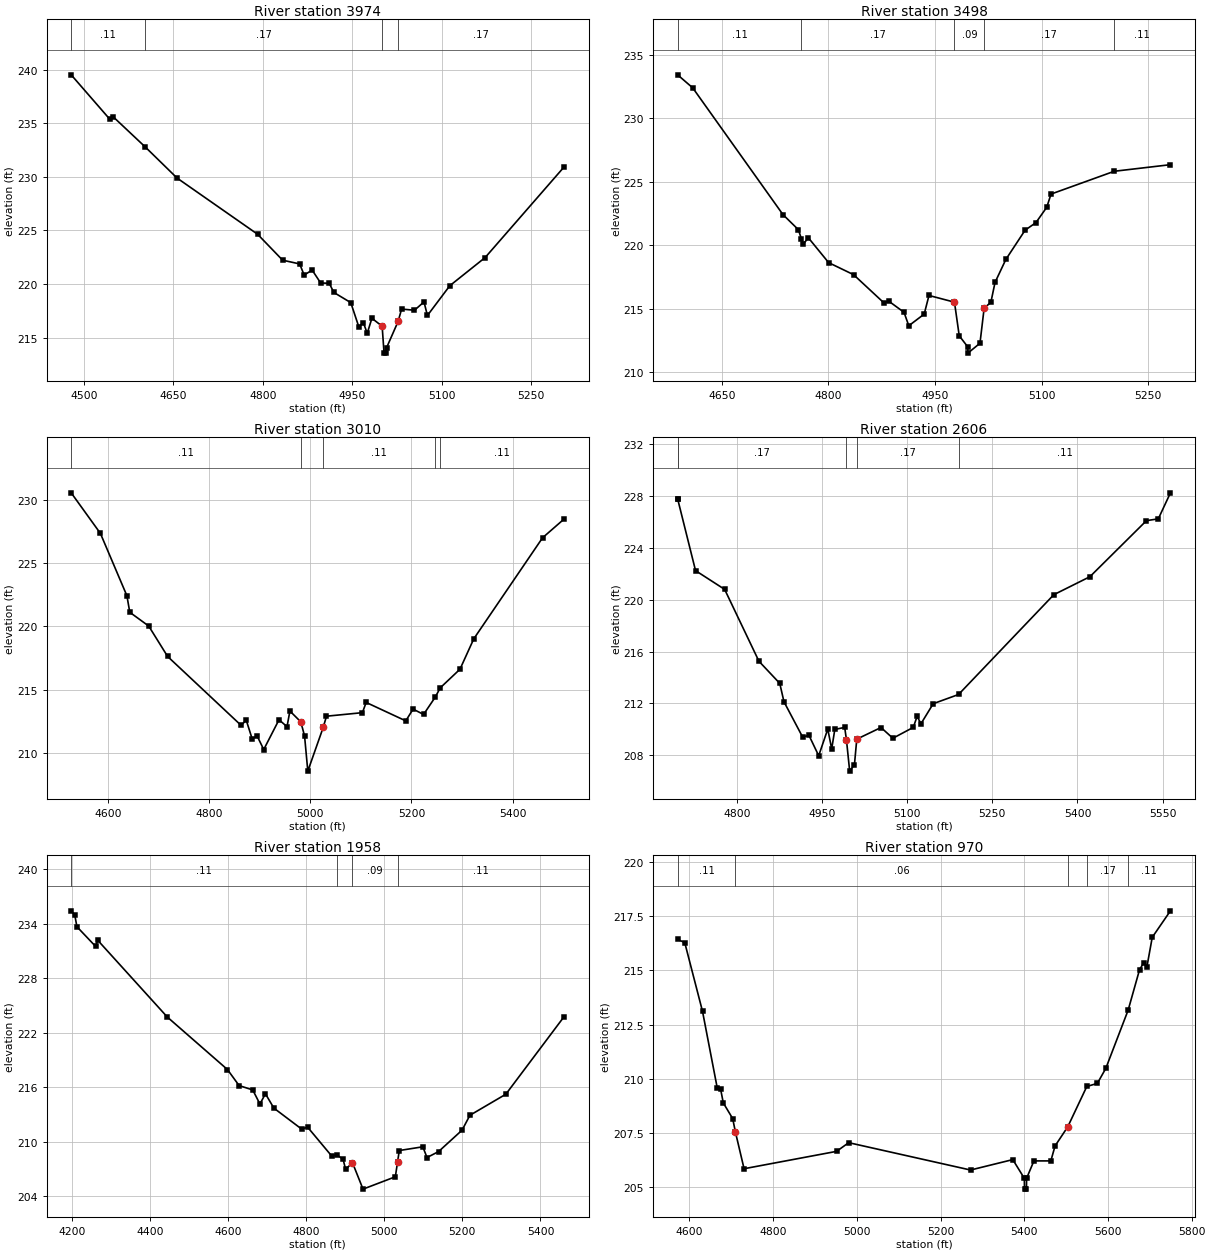
Type RM Length L Ch R = 1 ,3974    ,476,476,476
BEGIN DESCRIPTION:
DEER LAKE BRANCH 6.0
END DESCRIPTION:
XS GIS Cut Line= 3
      3779217.89     10106461.04      3779618.23     10106126.84
      3779767.85     10105861.07
#Sta/Elev= 30
  4478.5  239.51  4542.9  235.39  4549.4  235.57  4603.1  232.76  4656.1  229.88
  4791.1  224.64  4833.1  222.22  4861.7  221.87  4869.2  220.83  4882.6   221.3
  4896.9  220.09  4911.2  220.07    4919  219.21  4947.4  218.26  4960.7  216.03
  4968.5  216.39    4975   215.4  4982.8   216.8    5000  216.06  5003.2  213.55
  5007.1  213.55  5007.4  214.05  5026.8  216.51  5032.6  217.66  5054.2  217.55
  5070.2  218.33  5075.9  217.06  5113.5  219.84  5172.8  222.47    5305  230.91
#Mann= 4 ,-1 , 0
  4478.5     .11       0  4603.1     .17       0    5000     .09       0
  5026.8     .17       0
Bank Sta=5000,5026.8
XS Rating Curve= 0 ,0
Exp/Cntr=0.3,0.1

Type RM Length L Ch R = 1 ,3498    ,488,488,488
BEGIN DESCRIPTION:
DEER LAKE BRANCH 5.0
END DESCRIPTION:
XS GIS Cut Line= 3
      3779667.86     10106711.07      3779944.47     10106405.32
      3780095.28     10106167.75
#Sta/Elev= 30
  4587.7  233.44    4609  232.41    4736  222.41  4757.7  221.22    4762  220.49
  4764.4  220.09  4771.9  220.57  4800.3  218.62  4835.4  217.67    4878  215.45
  4884.7  215.59  4906.4   214.7  4913.1  213.64  4934.8  214.56  4941.5  216.03
  4977.4   215.5  4984.1  212.85    4996  211.98  4996.3  211.48  5013.3  212.26
  5019.2  215.04  5028.6  215.48  5034.5  217.06  5049.7  218.87  5076.8  221.18
  5092.1  221.78  5107.3  222.99  5113.3  224.03  5202.3  225.83  5281.4  226.35
#Mann= 5 ,-1 , 0
  4587.7     .11       0    4762     .17       0  4977.4     .09       0
  5019.2     .17       0  5202.3     .11       0
Bank Sta=4977.4,5019.2
XS Rating Curve= 0 ,0
Exp/Cntr=0.3,0.1

Type RM Length L Ch R = 1 ,3010    ,404,404,404
BEGIN DESCRIPTION:
DEER LAKE BRANCH 4.0
END DESCRIPTION:
XS GIS Cut Line= 3
      3780067.84      10107111.1      3780302.85     10106701.42
      3780617.85     10106311.07
#Sta/Elev= 30
  4527.7  230.58  4585.4  227.37  4637.8  222.43  4643.5  221.12  4680.9  220.03
  4718.3  217.62  4863.6  212.16  4873.6  212.58  4885.2  211.11  4895.2  211.32
  4908.2  210.25  4938.4  212.61  4954.2  212.06  4959.9   213.3  4981.5  212.44
  4988.9  211.32  4995.3  208.54  5025.8  212.01  5032.2  212.89  5103.2  213.17
  5110.6  213.98  5188.9  212.52  5203.3  213.45  5224.1  213.03  5246.8  214.38
  5257.1  215.14    5296  216.61  5323.3  219.02  5459.2  227.02  5501.6   228.5
#Mann= 5 ,-1 , 0
  4527.7     .11       0  4981.5     .07       0  5025.8     .11       0
  5246.8     .17       0  5257.1     .11       0
Bank Sta=4981.5,5025.8
XS Rating Curve= 0 ,0
Exp/Cntr=0.3,0.1

Type RM Length L Ch R = 1 ,2606    ,648,648,648
BEGIN DESCRIPTION:
DEER LAKE BRANCH 3.0
END DESCRIPTION:
XS GIS Cut Line= 3
      3780167.87     10107161.06      3780446.84     10107031.47
      3780867.89     10106661.04
#Sta/Elev= 30
  4695.4  227.75  4695.7  227.75    4727  222.25  4778.3   220.8  4838.7  215.25
  4875.4  213.54  4882.8  212.12  4915.6   209.4  4926.9  209.52    4944  207.95
    4960  210.01  4966.9  208.47  4972.4  209.98  4989.8  210.14 4992.86209.1942
  4998.6  206.76    5007  207.26  5011.1  209.23  5053.8  210.13  5074.7   209.3
  5110.7  210.14  5117.4  210.99  5124.2  210.42  5145.8  211.97  5190.4  212.68
  5358.3  220.39  5421.9  221.78  5521.5  226.11  5542.4  226.25  5563.8  228.26
#Mann= 5 ,-1 , 0
  4695.4     .11       0  4695.7     .17       0 4992.86     .09       0
  5011.1     .17       0  5190.4     .11       0
Bank Sta=4992.86,5011.1
XS Rating Curve= 0 ,0
Exp/Cntr=0.3,0.1

Type RM Length L Ch R = 1 ,1958    ,988,988,988
BEGIN DESCRIPTION:
DEER LAKE BRANCH 2.0
END DESCRIPTION:
XS GIS Cut Line= 3
      3780567.84      10107961.1      3780872.19     10107222.45
      3780917.85      10106761.1
#Sta/Elev= 30
  4197.9  235.45  4207.2  234.97  4212.6   233.7  4260.5  231.53  4265.9  232.21
  4444.3  223.75  4598.1  217.98  4628.1  216.21    4663  215.73  4681.4  214.18
  4695.5  215.31  4717.1  213.73    4788  211.43  4803.6  211.63  4865.2  208.46
  4878.4   208.6  4894.5  208.08  4900.9  206.99  4918.5  207.72  4945.5  204.81
  5028.3  206.17 5033.96207.7896  5038.4  209.06  5098.7  209.47  5109.4  208.29
  5138.9  208.94  5199.2   211.3  5219.3  212.94  5311.4  215.26  5460.4  223.79
#Mann= 4 ,-1 , 0
  4197.9     .11       0  4878.4     .17       0  4918.5     .09       0
 5033.96     .11       0
Bank Sta=4918.5,5033.96
XS Rating Curve= 0 ,0
Exp/Cntr=0.3,0.1

Type RM Length L Ch R = 1 ,970     ,148,148,148
BEGIN DESCRIPTION:
Mapping XS 17aacc86
END DESCRIPTION:
XS GIS Cut Line= 3
       3781497.2     10107834.41      3781766.29     10107495.88
      3781870.45     10106758.04
#Sta/Elev= 30
  4571.7  216.42  4588.7  216.28  4631.2  213.11  4666.5  209.57  4674.5  209.52
  4680.9  208.89  4703.3  208.17  4709.7  207.56  4730.5  205.86  4951.6  206.66
  4980.5  207.06  5271.6   205.8  5372.6  206.28  5400.1  205.42  5400.6  204.92
  5405.2  204.92  5405.6  205.42  5423.1  206.22  5463.5  206.22  5473.6  206.91
  5503.9  207.79  5549.5  209.65  5574.6  209.79  5594.8  210.48  5648.3  213.17
  5675.5  215.03  5685.6  215.35  5692.8  215.13  5705.8  216.52  5749.3  217.74
#Mann= 5 ,-1 , 0
  4571.7     .11       0  4709.7     .06       0  5503.9     .11       0
  5549.5     .17       0  5648.3     .11       0
Bank Sta=4709.7,5503.9
XS Rating Curve= 0 ,0
Exp/Cntr=0.3,0.1

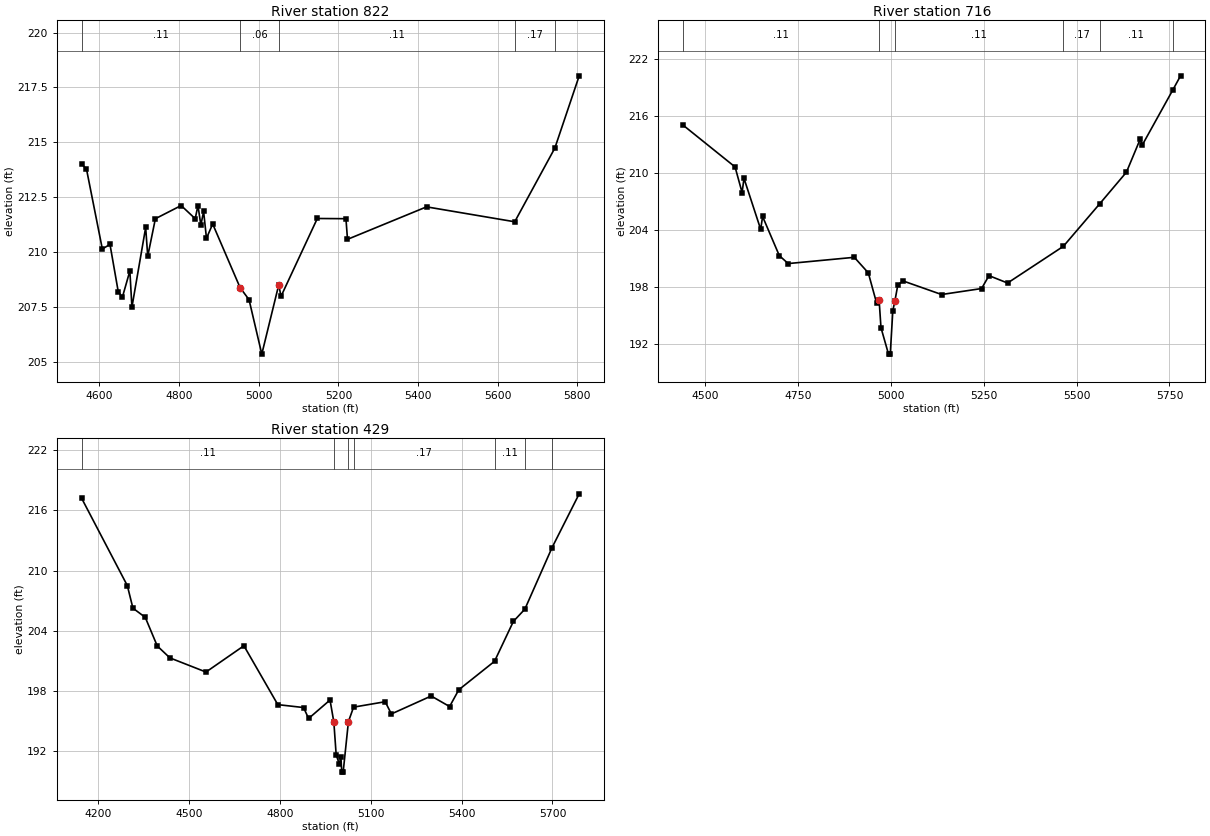
Type RM Length L Ch R = 1 ,822     ,106,106,106
BEGIN DESCRIPTION:
Mapping XS 3c04e80a
END DESCRIPTION:
XS GIS Cut Line= 6
      3781549.29     10107838.76      3781740.25     10107786.68
      3781827.05     10107704.22      3781909.52     10107526.26
      3781970.28     10107187.72      3781935.57     10106801.47
#Sta/Elev= 30
  4555.4  214.01  4567.5  213.78  4607.3  210.14  4626.5  210.35  4647.2   208.2
  4657.6  207.94  4676.4  209.14  4681.6  207.49  4716.1  211.12  4721.3  209.81
  4740.5  211.52  4805.2  212.12  4840.5  211.52  4847.4  212.12  4854.7  211.23
  4861.6  211.85  4868.8  210.63  4884.4  211.28  4953.2  208.38  4975.7  207.83
  5007.7  205.35  5050.3  208.51  5055.9  207.98  5147.1  211.53    5219  211.52
  5222.9  210.58  5421.4  212.06  5642.8  211.38  5743.6  214.74  5804.7  218.03
#Mann= 5 ,-1 , 0
  4555.4     .11       0  4953.2     .06       0  5050.3     .11       0
  5642.8     .17       0  5743.6     .11       0
Bank Sta=4953.2,5050.3
XS Rating Curve= 0 ,0
Exp/Cntr=0.3,0.1

Type RM Length L Ch R = 1 ,716     ,287,287,287
BEGIN DESCRIPTION:
Mapping XS eeb7c591
END DESCRIPTION:
XS GIS Cut Line= 4
      3781540.56     10107869.15      3781874.79      10107799.7
      3782048.41     10107478.52      3782065.75     10106845.43
#Sta/Elev= 30
    4440  215.04  4580.2  210.63  4599.1  207.93  4604.2  209.43  4649.2  204.05
  4654.3  205.41  4699.3  201.29  4723.2  200.45  4901.3  201.11    4939  199.47
  4961.3  196.29 4968.13196.5762  4973.1   193.7  4993.4  190.91  4998.1  190.91
    5005  195.49  5010.7  196.53  5018.5  198.21  5032.6  198.62  5136.3  197.19
    5244  197.82    5264  199.18    5314   198.4  5464.3  202.27  5562.6  206.77
  5634.1  210.08  5671.5  213.59  5676.5  212.92  5759.1  218.75  5779.8  220.23
#Mann= 6 ,-1 , 0
    4440     .11       0 4968.13     .07       0  5010.7     .11       0
  5464.3     .17       0  5562.6     .11       0  5759.1     .17       0
Bank Sta=4968.13,5010.7
XS Rating Curve= 0 ,0
Exp/Cntr=0.3,0.1

Type RM Length L Ch R = 1 ,429     ,0,0,0
BEGIN DESCRIPTION:
DEER LAKE BRANCH 1.0
END DESCRIPTION:
XS GIS Cut Line= 3
      3781501.55     10107903.86      3782248.06     10107760.64
      3782109.17     10106888.25
#Sta/Elev= 30
  4144.9   217.2  4295.7   208.5  4314.2  206.25    4355  205.33  4394.6  202.48
  4436.4  201.29  4555.6  199.88  4680.8   202.5  4792.8  196.63  4877.8  196.34
  4894.6  195.25  4965.3  197.09 4977.86194.9023  4985.6  191.63  4995.7  190.73
  5001.3  191.37    5004   189.9  5008.7   189.9  5026.1  194.94  5043.1  196.38
  5147.6  196.92  5167.9   195.7  5299.5  197.49  5360.3  196.44  5390.6  198.11
  5508.7  200.95    5571  204.93  5608.9  206.15  5698.6  212.28  5788.4  217.65
#Mann= 7 ,-1 , 0
  4144.9     .11       0 4977.86     .06       0  5026.1     .11       0
  5043.1     .17       0  5508.7     .11       0  5608.9     .17       0
  5698.6     .11       0
Bank Sta=4977.86,5026.1
XS Rating Curve= 0 ,0
Exp/Cntr=0.3,0.1

Chan Stop Cuts=-1
Use User Specified Reach Order=0
Composite Channel Slope=5