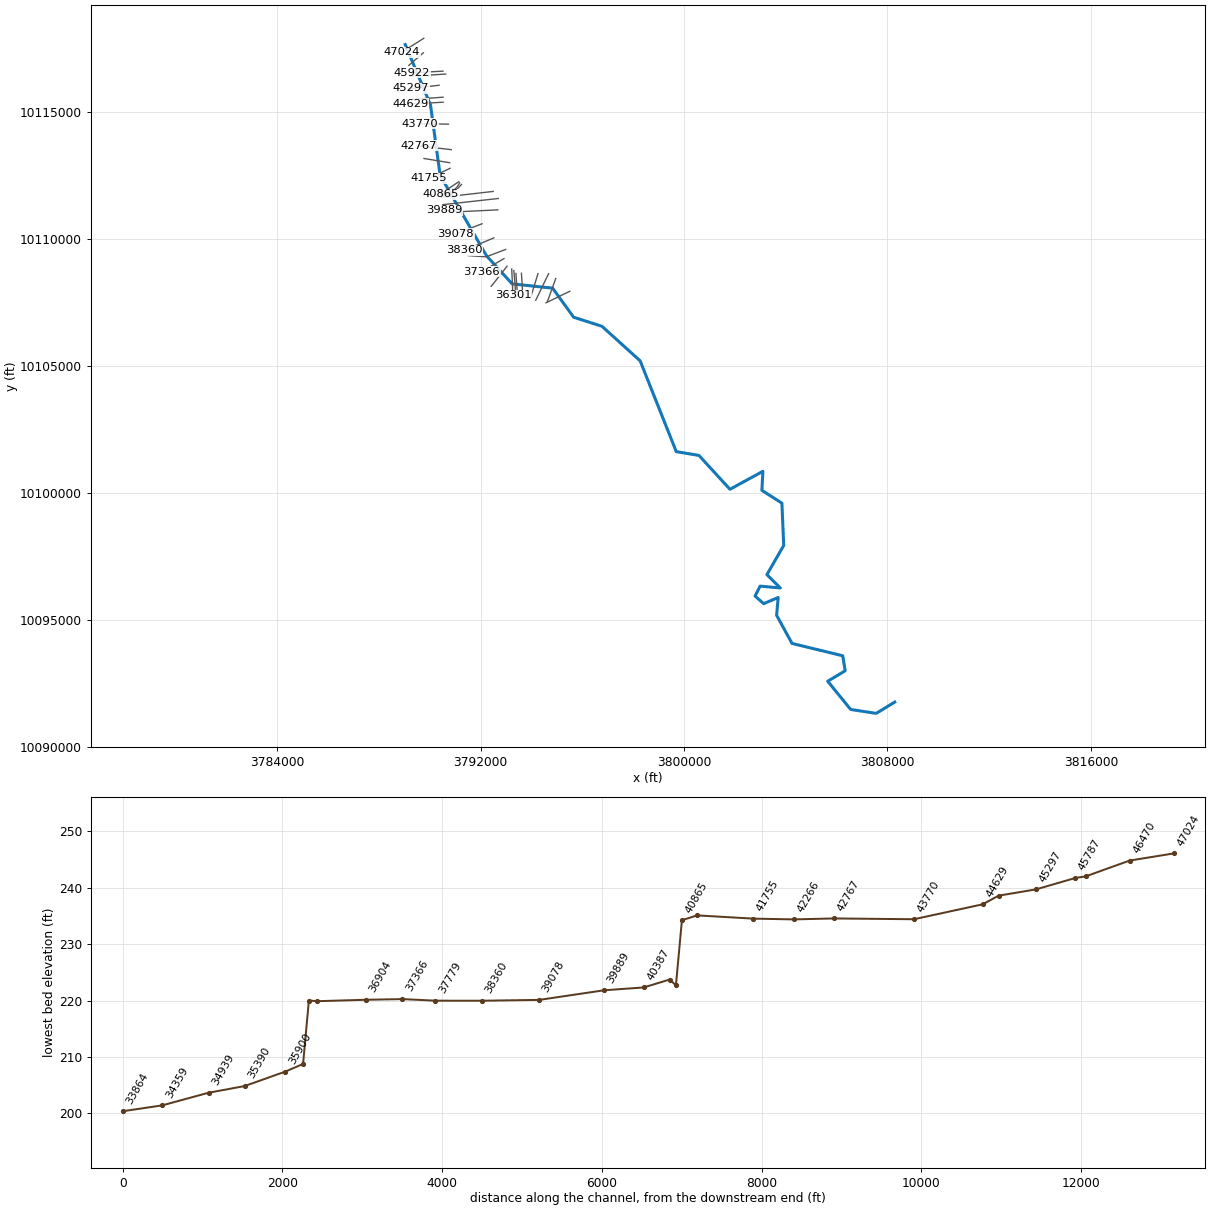
--- FISH CREEK.prj (project) ---

Proj Title=FISH CREEK Base Level Engineering
Current Plan=p01
Default Exp/Contr=0.3,0.1
English Units
Geom File=g01
Flow File=f01
Flow File=f02
Plan File=p01
Y Axis Title=Elevation
X Axis Title(PF)=Main Channel Distance
X Axis Title(XS)=Station
BEGIN DESCRIPTION:
FISH CREEK
END DESCRIPTION:
DSS Export Rating Curves= 0
DSS Export Rating Curve Sorted= 0
DSS Export Volume Flow Curves= 0
DXF OffsetX= 0
DXF OffsetY= 0
DXF ScaleX= 1
DXF ScaleY= 10

--- FISH CREEK.p01 (plan) ---

Plan Title=Multiple Run
Short Identifier=Multiple
Geom File=g01
Flow File=f01
Subcritical Flow
K Sum by GR= 0
Std Step Tol= 0.01
Critical Tol= 0.01
Num of Std Step Trials= 20
Max Error Tol= 0.3
Flow Tol Ratio= 0.001
Split Flow NTrial= 30
Split Flow Tol= 0.02
Split Flow Ratio= 0.02
Log Output Level= 0
Friction Slope Method= 1
Unsteady Friction Slope Method= 2
Unsteady Bridges Friction Slope Method= 1
Parabolic Critical Depth
Global Vel Dist=  1 , 1 , 1
Global Log Level= 0
CheckData=True
Encroach Param= -1, 0, 0, 0
BEGIN DESCRIPTION:
Multiple Run
END DESCRIPTION:

--- FISH CREEK.f01 (steady flow) ---

Flow Title=Multiple
Program Version=4.10
Number of Profiles= 7
Profile Names=10-year,25-year,50-year,1pct_min,100-year,1pct_plu,500-year
River Rch & RM=FISH CREEK,Reach-1         ,47024
     615     824    1107     489    1477    4460    2714
River Rch & RM=FISH CREEK,Reach-1         ,43770
     706     948    1273     561    1695    5119    3111
River Rch & RM=FISH CREEK,Reach-1         ,40865
     976    1331    1806     803    2426    7326    4530
River Rch & RM=FISH CREEK,Reach-1         ,36122
    1291    1790    2455    1105    3336   10075    6373
River Rch & RM=FISH CREEK,Reach-1         ,32943
    1502    2087    2868    1291    3900   11778    7460
River Rch & RM=FISH CREEK,Reach-1         ,28323
    1747    2442    3368    1521    4594   13874    8844
River Rch & RM=FISH CREEK,Reach-1         ,23189
    1957    2745    3794    1717    5184   15655   10016
River Rch & RM=FISH CREEK,Reach-1         ,11892
    2109    2959    4093    1851    5591   16885   10803
Boundary for River Rch & Prof#=FISH CREEK,Reach-1         , 1
Up Type= 0
Dn Type= 3
Dn Slope=0.005
Boundary for River Rch & Prof#=FISH CREEK,Reach-1         , 2
Up Type= 0
Dn Type= 3
Dn Slope=0.005
Boundary for River Rch & Prof#=FISH CREEK,Reach-1         , 3
Up Type= 0
Dn Type= 3
Dn Slope=0.005
Boundary for River Rch & Prof#=FISH CREEK,Reach-1         , 4
Up Type= 0
Dn Type= 3
Dn Slope=0.005
Boundary for River Rch & Prof#=FISH CREEK,Reach-1         , 5
Up Type= 0
Dn Type= 3
Dn Slope=0.005
Boundary for River Rch & Prof#=FISH CREEK,Reach-1         , 6
Up Type= 0
Dn Type= 3
Dn Slope=0.005
Boundary for River Rch & Prof#=FISH CREEK,Reach-1         , 7
Up Type= 0
Dn Type= 3
Dn Slope=0.005
DSS Import GetInterval= 0
DSS Import GetPeak= 0
DSS Import FillOption= 0

--- FISH CREEK.f02 (steady flow) ---

Flow Title=Orig_BLE_Flows
Program Version=4.10
Number of Profiles= 7
Profile Names=10-year,25-year,50-year,1pct_min,100-year,1pct_plu,500-year
River Rch & RM=FISH CREEK,Reach-1         ,47024
     615     808     963     376    1136    3430    1578
River Rch & RM=FISH CREEK,Reach-1         ,43770
     706     929    1107     432    1304    3938    1809
River Rch & RM=FISH CREEK,Reach-1         ,40865
     976    1305    1570     618    1866    5635    2634
River Rch & RM=FISH CREEK,Reach-1         ,36122
    1291    1755    2135     850    2566    7750    3705
River Rch & RM=FISH CREEK,Reach-1         ,32943
    1502    2046    2494     993    3000    9060    4337
River Rch & RM=FISH CREEK,Reach-1         ,28323
    1747    2394    2929    1170    3534   10673    5142
River Rch & RM=FISH CREEK,Reach-1         ,23189
    1957    2691    3299    1320    3988   12043    5823
River Rch & RM=FISH CREEK,Reach-1         ,11793
    2109    2901    3559    1424    4301   12990    6281
Boundary for River Rch & Prof#=FISH CREEK,Reach-1         , 1
Up Type= 0
Dn Type= 3
Dn Slope=0.005
Boundary for River Rch & Prof#=FISH CREEK,Reach-1         , 2
Up Type= 0
Dn Type= 3
Dn Slope=0.005
Boundary for River Rch & Prof#=FISH CREEK,Reach-1         , 3
Up Type= 0
Dn Type= 3
Dn Slope=0.005
Boundary for River Rch & Prof#=FISH CREEK,Reach-1         , 4
Up Type= 0
Dn Type= 3
Dn Slope=0.005
Boundary for River Rch & Prof#=FISH CREEK,Reach-1         , 5
Up Type= 0
Dn Type= 3
Dn Slope=0.005
Boundary for River Rch & Prof#=FISH CREEK,Reach-1         , 6
Up Type= 0
Dn Type= 3
Dn Slope=0.005
Boundary for River Rch & Prof#=FISH CREEK,Reach-1         , 7
Up Type= 0
Dn Type= 3
Dn Slope=0.005
DSS Import GetInterval= 0
DSS Import GetPeak= 0
DSS Import FillOption= 0

--- FISH CREEK.g01 (geometry) ---

Geom Title=Existing Conditions
Program Version=4.10

River Reach=FISH CREEK      ,Reach-1
Reach XY= 30
      3789031.92     10117652.37      3790026.53     10115274.43
      3790404.77      10112504.6      3792231.16      10109336.2
      3793237.23      10108232.9      3794828.93     10108064.57
       3795655.2     10106920.92      3796771.41     10106562.74
      3798271.09     10105204.25      3799692.96     10101628.73
      3800583.01     10101481.74      3801803.46     10100147.57
      3803099.52     10100856.03      3803060.88     10100106.05
      3803847.39     10099602.59      3803918.46      10097937.9
      3803258.46     10096789.61      3803785.14     10096265.12
      3802990.67     10096335.83      3802791.08     10095945.28
      3803130.22     10095646.72      3803700.52     10095889.85
       3803639.6     10095188.71      3804245.02     10094080.91
      3806240.31     10093594.74      3806335.44     10093005.16
      3805648.48     10092592.83      3806552.62     10091482.47
      3807554.94     10091328.17      3808284.57     10091771.73

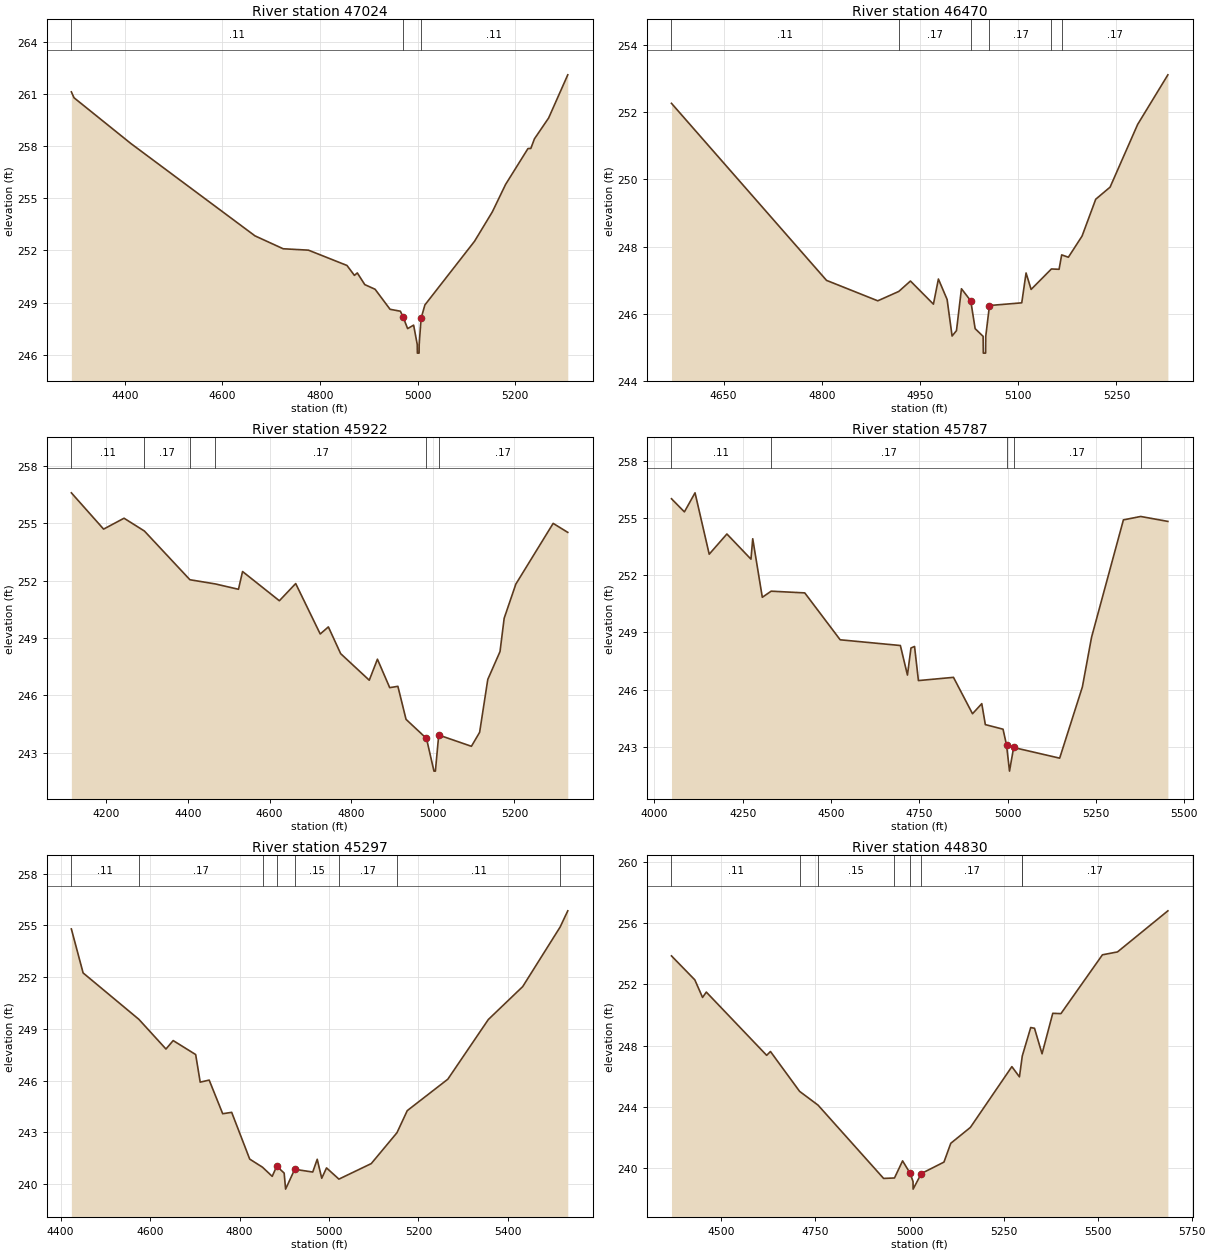
Type RM Length L Ch R = 1 ,47024   ,554,554,554
BEGIN DESCRIPTION:
FISH CREEK 44.0
END DESCRIPTION:
XS GIS Cut Line= 2
      3789761.12     10117896.68      3788900.01     10117355.02
#Sta/Elev= 30
  4290.3  261.11  4295.8  260.77  4412.3  258.14  4666.7  252.83  4724.4  252.09
  4776.2  252.01  4855.1  251.13  4870.4  250.56  4876.3   250.7  4891.6  250.03
  4912.8  249.76  4943.4  248.61  4964.6   248.5  4970.5  248.14  4979.4   247.5
  4991.7   247.7  4999.1  246.59  4999.4  246.09  5002.9  246.09  5003.1  246.59
    5007  248.09  5014.8  248.86  5116.5  252.52    5153  254.21  5180.2  255.79
    5226  257.85  5231.9  257.86  5239.3  258.41  5268.4  259.61  5307.6  262.09
#Mann= 3 , 0 , 0
  4290.3     .11       0  4970.5     .06       0    5007     .11       0
Bank Sta=4970.5,5007
XS Rating Curve= 0 ,0
Exp/Cntr=0.3,0.1

Type RM Length L Ch R = 1 ,46470   ,548,548,548
BEGIN DESCRIPTION:
Mapping XS cd76dc14
END DESCRIPTION:
XS GIS Cut Line= 2
      3789745.94     10117327.53      3789172.97     10116830.97
#Sta/Elev= 30
  4570.4  252.27  4807.2  246.99  4885.5  246.38  4917.6  246.66  4935.4  246.97
  4970.5  246.28  4978.1  247.03  4991.4  246.42    4999  245.33  5005.7  245.49
  5013.3  246.74  5027.5  246.38  5034.2  245.55  5046.4  245.32  5046.7  244.82
  5050.2  244.82  5050.4  245.32  5056.1  246.24  5105.4  246.32    5112  247.21
  5119.7  246.72  5150.7  247.33  5162.4  247.32  5166.4  247.75  5176.6  247.68
  5197.5  248.31  5218.4  249.41  5240.3  249.77  5282.4  251.64  5328.6  253.12
#Mann= 6 ,-1 , 0
  4570.4     .11       0  4917.6     .17       0  5027.5     .09       0
  5056.1     .17       0  5150.7     .11       0  5166.4     .17       0
Bank Sta=5027.5,5056.1
XS Rating Curve= 0 ,0
Exp/Cntr=0.3,0.1

Type RM Length L Ch R = 1 ,45922   ,135,135,135
BEGIN DESCRIPTION:
Mapping XS f3d63e3b
END DESCRIPTION:
XS GIS Cut Line= 2
      3790516.76      10116605.3      3789302.14     10116539.36
#Sta/Elev= 30
  4114.3   256.6  4193.3   254.7  4243.4  255.27  4293.3   254.6  4404.8  252.05
  4467.1  251.83  4523.8  251.55  4533.8  252.48    4624  250.95    4664  251.85
  4724.1  249.21  4744.1  249.58  4774.2  248.18  4844.3  246.79  4864.3  247.89
  4894.4   246.4  4914.4  246.47  4934.4  244.74  4984.5  243.74  5002.8  242.03
  5006.3  242.03  5014.5  243.92  5094.6  243.33  5114.7  244.06  5134.7  246.83
  5164.7  248.29  5174.8  250.03  5203.4  251.82  5294.9     255  5330.7  254.53
#Mann= 6 ,-1 , 0
  4114.3     .11       0  4293.3     .17       0  4404.8     .11       0
  4467.1     .17       0  4984.5     .09       0  5014.5     .17       0
Bank Sta=4984.5,5014.5
XS Rating Curve= 0 ,0
Exp/Cntr=0.3,0.1

Type RM Length L Ch R = 1 ,45787   ,490,490,490
BEGIN DESCRIPTION:
Mapping XS 985c8c4e
END DESCRIPTION:
XS GIS Cut Line= 2
      3790624.39     10116490.71      3789222.19     10116400.47
#Sta/Elev= 30
  4048.1  256.01  4084.7  255.32  4114.8  256.32  4154.9   253.1    4205  254.16
  4273.1  252.84  4278.1  253.91  4305.2  250.84  4330.3  251.16  4425.4  251.07
  4525.6  248.61    4696  248.31    4716  246.76    4726  248.18  4736.1  248.26
  4747.1  246.47  4846.3  246.64  4900.2  244.73  4926.4  245.26  4936.5  244.16
  4986.6  243.92  4996.6  243.08  5004.9  241.72  5016.6  242.96  5146.9   242.4
  5211.2  246.14  5237.1  248.74  5327.3   254.9  5376.3  255.08  5453.2  254.82
#Mann= 5 ,-1 , 0
  4048.1     .11       0  4330.3     .17       0  4996.6     .09       0
  5016.6     .17       0  5376.3     .11       0
Bank Sta=4996.6,5016.6
XS Rating Curve= 0 ,0
Exp/Cntr=0.3,0.1

Type RM Length L Ch R = 1 ,45297   ,467,467,467
BEGIN DESCRIPTION:
Mapping XS 9a76f1ff
END DESCRIPTION:
XS GIS Cut Line= 2
      3790364.01     10116049.75      3789261.35     10115924.92
#Sta/Elev= 30
  4424.1  254.79  4450.4  252.24  4575.1  249.55  4635.6  247.83  4651.7  248.32
    4702  247.51  4712.1  245.91  4732.2  246.03  4762.4  244.08  4782.5  244.16
  4822.8  241.45  4851.4  240.98  4873.1  240.45  4883.2  241.04  4899.8  240.64
    4903  239.71  4923.4  240.86  4963.7   240.7  4973.7  241.44  4983.8  240.34
  4994.5  240.94  5022.2  240.29  5094.5  241.19    5152  242.98    5175  244.26
  5265.6  246.08  5356.2  249.54  5433.1  251.45  5516.7   254.9  5533.8  255.84
#Mann= 8 ,-1 , 0
  4424.1     .11       0  4575.1     .17       0  4851.4     .15       0
  4883.2     .09       0  4923.4     .15       0  5022.2     .17       0
    5152     .11       0  5516.7     .17       0
Bank Sta=4883.2,4923.4
XS Rating Curve= 0 ,0
Exp/Cntr=0.3,0.1

Type RM Length L Ch R = 1 ,44830   ,201,201,201
BEGIN DESCRIPTION:
Mapping XS 025522ac
END DESCRIPTION:
XS GIS Cut Line= 2
      3790520.19     10115580.99      3789204.28     10115483.77
#Sta/Elev= 30
  4367.3  253.87  4429.4   252.3  4449.9  251.15  4459.9   251.5  4620.3  247.36
  4630.4  247.61  4707.9     245  4756.9   244.1  4931.2   239.3  4960.1  239.33
  4981.6  240.45  5001.4  239.65  5009.4   239.1  5009.6   238.6  5031.4  239.62
  5091.6  240.37  5109.7   241.6  5161.8  242.64  5272.1  246.62  5292.2  245.95
  5299.5  247.27  5299.8  247.32  5322.2  249.18  5332.3  249.13  5352.3  247.46
  5380.8  250.11  5402.5  250.09  5512.8  253.94  5552.9  254.13  5686.8  256.82
#Mann= 8 ,-1 , 0
  4367.3     .11       0  4707.9     .17       0  4756.9     .15       0
  4960.1     .17       0  5001.4     .09       0  5031.4     .17       0
  5299.5     .11       0  5299.8     .17       0
Bank Sta=5001.4,5031.4
XS Rating Curve= 0 ,0
Exp/Cntr=0.3,0.1

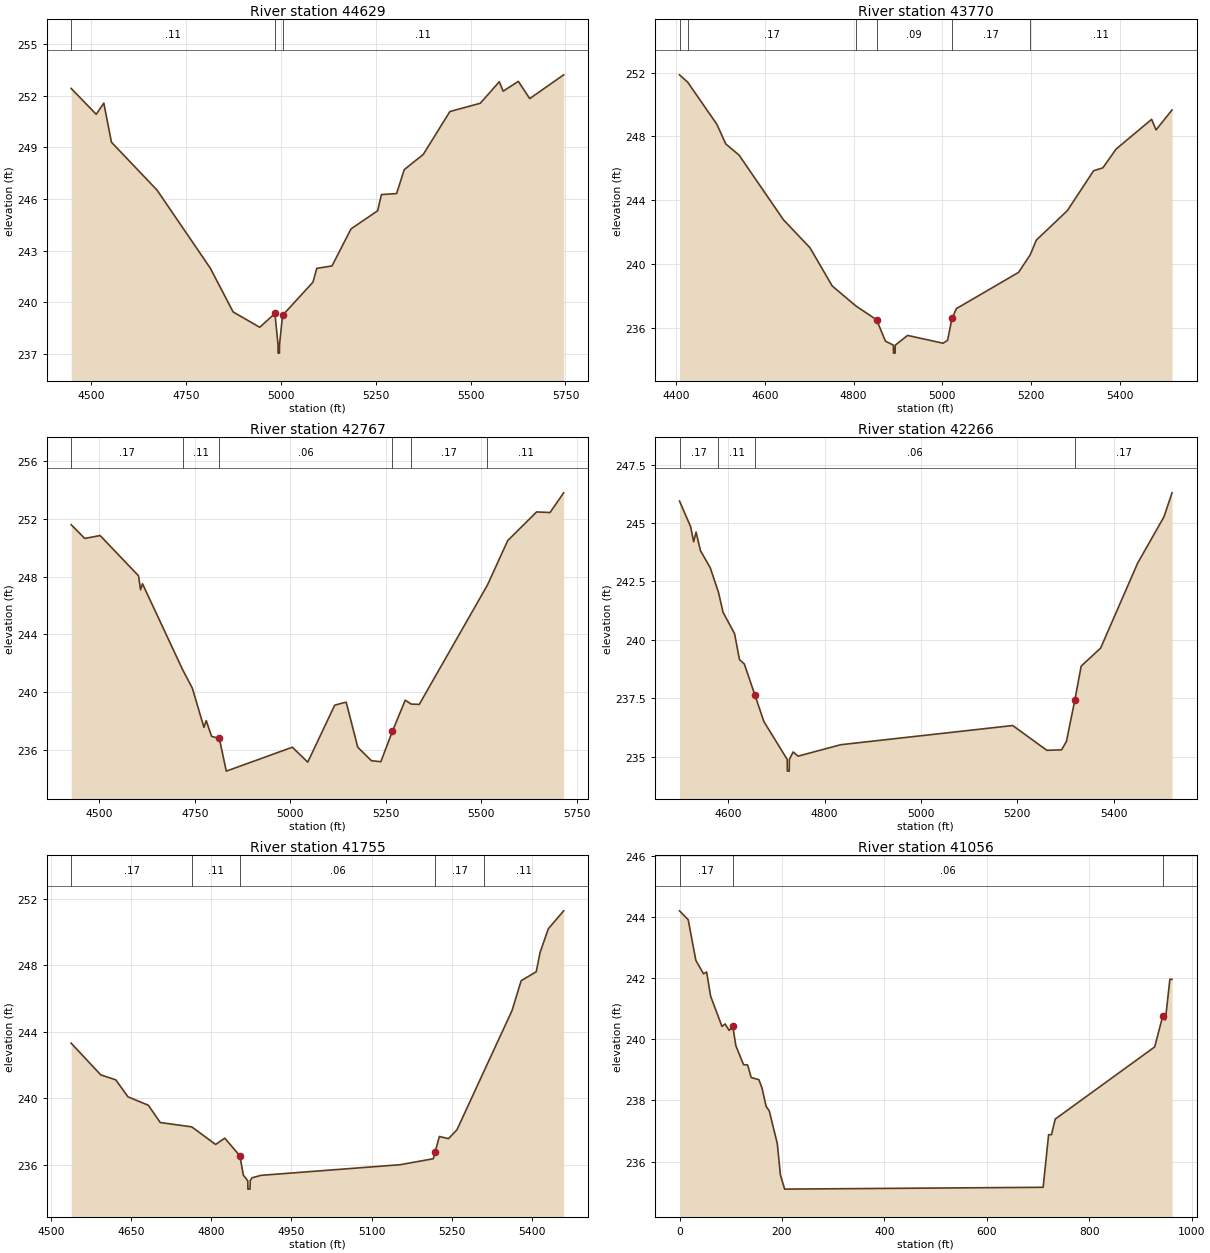
Type RM Length L Ch R = 1 ,44629   ,859,859,859
BEGIN DESCRIPTION:
Mapping XS 211d8c48
END DESCRIPTION:
XS GIS Cut Line= 2
      3790523.74     10115383.08      3789228.59     10115310.16
#Sta/Elev= 30
  4448.1  252.42  4514.1  250.92  4534.1  251.57  4554.2   249.3  4674.3  246.52
  4814.6  241.99  4874.7  239.45  4944.8  238.56  4984.8  239.36  4992.9  237.56
  4993.1  237.06  4996.6  237.06  4996.9  237.56  5004.9  239.25    5085  241.18
    5095  241.98  5135.1  242.12  5185.2  244.27  5255.3  245.32  5265.3  246.26
  5305.3  246.32  5325.4  247.71  5375.5  248.59  5445.6  251.08  5525.7  251.56
  5575.8  252.81  5585.8  252.26  5625.9  252.83  5655.9  251.83  5745.3  253.21
#Mann= 3 ,-1 , 0
  4448.1     .11       0  4984.8     .07       0  5004.9     .11       0
Bank Sta=4984.8,5004.9
XS Rating Curve= 0 ,0
Exp/Cntr=0.3,0.1

Type RM Length L Ch R = 1 ,43770   ,1003,1003,1003
BEGIN DESCRIPTION:
Mapping XS 78235bd9
END DESCRIPTION:
XS GIS Cut Line= 2
      3790731.99     10114518.49      3789621.89     10114539.31
#Sta/Elev= 30
  4407.7  251.86  4426.1   251.4  4491.9  248.76  4511.9  247.53  4541.9  246.83
  4641.9  242.78  4701.9  241.02  4751.9  238.63  4805.1  237.38  4851.9  236.51
  4871.9  235.17  4889.8  234.92  4890.1  234.42  4893.7  234.42    4894  234.92
  4921.9  235.53  5001.9  235.04  5011.9  235.22  5021.9  236.59  5031.9  237.21
    5172  239.48  5198.1  240.57    5212   241.5    5282  243.35  5341.2  245.85
    5362  246.03    5392  247.21    5472  249.07    5482  248.41    5518  249.66
#Mann= 6 ,-1 , 0
  4407.7     .11       0  4426.1     .17       0  4805.1     .11       0
  4851.9     .09       0  5021.9     .17       0  5198.1     .11       0
Bank Sta=4851.9,5021.9
XS Rating Curve= 0 ,0
Exp/Cntr=0.3,0.1

Type RM Length L Ch R = 1 ,42767   ,501,501,501
BEGIN DESCRIPTION:
Mapping XS e3d78770
END DESCRIPTION:
XS GIS Cut Line= 2
      3790843.11     10113515.02      3789562.37     10113664.27
#Sta/Elev= 30
  4426.2  251.58  4461.7  250.63    4502  250.83  4602.6  248.05  4607.9  247.08
  4612.9   247.5  4717.8  241.58  4743.6  240.28  4773.8  237.58  4779.8  238.05
  4793.9  236.96  4814.1  236.82  4832.3  234.56  5005.3  236.21  5045.6  235.18
  5116.1  239.11  5136.2  239.26  5146.3  239.32  5176.5  236.21  5212.3  235.28
  5236.9  235.21  5267.1   237.3  5300.8  239.46  5316.4  239.19  5337.6  239.17
    5516  247.41  5569.1  250.48  5644.7  252.46  5679.9  252.42  5715.6  253.78
#Mann= 6 ,-1 , 0
  4426.2     .17       0  4717.8     .11       0  4814.1     .06       0
  5267.1     .15       0  5316.4     .17       0    5516     .11       0
Bank Sta=4814.1,5267.1
XS Rating Curve= 0 ,0
Exp/Cntr=0.3,0.1

Type RM Length L Ch R = 1 ,42266   ,511,511,511
BEGIN DESCRIPTION:
Mapping XS c12c9c8e
END DESCRIPTION:
XS GIS Cut Line= 2
      3790780.67     10113001.13      3789771.51     10113167.59
#Sta/Elev= 30
  4498.6  245.94  4521.7  244.84  4527.9   244.2    4533  244.61    4542  243.82
  4562.3  243.09  4579.3  242.05    4589  241.18  4612.9  240.27  4623.1  239.16
  4633.2  238.97  4655.2  237.64  4673.8  236.51  4722.2  234.89  4722.5  234.39
  4726.4  234.39  4726.7  234.89  4734.6  235.21  4744.7  235.03  4833.5  235.52
  5190.6  236.34  5261.4  235.28    5292   235.3  5302.1  235.66 5319.57  237.43
  5332.7  238.88  5373.1  239.65  5449.9  243.28  5504.8  245.27  5521.4  246.29
#Mann= 4 ,-1 , 0
  4498.6     .17       0  4579.3     .11       0  4655.2     .06       0
 5319.57     .17       0
Bank Sta=4655.2,5319.57
XS Rating Curve= 0 ,0
Exp/Cntr=0.3,0.1

Type RM Length L Ch R = 1 ,41755   ,699,699,699
BEGIN DESCRIPTION:
Mapping XS 3e523324
END DESCRIPTION:
XS GIS Cut Line= 2
      3790797.97     10112782.36      3789968.14     10112383.07
#Sta/Elev= 30
  4538.2  243.32  4593.6  241.41  4621.7  241.11  4644.4  240.09  4682.6  239.58
  4704.8  238.54  4763.7  238.28  4808.3  237.22  4825.4   237.6  4853.6  236.54
  4860.2  235.37  4868.4  235.03  4868.7  234.53  4872.6  234.53    4873  235.03
  4876.2  235.21  4893.3  235.36  5153.3     236  5215.3  236.36  5218.7  236.76
  5226.7   237.7  5243.8  237.57  5259.7  238.11  5310.1  241.63  5362.5  245.28
  5379.6  247.08  5407.8  247.62    5415  248.78  5430.4  250.21  5459.1  251.29
#Mann= 5 ,-1 , 0
  4538.2     .17       0  4763.7     .11       0  4853.6     .06       0
  5218.7     .17       0  5310.1     .11       0
Bank Sta=4853.6,5218.7
XS Rating Curve= 0 ,0
Exp/Cntr=0.3,0.1

Type RM Length L Ch R = 1 ,41056   ,191,191,191
BEGIN DESCRIPTION:
Mapping XS 9b0f2a3f
END DESCRIPTION:
XS GIS Cut Line= 3
      3791138.28      10112254.6      3790537.12     10111850.84
      3790304.68     10111899.69
#Sta/Elev= 30
       0   244.2    16.9  243.91    31.9  242.58    46.9  242.14    52.9   242.2
    60.7  241.41    82.9  240.42      89   240.5    96.9  240.29   103.9  240.43
     110  239.79     125  239.17     133  239.16   139.9  238.75   154.9  238.68
     161  238.41   169.2   237.8   175.2  237.66   190.9  236.59     197  235.56
   205.3   235.1     710  235.16   720.7  236.88   726.3  236.88   733.6  237.39
   927.8  239.75   943.6  240.76   948.7  240.63   957.5  241.96   961.7  241.96
#Mann= 3 ,-1 , 0
       0     .17       0   103.9     .06       0   943.6     .17       0
Bank Sta=103.9,943.6
XS Rating Curve= 0 ,0
Exp/Cntr=0.3,0.1

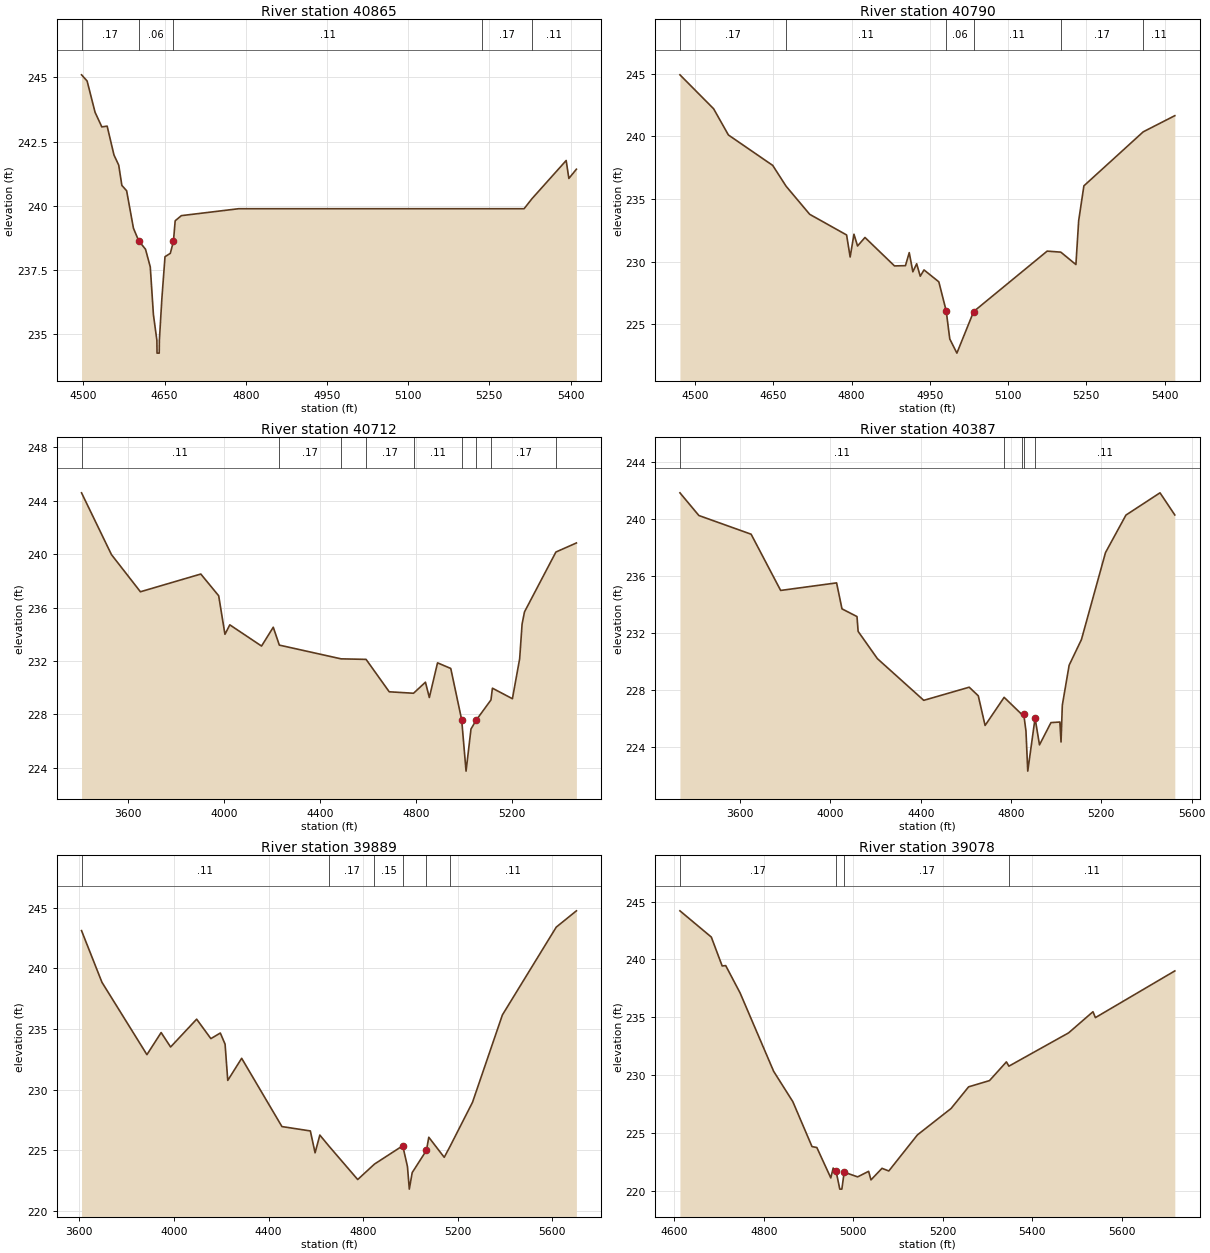
Type RM Length L Ch R = 1 ,40865   ,75,75,75
BEGIN DESCRIPTION:
Mapping XS 4a49fefe
END DESCRIPTION:
XS GIS Cut Line= 6
      3791169.54     10112202.54      3791079.58       10112052.
      3790881.66     10111847.31      3790820.72      10111814.5
      3790725.09     10111789.32      3790441.56      10111754.7
#Sta/Elev= 30
  4496.7   245.1    4507  244.86  4521.7  243.64  4534.2  243.07    4544   243.1
  4556.7  241.97  4565.4  241.58  4571.2  240.79    4580  240.58  4592.6  239.12
  4602.3  238.63  4614.9   238.3  4623.7  237.61  4629.5  235.75  4635.9  234.75
  4636.2  234.25  4640.2  234.25  4640.5  234.75  4645.1  236.37  4650.9  238.01
  4660.7  238.14  4666.5  238.61  4669.7  239.41  4681.1  239.61    4787  239.88
  5314.3  239.88  5328.8  240.27    5392  241.76    5397  241.06  5410.9  241.42
#Mann= 5 ,-1 , 0
  4496.7     .17       0  4602.3     .06       0  4666.5     .11       0
  5237.1     .17       0  5328.8     .11       0
Bank Sta=4602.3,4666.5
XS Rating Curve= 0 ,0
Exp/Cntr=0.3,0.1

Type RM Length L Ch R = 1 ,40790   ,78,78,78
BEGIN DESCRIPTION:
Mapping XS 9b490ce5
END DESCRIPTION:
XS GIS Cut Line= 3
      3791245.92     10112144.36      3790885.68     10111762.42
      3790464.71     10111714.68
#Sta/Elev= 30
    4471   244.9  4535.6  242.19  4563.9   240.1  4648.9  237.67  4674.5  236.01
  4719.7  233.77  4790.5  232.12  4797.3  230.36  4804.6  232.18  4811.5  231.24
  4825.7  231.92  4882.3  229.65  4903.3  229.67  4910.6  230.71  4917.5  229.18
  4924.8  229.82  4931.7  228.83  4938.9  229.33  4967.3  228.38  4981.4  226.07
  4988.3  223.82  5001.9  222.69  5034.1  226.01    5175  230.83  5201.1  230.75
  5230.1  229.76  5235.4  233.26  5245.4  236.04  5359.1  240.35  5419.7  241.64
#Mann= 6 ,-1 , 0
    4471     .17       0  4674.5     .11       0  4981.4     .06       0
  5034.1     .11       0  5201.1     .17       0  5359.1     .11       0
Bank Sta=4981.4,5034.1
XS Rating Curve= 0 ,0
Exp/Cntr=0.3,0.1

Type RM Length L Ch R = 1 ,40712   ,325,325,325
BEGIN DESCRIPTION:
Mapping XS bc74f806
END DESCRIPTION:
XS GIS Cut Line= 2
      3792491.61     10111870.93      3790442.97     10111636.55
#Sta/Elev= 30
  3406.4   244.6    3531  239.97  3651.7  237.18  3903.4  238.51  3977.9  236.88
    4004  233.99  4024.2   234.7  4156.5  233.11  4205.3  234.52  4230.6  233.18
  4487.8  232.15  4592.1  232.11  4688.5  229.68  4789.8  229.57  4839.4   230.4
  4855.6  229.25  4889.8  231.85  4944.9  231.43  4990.4  227.58  5008.6  223.73
  5029.2  226.89  5050.8  227.55  5112.4  229.07  5118.5  229.95  5201.8  229.16
    5232  232.16  5242.1  234.76  5252.1  235.67    5383  240.16  5468.4  240.84
#Mann= 9 ,-1 , 0
  3406.4     .11       0  4230.6     .17       0  4487.8     .11       0
  4592.1     .17       0  4789.8     .11       0  4990.4     .06       0
  5050.8     .11       0  5112.4     .17       0    5383     .11       0
Bank Sta=4990.4,5050.8
XS Rating Curve= 0 ,0
Exp/Cntr=0.3,0.1

Type RM Length L Ch R = 1 ,40387   ,498,498,498
BEGIN DESCRIPTION:
Mapping XS d3d295bf
END DESCRIPTION:
XS GIS Cut Line= 2
      3792691.23     10111593.14      3790512.64     10111350.11
#Sta/Elev= 30
  3333.3  241.83  3417.2  240.24  3648.6  238.93  3779.4  234.99  4027.2  235.52
  4051.1   233.7  4117.6  233.16  4122.6  232.12    4208  230.21  4413.3  227.29
  4614.6  228.21  4654.8  227.61    4685  225.53  4769.4   227.5  4848.6  226.29
  4856.1  226.34  4866.1  225.13    4874  222.33  4906.4  226.04    4926  224.17
  4976.8  225.73  5016.3  225.77  5021.4  224.37  5027.1  226.95  5057.3  229.75
  5111.8  231.55  5218.3  237.64  5308.9  240.27  5459.8  241.83  5525.4  240.28
#Mann= 5 ,-1 , 0
  3333.3     .11       0  4769.4     .17       0  4848.6     .11       0
  4856.1     .07       0  4906.4     .11       0
Bank Sta=4856.1,4906.4
XS Rating Curve= 0 ,0
Exp/Cntr=0.3,0.1

Type RM Length L Ch R = 1 ,39889   ,811,811,811
BEGIN DESCRIPTION:
Mapping XS db7492cf
END DESCRIPTION:
XS GIS Cut Line= 3
       3792673.9      10111146.1       3791254.6     10111076.65
      3790586.18     10111133.08
#Sta/Elev= 30
  3609.6   243.1  3695.8  238.85    3886  232.89  3946.1  234.71  3986.1  233.52
  4096.2  235.81  4156.3  234.21  4196.3  234.67  4216.4  233.75  4227.7  230.77
  4286.5  232.59  4456.7  226.97  4576.8  226.61  4596.8  224.81  4616.9  226.27
    4656  225.35    4777  222.61  4847.8  223.88  4967.3  225.39  4987.3  223.68
  4995.1  221.82  5007.3  223.18  5067.5  225.01  5077.5  226.09  5142.7  224.44
  5165.8  225.28  5262.3  228.97  5388.6  236.16  5616.3  243.39  5701.4  244.73
#Mann= 6 ,-1 , 0
  3609.6     .11       0    4656     .17       0  4847.8     .15       0
  4967.3     .09       0  5067.5     .17       0  5165.8     .11       0
Bank Sta=4967.3,5067.5
XS Rating Curve= 0 ,0
Exp/Cntr=0.3,0.1

Type RM Length L Ch R = 1 ,39078   ,718,718,718
BEGIN DESCRIPTION:
Mapping XS 89c40e0c
END DESCRIPTION:
XS GIS Cut Line= 2
      3792053.23     10110599.23      3791021.53     10110200.42
#Sta/Elev= 30
  4612.6   244.2  4682.7  241.93    4707  239.43  4714.9  239.46    4747   237.1
  4822.1  230.31  4864.9  227.69  4907.8   223.8  4918.6  223.72  4949.8  221.09
  4955.1  221.94  4961.4   221.7  4969.9  220.12  4974.5  220.12  4979.7  221.59
  5009.7  221.18  5034.3  221.66  5039.6  220.92  5064.2  221.92  5079.4  221.69
  5143.3  224.81  5218.7   227.1  5257.8  228.97  5304.5  229.51  5342.3  231.13
  5347.9  230.76  5481.3  233.64  5535.8  235.47  5541.2  234.96  5718.7     239
#Mann= 4 ,-1 , 0
  4612.6     .17       0  4961.4     .09       0  4979.7     .17       0
  5347.9     .11       0
Bank Sta=4961.4,4979.7
XS Rating Curve= 0 ,0
Exp/Cntr=0.3,0.1

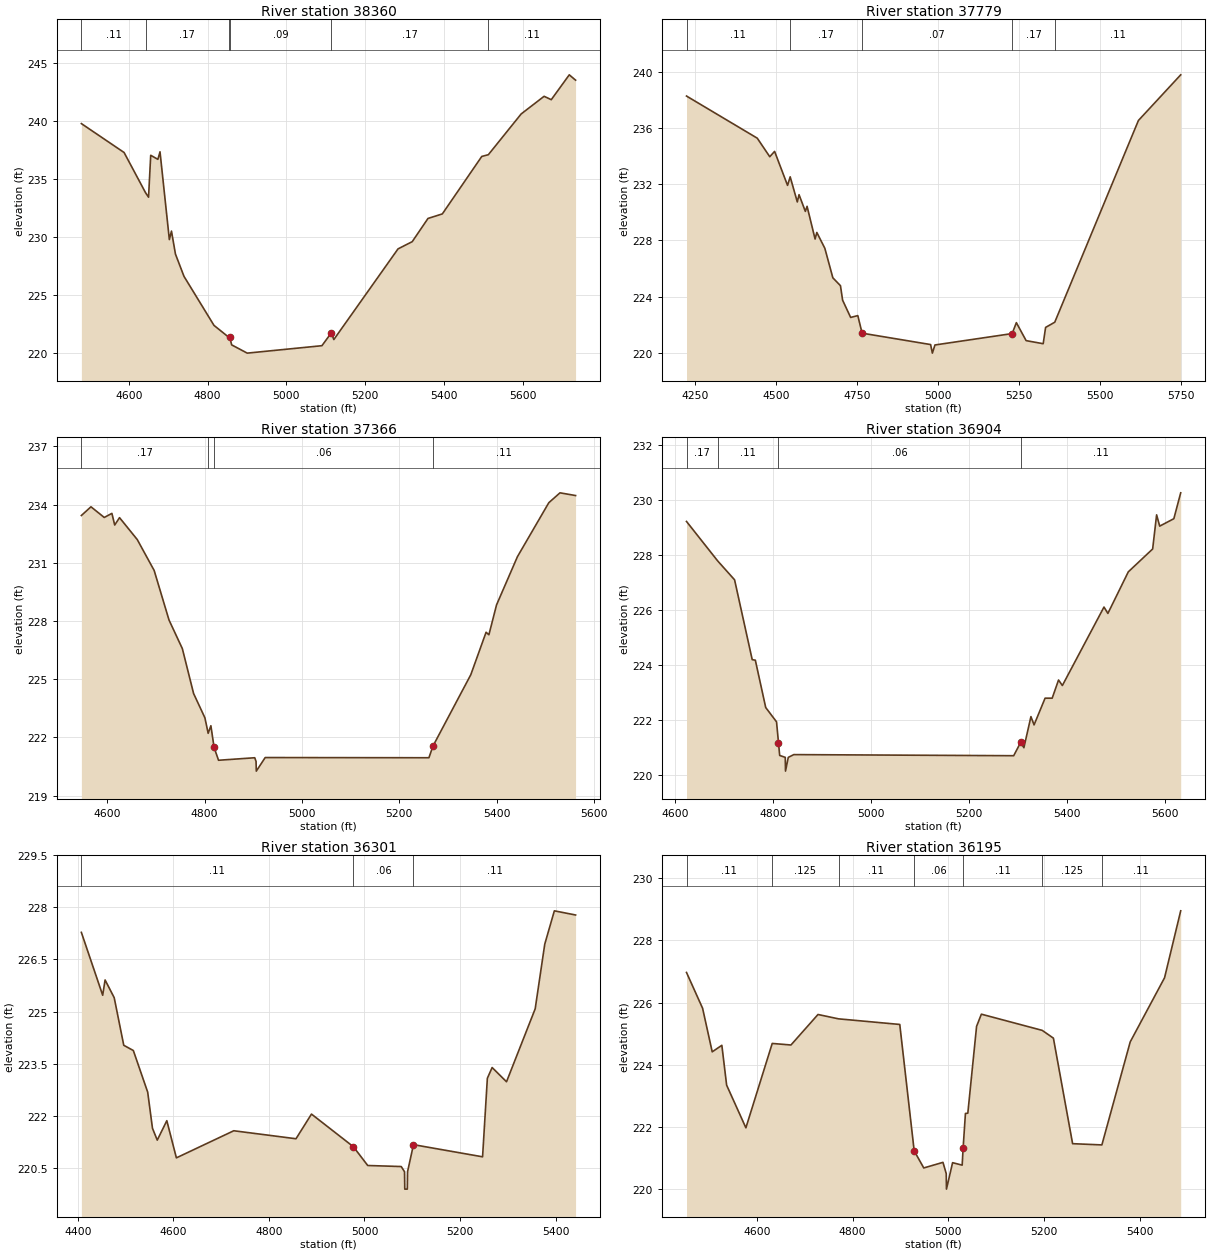
Type RM Length L Ch R = 1 ,38360   ,581,581,581
BEGIN DESCRIPTION:
Mapping XS b357f1a1
END DESCRIPTION:
XS GIS Cut Line= 2
      3792517.62     10110043.67      3791363.08      10109553.2
#Sta/Elev= 30
  4479.7  239.74  4588.1  237.25  4642.7  233.78  4650.2   233.4  4655.7  237.01
  4673.9  236.66  4679.3  237.31    4703  229.75  4708.4  230.48  4718.5   228.5
  4740.2  226.58  4816.3  222.36  4853.7  221.34  4855.7   221.4  4861.2  220.68
  4900.7  219.97  5090.3  220.61    5114  221.71  5120.5  221.14  5283.5  228.95
  5319.5  229.57  5359.5  231.57  5395.9  231.96    5496  236.91  5512.7  237.06
    5596  240.57  5654.2  242.09  5672.4   241.8  5718.1  243.94  5734.1  243.48
#Mann= 6 ,-1 , 0
  4479.7     .11       0  4642.7     .17       0  4853.7     .11       0
  4855.7     .09       0    5114     .17       0  5512.7     .11       0
Bank Sta=4855.7,5114
XS Rating Curve= 0 ,0
Exp/Cntr=0.3,0.1

Type RM Length L Ch R = 1 ,37779   ,413,413,413
BEGIN DESCRIPTION:
Mapping XS 2ee74c8f
END DESCRIPTION:
XS GIS Cut Line= 3
        3792982.     10109587.93      3792218.14     10109297.14
      3791511.78     10109344.81
#Sta/Elev= 30
  4224.5  238.28  4442.9  235.28  4481.5  233.96  4496.4  234.34  4536.4  231.92
  4544.5  232.53  4566.5  230.74  4571.8  231.26  4591.3  230.07  4596.6  230.43
  4621.4   228.1  4626.7  228.57  4651.5  227.44  4676.2  225.34  4699.7  224.78
  4706.3  223.75  4731.1  222.52  4753.2  222.65  4766.5   221.4  4977.9  220.59
  4983.4  219.98  4991.3  220.56 5229.67221.3716  5242.6  222.15  5272.7  220.87
  5325.4  220.65  5332.8  221.81  5361.1  222.18  5619.3  236.54  5749.8  239.79
#Mann= 5 ,-1 , 0
  4224.5     .11       0  4544.5     .17       0  4766.5     .07       0
 5229.67     .17       0  5361.1     .11       0
Bank Sta=4766.5,5229.67
XS Rating Curve= 0 ,0
Exp/Cntr=0.3,0.1

Type RM Length L Ch R = 1 ,37366   ,462,462,462
BEGIN DESCRIPTION:
Mapping XS af8c599a
END DESCRIPTION:
XS GIS Cut Line= 2
      3792916.97     10109227.72       3792040.2     10108715.55
#Sta/Elev= 30
  4546.8  233.44  4566.5  233.89  4593.8  233.34  4609.5  233.55  4615.3  232.95
  4625.2  233.33  4661.6   232.2  4696.3  230.61  4726.9  228.05  4754.2  226.58
  4777.4  224.26  4800.6  223.01  4807.3  222.21  4812.9   222.6  4819.5  221.48
  4828.6  220.82    4903  220.95  4905.7  220.76  4906.2  220.26  4924.5  220.96
  5260.9  220.95 5269.26221.5554  5346.9  225.23  5378.3  227.42  5384.1  227.29
  5399.8  228.83  5442.8  231.32  5507.2   234.1  5530.2  234.61  5562.2  234.47
#Mann= 4 ,-1 , 0
  4546.8     .17       0  4807.3     .11       0  4819.5     .06       0
 5269.26     .11       0
Bank Sta=4819.5,5269.26
XS Rating Curve= 0 ,0
Exp/Cntr=0.3,0.1

Type RM Length L Ch R = 1 ,36904   ,603,603,603
BEGIN DESCRIPTION:
Mapping XS 575d3df8
END DESCRIPTION:
XS GIS Cut Line= 2
      3793038.48     10108928.24      3792414.27     10108134.98
#Sta/Elev= 30
  4623.1  229.21  4686.6  227.78  4721.3  227.09  4757.3  224.19  4763.7  224.17
  4784.9  222.45    4807  221.93    4811221.1675  4813.4  220.71  4824.8  220.64
  4825.3  220.14    4831  220.64  4842.3  220.74  5291.4   220.7  5305.8  221.19
  5312.2  220.99  5326.6  222.12    5333  221.82  5355.5  222.79    5370  222.79
    5383  223.45  5390.8  223.25  5475.8   226.1  5483.8  225.87  5525.5  227.38
  5575.2  228.21  5583.3  229.45  5589.6  229.04  5618.5  229.31  5632.5  230.25
#Mann= 4 ,-1 , 0
  4623.1     .17       0  4686.6     .11       0    4811     .06       0
  5305.8     .11       0
Bank Sta=4811,5305.8
XS Rating Curve= 0 ,0
Exp/Cntr=0.3,0.1

Type RM Length L Ch R = 1 ,36301   ,106,106,106
BEGIN DESCRIPTION:
Mapping XS 812b360f
END DESCRIPTION:
XS GIS Cut Line= 2
      3793220.75     10108819.68      3793268.49     10107786.68
#Sta/Elev= 30
  4407.7  227.28  4452.3  225.47  4457.3  225.91  4476.4   225.4  4496.4  224.03
  4516.4  223.88  4546.5  222.68  4556.5  221.64  4566.5   221.3  4586.5  221.86
  4606.5  220.79  4726.6  221.57  4856.8  221.34  4889.2  222.05  4976.9  221.11
  5006.9  220.57    5077  220.54  5083.9  220.39  5084.4  219.89  5089.7  219.89
  5090.2  220.39  5102.6  221.17  5247.2  220.82  5257.2  223.08  5267.2  223.39
  5297.3  222.98  5357.3  225.08  5377.3  226.94  5397.4   227.9  5441.8  227.78
#Mann= 3 , 0 , 0
  4407.7     .11       0  4976.9     .06       0  5102.6     .11       0
Bank Sta=4976.9,5102.6
XS Rating Curve= 0 ,0
Exp/Cntr=0.3,0.1

Type RM Length L Ch R = 1 ,36195   ,73,73,73
BEGIN DESCRIPTION:
Mapping XS ef482e10
END DESCRIPTION:
XS GIS Cut Line= 4
      3793303.21     10108754.56      3793342.27     10108324.92
      3793363.97     10108012.42      3793385.67     10107726.01
#Sta/Elev= 30
  4453.2  226.97  4486.8  225.82  4506.9  224.42    4527  224.63    4537  223.35
  4577.2  221.98  4632.2  224.69  4671.3  224.64  4727.8  225.62  4770.6  225.48
  4898.5   225.3  4928.6  221.24  4948.6  220.69  4988.7  220.87  4995.5  220.51
    4996  220.01  5008.8  220.86  5028.8  220.78 5030.75  221.32  5035.6  222.44
  5040.6  222.45  5058.9  225.24  5068.9  225.63  5195.9  225.11  5219.3  224.86
  5259.4  221.47  5320.5  221.43  5379.7  224.74  5451.4   226.8  5485.1  228.95
#Mann= 7 ,-1 , 0
  4453.2     .11       0  4632.2    .125       0  4770.6     .11       0
  4928.6     .06       0 5030.75     .11       0  5195.9    .125       0
  5320.5     .11       0
Bank Sta=4928.6,5030.75
XS Rating Curve= 0 ,0
Exp/Cntr=0.3,0.1

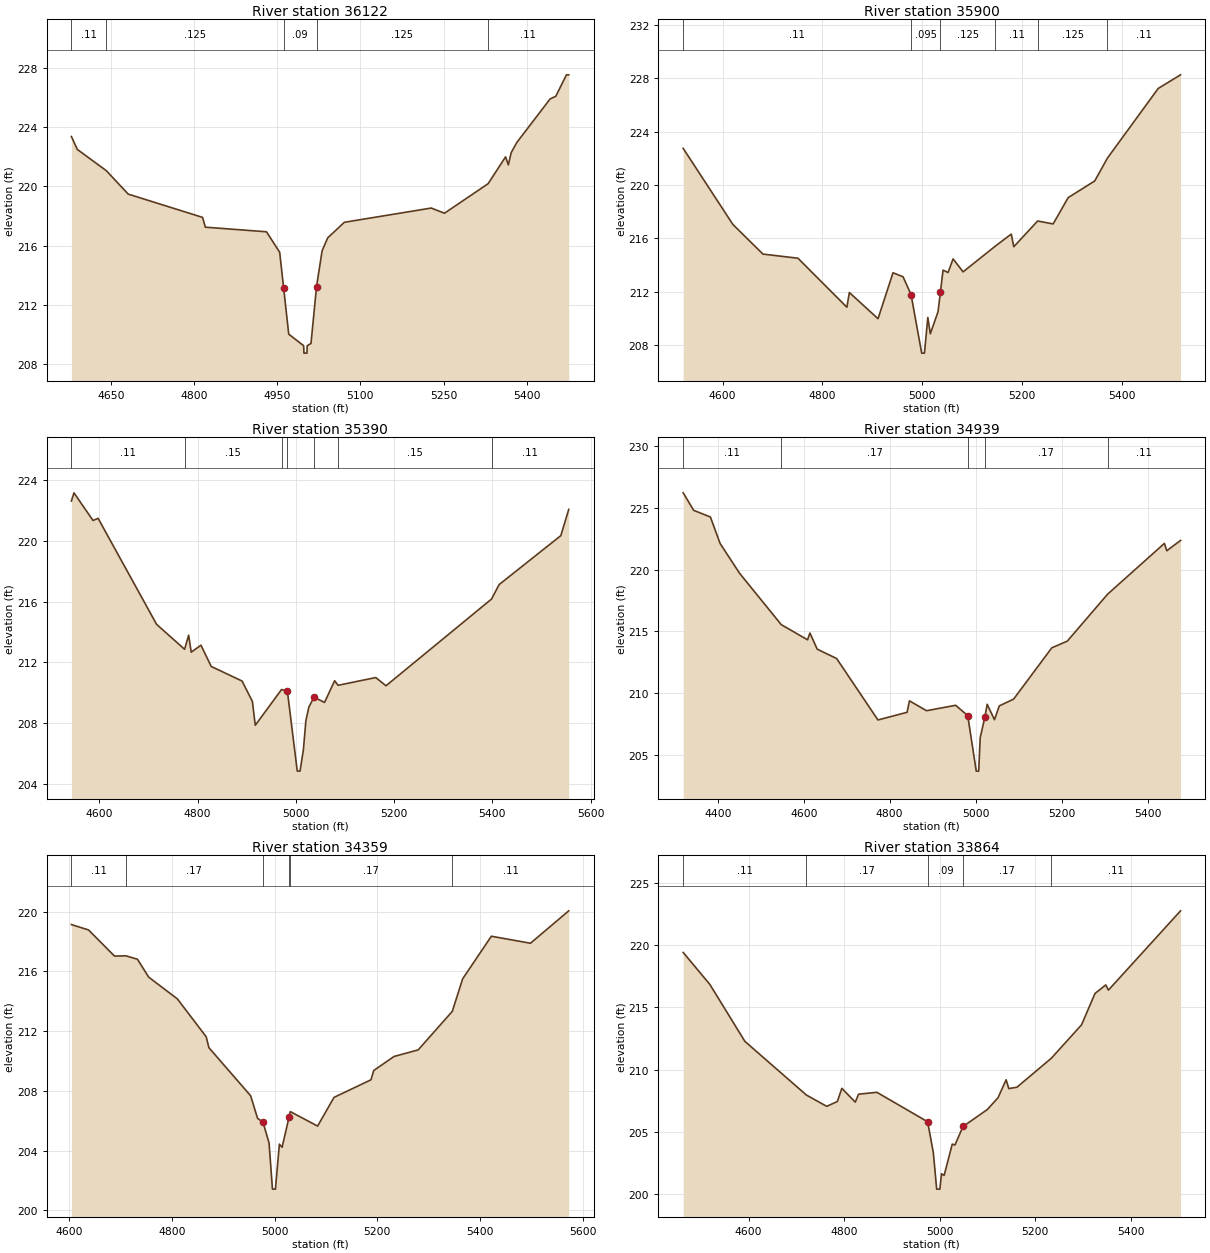
Type RM Length L Ch R = 1 ,36122   ,222,222,222
BEGIN DESCRIPTION:
Mapping XS 7eab3bf7
END DESCRIPTION:
XS GIS Cut Line= 2
      3793385.68     10108641.73      3793450.78     10107747.69
#Sta/Elev= 30
  4579.1  223.36  4589.8  222.49    4642  221.06  4681.5  219.48  4815.5  217.91
  4820.5  217.25  4930.7  216.94  4954.5  215.56 4961.61213.1522  4970.8  210.04
  4997.7  209.26  4998.2  208.76  5003.6  208.76  5004.1  209.26  5010.9  209.41
  5020.9  213.24  5030.9  215.65    5041  216.53  5071.1  217.58  5227.6  218.54
  5251.5  218.19  5330.1  220.18  5361.6  221.99  5366.6  221.45  5371.8  222.28
  5381.9  222.96    5442   225.9  5452.1  226.07  5471.3  227.52  5475.5  227.52
#Mann= 5 ,-1 , 0
  4579.1     .11       0    4642    .125       0 4961.61     .09       0
  5020.9    .125       0  5330.1     .11       0
Bank Sta=4961.61,5020.9
XS Rating Curve= 0 ,0
Exp/Cntr=0.3,0.1

Type RM Length L Ch R = 1 ,35900   ,510,510,510
BEGIN DESCRIPTION:
Mapping XS 633dee4d
END DESCRIPTION:
XS GIS Cut Line= 2
      3793602.69     10108650.43      3793663.46     10107656.48
#Sta/Elev= 30
  4521.2  222.75  4620.7  217.05  4680.9  214.83    4751  214.52  4848.9  210.85
  4853.9  211.95  4911.3  209.99  4941.3  213.43  4961.4  213.13  4977.5  211.79
  4998.7  207.41  5004.2  207.41    5011  210.08    5016  208.86  5031.5  210.52
 5036.22 211.988  5041.5  213.63  5051.5  213.45  5061.6  214.47  5081.6   213.5
  5146.3  215.43  5178.1  216.33  5183.1  215.38  5230.9  217.31  5261.9  217.09
    5292  219.06  5345.2  220.31  5370.6  222.02  5472.3  227.24    5517  228.26
#Mann= 6 ,-1 , 0
  4521.2     .11       0  4977.5    .095       0 5036.22    .125       0
  5146.3     .11       0  5230.9    .125       0  5370.6     .11       0
Bank Sta=4977.5,5036.22
XS Rating Curve= 0 ,0
Exp/Cntr=0.3,0.1

Type RM Length L Ch R = 1 ,35390   ,451,451,451
BEGIN DESCRIPTION:
Mapping XS 5c393e53
END DESCRIPTION:
XS GIS Cut Line= 2
      3794253.73     10108633.09      3793954.39     10107665.64
#Sta/Elev= 30
    4543  222.62  4548.2  223.16    4587  221.34  4597.4  221.48  4716.5   214.5
  4773.5  212.86  4781.7  213.79    4787  212.67  4806.8  213.13  4827.7  211.73
  4890.5  210.77  4911.5  209.43  4917.4  207.86  4970.8  210.21  4982.7  210.12
  5002.9  204.84  5008.5  204.84  5015.3  206.23  5020.5  208.18  5026.6  209.06
  5037.1  209.71  5058.4  209.36    5079  210.79    5086  210.49  5162.7     211
  5183.6  210.46  5398.5  216.17  5413.9  217.12  5539.5  220.34  5555.7  222.07
#Mann= 7 ,-1 , 0
    4543     .11       0  4773.5     .15       0  4970.8     .17       0
  4982.7     .09       0  5037.1     .17       0    5086     .15       0
  5398.5     .11       0
Bank Sta=4982.7,5037.1
XS Rating Curve= 0 ,0
Exp/Cntr=0.3,0.1

Type RM Length L Ch R = 1 ,34939   ,580,580,580
BEGIN DESCRIPTION:
Mapping XS d0cd5ef7
END DESCRIPTION:
XS GIS Cut Line= 2
      3794670.39     10108633.06      3794166.94     10107591.44
#Sta/Elev= 30
  4319.7  226.23  4344.1  224.81    4383  224.27  4405.6  222.12  4450.8  219.71
  4547.8  215.54    4609  214.31  4614.5  214.86  4631.5  213.55  4676.7  212.79
  4772.7  207.81  4840.5  208.43    4846  209.36  4885.7  208.56  4953.5     209
  4981.6  208.16  5001.4  203.66  5007.1  203.66  5010.5  206.36  5021.2  208.01
  5026.8  209.08  5043.8  207.83    5055  208.95  5088.3   209.5  5177.1  213.66
  5213.1   214.2  5306.9  218.01  5439.1  222.13  5444.6  221.53  5476.6  222.37
#Mann= 5 ,-1 , 0
  4319.7     .11       0  4547.8     .17       0  4981.6     .09       0
  5021.2     .17       0  5306.9     .11       0
Bank Sta=4981.6,5021.2
XS Rating Curve= 0 ,0
Exp/Cntr=0.3,0.1

Type RM Length L Ch R = 1 ,34359   ,495,495,495
BEGIN DESCRIPTION:
Mapping XS c601519e
END DESCRIPTION:
XS GIS Cut Line= 2
      3794952.52     10108442.11      3794622.76     10107530.94
#Sta/Elev= 30
  4604.1  219.13  4637.5  218.77  4688.1  217.02  4709.9  217.04  4732.8  216.81
  4754.7  215.61  4810.7  214.15  4866.7  211.62    4872  210.89  4953.3  207.67
  4966.8  206.16  4977.4   205.9  4989.2  204.51  4995.8  201.42  5001.6  201.42
  5009.3  204.43  5014.6  204.22    5028  206.22  5030.6  206.61  5083.8  205.64
  5115.7  207.56  5187.8  208.74  5193.1  209.36  5232.7   210.3  5279.7  210.74
  5346.2  213.32  5366.4   215.5  5422.3  218.35  5498.5  217.88  5573.1  220.05
#Mann= 6 ,-1 , 0
  4604.1     .11       0  4709.9     .17       0  4977.4     .09       0
    5028     .12       0  5030.6     .17       0  5346.2     .11       0
Bank Sta=4977.4,5028
XS Rating Curve= 0 ,0
Exp/Cntr=0.3,0.1

Type RM Length L Ch R = 1 ,33864   ,474,474,474
BEGIN DESCRIPTION:
Mapping XS 4878ba81
END DESCRIPTION:
XS GIS Cut Line= 2
      3795508.07     10107942.97      3794571.74     10107487.81
#Sta/Elev= 30
  4463.2  219.42    4519  216.85  4592.3  212.27  4721.1  207.95  4763.7  207.04
  4785.9  207.43  4795.3  208.49  4823.4  207.38  4830.4  208.02  4868.6  208.17
  4974.9   205.8  4986.9  203.29  4993.8  200.38  5000.5  200.38  5003.9  201.62
  5009.4  201.48  5026.4     204    5032  203.93    5049  205.42  5099.7  206.78
  5122.2  207.73  5139.2  209.18  5144.8  208.47  5161.8  208.58  5233.8  210.91
  5297.1   213.6  5325.2  216.12  5347.8  216.81  5353.3  216.39  5504.3  222.77
#Mann= 5 ,-1 , 0
  4463.2     .11       0  4721.1     .17       0  4974.9     .09       0
    5049     .17       0  5233.8     .11       0
Bank Sta=4974.9,5049
XS Rating Curve= 0 ,0
Exp/Cntr=0.3,0.1