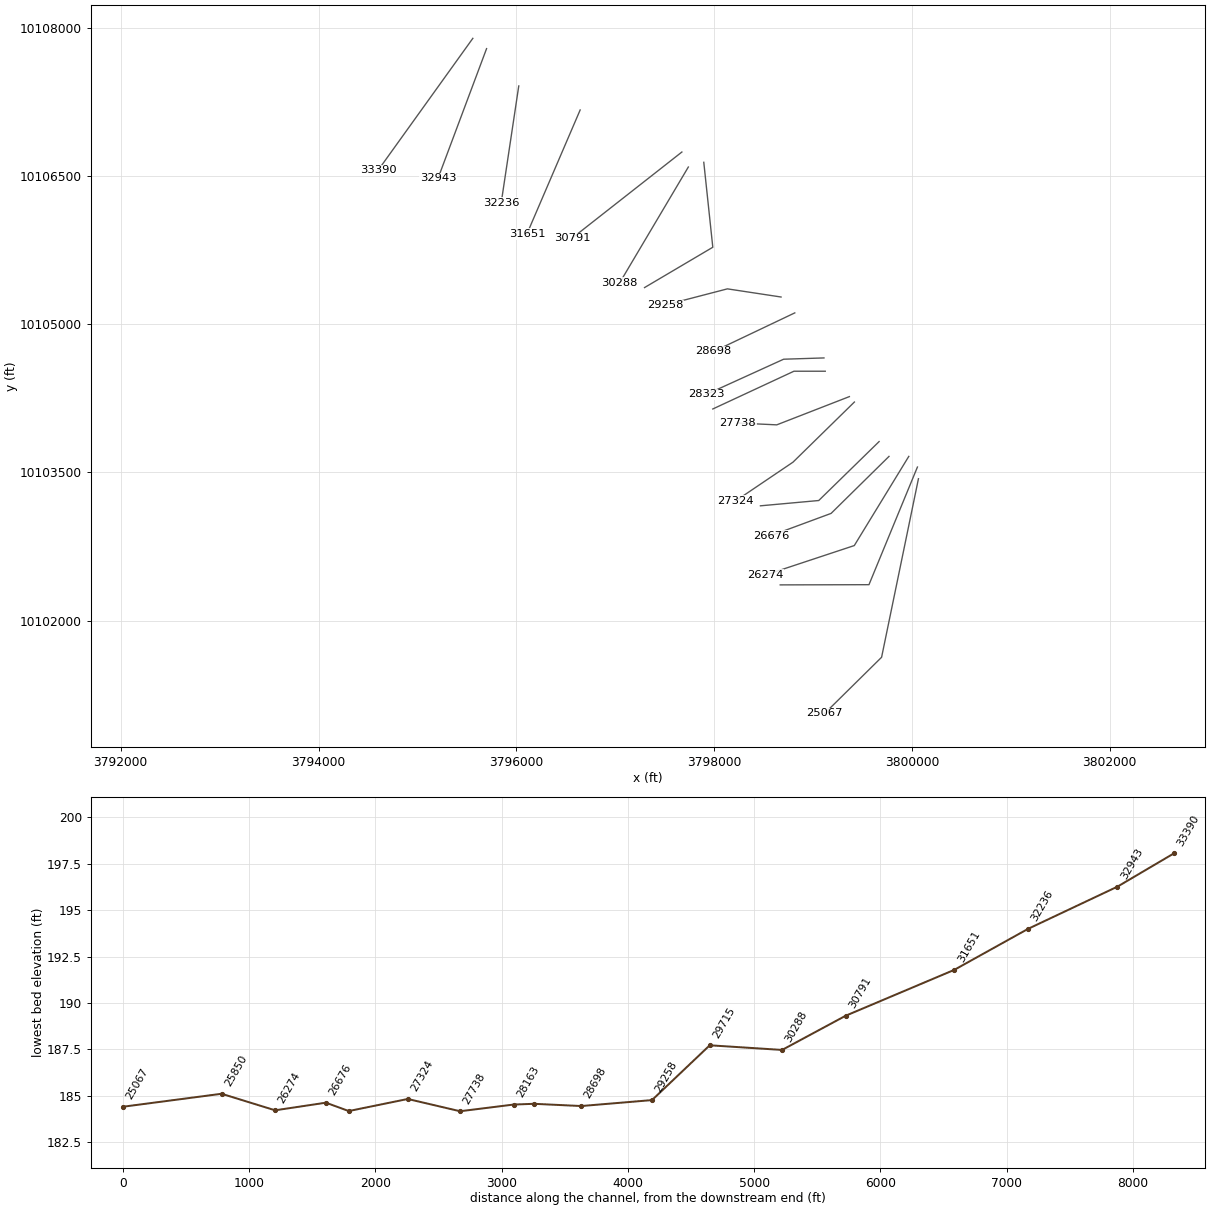
HEC-RAS study FISH CREEK.prj: FISH CREEK Base Level Engineering

--- FISH CREEK.g01 (geometry) --- (continued)

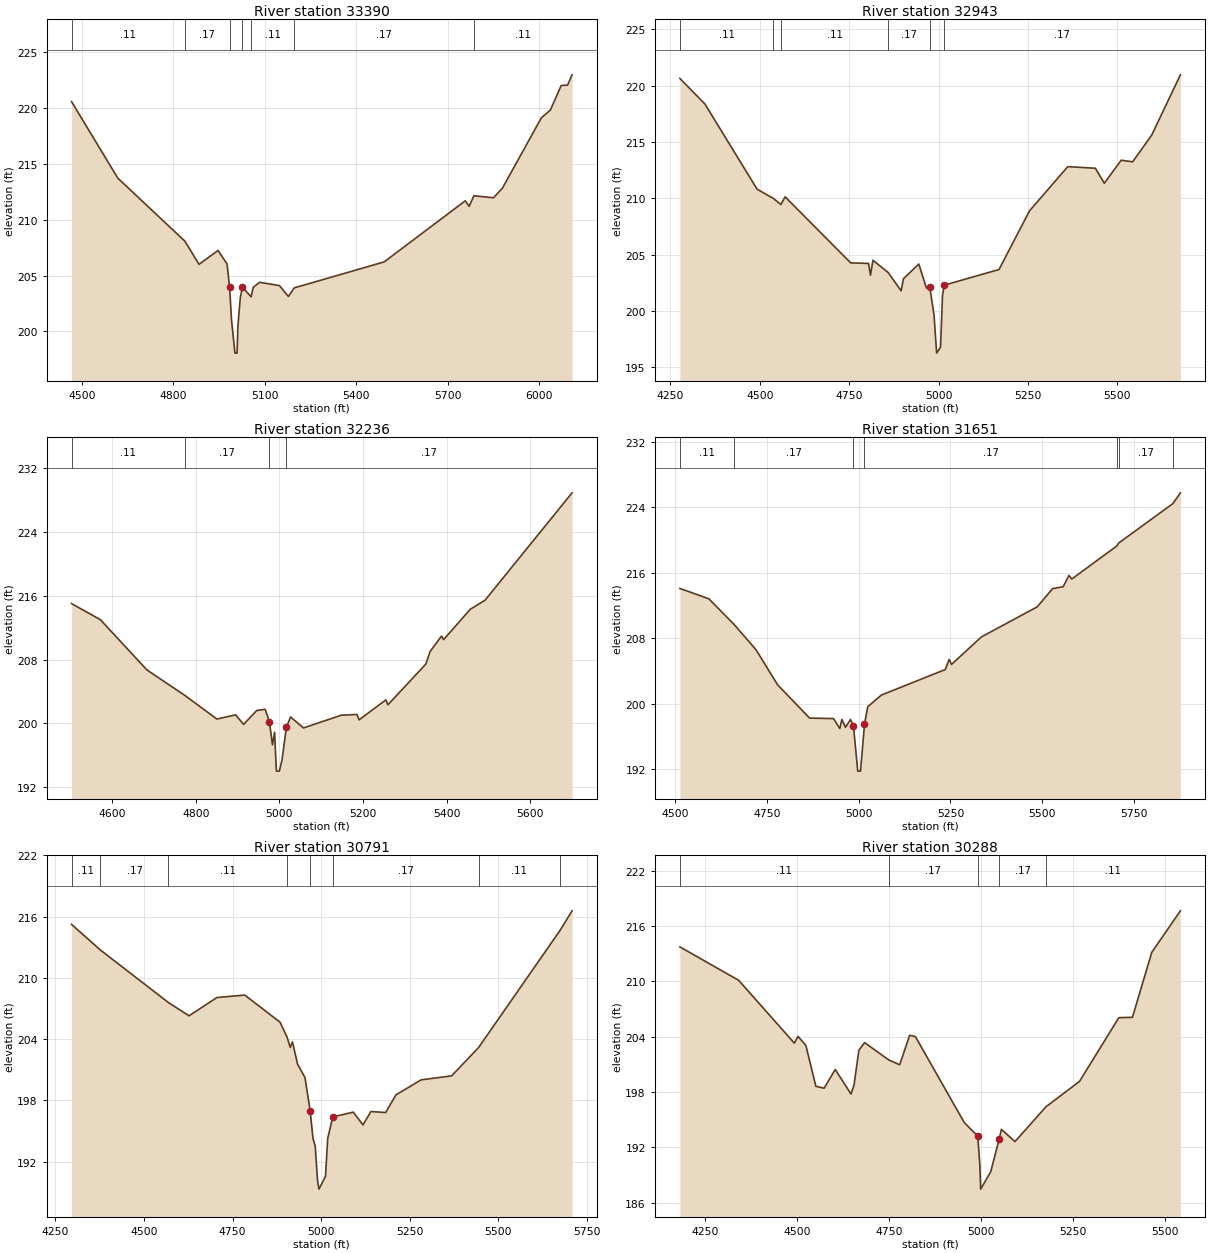
Type RM Length L Ch R = 1 ,33390   ,447,447,447
BEGIN DESCRIPTION:
Mapping XS 9df074b0
END DESCRIPTION:
XS GIS Cut Line= 2
      3795560.17      10107890.9      3794602.62      10106556.4
#Sta/Elev= 30
  4465.7  220.57  4617.4  213.72  4837.8  208.07  4883.9     206  4946.5  207.24
    4976  206.03  4984.4203.9427  4990.7  200.99    5002  198.05  5008.8  198.05
  5011.6  200.48  5019.4     203  5026.3  203.96    5055  203.09  5061.9  203.94
  5082.8  204.39  5147.9   204.1  5177.4  203.12  5196.3  203.89  5491.7  206.22
  5757.8  211.69  5770.5  211.19  5785.9  212.14  5850.3  211.96  5879.8  212.83
  6007.5  219.12    6037  219.81  6072.6  222.02  6093.5  222.05  6108.2  222.97
#Mann= 7 ,-1 , 0
  4465.7     .11       0  4837.8     .17       0  4984.4     .09       0
  5026.3     .17       0    5055     .11       0  5196.3     .17       0
  5785.9     .11       0
Bank Sta=4984.4,5026.3
XS Rating Curve= 0 ,0
Exp/Cntr=0.3,0.1

Type RM Length L Ch R = 1 ,32943   ,707,707,707
BEGIN DESCRIPTION:
Mapping XS dc56e01b
END DESCRIPTION:
XS GIS Cut Line= 2
      3795699.06     10107786.75      3795208.61       10106476.
#Sta/Elev= 30
  4276.7  220.64  4346.5  218.38  4492.6  210.81  4537.6     210  4559.2  209.45
    4571  210.13  4754.4  204.27  4804.3  204.22  4809.7  203.18  4816.6   204.5
  4859.3  203.41  4895.2  201.79    4902  202.87  4944.7  204.17  4966.1  202.04
  4975.3  202.16  4987.5  199.59  4994.6  196.26  5005.6   196.8    5011  201.38
 5015.78 202.291    5169  203.68  5254.4  208.89  5361.2  212.81  5438.5  212.67
  5463.5  211.34  5510.6  213.38  5542.7  213.24    5596  215.61  5676.2  220.96
#Mann= 6 ,-1 , 0
  4276.7     .11       0  4537.6     .17       0  4559.2     .11       0
  4859.3     .17       0  4975.3     .09       0 5015.78     .17       0
Bank Sta=4975.3,5015.78
XS Rating Curve= 0 ,0
Exp/Cntr=0.3,0.1

Type RM Length L Ch R = 1 ,32236   ,585,585,585
BEGIN DESCRIPTION:
Mapping XS 645e1dcc
END DESCRIPTION:
XS GIS Cut Line= 2
      3796024.57     10107409.16      3795846.75     10106225.14
#Sta/Elev= 30
  4502.9  215.02  4571.8     213    4683   206.7  4774.8  203.46  4850.5  200.53
  4895.3  201.05  4914.5  199.86  4945.9   201.6  4966.1  201.75  4976.2  200.19
  4983.5  197.29  4988.6  198.88  4992.9  193.99    5000  193.99  5006.6  195.47
  5016.7  199.48  5026.8  200.79  5057.7  199.41  5148.1  201.01  5185.7   201.1
  5190.7  200.43  5254.7  202.93  5259.8  202.32  5350.4  207.43  5360.5  208.99
  5387.8  210.94  5392.8  210.49  5456.8  214.31    5492  215.44  5700.2  228.92
#Mann= 4 ,-1 , 0
  4502.9     .11       0  4774.8     .17       0  4976.2     .09       0
  5016.7     .17       0
Bank Sta=4976.2,5016.7
XS Rating Curve= 0 ,0
Exp/Cntr=0.3,0.1

Type RM Length L Ch R = 1 ,31651   ,860,860,860
BEGIN DESCRIPTION:
Mapping XS e06bf6cb
END DESCRIPTION:
XS GIS Cut Line= 2
      3796645.23     10107166.07      3796107.04     10105911.75
#Sta/Elev= 30
  4512.1   214.1  4591.2  212.83  4660.1  209.69  4719.9   206.6  4778.7  202.32
  4865.8  198.26    4931   198.2  4948.3  196.99  4953.8   198.1  4963.7  197.13
  4977.3  198.09  4985.4  197.34  4997.1  191.78  5004.7  191.78 5015.51197.5033
  5024.4  199.65  5061.6  201.07  5235.7  204.19  5246.6  205.43  5252.8  204.81
  5334.4  208.18  5486.6  211.85  5528.3  214.07  5557.3  214.31  5573.1  215.69
  5580.9  215.25  5703.4  219.28  5708.8  219.65  5856.7  224.47    5877  225.78
#Mann= 7 ,-1 , 0
  4512.1     .11       0  4660.1     .17       0  4985.4     .09       0
 5015.51     .17       0  5703.4     .11       0  5708.8     .17       0
  5856.7     .11       0
Bank Sta=4985.4,5015.51
XS Rating Curve= 0 ,0
Exp/Cntr=0.3,0.1

Type RM Length L Ch R = 1 ,30791   ,503,503,503
BEGIN DESCRIPTION:
Mapping XS 9b331456
END DESCRIPTION:
XS GIS Cut Line= 2
      3797673.85      10106740.7       3796562.8     10105868.35
#Sta/Elev= 30
  4295.5  215.23    4377  212.72  4568.8  207.58  4627.1  206.28  4705.7  208.07
  4784.3  208.31  4883.8  205.66  4903.6  204.21  4912.7  203.19    4919  203.72
  4933.5  201.54  4954.3  200.24  4968.8     197  4976.9  194.28  4983.2  193.52
  4989.7  190.15  4993.8  189.31  5012.1  190.55  5018.5  194.29  5032.9  196.38
  5090.7  196.85  5117.9   195.6  5140.5  196.91  5182.1  196.81    5211  198.54
  5282.1  200.01  5368.2   200.4  5444.4  203.18  5673.9  214.63  5708.1  216.56
#Mann= 8 ,-1 , 0
  4295.5     .11       0    4377     .17       0  4568.8     .11       0
  4903.6     .17       0  4968.8     .09       0  5032.9     .17       0
  5444.4     .11       0  5673.9     .17       0
Bank Sta=4968.8,5032.9
XS Rating Curve= 0 ,0
Exp/Cntr=0.3,0.1

Type RM Length L Ch R = 1 ,30288   ,573,573,573
BEGIN DESCRIPTION:
Mapping XS e3bc3876
END DESCRIPTION:
XS GIS Cut Line= 2
      3797738.96     10106588.78      3797044.51     10105416.89
#Sta/Elev= 30
  4180.5  213.75  4340.6  210.12  4492.1   203.3  4501.9  204.04  4523.3  203.07
  4550.6  198.63    4573  198.42  4603.3  200.45  4646.1  197.79  4654.4  198.75
  4667.6  202.53  4683.2  203.36  4748.9  201.49  4778.7  200.96  4805.9  204.16
  4821.6  204.01  4954.2  194.71  4991.2  193.22    4997  190.01  4999.2  187.47
  5026.4  189.35  5049.6  192.91  5055.5  193.95  5092.6  192.63  5176.7   196.4
    5268  199.15  5375.2  206.07  5412.2  206.11  5464.9  213.16  5542.7  217.66
#Mann= 5 ,-1 , 0
  4180.5     .11       0  4748.9     .17       0  4991.2     .09       0
  5049.6     .17       0  5176.7     .11       0
Bank Sta=4991.2,5049.6
XS Rating Curve= 0 ,0
Exp/Cntr=0.3,0.1

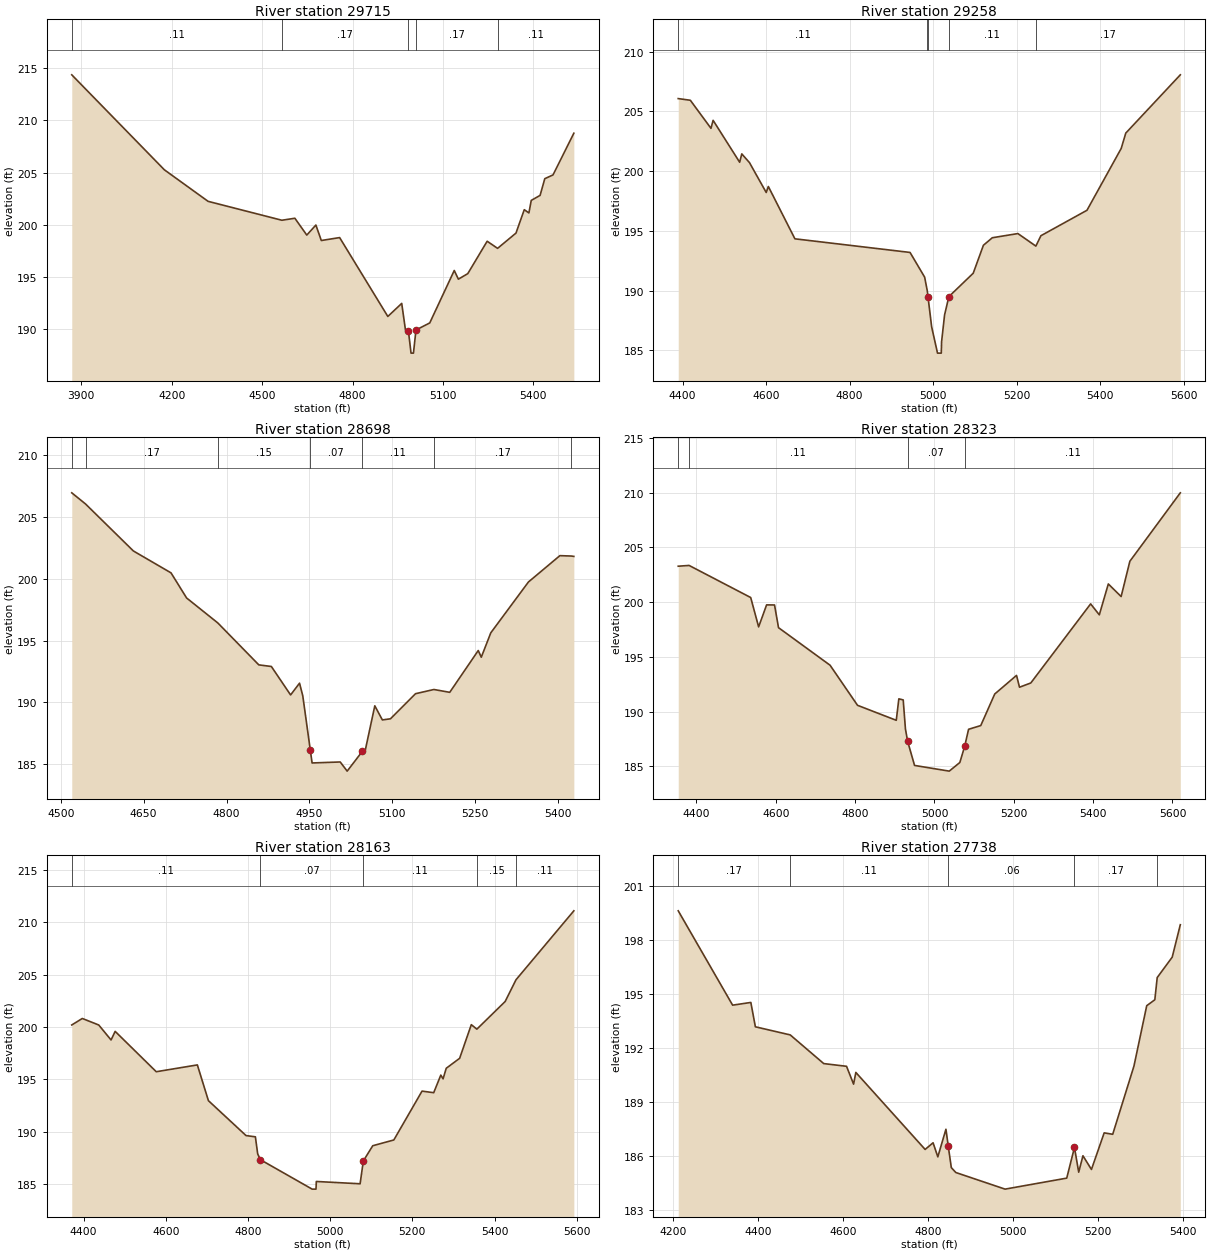
Type RM Length L Ch R = 1 ,29715   ,457,457,457
BEGIN DESCRIPTION:
Mapping XS f0a8d1c4
END DESCRIPTION:
XS GIS Cut Line= 3
      3797895.22     10106636.55      3797986.37     10105777.17
      3797296.25     10105369.18
#Sta/Elev= 30
  3868.3  214.36  4175.5  205.27  4320.6  202.25  4565.4  200.44  4608.6  200.63
  4648.1  199.02  4678.3  199.98  4696.3   198.5  4757.1  198.78    4917  191.23
  4963.1  192.48  4975.5  189.94  4985.3  189.84    4994  187.72    5002  187.72
 5010.42189.9351  5056.1  190.61  5137.4  195.63  5151.1   194.8  5182.3  195.33
  5246.6  198.43  5281.2  197.75  5342.2  199.21  5369.7  201.45  5385.1  201.14
  5392.9  202.34  5422.2  202.82  5437.8  204.42  5465.1  204.78  5534.2  208.77
#Mann= 5 ,-1 , 0
  3868.3     .11       0  4565.4     .17       0  4985.3     .09       0
 5010.42     .17       0  5281.2     .11       0
Bank Sta=4985.3,5010.42
XS Rating Curve= 0 ,0
Exp/Cntr=0.3,0.1

Type RM Length L Ch R = 1 ,29258   ,560,560,560
BEGIN DESCRIPTION:
Mapping XS 29c1c8a8
END DESCRIPTION:
XS GIS Cut Line= 3
      3798676.51     10105273.69      3798133.94     10105356.17
      3797501.51     10105191.56
#Sta/Elev= 30
  4389.6  206.08  4418.6  205.94    4468  203.59  4473.1  204.26  4536.7  200.75
  4541.8  201.45  4560.2  200.72  4600.3  198.22  4605.4  198.72    4669  194.34
  4944.7   193.2  4979.7  191.13    4986  189.98  4987.9189.4319  4996.4  186.98
  5010.5  184.77  5019.5  184.77  5020.2  185.71  5027.4  187.97  5037.7   189.5
    5096  191.46  5120.4   193.8  5141.7  194.43    5203  194.78    5246  193.73
  5258.1   194.6  5368.4  196.73  5450.4  201.91  5461.3  203.19  5591.9  208.07
#Mann= 5 ,-1 , 0
  4389.6     .11       0    4986     .08       0  4987.9     .06       0
  5037.7     .11       0    5246     .17       0
Bank Sta=4987.9,5037.7
XS Rating Curve= 0 ,0
Exp/Cntr=0.3,0.1

Type RM Length L Ch R = 1 ,28698   ,375,375,375
BEGIN DESCRIPTION:
Mapping XS c3a2afac
END DESCRIPTION:
XS GIS Cut Line= 2
      3798815.36     10105113.11      3797995.02     10104722.47
#Sta/Elev= 30
  4519.9  206.95  4544.8  206.05  4631.4  202.25  4699.5  200.48  4727.7  198.45
  4784.2  196.43  4858.4  193.04  4881.1  192.91  4915.9  190.61  4932.1  191.56
    4938  190.53  4951.6186.1423  4954.8  185.11  5005.7  185.19  5018.3  184.45
  5045.6  186.04  5051.2  186.17  5068.3  189.73    5082  188.59  5096.6  188.68
    5142  190.71  5175.3  191.05  5203.9  190.82  5255.5   194.2    5261  193.66
  5278.2  195.63  5346.3  199.74  5403.2  201.87    5424  201.84  5428.5  201.81
#Mann= 7 ,-1 , 0
  4519.9     .11       0  4544.8     .17       0  4784.2     .15       0
  4951.6     .07       0  5045.6     .11       0  5175.3     .17       0
    5424     .11       0
Bank Sta=4951.6,5045.6
XS Rating Curve= 0 ,0
Exp/Cntr=0.3,0.1

Type RM Length L Ch R = 1 ,28323   ,160,160,160
BEGIN DESCRIPTION:
Mapping XS 2b508492
END DESCRIPTION:
XS GIS Cut Line= 3
       3799110.5     10104657.38      3798702.52     10104644.36
      3797922.07     10104288.82
#Sta/Elev= 30
    4354  203.28  4381.4  203.35  4536.7  200.42  4556.7  197.74  4576.8  199.75
  4596.8  199.74  4606.8  197.67  4736.8  194.24    4806  190.58  4903.7  189.21
  4910.2  191.17  4921.2  191.07  4926.8  188.42  4932.3   187.3  4949.8  185.09
  5037.3  184.57    5064  185.36  5076.1  186.83    5086  188.39  5116.7  188.73
  5151.9  191.61  5206.9  193.31  5214.4  192.23  5242.9  192.62  5393.7  199.84
  5415.6  198.84  5438.3  201.66  5470.6  200.51  5492.6  203.73  5619.8  209.98
#Mann= 4 ,-1 , 0
    4354     .17       0  4381.4     .11       0  4932.3     .07       0
  5076.1     .11       0
Bank Sta=4932.3,5076.1
XS Rating Curve= 0 ,0
Exp/Cntr=0.3,0.1

Type RM Length L Ch R = 1 ,28163   ,425,425,425
BEGIN DESCRIPTION:
Mapping XS cde2267e
END DESCRIPTION:
XS GIS Cut Line= 3
       3799123.5     10104522.83      3798806.68     10104522.83
      3797986.36     10104140.88
#Sta/Elev= 30
  4371.3  200.19  4396.9  200.81  4436.9  200.19  4466.9  198.76  4476.9  199.58
  4576.9  195.73  4676.9  196.38  4703.8  192.97  4795.3  189.64  4818.1  189.52
  4823.7  187.89  4830.2  187.34  4956.2  184.53  4965.6  184.53  4966.4  185.26
  5072.9  185.04  5080.8  187.22  5103.7  188.67    5155  189.22  5223.6  193.88
    5252  193.73  5269.3  195.41  5274.8  195.05  5282.5  196.06  5315.1  197.01
  5343.5  200.22    5357  199.79  5425.9  202.43  5452.2   204.5    5593  211.08
#Mann= 5 ,-1 , 0
  4371.3     .11       0  4830.2     .07       0  5080.8     .11       0
    5357     .15       0  5452.2     .11       0
Bank Sta=4830.2,5080.8
XS Rating Curve= 0 ,0
Exp/Cntr=0.3,0.1

Type RM Length L Ch R = 1 ,27738   ,414,414,414
BEGIN DESCRIPTION:
FISH CREEK 43.0
END DESCRIPTION:
XS GIS Cut Line= 3
      3799367.22     10104266.04      3798633.07     10103980.29
      3798238.79     10103998.68
#Sta/Elev= 30
  4212.2   199.6  4340.3  194.37  4383.2  194.52  4393.9  193.17    4476  192.72
  4554.9  191.13  4608.6  190.98  4625.2  189.99  4630.5  190.64  4793.7  186.37
  4812.4  186.74  4823.6  185.96  4842.7  187.49  4848.1  186.56  4855.4  185.36
  4866.1  185.09    4982  184.17  5127.2  184.78  5145.4  186.48  5155.4  185.11
  5165.4  186.02  5185.4  185.26  5215.4  187.29  5235.5  187.21  5285.5  190.99
  5315.6  194.34  5334.7  194.67  5340.3   195.9  5375.6  197.03  5394.7  198.83
#Mann= 5 ,-1 , 0
  4212.2     .17       0    4476     .11       0  4848.1     .06       0
  5145.4     .17       0  5340.3     .11       0
Bank Sta=4848.1,5145.4
XS Rating Curve= 0 ,0
Exp/Cntr=0.3,0.1

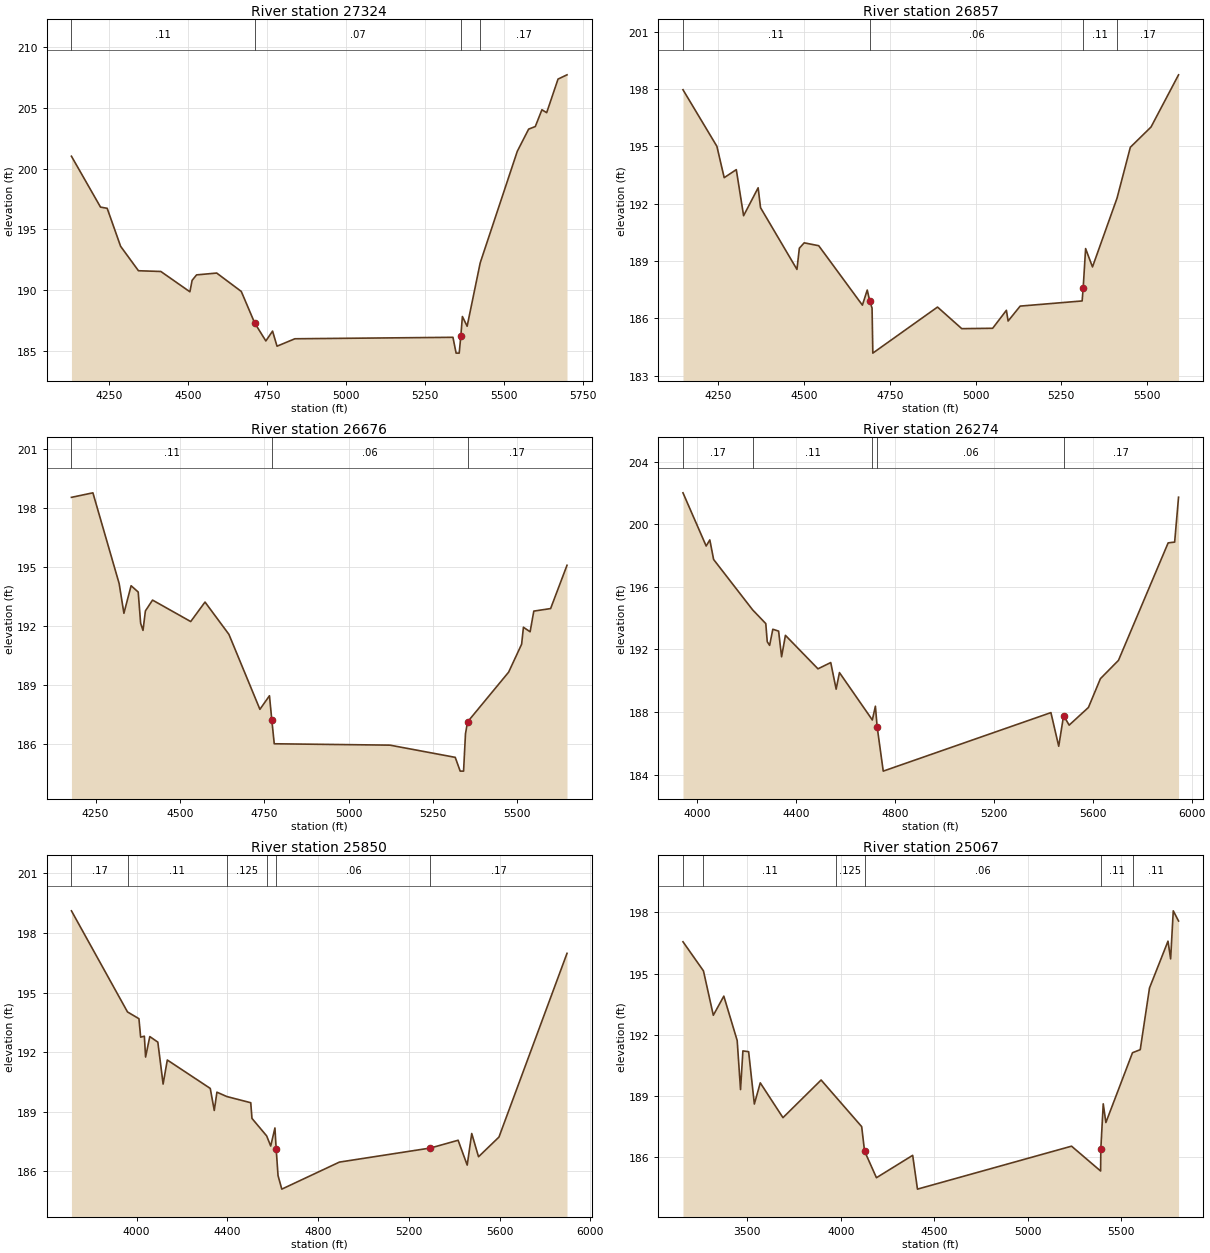
Type RM Length L Ch R = 1 ,27324   ,467,467,467
BEGIN DESCRIPTION:
FISH CREEK 42.0
END DESCRIPTION:
XS GIS Cut Line= 3
      3799417.89     10104211.11      3798797.13     10103602.69
      3798217.88     10103211.09
#Sta/Elev= 30
  4130.8  201.01  4222.8  196.83  4243.9  196.73  4286.4  193.61  4342.9   191.6
  4413.7  191.54  4505.7  189.87  4512.7  190.81  4526.8  191.26  4590.5  191.41
  4668.3   189.9  4710.7  187.31  4746.1  185.83  4767.3  186.64  4781.4   185.4
    4838  186.01  5338.2  186.13  5348.2  184.83    5358  184.83 5363.17186.2378
  5368.1  187.84  5383.1  187.04  5424.5  192.25  5541.9  201.42  5577.8  203.24
  5598.8  203.45  5619.8  204.83  5634.8  204.59  5670.8  207.35  5699.2   207.7
#Mann= 4 ,-1 , 0
  4130.8     .11       0  4710.7     .07       0 5363.17     .11       0
  5424.5     .17       0
Bank Sta=4710.7,5363.17
XS Rating Curve= 0 ,0
Exp/Cntr=0.3,0.1

Type RM Length L Ch R = 1 ,26857   ,181,181,181
BEGIN DESCRIPTION:
FISH CREEK 41.0
END DESCRIPTION:
XS GIS Cut Line= 3
      3799667.83     10103811.05      3799057.55     10103214.67
      3798467.88     10103161.07
#Sta/Elev= 30
  4146.7  197.96  4245.6     195  4266.9  193.36  4302.2  193.78  4323.5  191.37
  4365.9  192.83  4372.9  191.79  4479.1  188.56  4486.1  189.67  4500.2  189.95
  4542.6   189.8    4670  186.69  4684.1  187.48  4691.3  186.92  4698.2  186.53
  4700.4  184.18  4889.1  186.59  4959.8  185.46  5049.9  185.48    5090  186.42
    5095  185.86  5130.2  186.64  5310.9  186.91    5314   187.6    5321  189.65
  5341.1  188.69  5412.7  192.29  5451.5  194.95  5511.8  196.01  5592.1  198.74
#Mann= 4 ,-1 , 0
  4146.7     .11       0  4691.3     .06       0    5314     .11       0
  5412.7     .17       0
Bank Sta=4691.3,5314
XS Rating Curve= 0 ,0
Exp/Cntr=0.3,0.1

Type RM Length L Ch R = 1 ,26676   ,402,402,402
BEGIN DESCRIPTION:
FISH CREEK 40.0
END DESCRIPTION:
XS GIS Cut Line= 3
      3799767.84     10103661.06      3799182.55     10103084.46
      3798575.59      10102859.8
#Sta/Elev= 30
  4178.4  198.54    4242  198.77  4319.8  194.16  4333.9  192.65  4355.2  194.05
  4376.3  193.73  4383.5  192.14  4390.5  191.78  4397.6  192.77  4418.8  193.32
  4531.9  192.23  4574.3  193.22  4645.1  191.58    4737  187.77  4765.3  188.46
  4772.3  187.22  4779.5  186.02  5122.3  185.95  5315.9  185.33  5330.6  184.63
  5340.6  184.63  5346.3  186.53  5352.4  187.13  5474.2  189.66  5512.7  191.08
    5518  191.94  5537.8  191.71  5548.8  192.76  5598.6  192.89  5647.2  195.09
#Mann= 3 ,-1 , 0
  4178.4     .11       0  4772.3     .06       0  5352.4     .17       0
Bank Sta=4772.3,5352.4
XS Rating Curve= 0 ,0
Exp/Cntr=0.3,0.1

Type RM Length L Ch R = 1 ,26274   ,424,424,424
BEGIN DESCRIPTION:
FISH CREEK 39.0
END DESCRIPTION:
XS GIS Cut Line= 3
      3799967.88     10103661.11      3799416.92     10102758.94
      3798517.88     10102461.08
#Sta/Elev= 30
  3942.9  202.01  4036.7  198.61  4051.4     199  4066.8  197.75  4224.5  194.53
  4277.8  193.65  4283.7  192.49  4293.3  192.26  4306.2  193.29  4329.6  193.17
  4341.7  191.53  4357.2   192.9  4488.8  190.76  4540.5  191.16  4562.3  189.46
  4575.7  190.52  4708.7  187.49  4721.1  188.37    4728  187.07  4752.8  184.22
  5430.9  187.96  5462.5  185.81  5482.2  187.77  5504.7  187.16  5582.6  188.29
  5631.1  190.13  5704.1   191.3    5905  198.81  5931.3  198.86  5947.1  201.73
#Mann= 5 ,-1 , 0
  3942.9     .17       0  4224.5     .11       0  4708.7    .125       0
    4728     .06       0  5482.2     .17       0
Bank Sta=4728,5482.2
XS Rating Curve= 0 ,0
Exp/Cntr=0.3,0.1

Type RM Length L Ch R = 1 ,25850   ,783,783,783
BEGIN DESCRIPTION:
FISH CREEK 38.0
END DESCRIPTION:
XS GIS Cut Line= 3
      3800055.21     10103553.24      3799565.36     10102363.11
      3798667.86     10102361.07
#Sta/Elev= 30
    3713  199.12  3960.1  194.03  4010.5  193.69  4018.1  192.76  4034.4  192.81
  4039.8  191.76  4058.4  192.79  4093.8  192.51  4117.1   190.4  4135.6  191.61
  4324.9  190.18  4342.6  189.07  4354.3  189.99  4398.1  189.77  4503.4  189.46
  4508.8  188.67  4573.5  187.79  4591.4  187.28    4610  188.19  4615.4  187.14
  4623.7  185.79  4640.3  185.11  4894.1  186.47  5295.7  187.18  5417.5  187.57
  5457.5  186.32  5477.5  187.91  5507.5  186.74  5597.5  187.73  5897.5  196.98
#Mann= 6 ,-1 , 0
    3713     .17       0  3960.1     .11       0  4398.1    .125       0
  4573.5     .11       0  4615.4     .06       0  5295.7     .17       0
Bank Sta=4615.4,5295.7
XS Rating Curve= 0 ,0
Exp/Cntr=0.3,0.1

Type RM Length L Ch R = 1 ,25067   ,379,379,379
BEGIN DESCRIPTION:
FISH CREEK 37.0
END DESCRIPTION:
XS GIS Cut Line= 3
      3800065.63     10103435.19      3799692.96     10101628.73
      3799117.84     10101061.06
#Sta/Elev= 30
  3155.5  196.56  3265.1  195.13  3317.9  192.95  3374.1  193.89  3445.6  191.71
  3463.6   189.3  3476.2   191.2  3506.9  191.16  3537.5  188.59  3569.2  189.63
  3690.7  187.92  3894.9  189.77  3973.5  188.94    4112  187.48 4127.33  186.28
    4191  184.97    4385  186.07  4410.6  184.41  5235.3  186.52  5390.9   185.3
 5392.08  186.39    5405   188.6  5419.1  187.68  5561.6  191.11    5603  191.26
  5652.6  194.29  5751.6  196.59  5765.7  195.72  5779.8  198.08  5808.1  197.58
#Mann= 6 ,-1 , 0
  3155.5     .17       0  3265.1     .11       0  3973.5    .125       0
 4127.33     .06       0 5392.08     .11       0  5561.6     .11       0
Bank Sta=4127.33,5392.08
XS Rating Curve= 0 ,0
Exp/Cntr=0.3,0.1