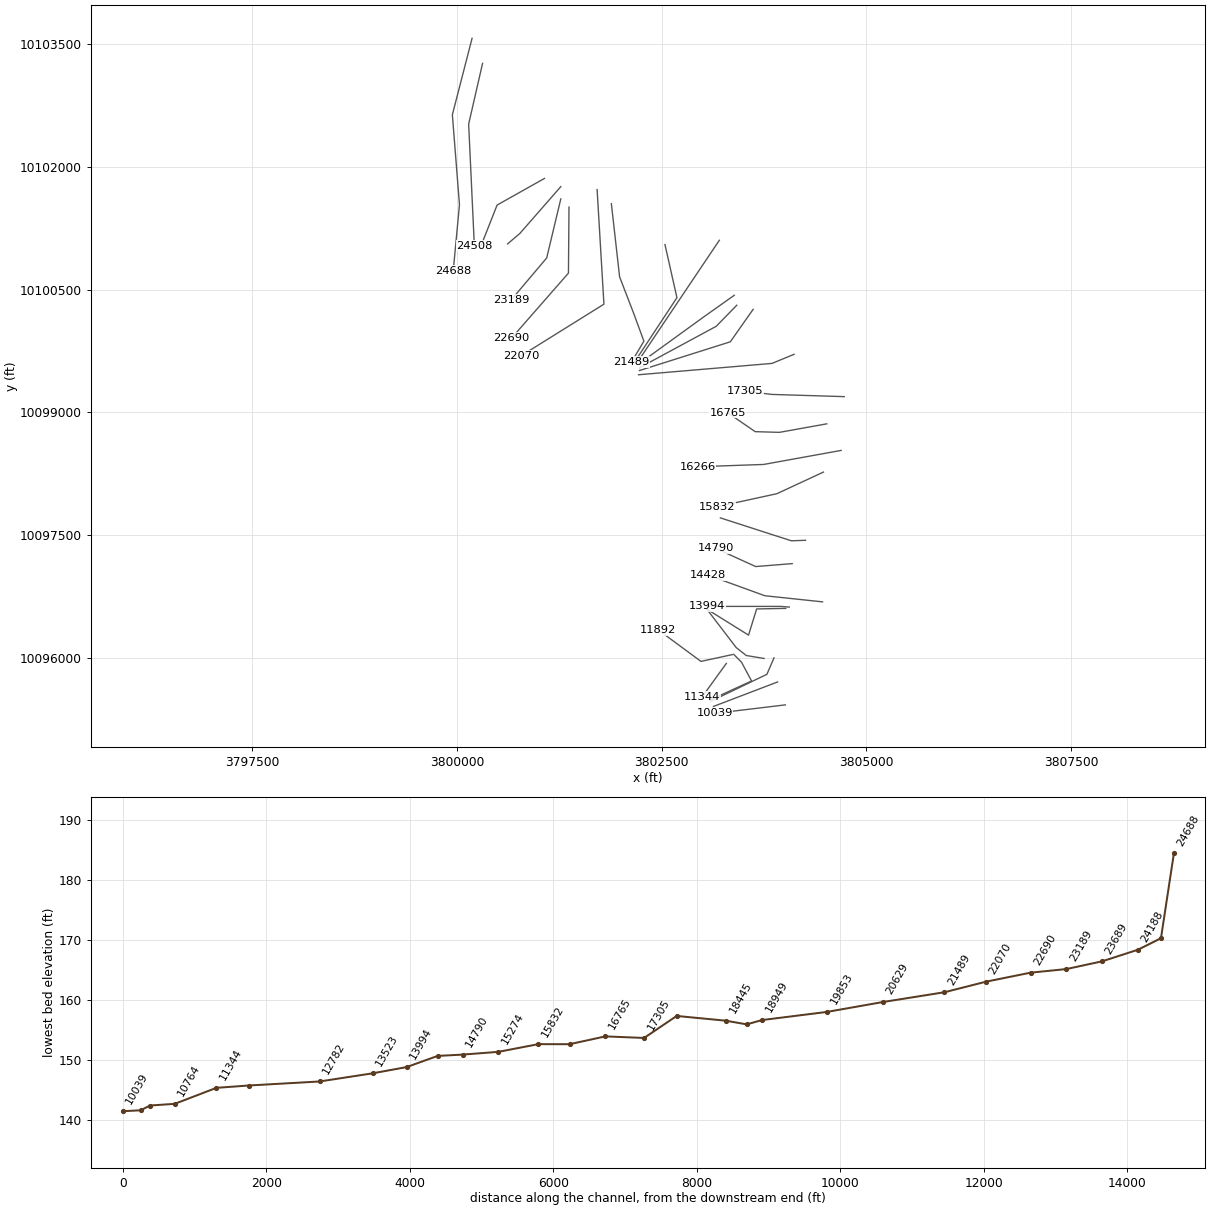
HEC-RAS study FISH CREEK.prj: FISH CREEK Base Level Engineering

--- FISH CREEK.g01 (geometry) --- (continued)

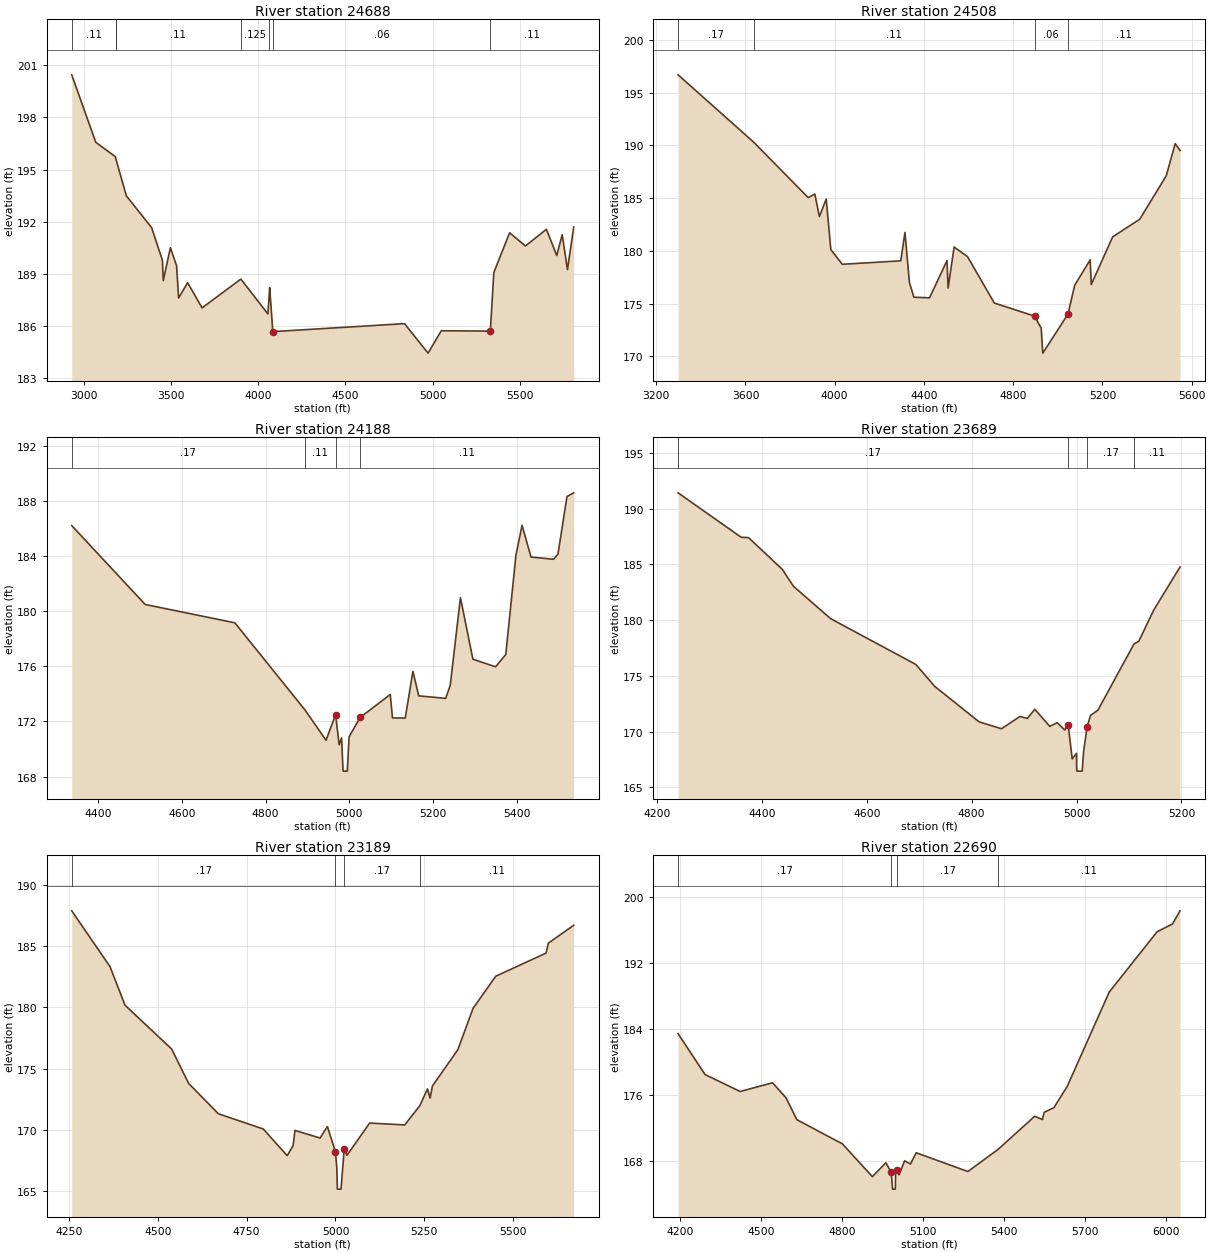
Type RM Length L Ch R = 1 ,24688   ,180,180,180
BEGIN DESCRIPTION:
FISH CREEK 36.0
END DESCRIPTION:
XS GIS Cut Line= 4
      3800183.69      10103574.1      3799942.94     10102639.95
      3800029.77     10101540.04      3799954.09     10100735.39
#Sta/Elev= 30
    2932  200.46  3069.4  196.57  3183.2  195.73  3184.4  195.62  3244.9  193.48
  3389.5  191.65  3451.3  189.77  3456.4  188.59  3497.1  190.49  3532.7  189.45
  3544.4  187.59    3596  188.47  3678.7  187.02  3900.9  188.68    4056  186.67
  4062.2   187.6  4066.1  188.19 4083.94  185.65  4838.5  186.11  4973.9  184.41
  5049.2   185.7  5330.4  185.68  5350.5  189.06  5440.9  191.35  5531.3  190.59
  5651.8  191.55  5710.9  190.04  5742.2  191.24  5772.4  189.23  5808.2  191.68
#Mann= 7 ,-1 , 0
    2932     .11       0  3183.2     .17       0  3184.4     .11       0
  3900.9    .125       0  4062.2     .11       0 4083.94     .06       0
  5330.4     .11       0
Bank Sta=4083.94,5330.4
XS Rating Curve= 0 ,0
Exp/Cntr=0.3,0.1

Type RM Length L Ch R = 1 ,24508   ,320,320,320
BEGIN DESCRIPTION:
Mapping XS 2568aab9
END DESCRIPTION:
XS GIS Cut Line= 3
      3800312.15     10103268.48      3800142.02     10102525.46
      3800211.46     10101039.33
#Sta/Elev= 30
  3298.1  196.68  3637.2  190.29  3881.4  185.04    3911  185.38  3931.5  183.24
  3962.1  184.91  3982.8  180.11  4034.1  178.72  4296.2  179.05    4315  181.74
    4335     177  4355.1   175.6  4425.1  175.54  4503.5  179.07  4508.5  176.47
  4535.3  180.36  4595.3  179.45  4715.5  175.05  4895.7  173.81  4925.7  172.66
  4932.9   170.3  5045.8     174  5075.8  176.73  5145.2  179.14  5150.2   176.8
    5246  181.32  5367.4  182.99  5486.3  187.11  5526.3  190.16  5548.1  189.51
#Mann= 4 ,-1 , 0
  3298.1     .17       0  3637.2     .11       0  4895.7     .06       0
  5045.8     .11       0
#Block Obstruct= 2 , 0
         4536.65  180.32
Bank Sta=4895.7,5045.8
XS Rating Curve= 0 ,0
Exp/Cntr=0.3,0.1

Type RM Length L Ch R = 1 ,24188   ,499,499,499
BEGIN DESCRIPTION:
FISH CREEK 35.0
END DESCRIPTION:
XS GIS Cut Line= 3
      3801067.81     10101861.05      3800489.36     10101535.63
      3800292.86     10101036.09
#Sta/Elev= 30
  4336.3   186.2  4511.9  180.48  4726.4  179.15  4893.8  172.84  4944.4  170.63
  4967.3  172.49  4975.9   170.3  4981.6   170.8  4985.2  168.39  4995.3  168.39
  4999.6  170.88  5026.2172.2854    5098  173.95  5103.4  172.25  5133.9  172.24
  5152.2  175.63  5166.1  173.85  5230.6  173.67  5241.5  174.61  5265.9  180.97
  5295.7  176.51  5349.9  175.96  5374.3  176.85  5398.7  184.07  5413.2  186.22
  5434.7  183.92  5488.5  183.76  5499.2  184.14  5520.7  188.31  5536.8  188.58
#Mann= 4 ,-1 , 0
  4336.3     .17       0  4893.8     .11       0  4967.3     .06       0
  5026.2     .11       0
#Block Obstruct= 2 , 0
                          5266.3          180.99
Bank Sta=4967.3,5026.2
XS Rating Curve= 0 ,0
Exp/Cntr=0.3,0.1

Type RM Length L Ch R = 1 ,23689   ,500,500,500
BEGIN DESCRIPTION:
FISH CREEK 34.0
END DESCRIPTION:
XS GIS Cut Line= 3
      3801267.84     10101761.06      3800768.03     10101189.06
      3800617.86     10101061.08
#Sta/Elev= 30
  4240.4  191.42  4360.5  187.44  4374.7   187.4  4439.2  184.55  4460.1  183.05
  4531.3  180.13  4693.6  176.03  4729.7  174.06  4814.2  170.88  4856.9  170.26
    4892  171.36  4906.2  171.19  4920.5  172.01    4949  170.47  4963.2  170.81
  4977.4  170.15  4984.1   170.6  4991.7  167.55    5000  168.06  5000.1  166.96
  5000.6  166.46  5010.8  166.46  5013.4   168.2    5020  170.41  5026.6  171.46
  5040.8  171.93  5109.6  177.87  5118.8  178.12  5147.3  180.92  5197.3  184.77
#Mann= 4 ,-1 , 0
  4240.4     .17       0  4984.1     .09       0    5020     .17       0
  5109.6     .11       0
Bank Sta=4984.1,5020
XS Rating Curve= 0 ,0
Exp/Cntr=0.3,0.1

Type RM Length L Ch R = 1 ,23189   ,499,499,499
BEGIN DESCRIPTION:
FISH CREEK 33.0
END DESCRIPTION:
XS GIS Cut Line= 3
      3801267.85     10101611.07      3801095.47     10100888.97
      3800662.58     10100376.54
#Sta/Elev= 30
  4257.6  187.88  4365.4  183.32  4407.5  180.18  4538.9   176.6  4586.6   173.8
  4670.4  171.32  4796.6  170.08  4864.2   167.9  4880.8  168.72    4886  169.96
  4956.7  169.34  4977.3  170.28    5000  168.21  5003.9  166.87  5005.4  165.17
  5015.6  165.17  5024.8  168.46  5032.5  167.93  5096.2  170.56  5195.1  170.41
  5237.6  171.98  5259.1  173.35  5266.5   172.6  5273.1  173.59  5344.6  176.55
  5387.4  179.92  5451.2  182.54  5592.9  184.43  5599.4  185.24  5670.8   186.7
#Mann= 4 ,-1 , 0
  4257.6     .17       0    5000     .09       0  5024.8     .17       0
  5237.6     .11       0
Bank Sta=5000,5024.8
XS Rating Curve= 0 ,0
Exp/Cntr=0.3,0.1

Type RM Length L Ch R = 1 ,22690   ,620,620,620
BEGIN DESCRIPTION:
FISH CREEK 32.0
END DESCRIPTION:
XS GIS Cut Line= 3
      3801367.85     10101511.04      3801361.28     10100703.87
      3800667.83     10099911.04
#Sta/Elev= 30
  4192.8  183.45  4292.8  178.49  4422.8  176.43  4542.8  177.49  4592.8  175.67
  4632.8  173.01  4802.1  170.06  4912.8  166.09  4962.8  167.77  4982.8  166.64
  4987.7  164.57  4997.9  164.57  4998.4  165.07  4998.9  166.93  5005.2  166.93
  5011.6   166.3  5032.5  168.01  5054.3  167.62  5075.2  168.99  5266.9  166.71
  5378.5  169.39  5514.6  173.42  5543.1  173.02  5549.7   173.9  5585.8  174.47
  5635.2  177.05  5790.8  188.51  5968.3  195.84  6025.3  196.78  6053.3  198.38
#Mann= 4 ,-1 , 0
  4192.8     .17       0  4982.8     .09       0  5005.2     .17       0
  5378.5     .11       0
Bank Sta=4982.8,5005.2
XS Rating Curve= 0 ,0
Exp/Cntr=0.3,0.1

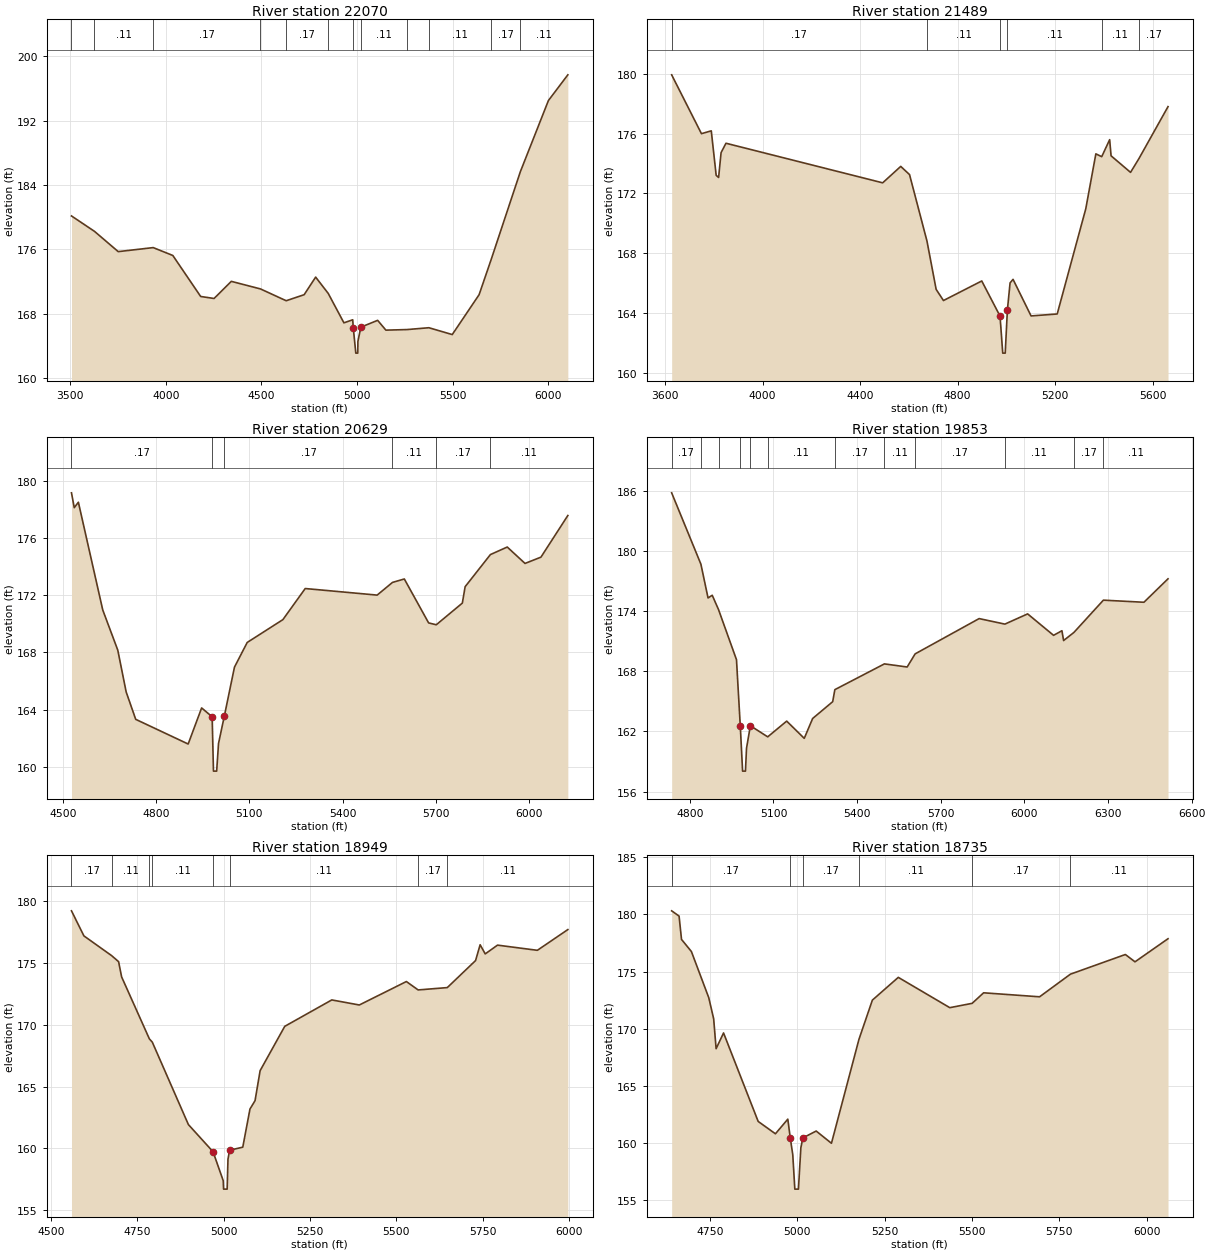
Type RM Length L Ch R = 1 ,22070   ,581,581,581
BEGIN DESCRIPTION:
Mapping XS 0dd19fad
END DESCRIPTION:
XS GIS Cut Line= 3
      3801711.42     10101725.03      3801794.75     10100324.03
      3800784.35     10099693.83
#Sta/Elev= 30
  3507.1  180.14    3627  178.23  3751.5   175.7  3934.2   176.2  4036.8  175.22
  4182.3  170.12  4252.4  169.87  4342.5     172  4494.7  171.06  4629.3  169.59
  4723.2  170.34  4783.3  172.53    4849   170.5    4931  166.84    4977  167.22
    4980166.2081  4993.2  163.07  5003.4  163.07  5004.1  164.52  5019.5   166.3
  5107.3  167.15  5150.4  165.93  5260.7     166  5375.1  166.23  5497.3  165.38
  5637.6  170.34  5700.8  174.73  5853.1  185.64  5999.9   194.5  6101.4   197.7
#Mann= 12 ,-1 , 0
  3507.1     .17       0    3627     .11       0  3934.2     .17       0
  4494.7     .11       0  4629.3     .17       0    4849     .11       0
    4980     .07       0  5019.5     .11       0  5260.7     .17       0
  5375.1     .11       0  5700.8     .17       0  5853.1     .11       0
Bank Sta=4980,5019.5
XS Rating Curve= 0 ,0
Exp/Cntr=0.3,0.1

Type RM Length L Ch R = 1 ,21489   ,860,860,860
BEGIN DESCRIPTION:
FISH CREEK 31.0
END DESCRIPTION:
XS GIS Cut Line= 5
      3801885.46      10101552.5      3801986.35     10100657.54
       3802156.3      10100216.8      3802283.03     10099871.94
      3802132.43     10099617.48
#Sta/Elev= 30
    3627  179.94  3749.2     176  3789.5  176.19  3809.6  173.21  3819.6  173.07
  3829.7  174.73  3849.8  175.36  4492.6  172.71  4566.7  173.81  4602.8  173.26
  4674.2  168.82  4711.9  165.58  4741.9  164.83    4899  166.14    4974  163.79
  4985.1  161.31  4995.3  161.31  5004.2164.1984  5015.2  166.01  5027.4  166.25
  5101.3   163.8  5208.5  163.93  5325.7  170.97  5367.1  174.65  5391.1  174.46
  5423.7   175.6  5429.5  174.52  5509.4  173.41  5543.7  174.33  5663.1  177.81
#Mann= 6 ,-1 , 0
    3627     .17       0  4674.2     .11       0    4974     .09       0
  5004.2     .11       0  5391.1     .11       0  5543.7     .17       0
Bank Sta=4974,5004.2
XS Rating Curve= 0 ,0
Exp/Cntr=0.3,0.1

Type RM Length L Ch R = 1 ,20629   ,776,776,776
BEGIN DESCRIPTION:
FISH CREEK 30.0
END DESCRIPTION:
XS GIS Cut Line= 3
      3802540.42     10101052.73      3802686.68     10100403.19
      3802174.18     10099625.35
#Sta/Elev= 30
  4527.5  179.19  4536.4  178.15  4549.7  178.53  4628.1  170.98  4676.5  168.16
  4703.5  165.23  4734.2  163.31    4903  161.58  4946.3  164.11  4980.2  163.49
  4984.4  159.68  4994.7  159.68  5000.7  161.62 5019.61163.5606    5052  166.97
    5093   168.7  5207.8   170.3  5279.7  172.48  5511.2  172.02  5560.5  172.91
  5598.6  173.15  5676.8  170.07  5701.4  169.94  5785.3  171.46  5794.3  172.61
  5875.6  174.86  5929.8  175.39    5987  174.24  6038.2  174.68  6124.8   177.6
#Mann= 6 ,-1 , 0
  4527.5     .17       0  4980.2     .09       0 5019.61     .17       0
  5560.5     .11       0  5701.4     .17       0  5875.6     .11       0
Bank Sta=4980.2,5019.61
XS Rating Curve= 0 ,0
Exp/Cntr=0.3,0.1

Type RM Length L Ch R = 1 ,19853   ,904,904,904
BEGIN DESCRIPTION:
FISH CREEK 29.0
END DESCRIPTION:
XS GIS Cut Line= 2
      3803204.91     10101105.46      3802212.78     10099627.24
#Sta/Elev= 30
  4734.9  185.81  4839.8  178.69  4865.4  175.32  4880.4  175.59    4903  174.16
  4967.4  169.16  4981.1  162.51  4989.3  158.04  4999.6  158.04  5003.4  160.32
  5017.2  162.57  5079.4  161.46  5147.5  163.03  5210.5  161.31  5240.5  163.29
  5312.5  164.97  5320.2  166.17    5498  168.74  5579.6  168.43  5608.2  169.74
  5837.7  173.26  5930.1  172.71  6011.7  173.73  6104.7  171.59  6134.7  172.05
  6140.7  171.07  6177.7  171.88  6283.4   175.1  6428.8  174.89  6515.2  177.23
#Mann= 12 ,-1 , 0
  4734.9     .17       0  4839.8     .11       0    4903     .17       0
  4981.1     .09       0  5017.2     .17       0  5079.4     .11       0
  5320.2     .17       0    5498     .11       0  5608.2     .17       0
  5930.1     .11       0  6177.7     .17       0  6283.4     .11       0
Bank Sta=4981.1,5017.2
XS Rating Curve= 0 ,0
Exp/Cntr=0.3,0.1

Type RM Length L Ch R = 1 ,18949   ,214,214,214
BEGIN DESCRIPTION:
FISH CREEK 28.0
END DESCRIPTION:
XS GIS Cut Line= 3
      3803387.18      10100432.7      3803033.03     10100181.84
      3802221.71     10099594.15
#Sta/Elev= 30
  4560.1  179.24    4596  177.21  4676.2  175.61  4696.4  175.12  4705.1  173.89
  4785.5  168.86  4793.9   168.6  4898.3  161.92  4969.6  159.72  4999.1  157.37
  5000.1  156.69  5010.4  156.69  5012.8  159.12 5017.61159.8415  5055.6  160.09
  5076.4  163.18  5091.1  163.86  5105.8  166.29    5177  169.88  5313.1  172.02
  5392.7  171.61  5528.8  173.51  5562.9  172.83  5647.2  173.02    5729  175.21
  5742.2  176.49  5756.9  175.75  5792.5  176.46  5907.7  176.04  5995.9  177.72
#Mann= 8 ,-1 , 0
  4560.1     .17       0  4676.2     .11       0  4785.5     .17       0
  4793.9     .11       0  4969.6     .07       0 5017.61     .11       0
  5562.9     .17       0  5647.2     .11       0
Bank Sta=4969.6,5017.61
XS Rating Curve= 0 ,0
Exp/Cntr=0.3,0.1

Type RM Length L Ch R = 1 ,18735   ,290,290,290
BEGIN DESCRIPTION:
FISH CREEK 27.0
END DESCRIPTION:
XS GIS Cut Line= 3
      3803417.85     10100311.07      3803167.17     10100053.82
      3802233.59     10099549.05
#Sta/Elev= 30
  4640.8  180.31    4662  179.85    4669  177.81  4697.3  176.75  4746.9  172.72
    4761  170.87    4768  168.25  4789.3  169.63  4888.4  161.89  4937.8  160.81
  4973.2  162.09  4980.2  160.46  4987.4  158.98  4993.3  155.97  5003.6  155.97
  5010.6   159.6  5016.3  160.45  5054.4  161.05  5098.1  159.98  5176.8  169.07
  5215.2   172.5  5289.4  174.49  5436.8  171.84  5500.8  172.22  5533.5  173.14
  5693.7  172.79    5782  174.77  5939.2  176.49  5966.8  175.85  6061.3  177.87
#Mann= 6 ,-1 , 0
  4640.8     .17       0  4980.2     .09       0  5016.3     .17       0
  5176.8     .11       0  5500.8     .17       0    5782     .11       0
Bank Sta=4980.2,5016.3
XS Rating Curve= 0 ,0
Exp/Cntr=0.3,0.1

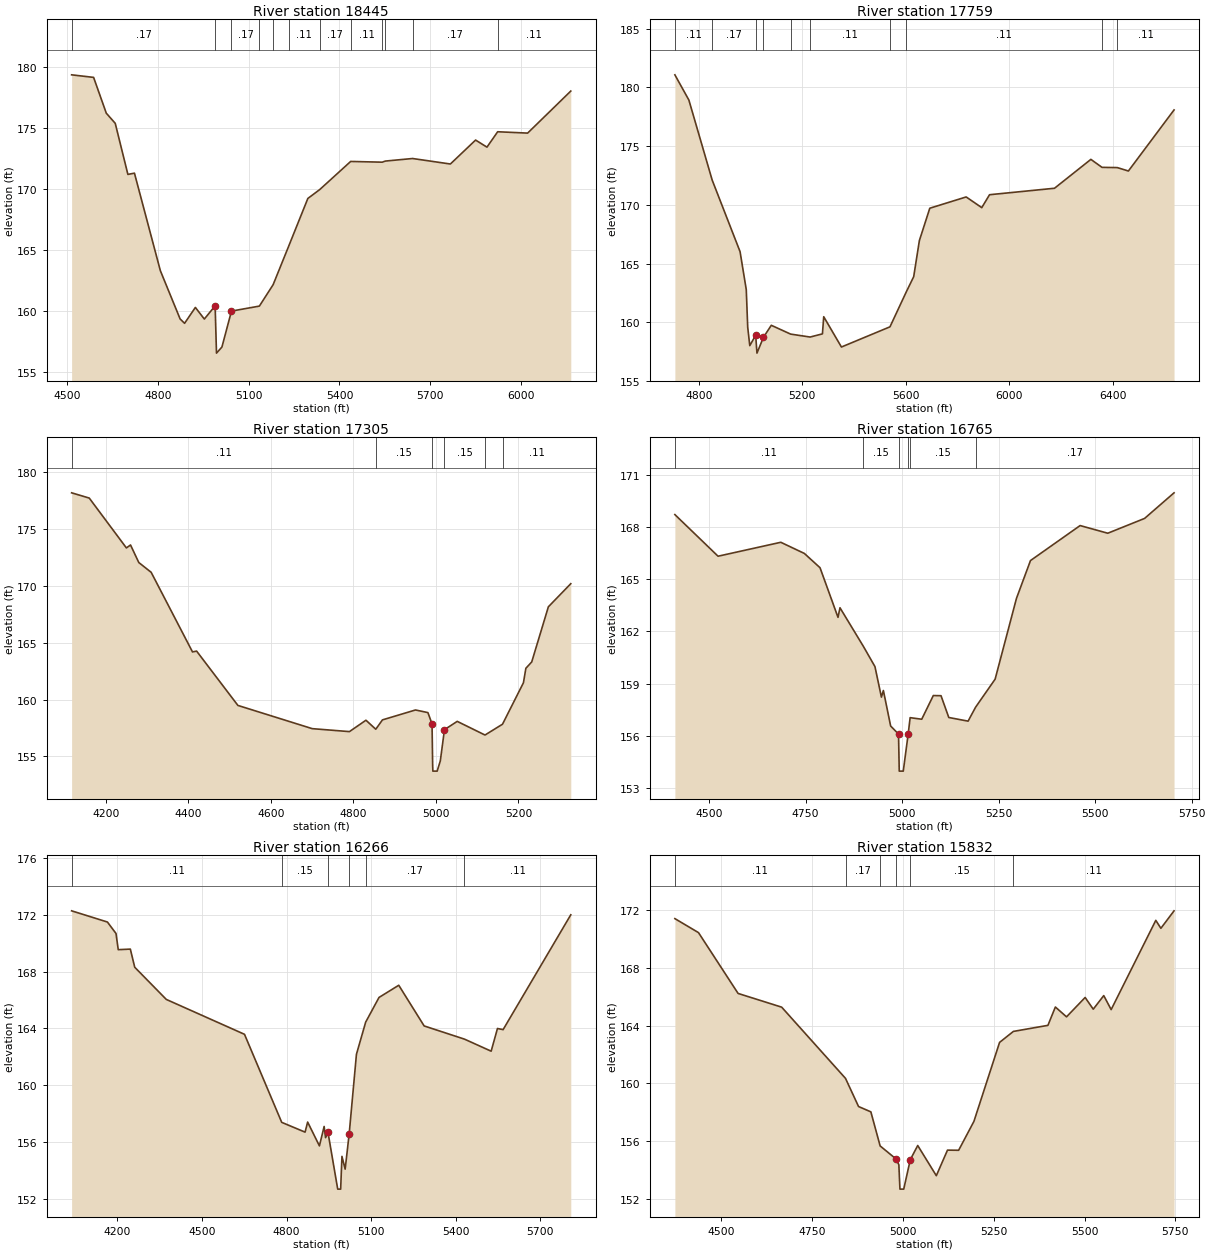
Type RM Length L Ch R = 1 ,18445   ,686,686,686
BEGIN DESCRIPTION:
FISH CREEK 26.0
END DESCRIPTION:
XS GIS Cut Line= 3
      3803617.85     10100261.07      3803338.82     10099863.88
      3802228.37     10099512.58
#Sta/Elev= 30
  4514.6  179.36  4587.3  179.15  4629.2  176.22  4658.8  175.39  4700.6  171.21
  4722.3  171.31  4807.9  163.33  4873.2  159.38    4888  159.02  4923.7  160.32
  4953.3  159.37    4989  160.45  4993.5  156.58  5011.5  157.08    5043  160.02
  5135.3  160.43  5180.7  162.18  5232.6  165.36  5295.5  169.24  5334.9  169.97
  5437.1  172.27  5541.3  172.21  5551.7   172.3  5641.6  172.51  5766.7  172.06
    5850  174.02  5887.6  173.44    5923   174.7  6022.1  174.59  6164.7  178.03
#Mann= 12 ,-1 , 0
  4514.6     .17       0    4989     .09       0    5043     .17       0
  5135.3     .11       0  5180.7     .17       0  5232.6     .11       0
  5334.9     .17       0  5437.1     .11       0  5541.3     .17       0
  5551.7     .11       0  5641.6     .17       0    5923     .11       0
Bank Sta=4989,5043
XS Rating Curve= 0 ,0
Exp/Cntr=0.3,0.1

Type RM Length L Ch R = 1 ,17759   ,454,454,454
BEGIN DESCRIPTION:
FISH CREEK 25.0
END DESCRIPTION:
XS GIS Cut Line= 3
      3804117.88     10099711.08      3803847.92     10099599.79
      3802217.81     10099461.07
#Sta/Elev= 30
    4708  181.07  4762.1  178.92    4852  172.11  4959.8  166.01  4983.7  162.78
  4989.3  159.58  4997.3  158.01  5020.1  158.89    5025  157.37  5050.2  158.72
  5080.4  159.74  5155.1  158.99  5230.3  158.74  5277.9  159.01  5282.9  160.47
  5351.3  157.89  5538.8  159.61  5602.1   162.6  5630.4  163.88  5652.4  166.96
  5692.6  169.71  5833.1  170.67  5893.3  169.76  5923.4  170.86  6174.3  171.41
  6314.8  173.87  6357.8  173.19  6416.7  173.17  6459.7  172.88    6636  178.08
#Mann= 10 ,-1 , 0
    4708     .11       0    4852     .17       0  5020.1     .09       0
  5050.2     .11       0  5155.1     .17       0  5230.3     .11       0
  5538.8     .17       0  5602.1     .11       0  6357.8     .17       0
  6416.7     .11       0
Bank Sta=5020.1,5050.2
XS Rating Curve= 0 ,0
Exp/Cntr=0.3,0.1

Type RM Length L Ch R = 1 ,17305   ,540,540,540
BEGIN DESCRIPTION:
FISH CREEK 24.0
END DESCRIPTION:
XS GIS Cut Line= 3
       3804730.5     10099193.56      3803848.41     10099220.57
      3803523.94     10099258.66
#Sta/Elev= 30
  4117.5  178.15  4160.2  177.69  4250.2  173.31  4260.2  173.57  4280.2  172.03
  4310.2  171.17  4410.3  164.18  4420.3  164.25  4520.3  159.48  4700.4  157.44
  4790.5  157.18  4830.5  158.18  4854.3  157.39  4870.5  158.21  4950.5  159.08
  4980.6  158.85  4990.6  157.86  4992.1  154.21  4992.6  153.71    5003  153.71
  5010.6   154.6  5020.7  157.35  5051.6  158.08  5118.9  156.88  5161.3  157.83
    5212  161.47  5217.9  162.74  5232.1   163.3  5272.4  168.14  5326.7  170.17
#Mann= 6 ,-1 , 0
  4117.5     .11       0  4854.3     .15       0  4990.6     .09       0
  5020.7     .15       0  5118.9     .17       0  5161.3     .11       0
Bank Sta=4990.6,5020.7
XS Rating Curve= 0 ,0
Exp/Cntr=0.3,0.1

Type RM Length L Ch R = 1 ,16765   ,499,499,499
BEGIN DESCRIPTION:
FISH CREEK 23.0
END DESCRIPTION:
XS GIS Cut Line= 4
      3804517.85     10098861.07      3803938.75     10098756.85
      3803642.25     10098765.49      3803306.56     10098996.99
#Sta/Elev= 30
  4411.6   168.7  4523.4  166.31  4685.9  167.11  4746.9  166.47  4787.5  165.65
  4834.1   162.8  4839.2  163.35  4899.9  161.13  4929.8  159.97  4946.5  158.22
  4951.6   158.6  4970.4  156.56  4990.8   156.1  4992.7  153.97  5003.1  153.97
 5015.95156.1194  5020.9  157.04  5050.9  156.95  5080.9  158.31  5100.9   158.3
    5121  157.05    5171  156.84  5190.4  157.64    5241  159.25  5296.3  163.89
  5332.6  166.06  5461.1  168.07  5532.8  167.63  5628.1  168.48  5704.4  169.95
#Mann= 6 ,-1 , 0
  4411.6     .11       0  4899.9     .15       0  4990.8     .09       0
 5015.95     .12       0  5020.9     .15       0  5190.4     .17       0
Bank Sta=4990.8,5015.95
XS Rating Curve= 0 ,0
Exp/Cntr=0.3,0.1

Type RM Length L Ch R = 1 ,16266   ,434,434,434
BEGIN DESCRIPTION:
FISH CREEK 22.0
END DESCRIPTION:
XS GIS Cut Line= 3
      3804692.82     10098536.07      3803745.55     10098364.41
      3802937.94     10098336.35
#Sta/Elev= 30
  4037.3   172.3  4164.3  171.51  4194.8   170.7  4202.7  169.56  4245.6   169.6
  4261.2  168.32  4373.2  166.05  4650.6  163.59  4782.6  157.38  4865.5  156.69
  4874.6   157.4  4916.4  155.72  4933.1  157.09  4938.2   156.3  4946.8  156.67
  4981.3  152.67  4991.7  152.67  4996.3  154.98  5007.7  154.08    5022156.5762
  5047.7  162.18  5080.5  164.45  5127.8  166.19  5197.8  167.05  5287.9  164.18
  5430.9  163.25  5525.6   162.4    5548     164    5568  163.92  5808.1  172.02
#Mann= 6 ,-1 , 0
  4037.3     .11       0  4782.6     .15       0  4946.8     .09       0
    5022     .15       0  5080.5     .17       0  5430.9     .11       0
Bank Sta=4946.8,5022
XS Rating Curve= 0 ,0
Exp/Cntr=0.3,0.1

Type RM Length L Ch R = 1 ,15832   ,558,558,558
BEGIN DESCRIPTION:
FISH CREEK 21.0
END DESCRIPTION:
XS GIS Cut Line= 3
      3804476.58     10098271.24      3803907.96      10098006.8
      3803178.84     10097848.07
#Sta/Elev= 30
  4372.9  171.41  4437.9  170.44  4546.8  166.23  4666.7  165.28  4842.3  160.35
  4878.2   158.4  4912.1  158.03  4937.6  155.67  4980.8  154.78  4989.1  154.37
  4992.1  152.68  5002.5  152.68  5020.6  154.72    5041   155.7  5092.2  153.61
  5122.9  155.38  5153.6  155.37  5195.6  157.37  5266.2  162.84  5304.2   163.6
  5399.2  164.02  5419.7  165.29  5450.4  164.61  5501.6  165.95  5523.9  165.14
  5552.8  166.08  5573.2  165.11    5696  171.29    5710  170.74  5746.2  171.95
#Mann= 6 ,-1 , 0
  4372.9     .11       0  4842.3     .17       0  4937.6     .15       0
  4980.8     .09       0  5020.6     .15       0  5304.2     .11       0
Bank Sta=4980.8,5020.6
XS Rating Curve= 0 ,0
Exp/Cntr=0.3,0.1

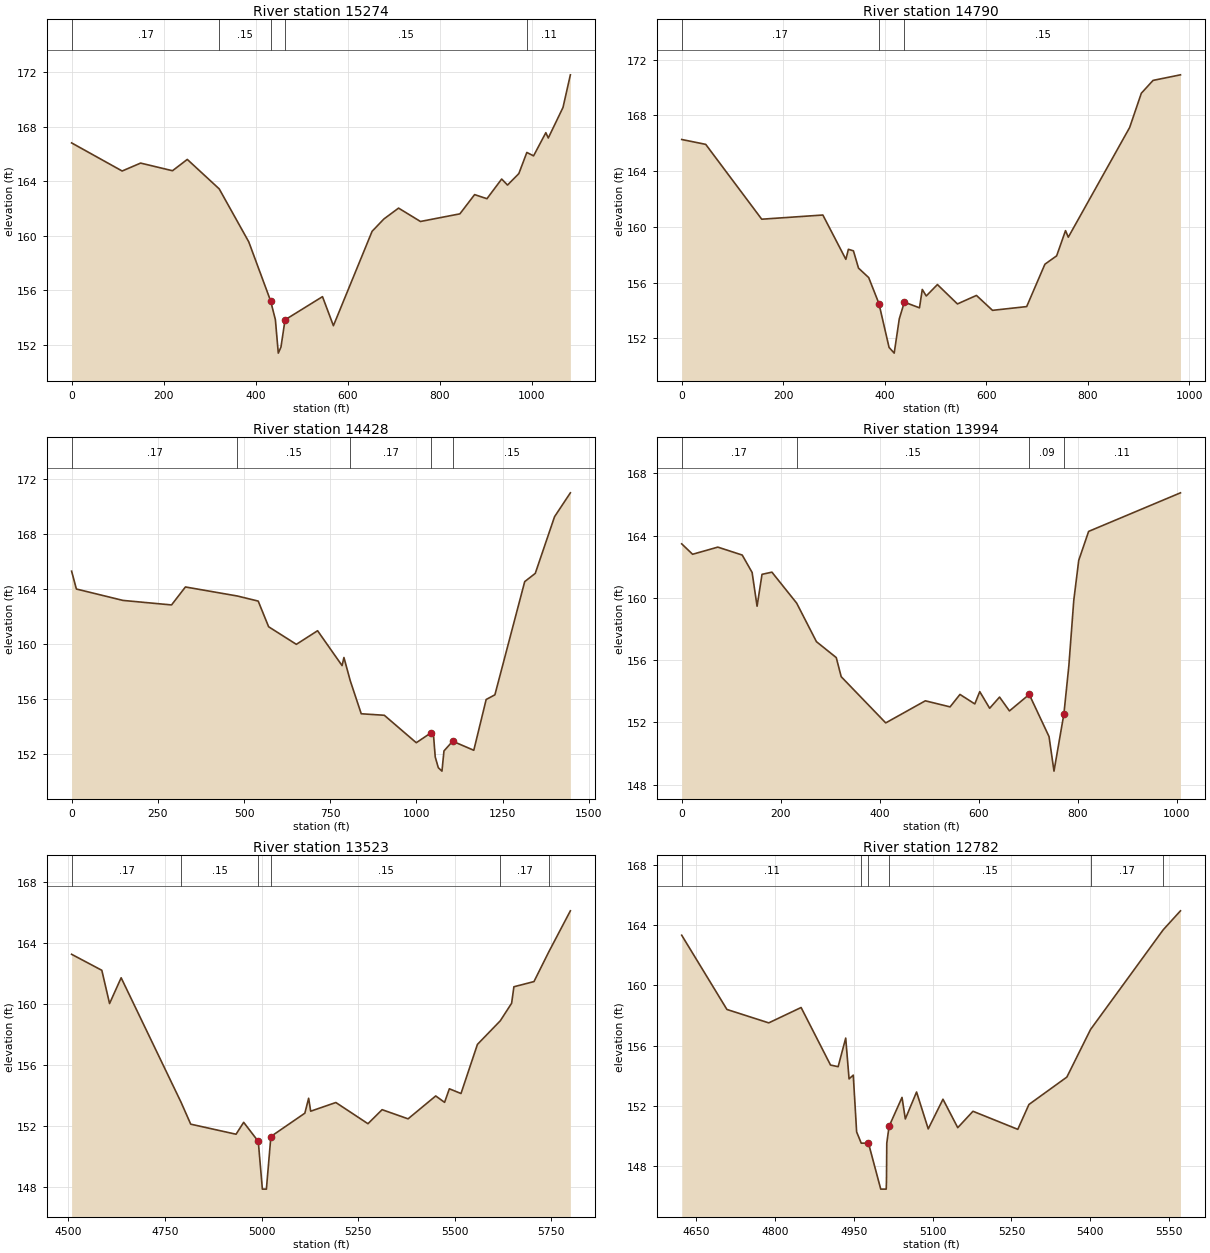
Type RM Length L Ch R = 1 ,15274   ,499,499,499
BEGIN DESCRIPTION:
FISH CREEK 20.0
END DESCRIPTION:
XS GIS Cut Line= 4
      3804257.73     10097437.15      3804084.79     10097431.24
      3803816.38     10097517.52      3803217.85     10097711.07
#Sta/Elev= 30
       0  166.81   109.9  164.75     150  165.33   219.3  164.77   251.4   165.6
   320.8  163.44     385  159.56   432.4  155.24   442.9  153.85   449.2   151.4
     455  151.84   463.9  153.84   545.3  155.54     569  153.41   653.1  160.33
   678.6  161.23   710.6  162.03   758.2  161.05   843.9  161.61   875.9  163.02
   902.7  162.72   934.7  164.16   947.4  163.72     972  164.56   989.4  166.11
    1004  165.86  1030.7  167.56    1036  167.17    1068  169.41    1084   171.8
#Mann= 5 ,-1 , 0
       0     .17       0   320.8     .15       0   432.4     .09       0
   463.9     .15       0   989.4     .11       0
Bank Sta=432.4,463.9
XS Rating Curve= 0 ,0
Exp/Cntr=0.3,0.1

Type RM Length L Ch R = 1 ,14790   ,347,347,347
BEGIN DESCRIPTION:
FISH CREEK 19.0
END DESCRIPTION:
XS GIS Cut Line= 3
      3804094.97     10097151.99      3803648.86     10097116.13
       3803161.5     10097338.09
#Sta/Elev= 30
       0  166.27    47.3  165.92   157.6  160.55     278  160.85   323.3  157.67
   328.3  158.39   338.2  158.28   348.2  157.04   368.3  156.36   388.4   154.5
   408.4  151.35   418.5  150.94   428.5   153.4   438.5   154.6   468.3  154.19
   473.8  155.51   481.6  155.04   503.6  155.86     543  154.47   580.5  155.08
   612.1  154.01   679.4  154.28   715.3  157.32   738.4  157.92   755.9  159.73
   761.4  159.26   882.2  167.13   905.2  169.59   928.3  170.51   982.3  170.91
#Mann= 3 ,-1 , 0
       0     .17       0   388.4     .09       0   438.5     .15       0
Bank Sta=388.4,438.5
XS Rating Curve= 0 ,0
Exp/Cntr=0.3,0.1

Type RM Length L Ch R = 1 ,14428   ,434,434,434
BEGIN DESCRIPTION:
FISH CREEK 18.0
END DESCRIPTION:
XS GIS Cut Line= 3
      3804466.06     10096684.54      3803760.91     10096759.36
      3803067.85     10097011.07
#Sta/Elev= 30
       0  165.29    13.9  163.99     149  163.16   289.8  162.83   330.1  164.14
   480.9  163.48   541.2  163.11   571.4  161.24   651.8  159.96   713.4  160.95
   784.4  158.41   789.8     159   808.1  157.31     840   154.9   906.9  154.79
   999.6  152.79  1042.2  153.51  1049.3  153.43  1054.6  151.75  1063.5  150.97
  1074.1  150.72  1079.9  152.19  1105.1   152.9  1166.4  152.24  1202.3  155.94
  1227.6  156.28  1314.1  164.53  1344.7  165.13  1400.6  169.26  1446.5     171
#Mann= 5 ,-1 , 0
       0     .17       0   480.9     .15       0   808.1     .17       0
  1042.2     .09       0  1105.1     .15       0
Bank Sta=1042.2,1105.1
XS Rating Curve= 0 ,0
Exp/Cntr=0.3,0.1

Type RM Length L Ch R = 1 ,13994   ,471,471,471
BEGIN DESCRIPTION:
Mapping XS 736b1a81
END DESCRIPTION:
XS GIS Cut Line= 3
      3804059.81     10096620.74      3803954.34     10096628.93
      3803051.54     10096628.93
#Sta/Elev= 30
       0  163.47      22   162.8      73  163.26   122.3  162.75   142.3  161.63
   152.3  159.46   162.3  161.51   182.3  161.65   232.3  159.66   272.3  157.18
   312.3  156.16   322.3  154.93   412.3  151.96   492.3  153.38   542.3  152.99
   562.3  153.79   592.3  153.18   602.3  153.97   622.3   152.9   642.3  153.62
   662.3  152.73   702.3  153.79   742.3  151.08   752.3  148.86   772.3  152.53
   782.3  155.62   792.3  159.84   802.3  162.41   822.3  164.27  1007.9  166.75
#Mann= 4 ,-1 , 0
       0     .17       0   232.3     .15       0   702.3     .09       0
   772.3     .11       0
Bank Sta=702.3,772.3
XS Rating Curve= 0 ,0
Exp/Cntr=0.3,0.1

Type RM Length L Ch R = 1 ,13523   ,741,741,741
BEGIN DESCRIPTION:
Mapping XS 37a5578e
END DESCRIPTION:
XS GIS Cut Line= 4
      3804016.01     10096604.65      3803660.67     10096598.03
      3803561.35     10096278.02      3803052.16     10096595.43
#Sta/Elev= 30
  4508.6  163.23  4586.8  162.18  4606.8     160  4636.8  161.69  4792.1  153.51
  4816.8  152.09  4934.1  151.43  4953.8  152.21  4991.6  150.96  5002.2  147.83
  5012.6  147.83  5024.2  151.28  5112.1  152.81  5121.9  153.79  5127.2  152.94
  5192.3  153.51  5275.4  152.12    5312  153.04  5379.2  152.44  5450.7  153.94
  5473.6  153.52    5486  154.41  5516.1   154.1  5558.6  157.32  5617.8  158.87
  5647.1  160.02    5653   161.1  5704.9  161.44  5743.3  163.39  5799.1  166.08
#Mann= 6 ,-1 , 0
  4508.6     .17       0  4792.1     .15       0  4991.6     .09       0
  5024.2     .15       0  5617.8     .17       0  5743.3     .11       0
Bank Sta=4991.6,5024.2
XS Rating Curve= 0 ,0
Exp/Cntr=0.3,0.1

Type RM Length L Ch R = 1 ,12782   ,989,989,989
BEGIN DESCRIPTION:
FISH CREEK 17.0
END DESCRIPTION:
XS GIS Cut Line= 4
       3803751.4     10095992.73      3803533.75     10096028.44
      3803410.61     10096125.89      3803063.35      10096580.3
#Sta/Elev= 30
  4622.4  163.33  4708.5   158.4  4788.1  157.51  4849.7  158.53  4905.7  154.71
  4920.2   154.6  4934.6   156.5    4941  153.79    4949  154.04  4955.4  150.27
  4964.2  149.52  4977.9  149.53  5001.3  146.47  5011.7  146.47  5012.2  146.97
  5012.8  149.52 5017.14 150.636  5041.8  152.56  5048.1  151.13  5069.5  152.92
  5091.7  150.47  5119.8  152.44  5147.9  150.55  5176.9  151.64  5262.2  150.44
  5283.4  152.09  5355.6  153.91  5400.7  157.07    5539  163.69  5571.9  164.95
#Mann= 6 ,-1 , 0
  4622.4     .11       0  4964.2     .15       0  4977.9     .09       0
 5017.14     .15       0  5400.7     .17       0    5539     .11       0
Bank Sta=4977.9,5017.14
XS Rating Curve= 0 ,0
Exp/Cntr=0.3,0.1

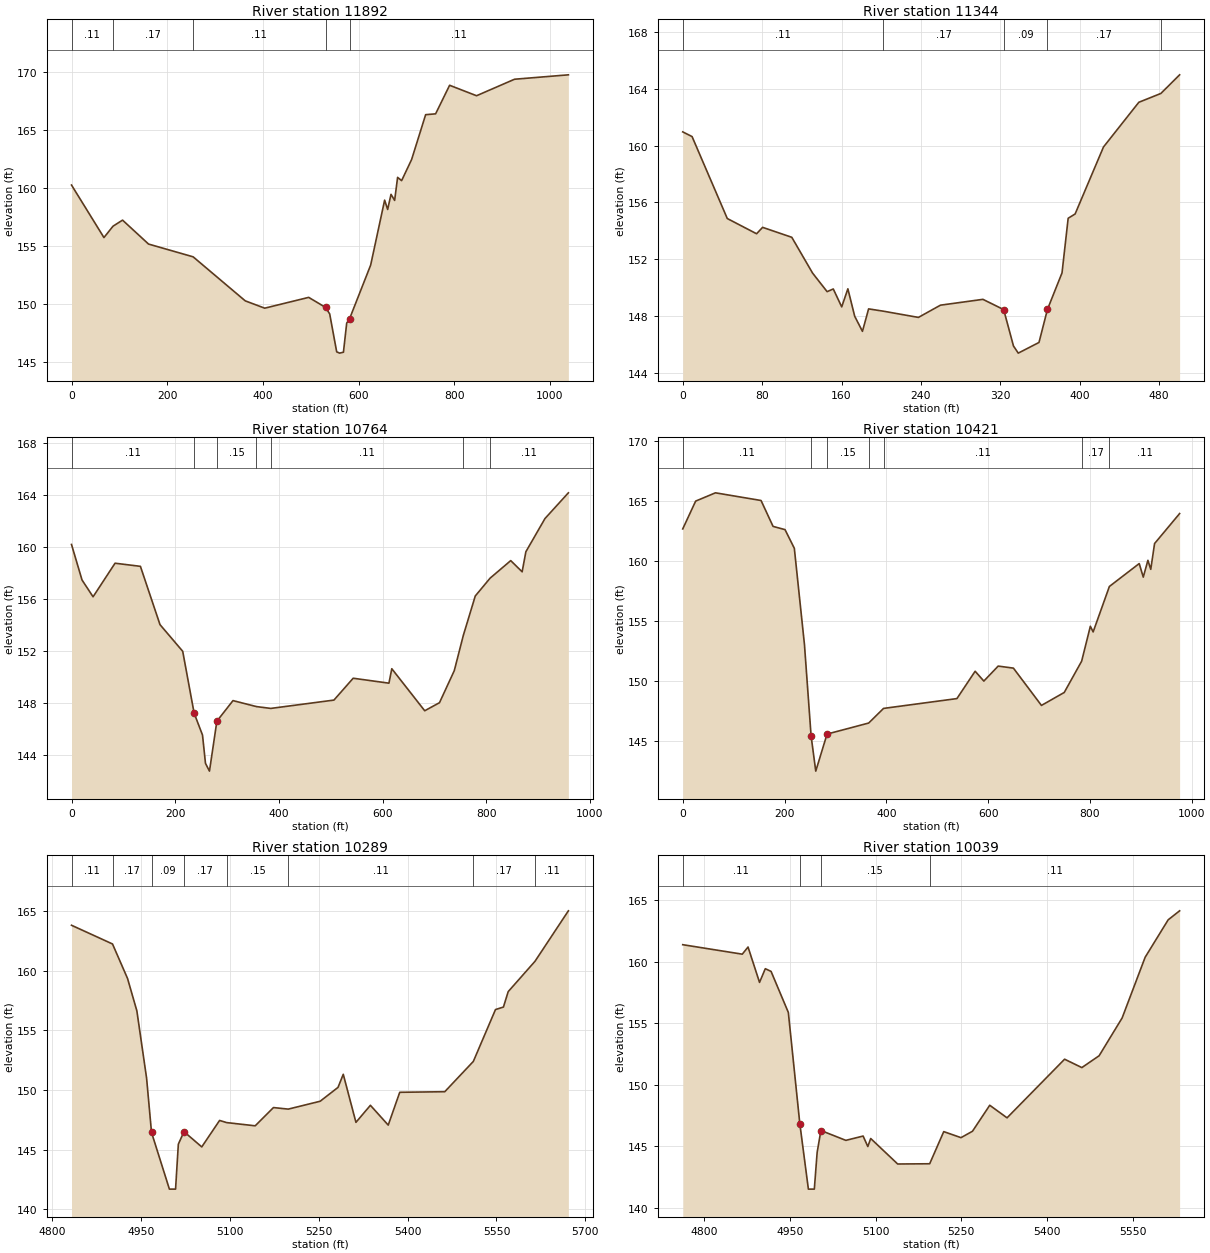
Type RM Length L Ch R = 1 ,11892   ,449,449,449
BEGIN DESCRIPTION:
Mapping XS 841287b6
END DESCRIPTION:
XS GIS Cut Line= 3
      3803362.72     10096039.66      3802980.39     10095956.68
      3802459.55     10096340.79
#Sta/Elev= 30
       0  160.27    67.8  155.75    86.8  156.73   106.7  157.25     161  155.19
   254.2  154.09   363.1   150.3   403.8  149.67   495.7   150.6   531.1  149.73
   539.6  149.17   554.2  145.91   560.4   145.8   568.3  145.88   575.1  148.38
   581.3  148.78   625.2  153.38   654.4  158.97   660.7  158.17   667.7  159.47
   675.3  158.95   681.5  160.93   689.9  160.65   710.8  162.47   740.1  166.33
   760.9   166.4   790.2  168.86   846.5  167.96   925.9  169.38  1038.4  169.76
#Mann= 5 ,-1 , 0
       0     .11       0    86.8     .17       0   254.2     .11       0
   531.1     .06       0   581.3     .11       0
Bank Sta=531.1,581.3
XS Rating Curve= 0 ,0
Exp/Cntr=0.3,0.1

Type RM Length L Ch R = 1 ,11344   ,580,580,580
BEGIN DESCRIPTION:
Mapping XS 8ddfcc8c
END DESCRIPTION:
XS GIS Cut Line= 2
      3803289.89     10095931.52      3802996.36     10095525.44
#Sta/Elev= 30
       0  160.96     9.4  160.63    44.9  154.87    74.4   153.8    80.5  154.25
   109.9  153.55   130.8  151.04   145.5  149.73   151.7  149.92   160.2  148.66
   166.4  149.93   173.3     148   181.1  146.94   187.3  148.52     202  148.36
   237.5  147.92   259.7  148.78   302.5  149.19   323.4  148.47   333.3  145.91
   338.1  145.41     359  146.16   367.5148.4781   382.2  151.05   388.4  154.89
   395.4  155.19     424   159.9   459.6  163.04   481.8  163.66   500.7  164.97
#Mann= 5 ,-1 , 0
       0     .11       0     202     .17       0   323.4     .09       0
   367.5     .17       0   481.8     .11       0
Bank Sta=323.4,367.5
XS Rating Curve= 0 ,0
Exp/Cntr=0.3,0.1

Type RM Length L Ch R = 1 ,10764   ,343,343,343
BEGIN DESCRIPTION:
FISH CREEK 16.0
END DESCRIPTION:
XS GIS Cut Line= 4
      3803380.55     10096042.56      3803475.43     10095946.91
      3803598.52       10095717.      3803086.81     10095482.62
#Sta/Elev= 30
       0  160.17    20.3  157.44    41.6  156.15      84  158.73   132.9  158.49
   170.7  154.01   214.5  151.96   236.5  147.21   252.7  145.52   258.4  143.35
   266.1  142.75   280.4  146.59   311.5  148.17   356.8  147.71   384.4  147.57
   506.2  148.21   543.3  149.89   612.3  149.51   617.8  150.62   681.3  147.39
   709.8  148.01   738.3  150.47   755.8  153.19   778.8  156.21   807.4  157.58
   847.2  158.93   869.2  158.07   876.4  159.61   913.2  162.16   958.4  164.14
#Mann= 7 ,-1 , 0
       0     .11       0   236.5     .06       0   280.4     .15       0
   356.8     .17       0   384.4     .11       0   755.8     .17       0
   807.4     .11       0
Bank Sta=236.5,280.4
XS Rating Curve= 0 ,0
Exp/Cntr=0.3,0.1

Type RM Length L Ch R = 1 ,10421   ,132,132,132
BEGIN DESCRIPTION:
FISH CREEK 16.0
END DESCRIPTION:
XS GIS Cut Line= 3
      3803872.61     10096000.15      3803785.81     10095798.76
      3803103.52     10095470.64
#Sta/Elev= 30
       0  162.67    25.4  164.99    64.3  165.68   153.9  165.04   177.5  162.88
     201  162.61   219.3  161.05   239.2  153.02   252.2  145.42   261.4  142.47
   283.6  145.56   365.4  146.48   394.6   147.7   538.8  148.52   574.6   150.8
   591.7  149.98   619.9  151.23   649.8  151.06   704.9  147.95   749.7  149.03
   783.9  151.64     801  154.55   806.5  154.08   838.4  157.87     897  159.78
     905  158.65   914.1  160.05   919.7   159.3   927.2  161.45   976.4  163.95
#Mann= 7 ,-1 , 0
       0     .11       0   252.2     .06       0   283.6     .15       0
   365.4     .17       0   394.6     .11       0   783.9     .17       0
   838.4     .11       0
Bank Sta=252.2,283.6
XS Rating Curve= 0 ,0
Exp/Cntr=0.3,0.1

Type RM Length L Ch R = 1 ,10289   ,250,250,250
BEGIN DESCRIPTION:
FISH CREEK 15.0
END DESCRIPTION:
XS GIS Cut Line= 2
      3803916.23     10095705.28      3803132.95     10095406.02
#Sta/Elev= 30
  4832.9  163.81  4902.1  162.24  4927.5  159.34  4943.2  156.63  4959.6  150.99
  4967.9  146.44  4998.1  141.68  5008.5  141.68  5013.2  145.45  5022.7   146.5
  5052.7  145.22  5082.8  147.44  5094.7  147.26  5142.9  146.99  5173.7  148.52
  5198.7  148.39  5252.5  149.05  5282.6  150.21  5291.5  151.31  5312.9  147.28
  5337.3  148.71  5367.4  147.05  5386.8   149.8  5462.8  149.85    5511  152.39
  5548.4  156.74  5561.8  156.95  5569.8  158.24  5615.1  160.79  5671.4  165.02
#Mann= 8 ,-1 , 0
  4832.9     .11       0  4902.1     .17       0  4967.9     .09       0
  5022.7     .17       0  5094.7     .15       0  5198.7     .11       0
    5511     .17       0  5615.1     .11       0
Bank Sta=4967.9,5022.7
XS Rating Curve= 0 ,0
Exp/Cntr=0.3,0.1

Type RM Length L Ch R = 1 ,10039   ,676,676,676
BEGIN DESCRIPTION:
FISH CREEK 14.0
END DESCRIPTION:
XS GIS Cut Line= 2
      3804011.33      10095425.2      3803147.97     10095321.16
#Sta/Elev= 30
  4762.6  161.37  4866.8   160.6  4876.9  161.18    4897  158.31  4907.1  159.42
  4917.2   159.2  4947.4  155.87  4967.5  146.84  4982.5  141.52  4992.9  141.52
  4997.8  144.49  5004.4  146.28  5048.1  145.48  5078.3  145.83  5086.5  144.98
  5091.6  145.63  5138.8  143.56  5194.8  143.58  5219.4  146.19  5249.6   145.7
  5269.7  146.22  5299.9  148.33  5330.2  147.31  5430.9  152.07  5461.1  151.39
  5491.3  152.35  5531.6  155.42  5571.9  160.35  5612.2  163.39  5632.2  164.12
#Mann= 4 ,-1 , 0
  4762.6     .11       0  4967.5     .09       0  5004.4     .15       0
  5194.8     .11       0
Bank Sta=4967.5,5004.4
XS Rating Curve= 0 ,0
Exp/Cntr=0.3,0.1