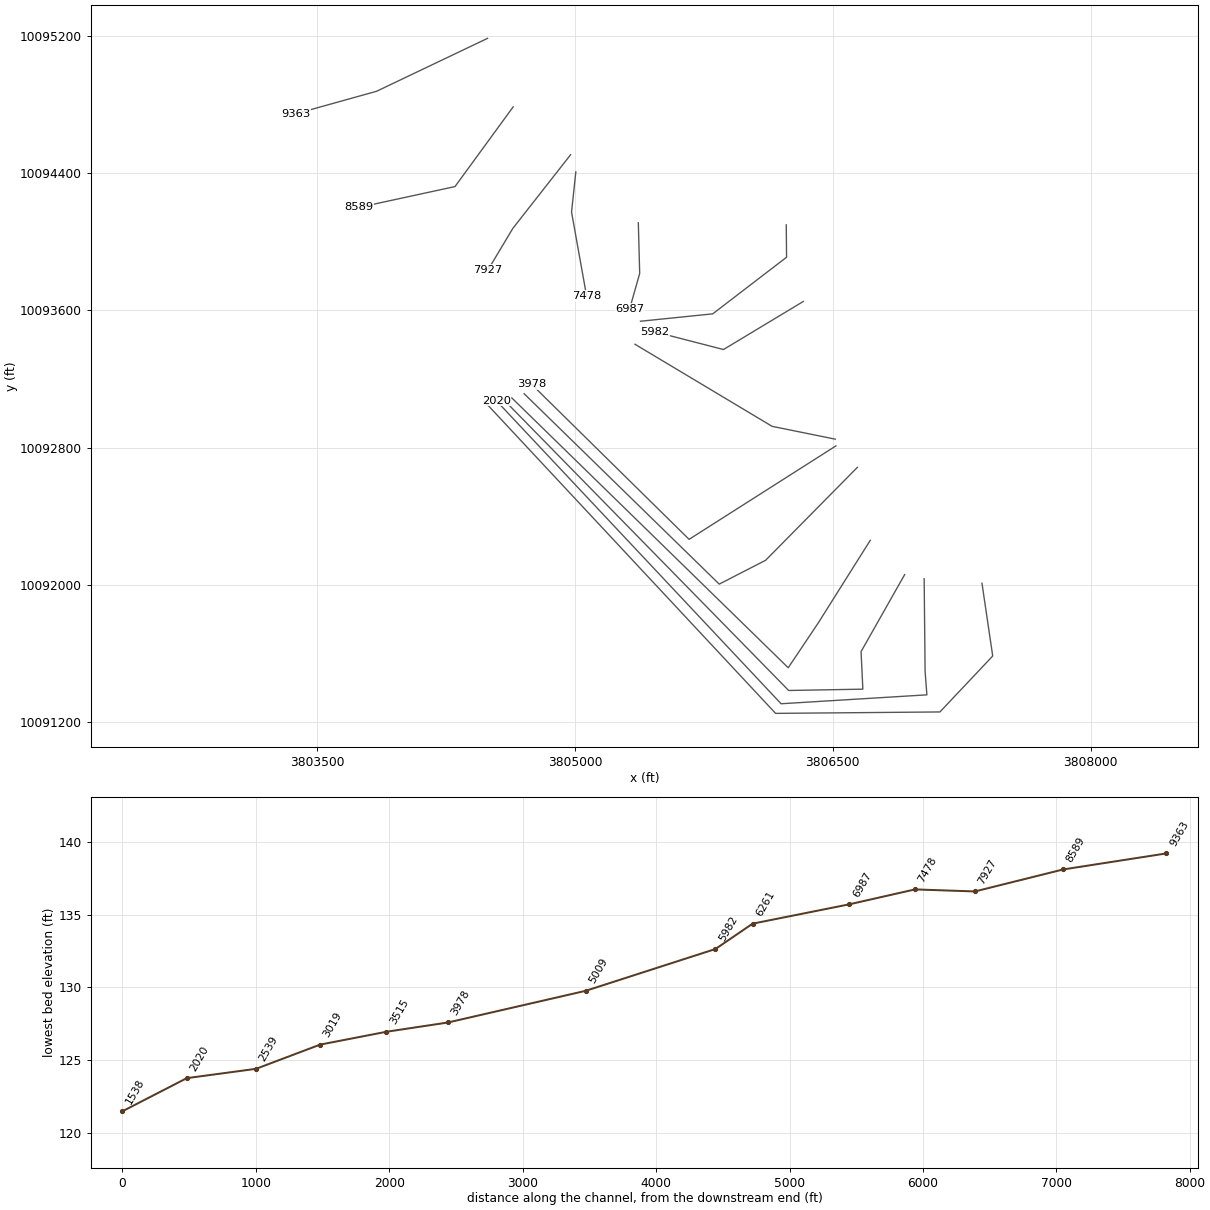
HEC-RAS study FISH CREEK.prj: FISH CREEK Base Level Engineering

--- FISH CREEK.g01 (geometry) --- (continued)

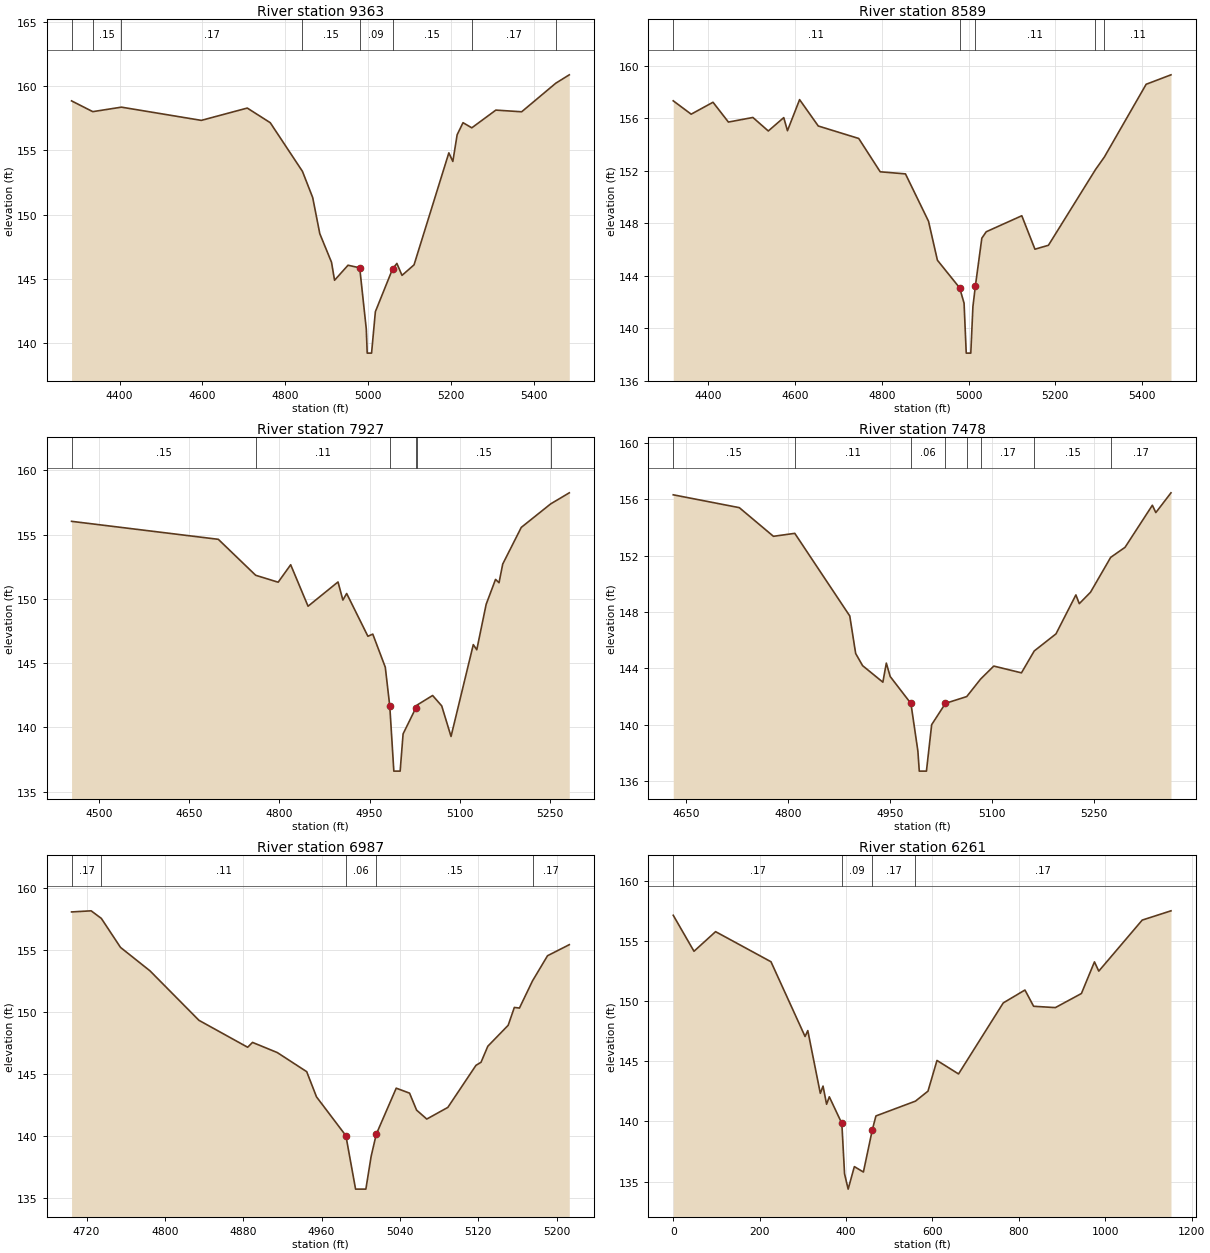
Type RM Length L Ch R = 1 ,9363    ,774,774,774
BEGIN DESCRIPTION:
FISH CREEK 13.0
END DESCRIPTION:
XS GIS Cut Line= 3
      3804490.47     10095185.62      3803844.45     10094877.12
      3803377.18     10094746.82
#Sta/Elev= 30
  4284.1  158.86  4335.3  158.02  4404.5  158.37  4597.3  157.34  4708.1   158.3
  4763.5  157.16  4841.2  153.37    4866  151.32  4883.1  148.51  4911.4  146.28
  4918.7  144.88  4951.2  146.05  4979.4  145.85  4995.3  141.07  4997.5   139.2
    5008   139.2  5017.2  142.43  5058.8  145.77  5069.1  146.19  5081.5  145.26
  5110.5  146.08  5194.5  154.81  5204.1  154.14  5214.5  156.22  5228.7  157.16
  5249.9  156.76  5307.9  158.14  5370.2  158.01  5452.6  160.24  5485.1  160.89
#Mann= 8 ,-1 , 0
  4284.1     .17       0  4335.3     .15       0  4404.5     .17       0
  4841.2     .15       0  4979.4     .09       0  5058.8     .15       0
  5249.9     .17       0  5452.6    .125       0
Bank Sta=4979.4,5058.8
XS Rating Curve= 0 ,0
Exp/Cntr=0.3,0.1

Type RM Length L Ch R = 1 ,8589    ,662,662,662
BEGIN DESCRIPTION:
Mapping XS 3d2ef945
END DESCRIPTION:
XS GIS Cut Line= 3
       3804639.5     10094786.34      3804300.97     10094321.95
      3803741.97     10094200.62
#Sta/Elev= 30
  4319.7  157.33    4361  156.31  4411.3  157.22  4446.8  155.71  4503.2  156.06
  4538.7  155.03  4574.3  156.05  4582.8  155.05  4610.8  157.42  4653.8  155.41
    4747  154.46  4796.5  151.92  4854.7  151.76  4907.8  148.15  4928.3  145.18
  4979.4  143.08  4989.7  141.91  4994.7   138.1  5005.2   138.1  5010.1  141.65
  5015.8  143.22  5030.6  146.86  5040.8  147.35  5122.7  148.57    5153  146.02
  5184.1  146.32  5292.3  152.08    5313  153.05  5409.2  158.59  5466.4  159.31
#Mann= 5 ,-1 , 0
  4319.7     .11       0  4979.4     .06       0  5015.8     .11       0
  5292.3     .15       0    5313     .11       0
Bank Sta=4979.4,5015.8
XS Rating Curve= 0 ,0
Exp/Cntr=0.3,0.1

Type RM Length L Ch R = 1 ,7927    ,449,449,449
BEGIN DESCRIPTION:
FISH CREEK 12.0
END DESCRIPTION:
XS GIS Cut Line= 3
      3804973.84     10094507.57      3804637.42     10094078.16
      3804492.84     10093836.05
#Sta/Elev= 30
  4454.5  156.04  4698.5  154.64  4760.6  151.84    4798   151.3  4818.8  152.66
  4847.7  149.43  4897.5  151.32  4905.6  149.91  4911.9  150.42  4947.2  147.09
  4955.3  147.26  4976.1  144.68  4983.6  141.63  4990.3  136.59  5000.8  136.59
  5005.7  139.49  5027.1  141.53  5029.1  141.74  5054.8  142.48  5069.9  141.67
  5085.4  139.29  5122.4  146.44  5128.2  146.04  5143.8  149.58  5159.4  151.52
  5165.2  151.26  5171.3  152.71  5202.2  155.57  5251.1   157.4    5282  158.26
#Mann= 6 ,-1 , 0
  4454.5     .15       0  4760.6     .11       0  4983.6     .06       0
  5027.1     .11       0  5029.1     .15       0  5251.1     .17       0
Bank Sta=4983.6,5027.1
XS Rating Curve= 0 ,0
Exp/Cntr=0.3,0.1

Type RM Length L Ch R = 1 ,7478    ,491,491,491
BEGIN DESCRIPTION:
FISH CREEK 11.0
END DESCRIPTION:
XS GIS Cut Line= 3
      3805004.19     10094407.68      3804979.24     10094173.46
      3805066.84     10093684.49
#Sta/Elev= 30
  4630.7   156.3  4727.9  155.39  4778.1  153.36  4809.5  153.57  4890.4  147.72
  4899.1  145.06  4909.3   144.2  4939.1  143.03  4944.2  144.38  4949.9  143.43
  4980.4  141.52  4990.6  138.16  4992.7  136.73  5003.2  136.73  5010.9  140.02
  5031.2  141.53  5062.5  142.01  5082.9  143.25  5102.3  144.17    5143  143.69
  5161.8  145.24  5193.8  146.45  5223.1  149.21  5228.1  148.59  5244.6   149.4
  5274.3  151.87  5295.4  152.58  5335.6  155.56  5340.7  155.04    5363  156.44
#Mann= 8 ,-1 , 0
  4630.7     .15       0  4809.5     .11       0  4980.4     .06       0
  5031.2     .11       0  5062.5     .15       0  5082.9     .17       0
  5161.8     .15       0  5274.3     .17       0
Bank Sta=4980.4,5031.2
XS Rating Curve= 0 ,0
Exp/Cntr=0.3,0.1

Type RM Length L Ch R = 1 ,6987    ,726,726,726
BEGIN DESCRIPTION:
FISH CREEK 10.0
END DESCRIPTION:
XS GIS Cut Line= 3
      3805367.85      10094111.1      3805375.86     10093815.91
      3805317.85     10093611.06
#Sta/Elev= 30
  4704.7  158.06  4724.7  158.15  4735.1  157.54  4754.7   155.2  4784.8  153.31
  4834.8  149.32  4884.5  147.15  4889.5  147.54  4914.8  146.72  4944.8  145.18
  4954.8  143.15  4984.8  140.02  4994.7  135.71  5005.2  135.71  5010.6  138.36
  5015.8  140.13  5036.2  143.85  5049.8  143.45    5057  142.08  5067.4  141.36
  5088.9   142.3  5117.6  145.69  5122.8  145.94  5129.7  147.23  5150.5  148.92
  5156.8  150.36    5162  150.31  5175.4  152.51  5190.7  154.53  5212.9  155.42
#Mann= 5 ,-1 , 0
  4704.7     .17       0  4735.1     .11       0  4984.8     .06       0
  5015.8     .15       0  5175.4     .17       0
Bank Sta=4984.8,5015.8
XS Rating Curve= 0 ,0
Exp/Cntr=0.3,0.1

Type RM Length L Ch R = 1 ,6261    ,279,279,279
BEGIN DESCRIPTION:
FISH CREEK 9.5
END DESCRIPTION:
XS GIS Cut Line= 4
      3806228.88     10094099.07      3806230.62     10093910.27
      3805800.93     10093580.41      3805380.36     10093537.37
#Sta/Elev= 30
       0  157.13      48  154.14      98  155.77   226.2  153.27   305.1  147.06
   311.4  147.55   340.4  142.34   346.7  142.94   354.9  141.43   361.2  142.05
   390.2  139.84   396.5  135.65   404.8  134.38   419.2  136.25   440.1   135.8
   460.9  139.33   469.1  140.46   560.6  141.69   589.6  142.52   610.4  145.07
   660.3  143.95   763.8  149.85     814  150.92   834.1  149.57   884.4  149.46
   944.7  150.63   974.9  153.26   984.9  152.49  1085.4  156.73    1152   157.5
#Mann= 4 ,-1 , 0
       0     .17       0   390.2     .09       0   460.9     .17       0
   560.6     .17       0
Bank Sta=390.2,460.9
XS Rating Curve= 0 ,0
Exp/Cntr=0.3,0.1

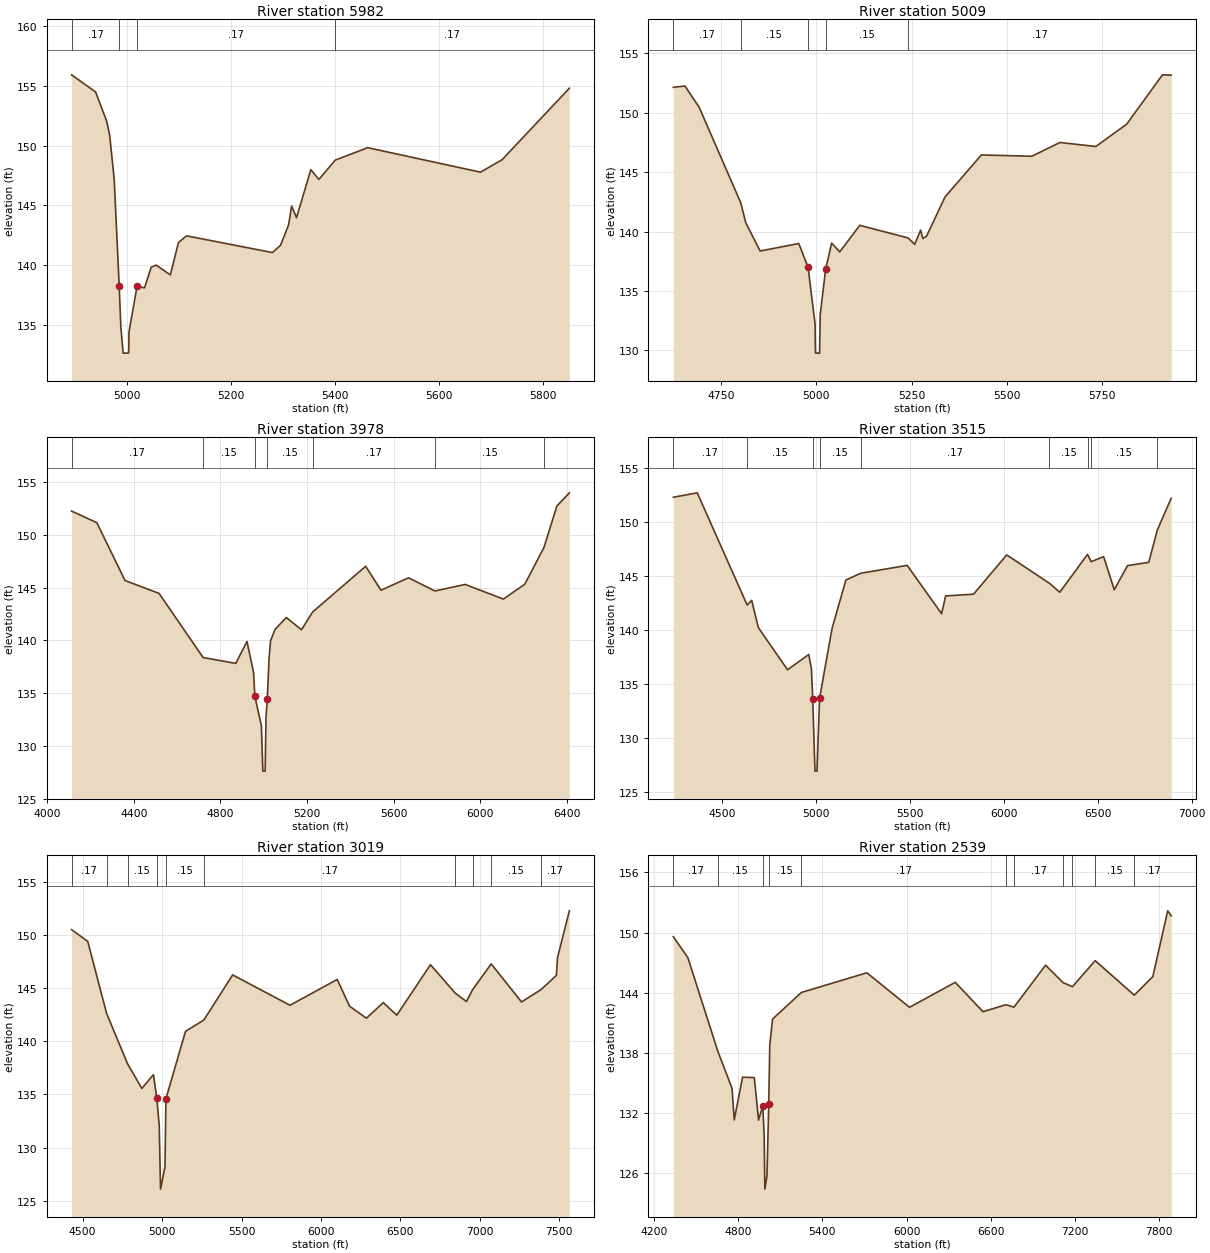
Type RM Length L Ch R = 1 ,5982    ,973,973,973
BEGIN DESCRIPTION:
FISH CREEK 9.0
END DESCRIPTION:
XS GIS Cut Line= 3
      3806328.01     10093652.52      3805863.57     10093372.56
      3805462.61     10093476.03
#Sta/Elev= 30
  4894.2  155.94  4940.3  154.51  4961.7  152.06  4967.5  150.86  4976.1  147.21
 4985.76138.2318  4988.9  134.81  4993.3  132.64  5003.8  132.64  5004.3  133.14
  5004.4  134.38    5020  138.22  5034.5  138.11  5047.2  139.83  5056.8  140.01
    5084  139.19  5099.6   141.9  5115.1  142.46  5280.1  141.06  5295.7  141.67
  5311.2  143.38    5317  144.95  5326.4  143.98  5353.9     148  5369.4  147.18
  5400.8   148.8  5463.1  149.84  5679.9  147.79  5721.3  148.83  5850.6  154.82
#Mann= 4 ,-1 , 0
  4894.2     .17       0 4985.76     .09       0    5020     .17       0
  5400.8     .17       0
Bank Sta=4985.76,5020
XS Rating Curve= 0 ,0
Exp/Cntr=0.3,0.1

Type RM Length L Ch R = 1 ,5009    ,1031,1031,1031
BEGIN DESCRIPTION:
FISH CREEK 8.0
END DESCRIPTION:
XS GIS Cut Line= 3
      3806514.07     10092850.33      3806146.58       10092925.
      3805348.32     10093403.33
#Sta/Elev= 30
    4625  152.13  4655.4  152.24  4692.6  150.46  4801.5  142.44    4815  140.73
  4852.7  138.36    4954  138.99  4978.3     137  4996.8   132.2  4997.4  130.27
  4997.9  129.77  5008.5  129.77  5010.2  133.02  5024.6  136.86  5040.2  139.02
  5061.5  138.29    5114  140.52  5240.6  139.46  5257.9  138.92  5273.5  140.12
  5279.3  139.41    5289   139.6  5337.6  142.91  5432.9  146.44  5565.1  146.33
    5639  147.49    5733  147.15    5814  149.03  5907.8  153.18  5930.6  153.15
#Mann= 5 ,-1 , 0
    4625     .17       0  4801.5     .15       0  4978.3     .09       0
  5024.6     .15       0  5240.6     .17       0
Bank Sta=4978.3,5024.6
XS Rating Curve= 0 ,0
Exp/Cntr=0.3,0.1

Type RM Length L Ch R = 1 ,3978    ,463,463,463
BEGIN DESCRIPTION:
FISH CREEK 7.0
END DESCRIPTION:
XS GIS Cut Line= 3
      3806517.87     10092811.09      3805663.34     10092266.57
      3804745.98      10093170.7
#Sta/Elev= 30
  4111.6  152.27  4228.4  151.17  4358.8  145.68  4516.2  144.46  4719.7  138.38
  4870.9  137.82  4922.5   139.9    4953  136.96  4958.9  134.71  4989.1   131.9
  4995.9   127.6  5006.6   127.6  5010.5  132.73  5016.4  134.43  5024.7  138.29
  5031.7  139.98  5052.8  141.06  5104.5  142.17  5174.4  141.01  5226.3   142.7
  5471.3  147.03    5542  144.76  5669.3  145.94  5791.4  144.69    5931  145.31
  6107.8  143.92  6206.8  145.33  6295.3  148.81  6355.2  152.75  6412.9     154
#Mann= 7 ,-1 , 0
  4111.6     .17       0  4719.7     .15       0  4958.9     .09       0
  5016.4     .15       0  5226.3     .17       0  5791.4     .15       0
  6295.3     .17       0
Bank Sta=4958.9,5016.4
XS Rating Curve= 0 ,0
Exp/Cntr=0.3,0.1

Type RM Length L Ch R = 1 ,3515    ,496,496,496
BEGIN DESCRIPTION:
FISH CREEK 6.0
END DESCRIPTION:
XS GIS Cut Line= 4
      3806642.89     10092686.11      3806108.49     10092144.45
      3805838.69      10092005.8      3804703.24     10093115.21
#Sta/Elev= 30
  4239.1  152.33  4366.4  152.74  4632.1  142.35  4656.3  142.78  4691.7  140.26
  4847.3  136.35  4960.4  137.76  4974.6  136.43  4981.6  133.64  4993.5  126.96
  5004.2  126.96    5018  133.71  5084.5  140.17  5158.1  144.66  5237.7  145.29
  5484.5  146.02  5668.2  141.54  5689.5  143.19    5838  143.35  6014.9  146.99
  6242.5  144.36  6297.6  143.53  6445.3  147.04  6464.9  146.36  6531.1  146.83
  6587.7  143.76  6658.4     146  6771.5   146.3  6817.3  149.31  6890.8  152.23
#Mann= 9 ,-1 , 0
  4239.1     .17       0  4632.1     .15       0  4981.6     .09       0
    5018     .15       0  5237.7     .17       0  6242.5     .15       0
  6445.3     .17       0  6464.9     .15       0  6817.3     .17       0
Bank Sta=4981.6,5018
XS Rating Curve= 0 ,0
Exp/Cntr=0.3,0.1

Type RM Length L Ch R = 1 ,3019    ,480,480,480
BEGIN DESCRIPTION:
FISH CREEK 5.0
END DESCRIPTION:
XS GIS Cut Line= 4
      3806717.83     10092261.03      3806414.75     10091779.11
      3806240.23     10091518.49      3804631.58     10093090.54
#Sta/Elev= 30
  4430.7  150.54  4532.5  149.43  4651.3  142.64  4783.5  137.88  4872.9  135.57
  4945.9  136.87  4967.1  134.65  4982.4  132.07  4990.5  126.08  5018.5  128.19
  5024.6   134.6  5147.6  140.95  5263.2  142.02  5444.4  146.27  5805.2  143.41
  6102.1  145.84  6179.9  143.32  6285.9  142.19  6392.1  143.66    6477  142.47
    6689  147.23    6845  144.55  6915.3  143.76  6954.1  144.88  7071.1  147.31
  7261.8  143.72    7384  144.88  7481.1  146.22  7488.1  147.89  7562.9  152.31
#Mann= 10 ,-1 , 0
  4430.7     .17       0  4651.3     .11       0  4783.5     .15       0
  4967.1     .09       0  5024.6     .15       0  5263.2     .17       0
    6845     .15       0  6954.1     .17       0  7071.1     .15       0
    7384     .17       0
Bank Sta=4967.1,5024.6
XS Rating Curve= 0 ,0
Exp/Cntr=0.3,0.1

Type RM Length L Ch R = 1 ,2539    ,519,519,519
BEGIN DESCRIPTION:
FISH CREEK 4.0
END DESCRIPTION:
XS GIS Cut Line= 5
      3806917.85     10092061.07      3806664.21     10091612.57
      3806674.62     10091393.82      3806242.85     10091386.07
      3804578.46     10093086.34
#Sta/Elev= 30
  4339.3  149.59  4442.7   147.5  4655.9  138.18  4757.2  134.48  4773.1  131.32
  4832.3  135.58  4916.1  135.54  4946.2   131.3  4976.2  132.75  4986.2  129.76
  4990.9  124.42  5006.2  125.76 5018.75132.9046  5026.2  138.82  5046.3  141.38
  5251.3  144.03  5717.6  145.99  6021.6  142.55  6346.9  145.04  6544.9  142.11
  6707.5  142.81  6765.7  142.57  6990.4  146.75  7115.4     145  7181.9  144.61
  7343.7   147.2  7622.2  143.76  7754.1  145.61  7860.2  152.17  7884.7  151.68
#Mann= 11 ,-1 , 0
  4339.3     .17       0  4655.9     .15       0  4976.2     .09       0
 5018.75     .15       0  5251.3     .17       0  6707.5     .15       0
  6765.7     .17       0  7115.4     .15       0  7181.9     .17       0
  7343.7     .15       0  7622.2     .17       0
Bank Sta=4976.2,5018.75
XS Rating Curve= 0 ,0
Exp/Cntr=0.3,0.1

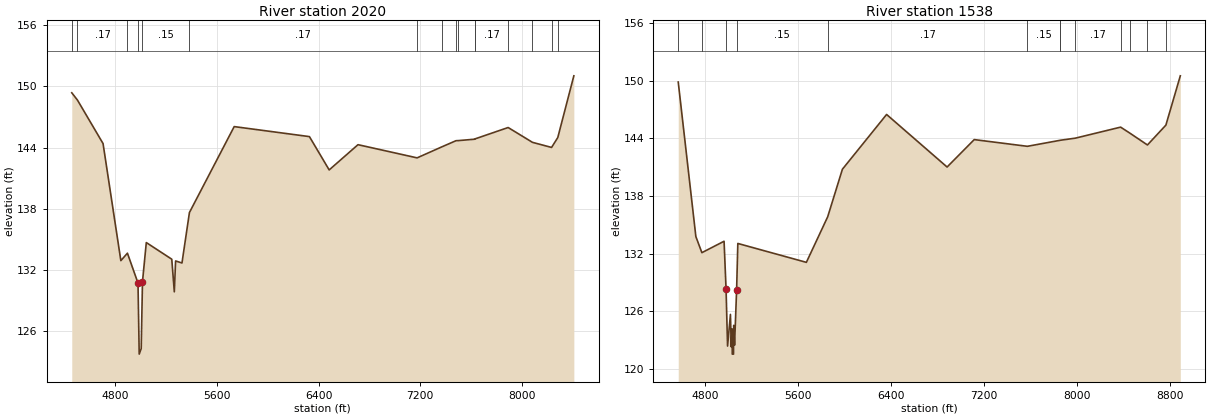
Type RM Length L Ch R = 1 ,2020    ,482,482,482
BEGIN DESCRIPTION:
FISH CREEK 3.0
END DESCRIPTION:
XS GIS Cut Line= 5
       3807031.4     10092037.05      3807036.94     10091496.78
      3807047.26     10091360.67      3806198.71     10091308.75
      3804541.77     10093074.14
#Sta/Elev= 30
  4459.7  149.36  4504.2  148.65  4705.7  144.39  4845.7  132.93  4897.4  133.66
 4980.52130.7309    4990  123.78  5005.7  124.32  5015.8  130.87  5045.8   134.7
  5246.1  133.07  5266.1  129.88  5276.2   132.9  5326.3   132.7    5385  137.64
    5737  146.05  6328.6  145.07  6483.9  141.81  6710.5  144.28  7175.2  142.99
  7370.3  144.07  7481.2  144.67  7500.5  144.68    7631  144.82  7631.5  144.85
  7891.1  145.96  8082.4  144.51  8232.7  144.01  8281.6  144.98  8407.8  151.02
#Mann= 16 ,-1 , 0
  4459.7     .11       0  4504.2     .17       0  4897.4     .15       0
 4980.52     .09       0  5015.8     .15       0    5385     .17       0
  7175.2     .15       0  7370.3     .17       0  7481.2     .15       0
  7500.5     .17       0    7631     .15       0  7631.5     .17       0
  7891.1     .15       0  8082.4     .17       0  8232.7     .11       0
  8281.6     .17       0
Bank Sta=4980.52,5015.8
XS Rating Curve= 0 ,0
Exp/Cntr=0.3,0.1

Type RM Length L Ch R = 1 ,1538    ,0,0,0
BEGIN DESCRIPTION:
FISH CREEK 2.0
END DESCRIPTION:
XS GIS Cut Line= 5
      3807367.85     10092011.09       3807430.4     10091586.88
      3807123.19     10091261.01      3806166.81     10091252.68
      3804472.09     10093070.04
#Sta/Elev= 30
  4571.2  149.88  4722.8  133.77  4774.6  132.09  4965.4  133.28  4982.5  128.29
  4995.4  122.35  5020.2  125.65  5027.1  122.27  5034.4  124.14  5035.9  121.51
  5046.6  121.51  5048.5  124.51  5055.4  122.44 5073.32  128.21  5083.7  133.05
  5673.2  131.08  5856.6  135.83  5983.2  140.79  6363.2   146.5  6883.4  141.02
  7116.9  143.88  7573.9  143.18  7852.4   143.8  7856.5  143.81  7986.3  144.03
  8375.8  145.18  8455.8  144.55  8606.6  143.32  8765.2  145.39  8889.2  150.53
#Mann= 13 ,-1 , 0
  4571.2     .17       0  4774.6     .15       0  4982.5     .09       0
 5073.32     .15       0  5856.6     .17       0  7573.9     .15       0
  7852.4     .17       0  7856.5     .15       0  7986.3     .17       0
  8375.8     .15       0  8455.8     .17       0  8606.6     .11       0
  8765.2     .17       0
Bank Sta=4982.5,5073.32
XS Rating Curve= 0 ,0
Exp/Cntr=0.3,0.1

Chan Stop Cuts=-1
Use User Specified Reach Order=0
Composite Channel Slope=5