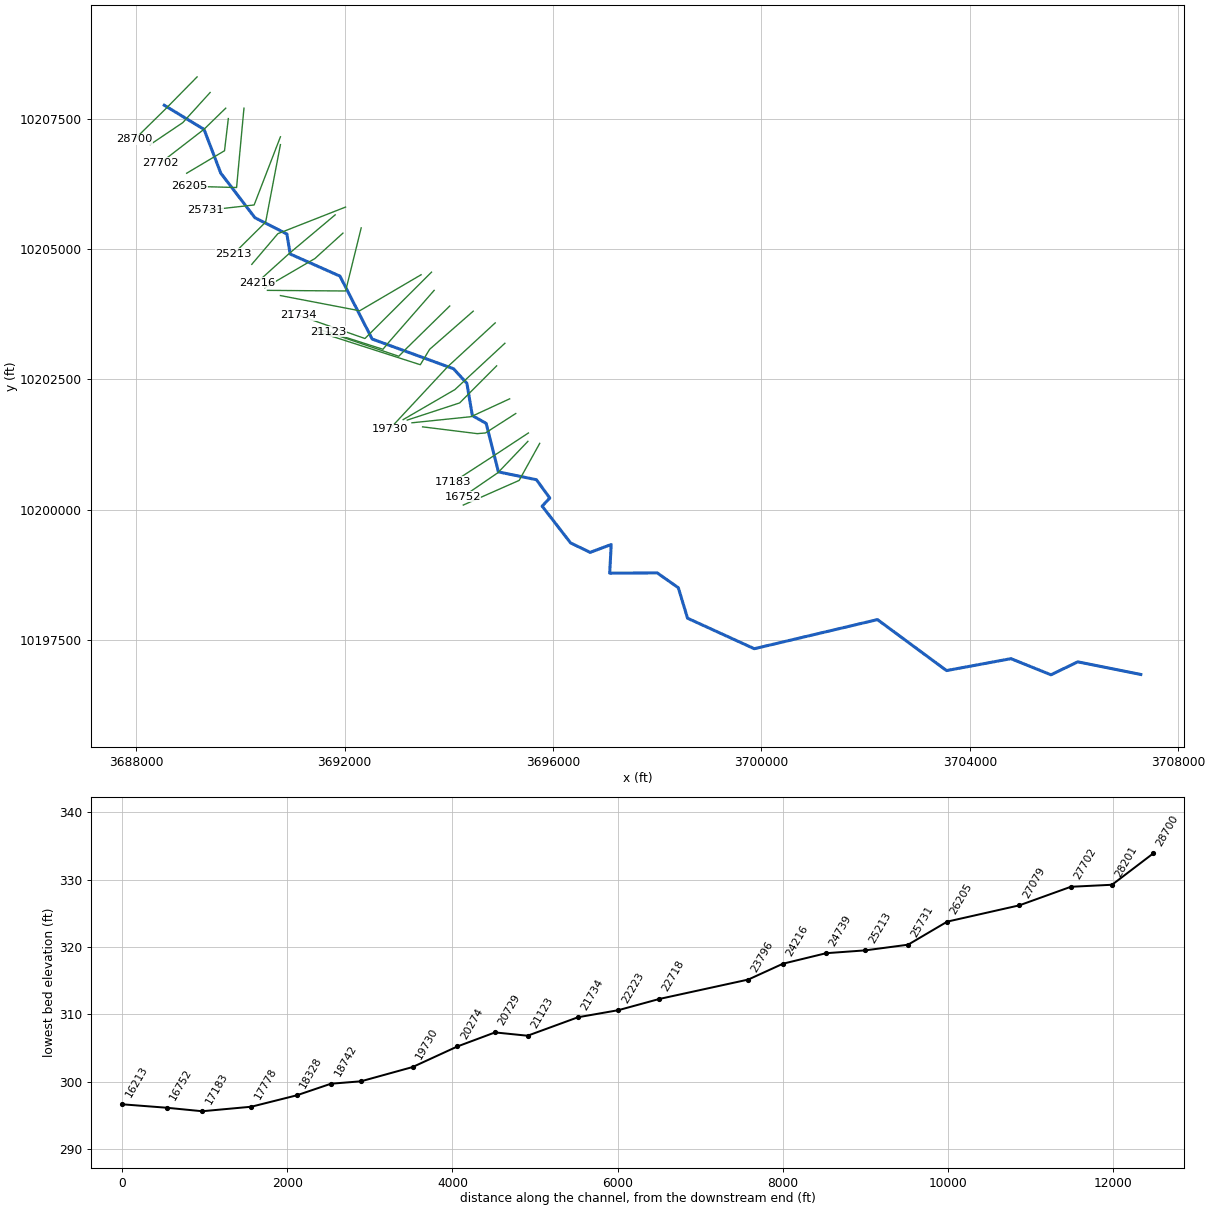
--- FLAGTAIL CREEK.prj (project) ---

Proj Title=FLAGTAIL CREEK Base Level Engineering
Current Plan=p01
Default Exp/Contr=0.3,0.1
English Units
Geom File=g01
Flow File=f01
Flow File=f02
Plan File=p01
Y Axis Title=Elevation
X Axis Title(PF)=Main Channel Distance
X Axis Title(XS)=Station
BEGIN DESCRIPTION:
FLAGTAIL CREEK
END DESCRIPTION:
DSS Export Rating Curves= 0
DSS Export Rating Curve Sorted= 0
DSS Export Volume Flow Curves= 0
DXF OffsetX= 0
DXF OffsetY= 0
DXF ScaleX= 1
DXF ScaleY= 10

--- FLAGTAIL CREEK.p01 (plan) ---

Plan Title=Multiple Run
Short Identifier=Multiple
Geom File=g01
Flow File=f01
Subcritical Flow
K Sum by GR= 0
Std Step Tol= 0.01
Critical Tol= 0.01
Num of Std Step Trials= 20
Max Error Tol= 0.3
Flow Tol Ratio= 0.001
Split Flow NTrial= 30
Split Flow Tol= 0.02
Split Flow Ratio= 0.02
Log Output Level= 0
Friction Slope Method= 1
Unsteady Friction Slope Method= 2
Unsteady Bridges Friction Slope Method= 1
Parabolic Critical Depth
Global Vel Dist=  1 , 1 , 1
Global Log Level= 0
CheckData=True
Encroach Param= -1, 0, 0, 0
BEGIN DESCRIPTION:
Multiple Run
END DESCRIPTION:

--- FLAGTAIL CREEK.f01 (steady flow) ---

Flow Title=Multiple
Program Version=4.10
Number of Profiles= 7
Profile Names=10-year,25-year,50-year,1pct_min,100-year,1pct_plu,500-year
River Rch & RM=FLAGTAIL CREEK,Reach-1         ,28700
     779    1081    1485     671    2027    6121    3904
River Rch & RM=FLAGTAIL CREEK,Reach-1         ,25731
     969    1348    1856     839    2534    7653    4887
River Rch & RM=FLAGTAIL CREEK,Reach-1         ,22223
    1226    1731    2404    1095    3307    9987    6490
River Rch & RM=FLAGTAIL CREEK,Reach-1         ,19730
    1896    2682    3725    1693    5113   15441    9985
River Rch & RM=FLAGTAIL CREEK,Reach-1         ,17183
    1782    2489    3428    1544    4662   14079    8937
River Rch & RM=FLAGTAIL CREEK,Reach-1         ,14754
    2071    2924    4057    1841    5559   16788   10815
River Rch & RM=FLAGTAIL CREEK,Reach-1         ,12285
    2364    3367    4700    2145    6477   19560   12749
River Rch & RM=FLAGTAIL CREEK,Reach-1         ,10289
    2076    2905    4004    1804    5448   16453   10447
River Rch & RM=FLAGTAIL CREEK,Reach-1         ,6743
    2227    3124    4316    1948    5883   17766   11321
River Rch & RM=FLAGTAIL CREEK,Reach-1         ,5545
    2630    3725    5182    2354    7110   21472   13868
Boundary for River Rch & Prof#=FLAGTAIL CREEK,Reach-1         , 1
Up Type= 0
Dn Type= 3
Dn Slope=0.002
Boundary for River Rch & Prof#=FLAGTAIL CREEK,Reach-1         , 2
Up Type= 0
Dn Type= 3
Dn Slope=0.002
Boundary for River Rch & Prof#=FLAGTAIL CREEK,Reach-1         , 3
Up Type= 0
Dn Type= 3
Dn Slope=0.002
Boundary for River Rch & Prof#=FLAGTAIL CREEK,Reach-1         , 4
Up Type= 0
Dn Type= 3
Dn Slope=0.002
Boundary for River Rch & Prof#=FLAGTAIL CREEK,Reach-1         , 5
Up Type= 0
Dn Type= 3
Dn Slope=0.002
Boundary for River Rch & Prof#=FLAGTAIL CREEK,Reach-1         , 6
Up Type= 0
Dn Type= 3
Dn Slope=0.002
Boundary for River Rch & Prof#=FLAGTAIL CREEK,Reach-1         , 7
Up Type= 0
Dn Type= 3
Dn Slope=0.002
DSS Import GetInterval= 0
DSS Import GetPeak= 0
DSS Import FillOption= 0

--- FLAGTAIL CREEK.f02 (steady flow) ---

Flow Title=Orig_BLE_Flows
Program Version=4.10
Number of Profiles= 7
Profile Names=10-year,25-year,50-year,1pct_min,100-year,1pct_plu,500-year
River Rch & RM=FLAGTAIL CREEK,Reach-1         ,28700
     779    1060    1291     516    1559    4708    2270
River Rch & RM=FLAGTAIL CREEK,Reach-1         ,25731
     969    1322    1614     645    1949    5885    2841
River Rch & RM=FLAGTAIL CREEK,Reach-1         ,22223
    1226    1697    2090     843    2544    7684    3773
River Rch & RM=FLAGTAIL CREEK,Reach-1         ,19730
    1896    2629    3239    1302    3933   11879    5805
River Rch & RM=FLAGTAIL CREEK,Reach-1         ,17183
    1782    2440    2981    1188    3586   10831    5196
River Rch & RM=FLAGTAIL CREEK,Reach-1         ,14754
    2071    2867    3528    1416    4276   12914    6288
River Rch & RM=FLAGTAIL CREEK,Reach-1         ,12285
    2364    3301    4087    1650    4982   15047    7412
River Rch & RM=FLAGTAIL CREEK,Reach-1         ,10289
    2076    2848    3482    1388    4191   12656    6074
River Rch & RM=FLAGTAIL CREEK,Reach-1         ,6743
    2227    3063    3753    1498    4525   13665    6582
River Rch & RM=FLAGTAIL CREEK,Reach-1         ,5545
    2630    3652    4506    1811    5469   16517    8063
Boundary for River Rch & Prof#=FLAGTAIL CREEK,Reach-1         , 1
Up Type= 0
Dn Type= 3
Dn Slope=0.002
Boundary for River Rch & Prof#=FLAGTAIL CREEK,Reach-1         , 2
Up Type= 0
Dn Type= 3
Dn Slope=0.002
Boundary for River Rch & Prof#=FLAGTAIL CREEK,Reach-1         , 3
Up Type= 0
Dn Type= 3
Dn Slope=0.002
Boundary for River Rch & Prof#=FLAGTAIL CREEK,Reach-1         , 4
Up Type= 0
Dn Type= 3
Dn Slope=0.002
Boundary for River Rch & Prof#=FLAGTAIL CREEK,Reach-1         , 5
Up Type= 0
Dn Type= 3
Dn Slope=0.002
Boundary for River Rch & Prof#=FLAGTAIL CREEK,Reach-1         , 6
Up Type= 0
Dn Type= 3
Dn Slope=0.002
Boundary for River Rch & Prof#=FLAGTAIL CREEK,Reach-1         , 7
Up Type= 0
Dn Type= 3
Dn Slope=0.002
DSS Import GetInterval= 0
DSS Import GetPeak= 0
DSS Import FillOption= 0

--- FLAGTAIL CREEK.g01 (geometry) ---

Geom Title=Existing Conditions
Program Version=4.10

River Reach=FLAGTAIL CREEK  ,Reach-1
Reach XY= 30
      3688538.23     10207766.84      3689301.67     10207302.98
      3689622.17     10206463.68      3690277.05     10205607.57
      3690891.34      10205294.1        3690955.     10204909.39
      3691910.73     10204484.37       3692528.3     10203276.38
      3694090.17     10202705.31      3694346.65     10202425.24
      3694451.44     10201805.27       3694716.3     10201655.98
      3694952.22     10200723.83      3695681.71     10200573.76
      3695937.67     10200221.67      3695790.74     10200066.19
      3696337.41     10199359.43      3696712.46     10199178.33
      3697116.35     10199328.92      3697087.82     10198778.11
      3697999.02     10198784.09      3698404.72     10198499.22
        3698582.     10197913.33      3699863.37     10197327.46
      3702227.11     10197886.94      3703552.56     10196907.86
      3704789.16     10197136.54      3705557.19     10196826.81
      3706072.85     10197075.59      3707281.52     10196832.75

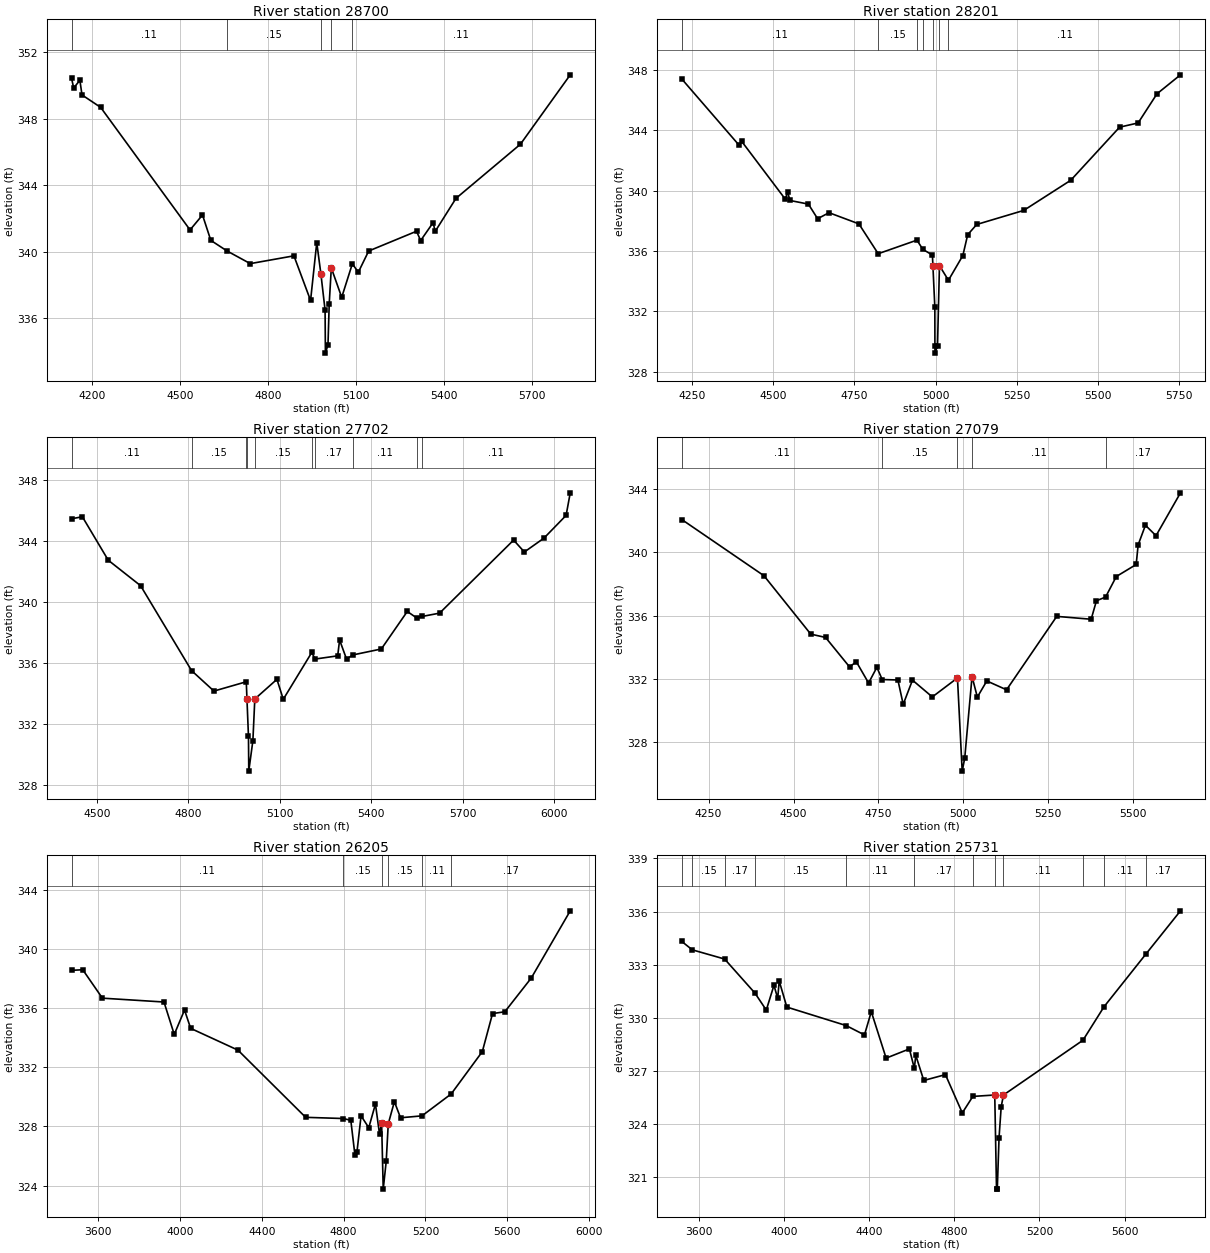
Type RM Length L Ch R = 1 ,28700   ,499,499,499
BEGIN DESCRIPTION:
FLAGTAIL CREEK 52.0
END DESCRIPTION:
XS GIS Cut Line= 3
      3689167.85     10208311.07      3688558.96     10207692.04
      3687967.86     10207111.08
#Sta/Elev= 30
  4131.7  350.42  4138.8  349.85  4159.9  350.31  4167.1  349.43  4230.6  348.68
  4534.8   341.3  4577.2   342.2  4605.5  340.67    4661  340.03  4739.8  339.27
  4888.4  339.74    4945  337.05  4966.1  340.54  4980.3  338.63  4994.4  336.47
  4995.5  333.88  5004.3  334.38  5008.5  336.86  5015.6  339.01    5051  337.24
  5087.2  339.26  5107.5  338.75  5142.8  340.03  5305.6  341.22  5319.7  340.66
  5362.1  341.74  5369.1  341.21  5439.9   343.2  5659.2  346.46  5828.8  350.64
#Mann= 5 ,-1 , 0
  4131.7     .11       0    4661     .15       0  4980.3     .09       0
  5015.6     .15       0  5087.2     .11       0
Bank Sta=4980.3,5015.6
XS Rating Curve= 0 ,0
Exp/Cntr=0.3,0.1

Type RM Length L Ch R = 1 ,28201   ,499,499,499
BEGIN DESCRIPTION:
FLAGTAIL CREEK 51.0
END DESCRIPTION:
XS GIS Cut Line= 3
      3689417.88      10208011.1      3688892.77     10207432.71
      3688267.82     10207011.05
#Sta/Elev= 30
  4218.8   347.4  4395.6     343    4403  343.27  4537.5  339.43  4544.2  339.92
  4551.7  339.35  4608.4  339.11  4636.8  338.14  4671.9  338.54  4763.8   337.8
  4823.3  335.82  4942.5  336.72  4960.8  336.11  4990.2  335.73 4991.72335.0268
  4997.7  332.26  4997.9  329.73  4998.2  329.23  5005.9  329.73  5011.9  335.03
  5039.5  334.06  5083.9   335.7  5098.8  337.08  5126.6  337.76  5271.3  338.69
  5416.1  340.69  5566.5  344.21  5623.5  344.49  5681.5  346.42  5753.9  347.68
#Mann= 7 ,-1 , 0
  4218.8     .11       0  4823.3     .15       0  4942.5     .11       0
  4960.8     .15       0 4991.72     .09       0  5011.9     .15       0
  5039.5     .11       0
Bank Sta=4991.72,5011.9
XS Rating Curve= 0 ,0
Exp/Cntr=0.3,0.1

Type RM Length L Ch R = 1 ,27702   ,623,623,623
BEGIN DESCRIPTION:
FLAGTAIL CREEK 50.0
END DESCRIPTION:
XS GIS Cut Line= 3
      3689717.82     10207711.05      3689300.23     10207304.65
      3688467.82     10206661.05
#Sta/Elev= 30
  4417.3  345.48  4452.6  345.61  4537.5  342.76  4643.5  341.09  4810.7  335.52
    4884  334.18    4990  334.79  4992.3333.6465  4997.2  331.21  4998.2  328.93
  5011.7  330.93    5018  333.66  5090.5  334.95  5111.3  333.64  5204.7  336.71
  5215.7  336.28  5289.7  336.49    5296  337.53  5318.7  336.28  5339.5  336.55
  5432.8  336.94  5517.9   339.4  5549.9  338.96  5565.7  339.07  5623.8  339.29
  5866.5  344.08  5901.8   343.3  5966.1  344.21  6038.6   345.7  6052.2  347.18
#Mann= 10 ,-1 , 0
  4417.3     .11       0  4810.7     .15       0    4990     .12       0
  4992.3     .09       0    5018     .15       0  5204.7     .11       0
  5215.7     .17       0  5339.5     .11       0  5549.9     .17       0
  5565.7     .11       0
Bank Sta=4992.3,5018
XS Rating Curve= 0 ,0
Exp/Cntr=0.3,0.1

Type RM Length L Ch R = 1 ,27079   ,874,874,874
BEGIN DESCRIPTION:
FLAGTAIL CREEK 49.0
END DESCRIPTION:
XS GIS Cut Line= 3
      3689767.85      10207511.1      3689694.34     10206893.02
      3688967.89     10206461.09
#Sta/Elev= 30
  4171.3  342.08    4413  338.53  4550.7  334.84  4594.3  334.63  4664.8  332.77
  4684.9  333.09  4720.9  331.75  4745.3  332.74    4761  331.97  4807.2  331.94
  4822.8   330.4  4850.1  331.93  4908.5  330.87  4982.5  332.07  4996.4  326.18
  5003.9     327  5025.4  332.16    5041  330.86  5068.9  331.88    5127  331.32
  5274.7  335.96    5376  335.78  5391.6  336.95  5418.4  337.18    5450  338.48
  5508.5  339.24  5514.3  340.48  5535.7  341.72  5566.9  341.06  5638.9  343.77
#Mann= 5 ,-1 , 0
  4171.3     .11       0    4761     .15       0  4982.5     .09       0
  5025.4     .11       0  5418.4     .17       0
Bank Sta=4982.5,5025.4
XS Rating Curve= 0 ,0
Exp/Cntr=0.3,0.1

Type RM Length L Ch R = 1 ,26205   ,474,474,474
BEGIN DESCRIPTION:
FLAGTAIL CREEK 48.0
END DESCRIPTION:
XS GIS Cut Line= 3
      3690067.86     10207711.11      3689925.94      10206186.7
      3689017.86     10206211.07
#Sta/Elev= 30
    3469  338.54  3523.6  338.58  3619.7  336.66    3921   336.4  3971.2  334.21
  4021.4  335.86  4051.5  334.62  4282.8  333.15    4614  328.61  4797.6  328.53
  4834.9  328.41    4855  326.07  4865.1  326.28  4885.1  328.71  4922.8  327.91
  4955.4  329.51  4975.5  327.47  4985.6  328.23  4993.5  323.76  5008.1  325.63
  5018.1  328.17  5048.1  329.67  5078.1  328.58  5183.1  328.71    5326  330.19
  5478.3  333.05  5528.3  335.62  5588.3  335.74  5717.7  338.02  5908.4  342.56
#Mann= 6 ,-1 , 0
    3469     .11       0  4797.6     .15       0  4985.6     .09       0
  5018.1     .15       0  5183.1     .11       0    5326     .17       0
Bank Sta=4985.6,5018.1
XS Rating Curve= 0 ,0
Exp/Cntr=0.3,0.1

Type RM Length L Ch R = 1 ,25731   ,518,518,518
BEGIN DESCRIPTION:
FLAGTAIL CREEK 47.0
END DESCRIPTION:
XS GIS Cut Line= 3
      3690767.85     10207161.06      3690262.92     10205851.35
      3689331.28     10205747.35
#Sta/Elev= 30
  3521.1  334.31  3570.1  333.84    3722  333.32  3864.3   331.4  3917.6  330.44
  3953.6  331.84  3971.2   331.1  3978.2  332.08  4014.1  330.61    4292  329.57
  4378.5  329.04  4410.6  330.35  4480.2  327.73  4589.4  328.25  4612.7  327.15
  4619.4  327.89  4657.1  326.47  4758.6   326.8  4837.8  324.64  4887.4  325.57
  4990.2  325.65  4998.5  320.34  5002.1  320.34  5010.4  323.25  5020.4  324.98
  5031.1  325.65  5404.4  328.74  5503.3  330.63  5701.1  333.62  5862.2  336.04
#Mann= 12 ,-1 , 0
  3521.1     .11       0  3570.1     .15       0    3722     .17       0
  3864.3     .15       0    4292     .11       0  4612.7     .17       0
  4887.4     .15       0  4990.2     .09       0  5031.1     .11       0
  5404.4     .17       0  5503.3     .11       0  5701.1     .17       0
Bank Sta=4990.2,5031.1
XS Rating Curve= 0 ,0
Exp/Cntr=0.3,0.1

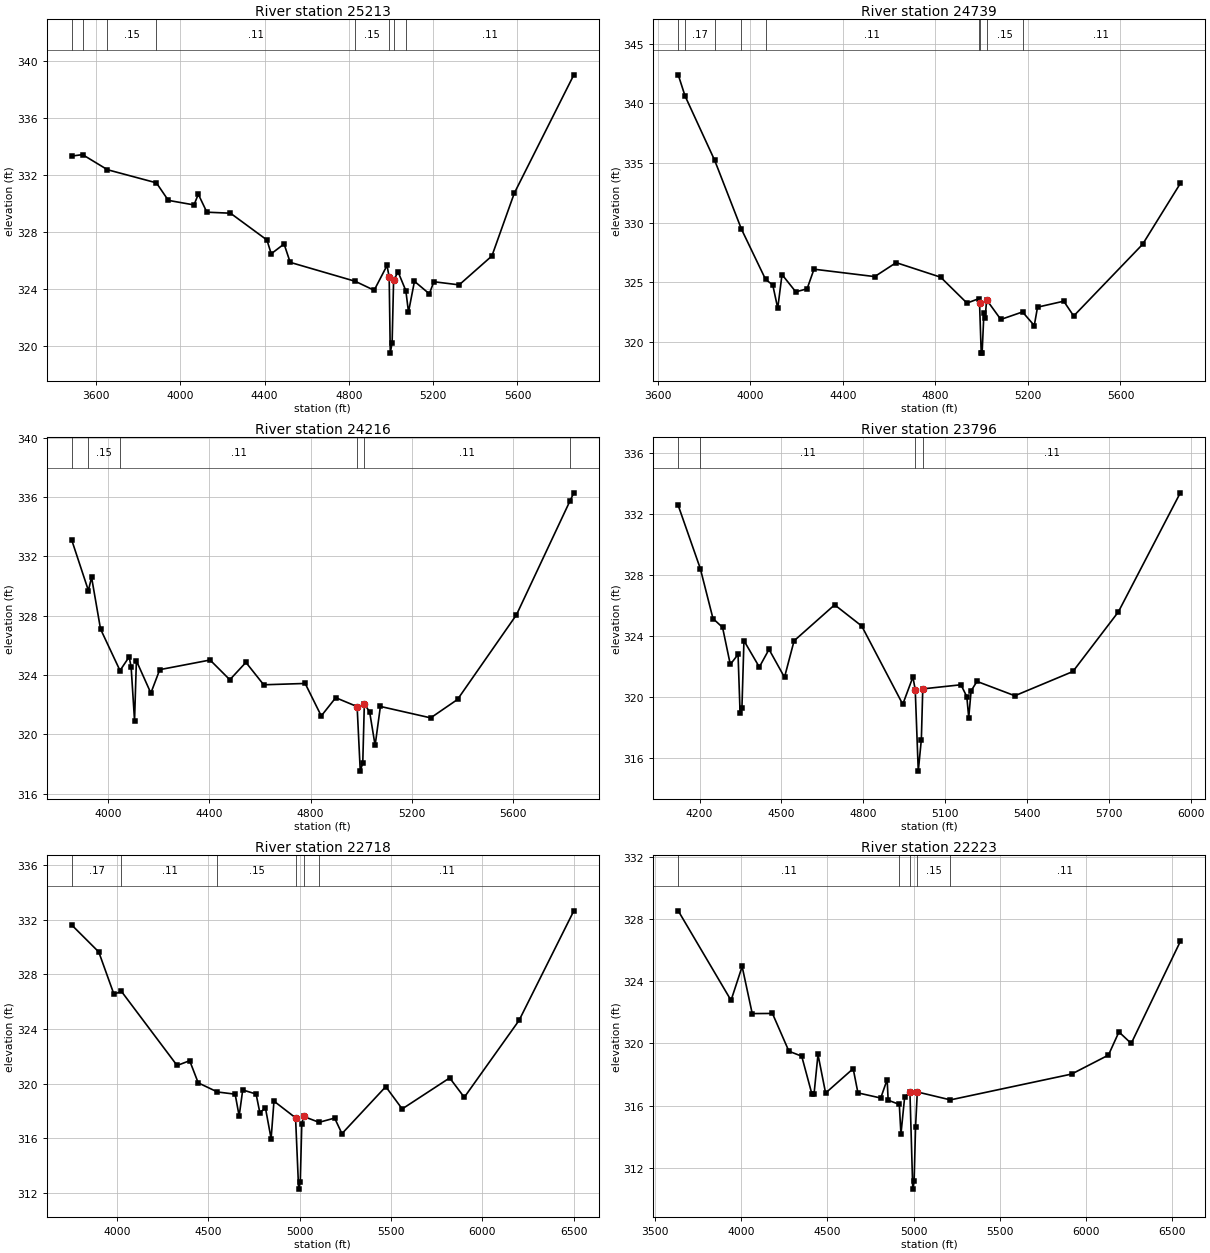
Type RM Length L Ch R = 1 ,25213   ,474,474,474
BEGIN DESCRIPTION:
FLAGTAIL CREEK 46.0
END DESCRIPTION:
XS GIS Cut Line= 3
      3690767.84     10207011.03      3690483.75     10205522.19
      3689867.88      10204911.1
#Sta/Elev= 30
  3484.3  333.33  3535.6  333.43  3653.9  332.37    3886  331.45  3942.6  330.22
  4064.5   329.9  4084.9  330.65  4125.6  329.39  4237.6  329.32  4410.7  327.44
    4431  326.47  4492.1  327.16  4521.1  325.87    4830  324.54  4919.7  323.91
  4980.8  325.65    4991  324.83  4996.2   319.5    5005  320.24    5012  324.61
  5033.3   325.2  5070.1  323.88  5082.7  322.38    5111  324.54  5181.7  323.66
    5203  324.51  5323.2  324.29  5478.7  326.32  5584.8  330.72  5867.6  339.03
#Mann= 8 ,-1 , 0
  3484.3     .15       0  3535.6     .17       0  3653.9     .15       0
    3886     .11       0    4830     .15       0    4991     .09       0
    5012     .15       0  5070.1     .11       0
Bank Sta=4991,5012
XS Rating Curve= 0 ,0
Exp/Cntr=0.3,0.1

Type RM Length L Ch R = 1 ,24739   ,523,523,523
BEGIN DESCRIPTION:
FLAGTAIL CREEK 45.0
END DESCRIPTION:
XS GIS Cut Line= 3
      3692017.89     10205811.09      3690718.65     10205300.13
      3690217.84     10204711.05
#Sta/Elev= 30
  3689.3  342.39  3718.5  340.63  3846.9  335.22  3962.3  329.47  4066.8  325.25
  4097.7  324.79  4119.2  322.84  4137.7  325.66  4197.3  324.21  4246.1  324.47
  4275.9  326.11  4538.2  325.49  4630.8  326.66  4823.1  325.44  4936.9  323.27
  4987.5  323.64  4991.1  323.31  4998.4  319.08  5002.2  319.08  5010.1  322.44
  5015.5  322.06  5021.8  323.54  5083.1   321.9  5176.8  322.53  5227.6  321.39
  5241.7  322.93    5355  323.43  5397.9  322.19  5695.5  328.19  5858.6  333.29
#Mann= 9 ,-1 , 0
  3689.3    .125       0  3718.5     .17       0  3846.9     .11       0
  3962.3     .15       0  4066.8     .11       0  4987.5     .15       0
  4991.1     .09       0  5021.8     .15       0  5176.8     .11       0
Bank Sta=4991.1,5021.8
XS Rating Curve= 0 ,0
Exp/Cntr=0.3,0.1

Type RM Length L Ch R = 1 ,24216   ,420,420,420
BEGIN DESCRIPTION:
FLAGTAIL CREEK 44.0
END DESCRIPTION:
XS GIS Cut Line= 3
      3691817.81     10205661.04      3690941.86     10204924.43
      3690317.85     10204361.07
#Sta/Elev= 30
  3855.5  333.09  3921.3  329.69  3933.8  330.59  3969.2   327.1  4046.2   324.3
  4082.4  325.22  4090.2  324.54  4103.7  320.92    4111  324.96  4168.2  322.78
  4203.4  324.36  4402.4  325.01  4480.4  323.68  4544.1  324.85  4614.4  323.34
  4778.3  323.43    4842  321.24  4899.2  322.47  4983.8  321.87  4996.2  317.52
  5006.1  318.08  5012.3  322.04  5033.2  321.52  5054.9  319.25  5075.8  321.88
  5274.6  321.11  5380.7  322.35  5613.9  328.06  5824.5   335.7  5840.7  336.28
#Mann= 6 ,-1 , 0
  3855.5     .11       0  3921.3     .15       0  4046.2     .11       0
  4983.8     .06       0  5012.3     .11       0  5824.5     .17       0
Bank Sta=4983.8,5012.3
XS Rating Curve= 0 ,0
Exp/Cntr=0.3,0.1

Type RM Length L Ch R = 1 ,23796   ,1078,1078,1078
BEGIN DESCRIPTION:
FLAGTAIL CREEK 43.0
END DESCRIPTION:
XS GIS Cut Line= 3
      3691967.88     10205311.09      3691430.46      10204822.7
      3690467.81     10204261.05
#Sta/Elev= 30
  4121.8  332.58  4202.8  328.44  4249.2  325.17  4284.3  324.59  4312.7  322.16
  4341.1  322.82  4348.5     319  4355.3  319.29  4362.7  323.72  4419.1  321.99
  4454.6  323.15  4511.4  321.32  4546.5  323.71  4695.2  326.07  4794.5  324.68
    4945  319.55  4982.2  321.34 4990.69320.4987  5001.8  315.17  5013.1  317.24
 5018.29  320.56  5158.3  320.83  5179.8  320.05  5186.8  318.67  5195.5  320.43
    5217  321.05  5355.9  320.11  5568.8   321.7  5735.5  325.61  5962.5  333.41
#Mann= 4 ,-1 , 0
  4121.8     .17       0  4202.8     .11       0 4990.69    .065       0
 5018.29     .11       0
Bank Sta=4990.69,5018.29
XS Rating Curve= 0 ,0
Exp/Cntr=0.3,0.1

Type RM Length L Ch R = 1 ,22718   ,495,495,495
BEGIN DESCRIPTION:
FLAGTAIL CREEK 42.0
END DESCRIPTION:
XS GIS Cut Line= 3
      3692317.86      10205411.1      3692019.14     10204199.07
      3690517.89     10204211.07
#Sta/Elev= 30
  3751.7  331.62  3899.5  329.65  3982.5  326.56  4023.9  326.76  4328.5  321.34
  4397.4  321.69  4444.1  320.07  4549.4   319.4  4646.4  319.24  4668.4  317.64
  4687.9  319.55  4761.1  319.25  4781.6  317.89  4812.4  318.23  4843.4  315.98
    4859  318.73  4977.3  317.51  4994.1  312.29  5003.1  312.79  5011.3  317.05
  5021.3  317.61    5106  317.18  5191.3  317.49  5231.3  316.35  5471.3  319.79
  5561.3  318.16  5821.3  320.43  5901.3  319.01  6201.3  324.64  6501.3  332.66
#Mann= 6 ,-1 , 0
  3751.7     .17       0  4023.9     .11       0  4549.4     .15       0
  4977.3     .09       0  5021.3     .15       0    5106     .11       0
Bank Sta=4977.3,5021.3
XS Rating Curve= 0 ,0
Exp/Cntr=0.3,0.1

Type RM Length L Ch R = 1 ,22223   ,489,489,489
BEGIN DESCRIPTION:
FLAGTAIL CREEK 41.0
END DESCRIPTION:
XS GIS Cut Line= 3
      3693467.83     10204511.06      3692289.16     10203819.23
      3690767.81     10204111.08
#Sta/Elev= 30
  3633.3  328.53    3940  322.77  4004.4  324.95    4063  321.92  4180.3  321.93
  4276.1   319.5  4350.4  319.18    4409  316.77  4421.8  316.73  4444.9  319.29
  4489.1  316.81  4649.3  318.38  4676.9  316.82  4809.4  316.49  4846.6  317.68
  4852.4  316.35  4917.1  316.08  4926.7  314.17  4948.2  316.55 4978.91 316.847
  4995.3  310.63  5003.2  311.13  5011.5  314.62  5021.7  316.88    5214  316.37
  5917.7  318.03  6131.6  319.25  6192.7  320.74  6263.9     320  6549.1  326.56
#Mann= 5 ,-1 , 0
  3633.3     .11       0  4917.1     .15       0 4978.91     .09       0
  5021.7     .15       0    5214     .11       0
Bank Sta=4978.91,5021.7
XS Rating Curve= 0 ,0
Exp/Cntr=0.3,0.1

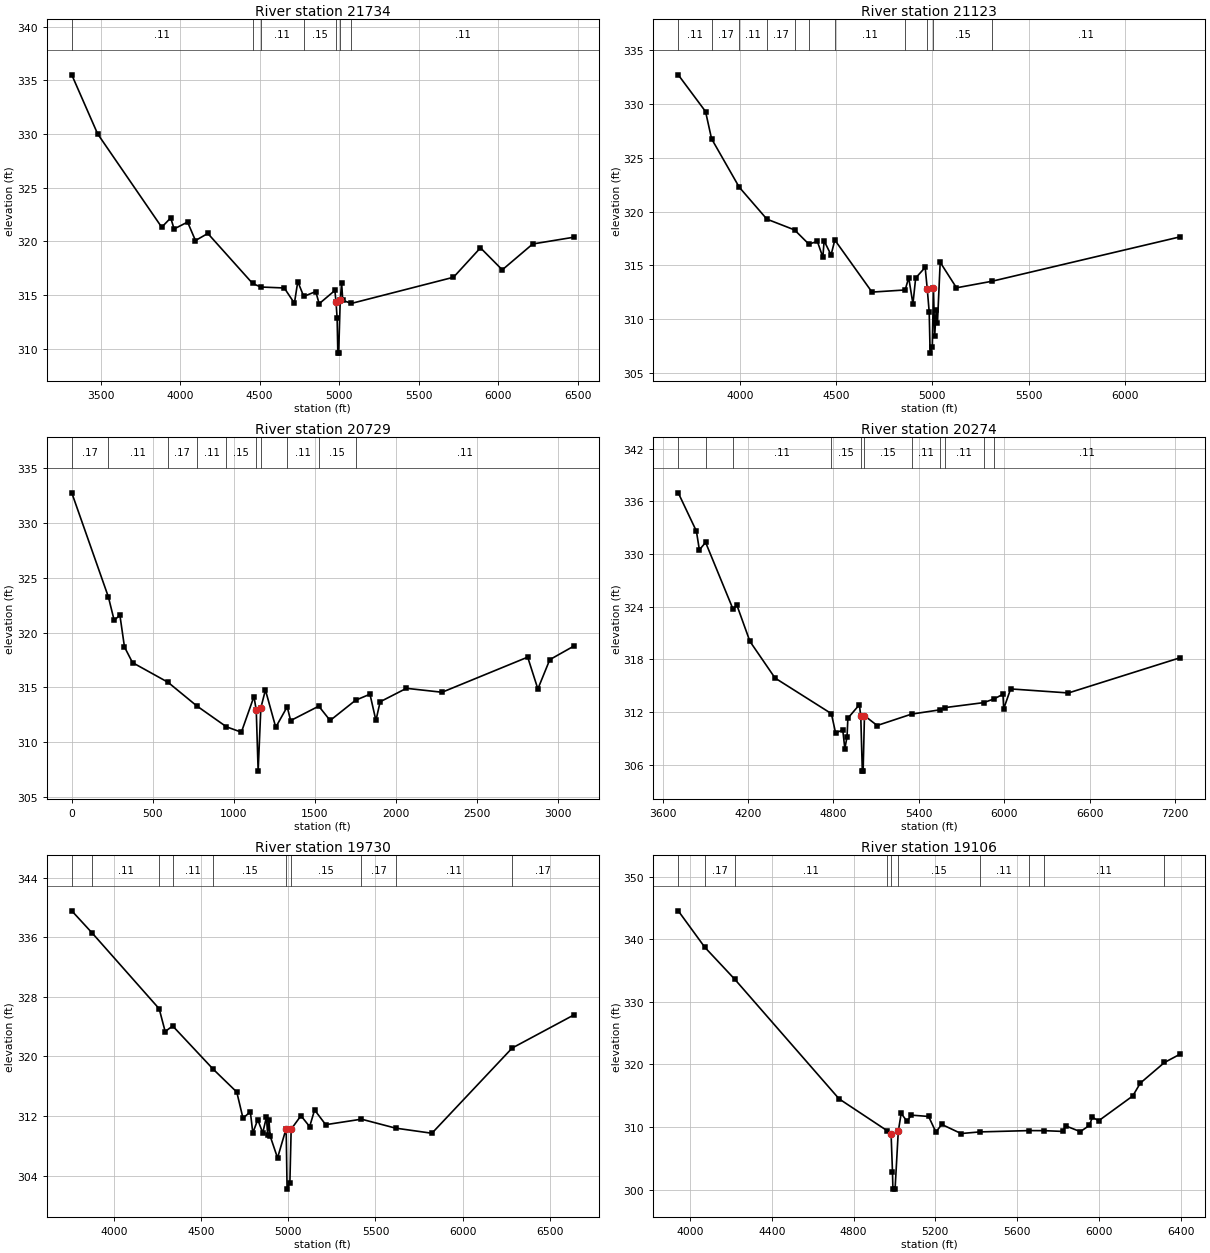
Type RM Length L Ch R = 1 ,21734   ,611,611,611
BEGIN DESCRIPTION:
FLAGTAIL CREEK 40.0
END DESCRIPTION:
XS GIS Cut Line= 3
      3693667.83     10204561.05      3692389.66     10203286.24
      3691113.63     10203733.29
#Sta/Elev= 30
  3318.8  335.51  3481.4  330.01  3884.4  321.31    3941  322.18  3962.2  321.15
  4047.1  321.79  4096.6  320.07  4174.4  320.73  4456.1  316.07  4507.3  315.74
  4655.2  315.65  4718.8  314.23  4740.1  316.25  4777.5  314.86  4853.2  315.32
  4874.4  314.18  4973.4  315.42  4980.5  314.35  4987.5  312.83    4992  309.58
  4997.2  309.58 5007.02314.5199  5015.8  316.11  5022.9   314.5  5076.8  314.21
  5719.3  316.65  5888.9  319.39  6026.1  317.34  6217.5  319.75  6476.1  320.38
#Mann= 7 ,-1 , 0
  3318.8     .11       0  4456.1     .17       0  4507.3     .11       0
  4777.5     .15       0  4980.5     .09       0 5007.02     .15       0
  5076.8     .11       0
Bank Sta=4980.5,5007.02
XS Rating Curve= 0 ,0
Exp/Cntr=0.3,0.1

Type RM Length L Ch R = 1 ,21123   ,394,394,394
BEGIN DESCRIPTION:
FLAGTAIL CREEK 39.0
END DESCRIPTION:
XS GIS Cut Line= 4
      3693717.83     10204211.05      3692849.73      10203216.8
      3692736.04     10203079.36      3691678.73     10203417.73
#Sta/Elev= 30
  3679.8   332.7  3821.7  329.29  3852.9  326.76  3996.6  322.26  4140.3  319.29
    4284  318.29  4358.2  316.97  4402.6  317.22  4431.1  315.75  4437.7  317.27
  4473.8  315.96  4493.3  317.35  4686.5  312.51  4858.8  312.71  4877.2  313.86
  4899.1  311.41  4913.3  313.82  4962.7  314.81 4973.46312.8095  4983.6  310.66
  4988.4  306.84  4999.7  307.38  5005.6  312.92  5012.1  308.42  5019.9  310.87
  5026.4  309.61  5040.7  315.28  5125.4  312.91  5310.1  313.52  6288.2  317.65
#Mann= 11 ,-1 , 0
  3679.8     .11       0  3852.9     .17       0  3996.6     .11       0
  4140.3     .17       0    4284     .11       0  4358.2     .17       0
  4493.3     .11       0  4858.8     .15       0 4973.46     .09       0
  5005.6     .15       0  5310.1     .11       0
Bank Sta=4973.46,5005.6
XS Rating Curve= 0 ,0
Exp/Cntr=0.3,0.1

Type RM Length L Ch R = 1 ,20729   ,455,455,455
BEGIN DESCRIPTION:
FLAGTAIL CREEK 38.0
END DESCRIPTION:
XS GIS Cut Line= 4
      3694017.85     10203911.07      3693196.49     10203104.87
      3693038.84     10202945.19      3691407.32     10203499.02
#Sta/Elev= 30
       0  332.77   226.2  323.24   261.7  321.11     297  321.59   325.2  318.68
   374.8  317.25     594  315.45   770.7   313.3   954.6  311.38  1046.6  310.89
  1124.3  314.15  1138.5  312.89  1150.1  307.33  1166.8  313.11  1195.1  314.75
  1258.7  311.34  1329.4  313.21  1350.7  311.95  1524.2  313.27  1594.3  311.96
  1751.3  313.81  1840.2  314.36  1876.9  311.96    1903  313.67  2065.2   314.9
    2285  314.54  2813.5  317.75  2876.3  314.84  2949.8  317.52  3098.3  318.76
#Mann= 10 ,-1 , 0
       0     .17       0   226.2     .11       0     594     .17       0
   770.7     .11       0   954.6     .15       0  1138.5     .09       0
  1166.8     .15       0  1329.4     .11       0  1524.2     .15       0
  1751.3     .11       0
Bank Sta=1138.5,1166.8
XS Rating Curve= 0 ,0
Exp/Cntr=0.3,0.1

Type RM Length L Ch R = 1 ,20274   ,544,544,544
BEGIN DESCRIPTION:
FLAGTAIL CREEK 37.0
END DESCRIPTION:
XS GIS Cut Line= 4
      3694467.83     10203811.05      3693630.98     10203077.91
      3693453.03     10202782.77      3691483.28     10203416.22
#Sta/Elev= 30
  3709.6  336.97  3837.2   332.6  3858.1  330.47  3901.8  331.32  4095.2  323.68
    4121  324.19    4213  320.04  4389.6  315.86  4785.3   311.8  4814.7  309.61
  4865.2  309.93  4879.7  307.81  4895.2  309.16    4901  311.28    4982  312.82
 4991.63311.4792  5002.5  305.25  5008.2  305.25  5017.5  311.57  5106.8  310.45
  5348.5  311.75  5545.4  312.23  5582.7  312.49  5855.8  313.06  5928.7  313.49
  5990.3  314.01  5995.5  312.35  6044.1  314.62    6450  314.16  7235.9  318.18
#Mann= 11 ,-1 , 0
  3709.6     .11       0  3901.8     .17       0  4095.2     .11       0
  4785.3     .15       0 4991.63     .09       0  5017.5     .15       0
  5348.5     .11       0  5545.4     .15       0  5582.7     .11       0
  5855.8     .15       0  5928.7     .11       0
Bank Sta=4991.63,5017.5
XS Rating Curve= 0 ,0
Exp/Cntr=0.3,0.1

Type RM Length L Ch R = 1 ,19730   ,624,624,624
BEGIN DESCRIPTION:
FLAGTAIL CREEK 36.0
END DESCRIPTION:
XS GIS Cut Line= 3
      3694889.68     10203585.74       3693978.1      10202744.4
      3692862.93     10201545.99
#Sta/Elev= 30
  3759.5  339.55    3878  336.53  4260.5   326.4  4294.7  323.35    4338  324.09
  4569.2  318.31  4705.2  315.22  4740.9   311.7  4782.9  312.58  4797.1  309.73
  4825.4  311.52  4853.8  309.74  4875.3  311.85  4882.1  309.52  4889.5  311.44
  4896.3  309.33  4938.8  306.38  4988.2  310.32  4993.5  302.19  5009.5  303.04
  5016.9  310.24    5073  312.04  5122.9  310.58  5151.2  312.82  5214.7  310.84
  5419.8  311.58    5615  310.38  5823.5  309.69  6283.5  321.13    6637  325.57
#Mann= 10 ,-1 , 0
  3759.5     .17       0    3878     .11       0  4260.5     .17       0
    4338     .11       0  4569.2     .15       0  4988.2     .09       0
  5016.9     .15       0  5419.8     .17       0    5615     .11       0
  6283.5     .17       0
Bank Sta=4988.2,5016.9
XS Rating Curve= 0 ,0
Exp/Cntr=0.3,0.1

Type RM Length L Ch R = 1 ,19106   ,364,364,364
BEGIN DESCRIPTION:
Mapping XS 0796a570
END DESCRIPTION:
XS GIS Cut Line= 3
      3695076.28     10203195.09      3694117.09     10202305.34
      3693123.17     10201728.09
#Sta/Elev= 30
  3941.3  344.54  4071.5  338.71  4217.9  333.61  4728.7   314.5  4964.5   309.4
  4983.2  308.92  4990.1  302.81  4992.1  300.08  5002.7  300.08  5018.4   309.3
  5032.6  312.18  5060.9  310.92  5082.4   311.9  5166.9  311.69  5202.6  309.19
    5231  310.42  5325.9  308.96  5417.1  309.22  5658.5  309.43    5732  309.42
  5823.4   309.3  5838.5  310.18  5909.5  309.26  5954.2  310.27  5968.2  311.55
  5999.7  311.01  6166.1  314.96  6203.3  317.02  6321.4  320.31    6399  321.66
#Mann= 10 ,-1 , 0
  3941.3     .11       0  4071.5     .17       0  4217.9     .11       0
  4964.5     .15       0  4983.2     .09       0  5018.4     .15       0
  5417.1     .11       0  5658.5     .17       0    5732     .11       0
  6321.4     .17       0
Bank Sta=4983.2,5018.4
XS Rating Curve= 0 ,0
Exp/Cntr=0.3,0.1

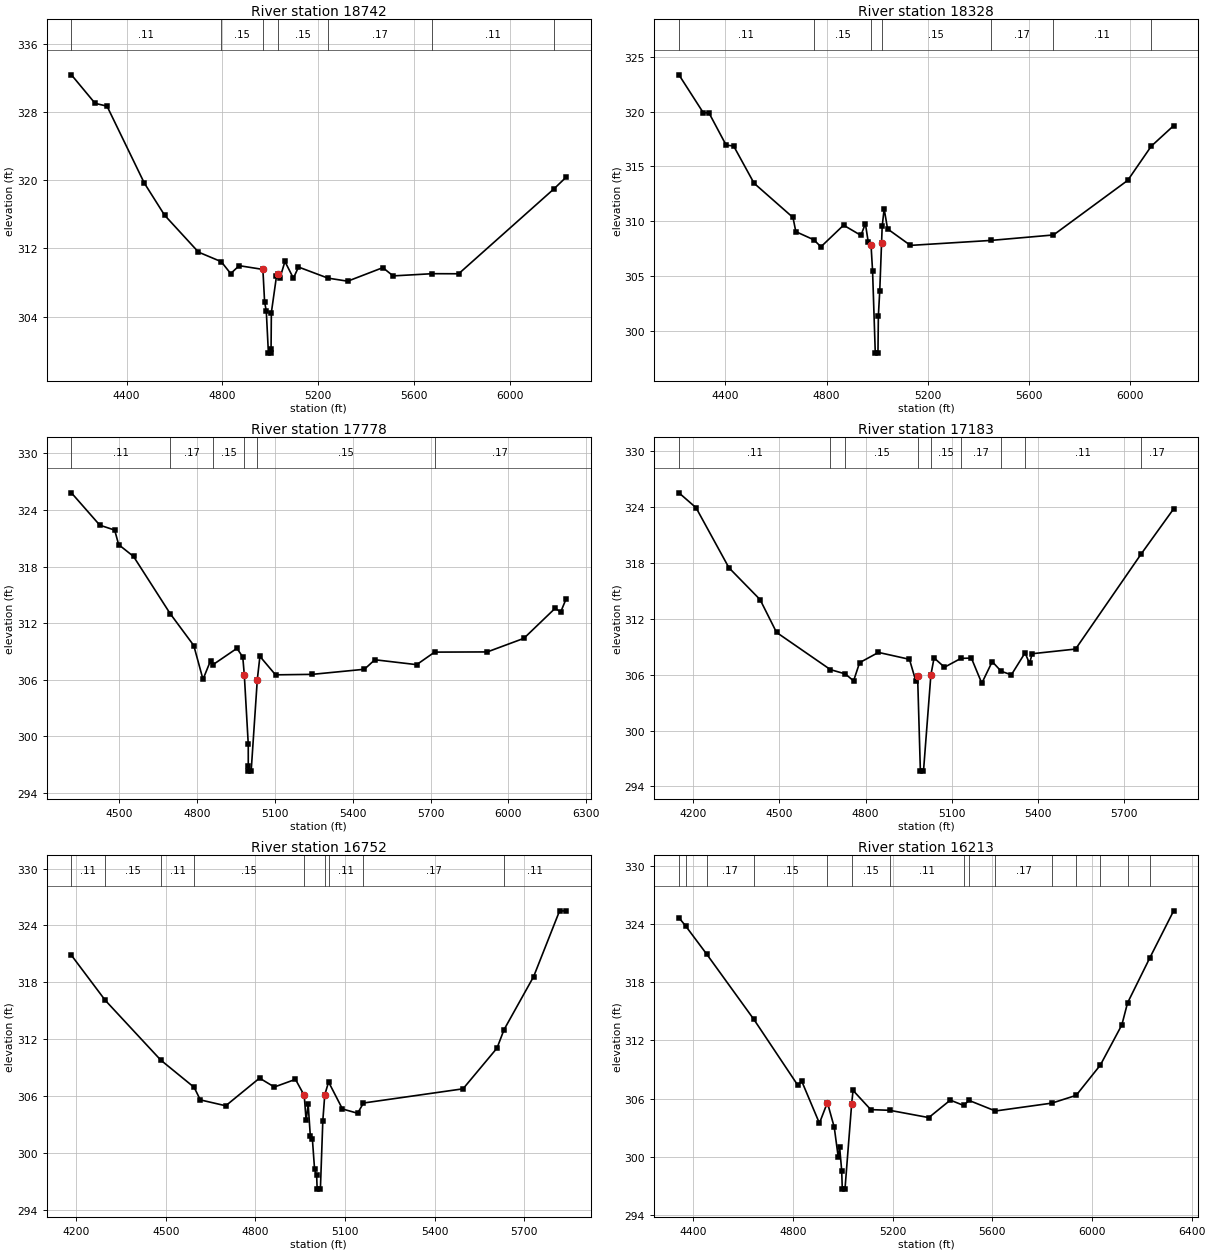
Type RM Length L Ch R = 1 ,18742   ,414,414,414
BEGIN DESCRIPTION:
FLAGTAIL CREEK 35.0
END DESCRIPTION:
XS GIS Cut Line= 3
      3694917.83     10202761.05      3694208.23     10202049.27
      3693201.89      10201719.4
#Sta/Elev= 30
  4169.7  332.37  4268.7  329.02  4318.2   328.7  4473.7  319.68  4558.6   315.9
    4700  311.57  4794.9  310.45  4834.3  309.05  4869.7  309.98  4968.7  309.54
  4975.8  305.73  4982.8  304.68  4991.7  299.72  5002.3  299.72  5002.8  300.22
    5004  304.47  5025.3  308.72  5032.3  309.06  5039.4  308.48  5060.6  310.47
    5096  308.51  5117.2  309.82  5240.1  308.52  5322.5  308.16  5469.3  309.75
  5511.9  308.78    5676  309.04  5785.5  309.03  6184.3  319.02  6233.8  320.36
#Mann= 7 ,-1 , 0
  4169.7     .11       0  4794.9     .15       0  4968.7     .09       0
  5032.3     .15       0  5240.1     .17       0    5676     .11       0
  6184.3     .17       0
Bank Sta=4968.7,5032.3
XS Rating Curve= 0 ,0
Exp/Cntr=0.3,0.1

Type RM Length L Ch R = 1 ,18328   ,550,550,550
BEGIN DESCRIPTION:
FLAGTAIL CREEK 34.0
END DESCRIPTION:
XS GIS Cut Line= 3
      3695167.46      10202127.4      3694425.25     10201784.51
      3693292.68     10201667.35
#Sta/Elev= 30
  4216.5  323.34  4312.4   319.9  4335.3  319.87  4403.3  316.93  4432.6  316.87
  4513.5  313.47  4667.5  310.35  4678.7  309.06  4749.9  308.32  4777.9  307.68
  4867.5  309.65  4936.3  308.72  4953.7   309.8  4965.1  308.11  4976.1  307.83
  4982.2  305.48  4992.9     298  5003.5     298  5005.1   301.4  5010.6  303.68
 5017.72308.0262  5020.2  309.54    5028  311.14  5041.5  309.31    5132  307.81
  5448.6  308.26  5697.6  308.76  5991.1  313.73  6084.1  316.84  6172.7  318.71
#Mann= 7 ,-1 , 0
  4216.5     .11       0  4749.9     .15       0  4976.1     .09       0
 5017.72     .15       0  5448.6     .17       0  5697.6     .11       0
  6084.1     .17       0
Bank Sta=4976.1,5017.72
XS Rating Curve= 0 ,0
Exp/Cntr=0.3,0.1

Type RM Length L Ch R = 1 ,17778   ,595,595,595
BEGIN DESCRIPTION:
FLAGTAIL CREEK 33.0
END DESCRIPTION:
XS GIS Cut Line= 4
      3695284.66      10201845.3      3694703.03     10201472.01
      3694546.78     10201458.99      3693496.42      10201589.2
#Sta/Elev= 30
    4316  325.82  4425.4  322.39  4482.8  321.87    4498  320.33  4555.5  319.07
  4696.6  313.01  4787.5  309.63  4823.1  306.04  4852.2  308.02  4862.3  307.61
  4953.9  309.33  4976.4  308.41  4982.3  306.51  4997.5  299.18  4997.6  296.81
  4998.1  296.31  5008.7  296.31  5032.4  306.02  5042.4  308.48  5102.6  306.52
  5243.4  306.57    5445  307.11  5485.3  308.12  5646.5   307.6  5715.7  308.93
  5918.6  308.95  6059.6  310.39  6180.6  313.59  6201.3  313.17  6222.3  314.57
#Mann= 6 ,-1 , 0
    4316     .11       0  4696.6     .17       0  4862.3     .15       0
  4982.3     .09       0  5032.4     .15       0  5715.7     .17       0
Bank Sta=4982.3,5032.4
XS Rating Curve= 0 ,0
Exp/Cntr=0.3,0.1

Type RM Length L Ch R = 1 ,17183   ,431,431,431
BEGIN DESCRIPTION:
FLAGTAIL CREEK 32.0
END DESCRIPTION:
XS GIS Cut Line= 3
      3695527.71     10201472.03      3694815.87     10201003.26
      3694086.72     10200530.18
#Sta/Elev= 30
  4150.2  325.53  4209.7  323.93  4324.2  317.48  4432.6  314.06  4489.8  310.54
  4677.5  306.54  4729.2  306.08  4757.9  305.33  4778.9  307.29  4844.5  308.39
  4952.3  307.65  4974.7   305.3  4980.7  305.88  4990.4  295.64  5001.2  295.64
 5026.88 305.958    5038   307.8  5074.3   306.8  5131.5  307.75  5167.9  307.78
  5204.1  305.08  5240.4   307.4  5271.4  306.37  5306.9  305.98  5354.6  308.34
  5370.2  307.21  5379.4  308.25  5530.4  308.75  5757.7  318.92  5871.7  323.81
#Mann= 9 ,-1 , 0
  4150.2     .11       0  4677.5     .17       0  4729.2     .15       0
  4980.7     .09       0 5026.88     .15       0  5131.5     .17       0
  5271.4     .15       0  5354.6     .11       0  5757.7     .17       0
Bank Sta=4980.7,5026.88
XS Rating Curve= 0 ,0
Exp/Cntr=0.3,0.1

Type RM Length L Ch R = 1 ,16752   ,539,539,539
BEGIN DESCRIPTION:
FLAGTAIL CREEK 31.0
END DESCRIPTION:
XS GIS Cut Line= 3
      3695517.85     10201311.07      3694941.74     10200708.12
      3694264.64      10200243.7
#Sta/Elev= 30
  4184.5  320.85  4297.8  316.09  4483.5  309.78    4595  306.91  4615.8  305.58
  4700.8  304.96    4814  307.88  4863.4  306.94  4934.1  307.75 4963.47 306.047
  4969.7  303.41  4976.6  305.11  4983.8  301.77  4990.7  301.46    4998  298.26
  5004.9  297.61  5006.7  296.16  5017.5  296.16  5025.6  303.37 5032.11306.1129
  5044.9  307.47  5091.3  304.62  5142.1  304.17  5161.5  305.25  5494.7  306.75
  5608.4  311.05  5631.8  312.99  5730.9   318.6  5817.5  325.52  5839.5  325.54
#Mann= 9 ,-1 , 0
  4184.5     .11       0  4297.8     .15       0  4483.5     .11       0
    4595     .15       0 4963.47     .09       0 5032.11     .15       0
  5044.9     .11       0  5161.5     .17       0  5631.8     .11       0
Bank Sta=4963.47,5032.11
XS Rating Curve= 0 ,0
Exp/Cntr=0.3,0.1

Type RM Length L Ch R = 1 ,16213   ,363,363,363
BEGIN DESCRIPTION:
FLAGTAIL CREEK 30.0
END DESCRIPTION:
XS GIS Cut Line= 3
      3695744.67     10201272.32      3695349.73     10200560.55
      3694277.67     10200087.46
#Sta/Elev= 30
  4341.9  324.63  4369.7  323.75  4452.7   320.9  4642.8  314.15  4818.8  307.38
  4834.8  307.79  4905.8  303.46  4937.8  305.59  4965.3  303.05  4981.3  299.97
    4987  300.96  4995.2  298.58  4997.6  296.67  5008.4  296.67 5035.07305.4003
  5040.8  306.84  5111.8  304.86  5187.9  304.79  5344.8  304.04  5431.2  305.84
  5484.7  305.29  5506.2  305.81  5612.2  304.72  5838.8  305.53  5936.4  306.33
  6033.5  309.45  6119.8  313.59  6142.6  315.85  6230.8  320.43  6327.7  325.34
#Mann= 15 ,-1 , 0
  4341.9     .17       0  4369.7     .11       0  4452.7     .17       0
  4642.8     .15       0  4937.8     .09       0 5035.07     .15       0
  5187.9     .11       0  5484.7     .17       0  5506.2     .15       0
  5612.2     .17       0  5838.8     .15       0  5936.4     .17       0
  6033.5     .15       0  6142.6     .11       0  6230.8     .17       0
Bank Sta=4937.8,5035.07
XS Rating Curve= 0 ,0
Exp/Cntr=0.3,0.1