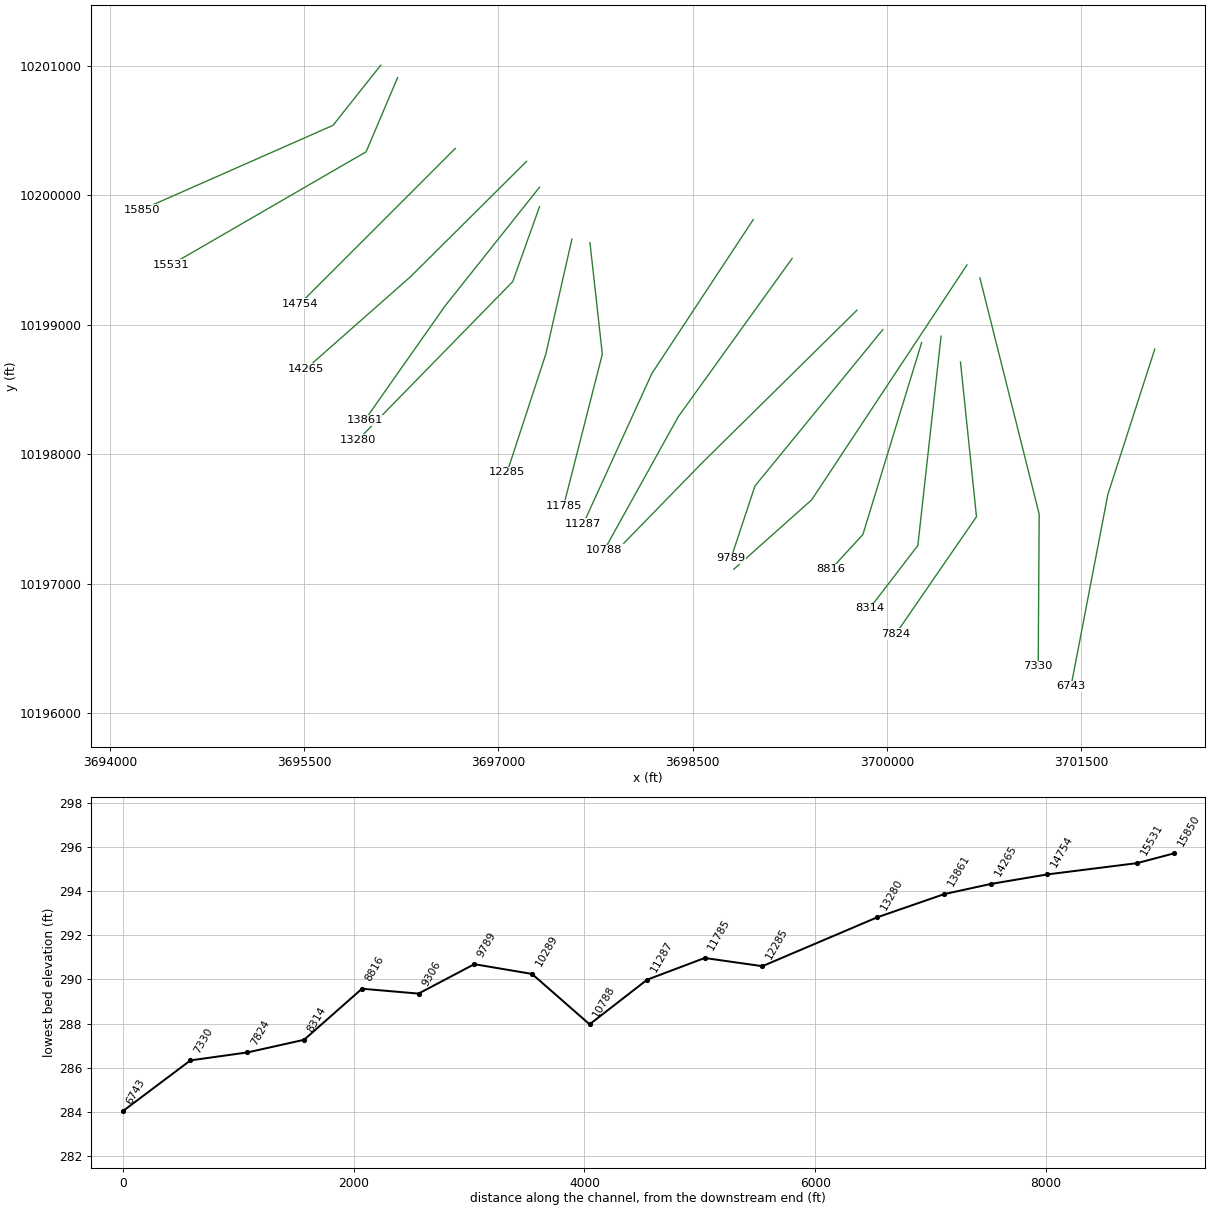
HEC-RAS study FLAGTAIL CREEK.prj: FLAGTAIL CREEK Base Level Engineering

--- FLAGTAIL CREEK.g01 (geometry) --- (continued)

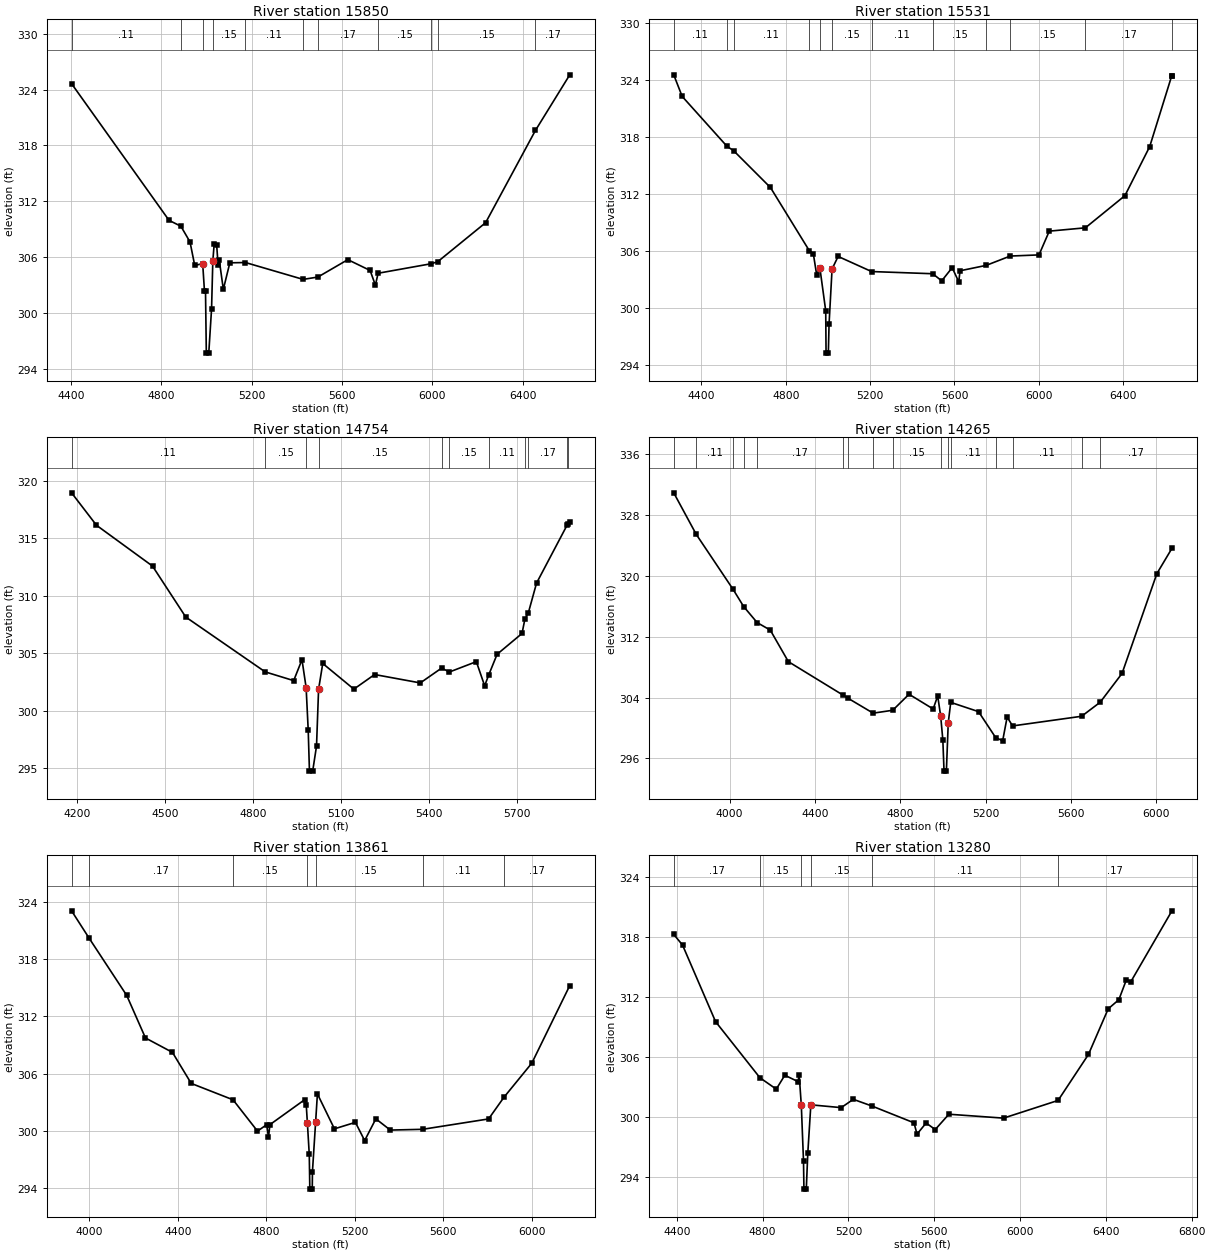
Type RM Length L Ch R = 1 ,15850   ,319,319,319
BEGIN DESCRIPTION:
FLAGTAIL CREEK 29.0
END DESCRIPTION:
XS GIS Cut Line= 3
      3696091.91     10201003.25      3695722.99     10200538.85
      3694247.32     10199887.82
#Sta/Elev= 30
  4401.8  324.64  4833.4  309.96  4885.8  309.33  4926.3  307.64  4947.1  305.12
  4982.4  305.31  4990.3  302.34  4994.9  302.34  4998.5   295.7  5009.3   295.7
  5021.7  300.46  5027.2  305.56  5033.3  307.44  5044.2  307.35  5050.5  305.21
    5056  305.65  5073.8  302.55  5102.6   305.4  5171.8  305.43  5427.1  303.62
  5492.4  303.87  5625.1  305.74  5723.8  304.58  5747.1     303  5759.3  304.28
  5993.9   305.3  6022.7  305.51  6235.3  309.71  6455.9  319.62  6607.8  325.59
#Mann= 11 ,-1 , 0
  4401.8     .11       0  4885.8     .15       0  4982.4     .09       0
  5027.2     .15       0  5171.8     .11       0  5427.1     .15       0
  5492.4     .17       0  5759.3     .15       0  5993.9     .17       0
  6022.7     .15       0  6455.9     .17       0
Bank Sta=4982.4,5027.2
XS Rating Curve= 0 ,0
Exp/Cntr=0.3,0.1

Type RM Length L Ch R = 1 ,15531   ,777,777,777
BEGIN DESCRIPTION:
FLAGTAIL CREEK 28.0
END DESCRIPTION:
XS GIS Cut Line= 3
      3696222.13     10200907.78      3695979.07     10200334.86
      3694473.03     10199462.48
#Sta/Elev= 30
  4268.6  324.53  4308.5  322.26  4521.2  317.01  4552.6  316.55  4727.2  312.68
  4911.1  306.05  4930.6  305.72  4946.4   303.5  4961.7  304.22  4989.4  299.71
    4991  295.26  5001.8  295.26  5005.2  298.31  5019.5  304.11  5048.2  305.43
  5206.9  303.84    5497  303.61  5539.5  302.86  5589.2  304.25  5620.4  302.75
  5626.4  303.92  5750.6  304.49  5864.5  305.47  6000.9  305.59  6049.7  308.09
  6220.9  308.44  6408.4  311.82    6526  316.98  6630.2  324.41  6631.4  324.41
#Mann= 12 ,-1 , 0
  4268.6     .11       0  4521.2     .15       0  4552.6     .11       0
  4911.1     .15       0  4961.7     .09       0  5019.5     .15       0
  5206.9     .11       0    5497     .15       0  5750.6     .17       0
  5864.5     .15       0  6220.9     .17       0  6630.2     .11       0
Bank Sta=4961.7,5019.5
XS Rating Curve= 0 ,0
Exp/Cntr=0.3,0.1

Type RM Length L Ch R = 1 ,14754   ,489,489,489
BEGIN DESCRIPTION:
FLAGTAIL CREEK 27.0
END DESCRIPTION:
XS GIS Cut Line= 3
      3696667.83     10200361.05      3696089.43     10199782.34
      3695467.87     10199161.09
#Sta/Elev= 30
  4181.8  318.95  4266.6  316.13  4457.5  312.58  4570.7  308.15  4841.3  303.38
  4938.4  302.62  4966.7  304.44  4980.8  302.01  4987.9  298.31  4992.1  294.75
  5003.1  294.75  5016.2  296.93  5023.2  301.86  5037.4  304.11  5143.4  301.88
  5214.1  303.15  5369.7  302.42  5442.3  303.71  5468.9  303.37  5560.6  304.27
  5588.9  302.17  5603.2  303.14  5631.3  304.91  5716.2  306.72  5726.1  307.98
  5737.6   308.5  5765.7   311.1  5870.8  316.19  5871.5  316.22  5878.8  316.38
#Mann= 11 ,-1 , 0
  4181.8     .11       0  4841.3     .15       0  4980.8     .09       0
  5023.2     .15       0  5442.3     .11       0  5468.9     .15       0
  5603.2     .11       0  5726.1     .15       0  5737.6     .17       0
  5870.8     .11       0  5871.5     .17       0
Bank Sta=4980.8,5023.2
XS Rating Curve= 0 ,0
Exp/Cntr=0.3,0.1

Type RM Length L Ch R = 1 ,14265   ,404,404,404
BEGIN DESCRIPTION:
FLAGTAIL CREEK 26.0
END DESCRIPTION:
XS GIS Cut Line= 3
      3697217.87     10200261.09      3696323.33     10199371.47
      3695517.85     10198661.07
#Sta/Elev= 30
  3738.4  330.95  3843.9  325.48  4016.7  318.24  4066.2  315.98  4129.4  313.87
    4191  312.88  4275.8  308.73  4533.5   304.3  4557.4  303.88  4673.3  301.95
    4765  302.33  4841.5  304.44  4954.6   302.5  4975.9  304.22    4990  301.53
    5000  298.41  5005.6  294.32  5016.6  294.32  5025.3  300.66    5037  303.37
  5167.3  302.15  5247.7  298.73  5280.5  298.32  5301.4  301.43  5327.1  300.27
  5650.6  301.54  5737.8  303.39  5840.2  307.18  6003.3  320.31    6074  323.64
#Mann= 16 ,-1 , 0
  3738.4     .17       0  3843.9     .11       0  4016.7     .17       0
  4066.2     .11       0  4129.4     .17       0  4533.5     .15       0
  4557.4     .17       0  4673.3     .11       0    4765     .15       0
    4990     .09       0  5025.3     .15       0    5037     .11       0
  5247.7     .15       0  5327.1     .11       0  5650.6     .15       0
  5737.8     .17       0
Bank Sta=4990,5025.3
XS Rating Curve= 0 ,0
Exp/Cntr=0.3,0.1

Type RM Length L Ch R = 1 ,13861   ,581,581,581
BEGIN DESCRIPTION:
FLAGTAIL CREEK 25.0
END DESCRIPTION:
XS GIS Cut Line= 3
      3697317.84     10200061.06      3696587.57     10199143.02
      3695967.84     10198261.05
#Sta/Elev= 30
  3919.9  323.08  3999.7  320.19    4169   314.2  4253.8  309.73  4375.6  308.22
  4460.5  304.96  4649.4  303.24    4760  299.95  4801.6  300.63  4809.7  299.31
  4816.1  300.63  4973.1  303.25  4980.4  302.65 4985.52300.7679  4993.9   297.5
  4996.4  293.86  5007.4  293.86  5008.3  295.71  5022.7  300.93  5030.7  303.86
  5107.6  300.19  5202.4  300.87  5244.2  298.96  5294.8  301.24  5360.1  300.06
  5506.2  300.14  5804.2  301.23  5873.1  303.49  5999.6  307.09  6170.9  315.23
#Mann= 7 ,-1 , 0
  3919.9     .11       0  3999.7     .17       0  4649.4     .15       0
 4985.52     .09       0  5022.7     .15       0  5506.2     .11       0
  5873.1     .17       0
Bank Sta=4985.52,5022.7
XS Rating Curve= 0 ,0
Exp/Cntr=0.3,0.1

Type RM Length L Ch R = 1 ,13280   ,995,995,995
BEGIN DESCRIPTION:
FLAGTAIL CREEK 24.0
END DESCRIPTION:
XS GIS Cut Line= 3
      3697317.85     10199911.08       3697111.4     10199332.83
      3695917.85     10198111.07
#Sta/Elev= 30
    4386  318.28  4426.9  317.22  4580.9  309.56  4787.6  303.95  4863.8  302.81
  4903.7   304.2  4965.3  303.56  4970.6  304.24  4980.6  301.19  4990.8  295.62
  4992.8  292.81  5003.8  292.81  5010.8  296.41    5025  301.24  5166.4  300.96
    5223  301.79  5311.1  301.11  5505.8  299.44  5519.9  298.31  5562.3  299.42
  5604.8  298.77  5668.5   300.3  5923.1  299.91  6177.4  301.68    6319  306.28
    6411  310.84  6460.5  311.75  6495.9  313.75    6517  313.57    6708  320.64
#Mann= 6 ,-1 , 0
    4386     .17       0  4787.6     .15       0  4980.6     .09       0
    5025     .15       0  5311.1     .11       0  6177.4     .17       0
Bank Sta=4980.6,5025
XS Rating Curve= 0 ,0
Exp/Cntr=0.3,0.1

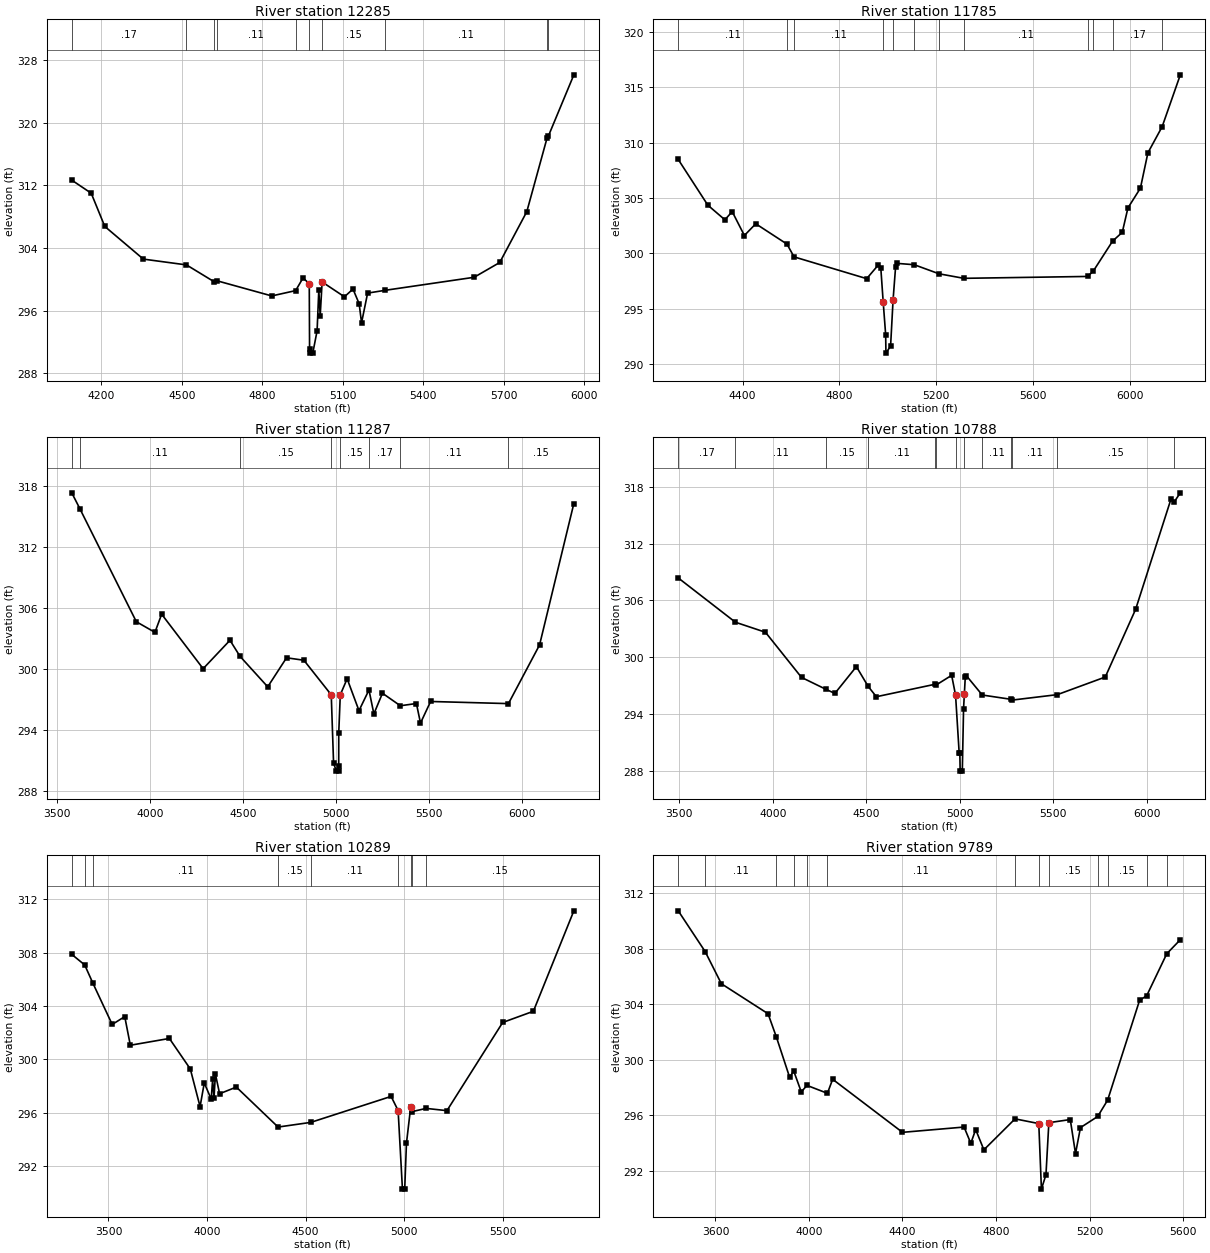
Type RM Length L Ch R = 1 ,12285   ,500,500,500
BEGIN DESCRIPTION:
FLAGTAIL CREEK 23.0
END DESCRIPTION:
XS GIS Cut Line= 3
      3697567.85     10199661.06      3697366.78     10198773.76
      3697067.85     10197861.06
#Sta/Elev= 30
  4090.2  312.68  4162.6  311.01  4213.2  306.77  4356.8   302.6  4517.5  301.86
  4619.1  299.74  4631.6  299.83  4835.2   297.9  4924.1  298.58  4951.5  300.19
 4974.85299.4738    4976   291.1  4976.5   290.6  4987.9   290.6    5004  293.44
  5010.4  298.65  5015.6  295.37 5022.68299.6864  5105.9  297.79  5137.7  298.78
  5160.7   296.9  5169.6  294.47  5192.2  298.26  5255.9  298.61  5588.9  300.28
  5684.4  302.17  5785.2  308.66  5860.3  318.02  5865.4  318.29  5960.4  326.12
#Mann= 10 ,-1 , 0
  4090.2     .17       0  4517.5     .11       0  4619.1     .15       0
  4631.6     .11       0  4924.1     .15       0 4974.85     .09       0
 5022.68     .15       0  5255.9     .11       0  5860.3     .17       0
  5865.4     .11       0
Bank Sta=4974.85,5022.68
XS Rating Curve= 0 ,0
Exp/Cntr=0.3,0.1

Type RM Length L Ch R = 1 ,11785   ,498,498,498
BEGIN DESCRIPTION:
FLAGTAIL CREEK 22.0
END DESCRIPTION:
XS GIS Cut Line= 3
      3697707.36     10199632.63      3697802.75      10198772.3
      3697504.24     10197601.35
#Sta/Elev= 30
  4134.4  308.47  4256.7  304.34  4327.1  303.02  4357.3  303.76  4407.6   301.6
  4454.7  302.66  4583.7  300.82  4612.7  299.67  4912.9   297.7    4961  298.94
  4971.1  298.69  4981.1  295.57  4991.2  292.65  4992.4  290.97  5011.6  291.61
  5021.9  295.79  5032.2  298.74  5038.7  299.08  5109.2  298.96  5211.6  298.14
  5314.1  297.73  5826.2   297.9  5849.7  298.41  5928.6  301.09  5968.7  301.89
    5992  304.09  6043.6  305.88  6074.5  309.07  6133.5  311.44  6208.4  316.12
#Mann= 12 ,-1 , 0
  4134.4     .11       0  4583.7     .15       0  4612.7     .11       0
  4981.1     .07       0  5021.9     .11       0  5109.2     .11       0
  5211.6     .15       0  5314.1     .11       0  5826.2     .17       0
  5849.7     .11       0  5928.6     .17       0  6133.5     .11       0
Bank Sta=4981.1,5021.9
XS Rating Curve= 0 ,0
Exp/Cntr=0.3,0.1

Type RM Length L Ch R = 1 ,11287   ,499,499,499
BEGIN DESCRIPTION:
FLAGTAIL CREEK 21.0
END DESCRIPTION:
XS GIS Cut Line= 3
      3698967.87      10199811.1       3698185.2     10198622.91
      3697655.28     10197460.72
#Sta/Elev= 30
  3577.2  317.32  3620.2  315.78  3924.5  304.66  4024.4  303.62  4060.6   305.4
  4283.7  300.05    4428  302.84  4481.7  301.27    4631  298.27  4732.2  301.12
  4825.5  300.88 4972.65297.4843  4985.2  290.74  5000.8  289.99  5012.3  289.99
  5012.8  290.49    5013  293.76 5021.27 297.489  5058.2  299.06  5121.8  295.93
  5175.5  297.96  5201.9  295.61    5248  297.64  5344.3  296.41  5430.6  296.63
  5452.6  294.71    5507  296.83  5925.5  296.62  6092.9  302.38  6277.3  316.27
#Mann= 8 ,-1 , 0
  3577.2     .17       0  3620.2     .11       0  4481.7     .15       0
 4972.65     .09       0 5021.27     .15       0  5175.5     .17       0
  5344.3     .11       0  5925.5     .15       0
Bank Sta=4972.65,5021.27
XS Rating Curve= 0 ,0
Exp/Cntr=0.3,0.1

Type RM Length L Ch R = 1 ,10788   ,499,499,499
BEGIN DESCRIPTION:
FLAGTAIL CREEK 20.0
END DESCRIPTION:
XS GIS Cut Line= 3
      3699267.83     10199511.04      3698388.81     10198288.68
      3697816.76     10197257.64
#Sta/Elev= 30
  3494.4  308.38  3800.1   303.7  3960.8  302.64  4153.6  297.87  4282.5  296.63
  4331.9  296.18    4447  299.01    4510  296.92  4553.8  295.83  4866.2  297.14
  4871.2  297.04  4956.4  298.09  4977.3     296  4996.5  289.93    5000  289.93
  5001.9  287.97  5013.4  287.97  5020.1  294.57 5024.22296.0719  5029.4  297.96
  5035.1  298.05  5120.1  296.01    5276  295.55    5278  295.47  5521.5  296.05
  5777.8  297.91  5940.3  305.07  6130.2  316.77  6146.2   316.4  6179.1  317.37
#Mann= 13 ,-1 , 0
  3494.4     .17       0  3800.1     .11       0  4282.5     .15       0
    4510     .11       0  4866.2     .15       0  4871.2     .17       0
  4977.3     .09       0 5024.22     .17       0  5120.1     .11       0
    5276     .17       0    5278     .11       0  5521.5     .15       0
  6146.2     .11       0
Bank Sta=4977.3,5024.22
XS Rating Curve= 0 ,0
Exp/Cntr=0.3,0.1

Type RM Length L Ch R = 1 ,10289   ,500,500,500
BEGIN DESCRIPTION:
FLAGTAIL CREEK 19.0
END DESCRIPTION:
XS GIS Cut Line= 3
      3699767.82     10199111.04       3698567.6     10197926.95
      3697967.82     10197311.04
#Sta/Elev= 30
    3314  307.87  3379.5  307.08  3421.4   305.7    3519  302.61  3582.6   303.2
  3610.9  301.05  3808.9  301.56    3915  299.27  3964.5  296.44  3985.8  298.22
  4021.1     297  4028.2  298.48  4035.2  297.11  4042.3  298.89  4063.5  297.41
  4148.4  297.91  4360.1  294.91  4525.8  295.26  4933.2  297.21  4968.7  296.15
  4990.6  290.25  5002.1  290.25    5011   293.7  5032.3  296.39  5040.3  296.07
  5110.7  296.31  5216.2  296.14  5498.9  302.76  5654.5   303.6  5859.7  311.14
#Mann= 9 ,-1 , 0
    3314     .11       0  3379.5     .17       0  3421.4     .11       0
  4360.1     .15       0  4525.8     .11       0  4968.7     .09       0
  5032.3     .15       0  5040.3     .11       0  5110.7     .15       0
Bank Sta=4968.7,5032.3
XS Rating Curve= 0 ,0
Exp/Cntr=0.3,0.1

Type RM Length L Ch R = 1 ,9789    ,483,483,483
BEGIN DESCRIPTION:
FLAGTAIL CREEK 18.0
END DESCRIPTION:
XS GIS Cut Line= 3
      3699967.85     10198961.07      3698981.11     10197753.95
      3698796.08     10197195.61
#Sta/Elev= 30
  3440.9  310.73  3555.9   307.8  3625.4  305.48    3825  303.32  3860.9  301.63
  3917.6  298.73  3934.5  299.21  3967.1  297.69  3991.4  298.16  4078.9  297.59
  4101.3   298.6    4400  294.78  4663.4  295.16  4692.2  293.99    4713  294.98
  4748.1  293.52  4881.4  295.75  4982.9  295.41  4994.2  290.69  5013.6  291.73
    5026295.4748  5117.6   295.7    5140  293.25  5161.1  295.12  5234.8  295.92
  5277.4   297.1  5413.9  304.28  5444.5  304.62  5530.3  307.64  5588.2  308.65
#Mann= 13 ,-1 , 0
  3440.9     .17       0  3555.9     .11       0  3860.9     .15       0
  3934.5     .11       0  3991.4     .15       0  4078.9     .11       0
  4881.4     .15       0  4982.9     .09       0    5026     .15       0
  5234.8     .17       0  5277.4     .15       0  5444.5     .11       0
  5530.3     .17       0
Bank Sta=4982.9,5026
XS Rating Curve= 0 ,0
Exp/Cntr=0.3,0.1

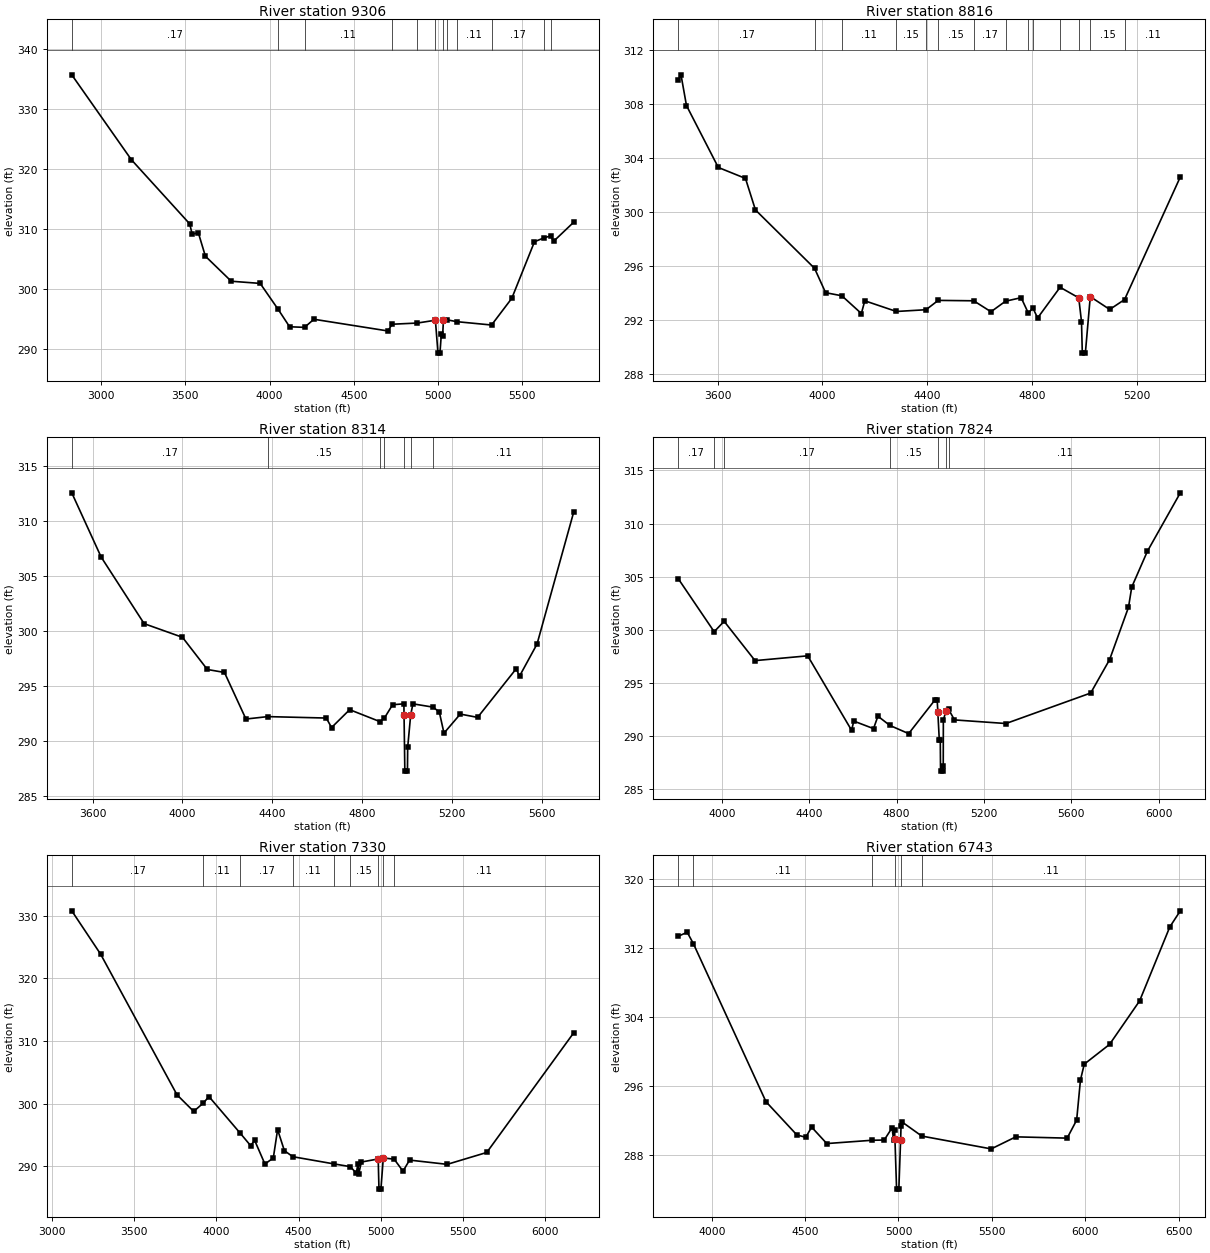
Type RM Length L Ch R = 1 ,9306    ,490,490,490
BEGIN DESCRIPTION:
FLAGTAIL CREEK 17.0
END DESCRIPTION:
XS GIS Cut Line= 3
      3700617.84     10199461.05      3699418.97     10197647.01
      3698817.88      10197111.1
#Sta/Elev= 30
  2825.6   335.7  3179.2  321.57  3525.3  310.89  3540.4  309.15  3576.5  309.42
  3618.6   305.5  3772.1  301.33  3943.7  300.97  4049.9  296.67  4118.3  293.75
  4206.8  293.65  4262.7     295  4702.1  293.05  4726.3  294.17  4876.4  294.37
 4983.64294.8375    4999  289.36  5010.6  289.36    5019  292.57  5026.5  292.21
 5031.46294.9194  5052.8  294.91    5110   294.6  5316.9  294.04  5437.1  298.49
  5571.7  307.91    5627  308.54  5668.6  308.89  5684.8  307.97  5805.3  311.18
#Mann= 12 ,-1 , 0
  2825.6     .17       0  4049.9     .15       0  4206.8     .11       0
  4726.3     .15       0  4876.4     .11       0 4983.64     .07       0
 5031.46     .11       0  5052.8     .15       0    5110     .11       0
  5316.9     .17       0    5627     .11       0  5668.6     .17       0
Bank Sta=4983.64,5031.46
XS Rating Curve= 0 ,0
Exp/Cntr=0.3,0.1

Type RM Length L Ch R = 1 ,8816    ,502,502,502
BEGIN DESCRIPTION:
FLAGTAIL CREEK 16.0
END DESCRIPTION:
XS GIS Cut Line= 3
      3700267.87     10198861.12      3699814.47     10197379.12
      3699567.88      10197111.1
#Sta/Elev= 30
  3450.2  309.79  3460.7  310.16  3481.6  307.89    3603  303.31  3706.5   302.5
  3744.5  300.17  3969.9  295.85    4012  294.05  4073.9  293.82  4148.3  292.51
  4161.4  293.45  4281.9  292.66  4394.8  292.79  4441.2  293.48  4576.6  293.45
  4642.4  292.64  4697.9  293.42  4757.4  293.68  4785.3  292.52  4801.9  292.93
  4820.2  292.18  4905.9  294.45    4977  293.67  4987.5  291.91  4990.6  289.58
  5002.2  289.58 5020.95 293.755  5095.1  292.81  5151.7  293.54  5364.2  302.61
#Mann= 14 ,-1 , 0
  3450.2     .17       0  3969.9     .15       0  4073.9     .11       0
  4281.9     .15       0  4394.8     .11       0  4441.2     .15       0
  4576.6     .17       0  4697.9     .11       0  4785.3     .17       0
  4801.9     .11       0  4905.9     .15       0    4977     .09       0
 5020.95     .15       0  5151.7     .11       0
Bank Sta=4977,5020.95
XS Rating Curve= 0 ,0
Exp/Cntr=0.3,0.1

Type RM Length L Ch R = 1 ,8314    ,490,490,490
BEGIN DESCRIPTION:
FLAGTAIL CREEK 15.0
END DESCRIPTION:
XS GIS Cut Line= 3
      3700417.85     10198911.05      3700238.62     10197294.06
      3699867.84     10196811.06
#Sta/Elev= 30
    3507  312.54  3637.8  306.71  3829.3  300.66    4000  299.42  4110.7   296.5
  4186.9  296.23  4282.6     292  4379.9  292.22  4640.2  292.09    4664  291.23
  4744.5  292.85    4880  291.76  4899.5   292.1  4935.7   293.3    4986  293.38
 4986.66292.3791  4990.2  287.27  5001.8  287.27  5002.9  289.44  5016.2  292.37
  5026.2  293.38  5115.9  293.08  5143.7  292.64  5164.5  290.72  5237.1  292.45
  5314.2  292.15  5486.3  296.57  5500.8  295.89  5578.9  298.81  5742.8  310.84
#Mann= 7 ,-1 , 0
    3507     .17       0  4379.9     .15       0    4880     .11       0
  4899.5     .15       0 4986.66     .09       0  5016.2     .15       0
  5115.9     .11       0
Bank Sta=4986.66,5016.2
XS Rating Curve= 0 ,0
Exp/Cntr=0.3,0.1

Type RM Length L Ch R = 1 ,7824    ,494,494,494
BEGIN DESCRIPTION:
FLAGTAIL CREEK 14.0
END DESCRIPTION:
XS GIS Cut Line= 3
      3700567.85     10198711.05      3700691.39     10197516.93
      3700067.86     10196611.08
#Sta/Elev= 30
  3799.5  304.81  3964.1  299.82  4009.8   300.8  4151.3   297.1  4392.6  297.55
  4593.7  290.54  4603.7  291.41  4694.2   290.7  4714.3  291.87  4769.1     291
  4855.1  290.23  4975.7   293.4  4985.8  293.43 4988.81292.2479  4995.4  289.66
    5000  289.66  5001.2   286.7  5013.1   286.7  5013.6   287.2  5014.1  291.51
 5026.52292.3781    5038  292.52  5064.9  291.52  5300.9  291.18  5689.1  294.05
  5775.7  297.19  5862.3  302.12  5877.2  304.02  5948.9  307.39  6099.7  312.89
#Mann= 7 ,-1 , 0
  3799.5     .17       0  3964.1     .11       0  4009.8     .17       0
  4769.1     .15       0 4988.81     .09       0 5026.52     .15       0
    5038     .11       0
Bank Sta=4988.81,5026.52
XS Rating Curve= 0 ,0
Exp/Cntr=0.3,0.1

Type RM Length L Ch R = 1 ,7330    ,587,587,587
BEGIN DESCRIPTION:
FLAGTAIL CREEK 13.0
END DESCRIPTION:
XS GIS Cut Line= 3
      3700717.85     10199361.07      3701175.51      10197536.6
      3701167.85     10196361.02
#Sta/Elev= 30
    3119  330.81  3294.3   323.9  3759.7  301.41  3861.3  298.76  3920.4  300.11
  3954.1  301.13  4145.4  295.25  4207.4   293.3  4232.5  294.12  4294.9  290.35
  4345.9  291.32  4372.1  295.85  4413.3  292.49  4464.7  291.52  4715.1  290.37
  4815.4  289.93    4851  288.88    4861  290.36  4866.1  288.79    4882  290.67
  4984.5  291.16  4989.2  286.34  5001.1  286.34  5015.5  291.32  5081.6  291.13
  5135.5  289.21  5175.5  290.98  5404.5   290.3  5645.5   292.2  6175.6  311.35
#Mann= 9 ,-1 , 0
    3119     .17       0  3920.4     .11       0  4145.4     .17       0
  4464.7     .11       0  4715.1     .17       0  4815.4     .15       0
  4984.5     .09       0  5015.5     .15       0  5081.6     .11       0
Bank Sta=4984.5,5015.5
XS Rating Curve= 0 ,0
Exp/Cntr=0.3,0.1

Type RM Length L Ch R = 1 ,6743    ,600,600,600
BEGIN DESCRIPTION:
FLAGTAIL CREEK 12.0
END DESCRIPTION:
XS GIS Cut Line= 3
      3702067.86     10198811.11      3701705.69     10197688.38
      3701420.96     10196205.77
#Sta/Elev= 30
  3820.3   313.4  3868.4  313.86  3901.6  312.53  4290.3  294.19  4455.8  290.33
  4503.3  290.06  4534.8  291.24    4616  289.33  4856.2  289.71  4923.6  289.74
  4965.6  291.15  4973.8   289.8    4979  290.93 4981.08289.8414  4989.9  284.04
    5002  284.04 5011.43289.7605  5013.8  291.36  5018.9  291.84  5124.8   290.2
  5496.8  288.71  5628.6  290.11  5903.5  289.96  5954.4  292.05  5974.8  296.71
  5995.2  298.55  6130.6  300.84  6291.6  305.89  6453.4  314.48  6509.7  316.35
#Mann= 6 ,-1 , 0
  3820.3     .17       0  3901.6     .11       0  4856.2     .15       0
 4981.08     .09       0 5011.43     .15       0  5124.8     .11       0
Bank Sta=4981.08,5011.43
XS Rating Curve= 0 ,0
Exp/Cntr=0.3,0.1