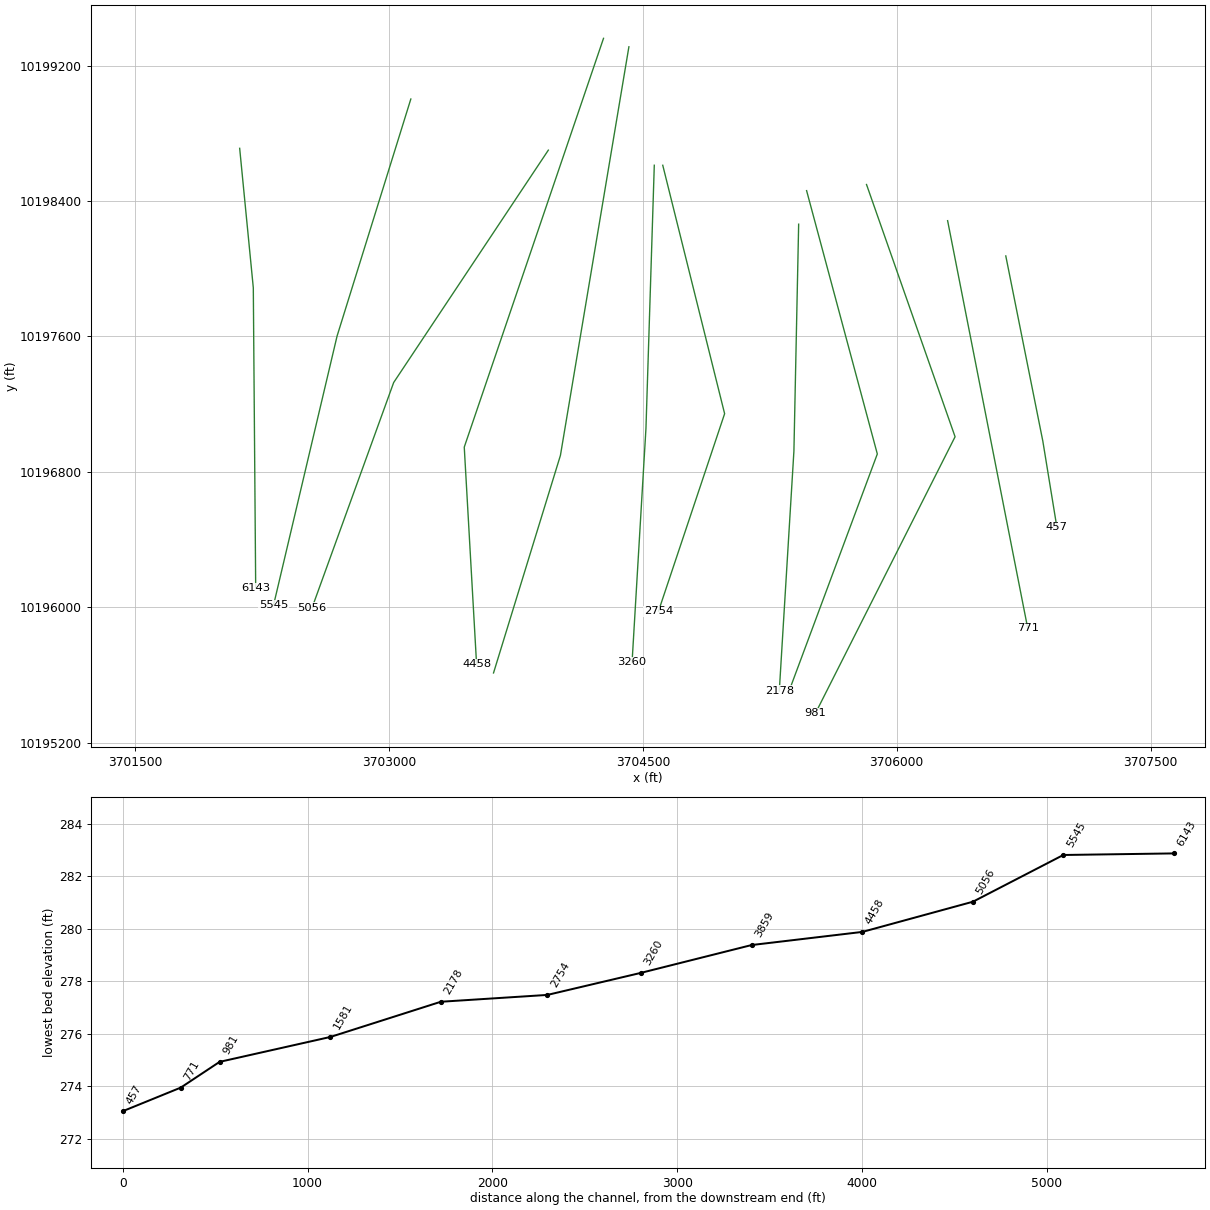
HEC-RAS study FLAGTAIL CREEK.prj: FLAGTAIL CREEK Base Level Engineering

--- FLAGTAIL CREEK.g01 (geometry) --- (continued)

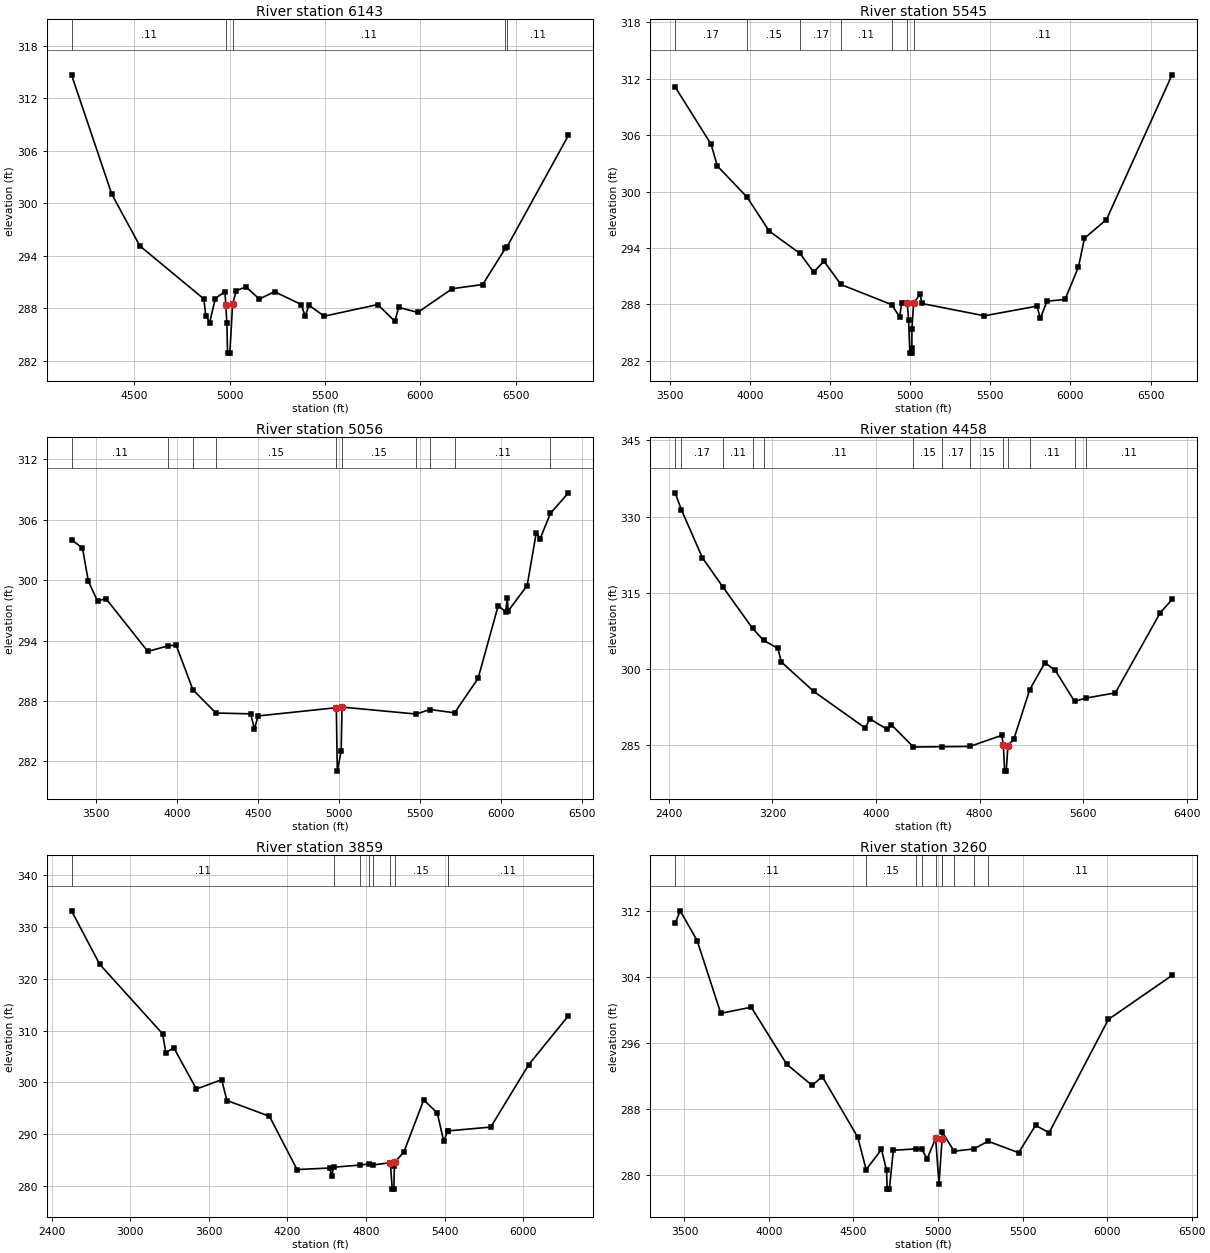
Type RM Length L Ch R = 1 ,6143    ,598,598,598
BEGIN DESCRIPTION:
FLAGTAIL CREEK 11.0
END DESCRIPTION:
XS GIS Cut Line= 3
      3702117.85     10198711.07      3702198.45       10197887.
      3702212.57     10196111.76
#Sta/Elev= 30
    4172  314.67    4383  301.03  4530.1  295.12  4865.3  289.06  4875.3  287.16
  4895.4  286.36  4925.6  289.11  4975.8  289.91 4979.97288.4235  4985.9  286.31
  4989.4  282.87  5001.5  282.87  5015.9  288.51  5035.9  290.01  5085.9  290.45
  5155.9  289.05  5235.9  289.89  5375.9  288.42  5395.9  287.09  5415.9  288.34
  5495.9  287.09    5776  288.42    5866  286.51    5886   288.1    5986  287.52
    6166  290.23    6326  290.71  6444.9  294.84  6452.7  294.98  6775.3  307.76
#Mann= 5 ,-1 , 0
    4172     .11       0 4979.97     .06       0  5015.9     .11       0
  6444.9     .17       0  6452.7     .11       0
Bank Sta=4979.97,5015.9
XS Rating Curve= 0 ,0
Exp/Cntr=0.3,0.1

Type RM Length L Ch R = 1 ,5545    ,489,489,489
BEGIN DESCRIPTION:
FLAGTAIL CREEK 10.0
END DESCRIPTION:
XS GIS Cut Line= 3
      3703129.25     10199002.43      3702693.31     10197601.39
      3702317.86     10196011.11
#Sta/Elev= 30
  3532.7  311.13  3757.7  305.01  3795.9  302.72  3981.3  299.41  4120.6  295.78
    4312  293.41  4396.9  291.43    4462  292.59  4567.3  290.11  4884.9  287.96
  4933.2  286.67    4948  288.18 4981.43288.1349  4989.9  286.32  4997.6  282.81
  5009.8  282.81  5010.3  283.31  5010.6  285.36  5020.9   288.1    5062  289.12
  5072.2  288.09  5462.7  286.78  5791.5  287.81    5812   286.5  5853.1  288.33
  5966.2  288.52    6050  291.97  6087.2  295.03  6224.4  297.01    6634  312.41
#Mann= 7 ,-1 , 0
  3532.7     .17       0  3981.3     .15       0    4312     .17       0
  4567.3     .11       0  4884.9     .15       0 4981.43     .09       0
  5020.9     .11       0
Bank Sta=4981.43,5020.9
XS Rating Curve= 0 ,0
Exp/Cntr=0.3,0.1

Type RM Length L Ch R = 1 ,5056    ,598,598,598
BEGIN DESCRIPTION:
FLAGTAIL CREEK 9.0
END DESCRIPTION:
XS GIS Cut Line= 3
      3703941.74      10198700.3      3703027.84     10197327.23
       3702545.9     10195997.15
#Sta/Elev= 30
  3350.6  304.01  3418.3  303.18  3454.3  299.89  3511.4  297.92  3562.5  298.17
    3821  292.92  3945.7  293.47  3995.3  293.56  4099.2  289.11  4241.1   286.8
  4455.2  286.72  4478.8   285.2  4500.3  286.51  4983.4  287.33  4989.4  281.03
  5013.3  283.04  5018.6  287.39  5475.5   286.7  5561.8  287.15  5712.4  286.82
  5857.4  290.24  5981.5  297.46  6027.6  296.86  6037.5  298.26  6042.8  296.93
    6160  299.46    6216  304.68  6240.4  304.13  6303.9  306.64  6414.7  308.67
#Mann= 10 ,-1 , 0
  3350.6     .11       0  3945.7     .15       0  4099.2     .11       0
  4241.1     .15       0  4983.4     .09       0  5018.6     .15       0
  5475.5     .11       0  5561.8     .15       0  5712.4     .11       0
  6303.9     .17       0
Bank Sta=4983.4,5018.6
XS Rating Curve= 0 ,0
Exp/Cntr=0.3,0.1

Type RM Length L Ch R = 1 ,4458    ,599,599,599
BEGIN DESCRIPTION:
FLAGTAIL CREEK 8.0
END DESCRIPTION:
XS GIS Cut Line= 3
      3704267.84     10199361.03      3703444.94     10196945.56
      3703517.85     10195661.02
#Sta/Elev= 30
  2448.2  334.67  2496.9  331.33  2659.4  321.87    2817  316.15  3046.6  307.98
  3132.7   305.6  3242.3  304.06  3268.4  301.37  3519.2  295.57  3916.2  288.38
  3952.9  290.16  4085.6  288.11  4117.3  289.04  4289.2  284.62  4511.2  284.69
  4724.7  284.74  4971.6  286.93  4983.6  284.94  4993.6  279.88  5005.8  279.88
 5018.91284.9247  5064.6  286.19  5187.5  295.93    5305  301.23  5385.1   299.7
  5533.2  293.61  5620.8  294.26  5848.1  295.28  6194.9  311.03  6286.6  313.68
#Mann= 13 ,-1 , 0
  2448.2     .11       0  2496.9     .17       0    2817     .11       0
  3046.6     .17       0  3132.7     .11       0  4289.2     .15       0
  4511.2     .17       0  4724.7     .15       0  4983.6     .09       0
 5018.91     .15       0  5187.5     .11       0  5533.2     .17       0
  5620.8     .11       0
Bank Sta=4983.6,5018.91
XS Rating Curve= 0 ,0
Exp/Cntr=0.3,0.1

Type RM Length L Ch R = 1 ,3859    ,599,599,599
BEGIN DESCRIPTION:
FLAGTAIL CREEK 7.0
END DESCRIPTION:
XS GIS Cut Line= 3
      3704417.85     10199311.08      3704013.24     10196896.75
      3703617.85     10195611.08
#Sta/Elev= 30
    2552  333.11  2766.9   322.8  3247.2  309.36  3271.9  305.74  3332.7  306.66
  3505.1  298.71  3697.8   300.5  3738.3  296.49  4062.8  293.45  4273.5  283.16
  4521.2  283.45  4539.3  281.93  4551.7  283.61  4752.3  284.02  4820.8  284.24
  4854.6  284.04  4985.5  284.49  5000.2  279.38  5012.4  279.38  5016.4  283.84
  5020.7284.5895  5089.6  286.59  5240.4   296.6  5343.7  294.08    5393  288.64
  5423.7   290.6  5428.2  290.63  5751.9  291.36  6041.7   303.4  6345.1  312.87
#Mann= 9 ,-1 , 0
    2552     .11       0  4551.7     .15       0  4752.3     .17       0
  4820.8     .15       0  4854.6     .11       0  4985.5     .06       0
  5020.7     .15       0  5423.7     .17       0  5428.2     .11       0
Bank Sta=4985.5,5020.7
XS Rating Curve= 0 ,0
Exp/Cntr=0.3,0.1

Type RM Length L Ch R = 1 ,3260    ,506,506,506
BEGIN DESCRIPTION:
FLAGTAIL CREEK 6.0
END DESCRIPTION:
XS GIS Cut Line= 3
      3704567.85     10198611.12      3704518.63      10197056.8
      3704436.58     10195675.13
#Sta/Elev= 30
  3444.9  310.47    3475  311.99    3575   308.4  3715.1  299.59  3895.2  300.33
  4105.3  293.42  4255.4  290.87  4315.4  291.94  4525.5  284.59  4574.8  280.68
  4665.6  283.12  4695.6   280.6    4699  278.32  4712.2  278.32  4735.6  283.02
    4872  283.19  4903.3  283.15  4935.7     282  4985.7  284.46  5005.7  278.99
 5023.93  284.37  5025.8  285.21  5094.7  282.91  5210.1  283.18  5296.2  284.11
  5476.6  282.73  5576.7  286.03  5656.9  285.15  6007.5  298.85  6384.1  304.18
#Mann= 10 ,-1 , 0
  3444.9     .11       0  4574.8     .15       0    4872     .11       0
  4903.3     .17       0  4985.7     .72       0 5023.93     .75       0
  5025.8     .17       0  5094.7     .11       0  5210.1     .17       0
  5296.2     .11       0
Bank Sta=4985.7,5023.93
XS Rating Curve= 0 ,0
Exp/Cntr=0.3,0.1

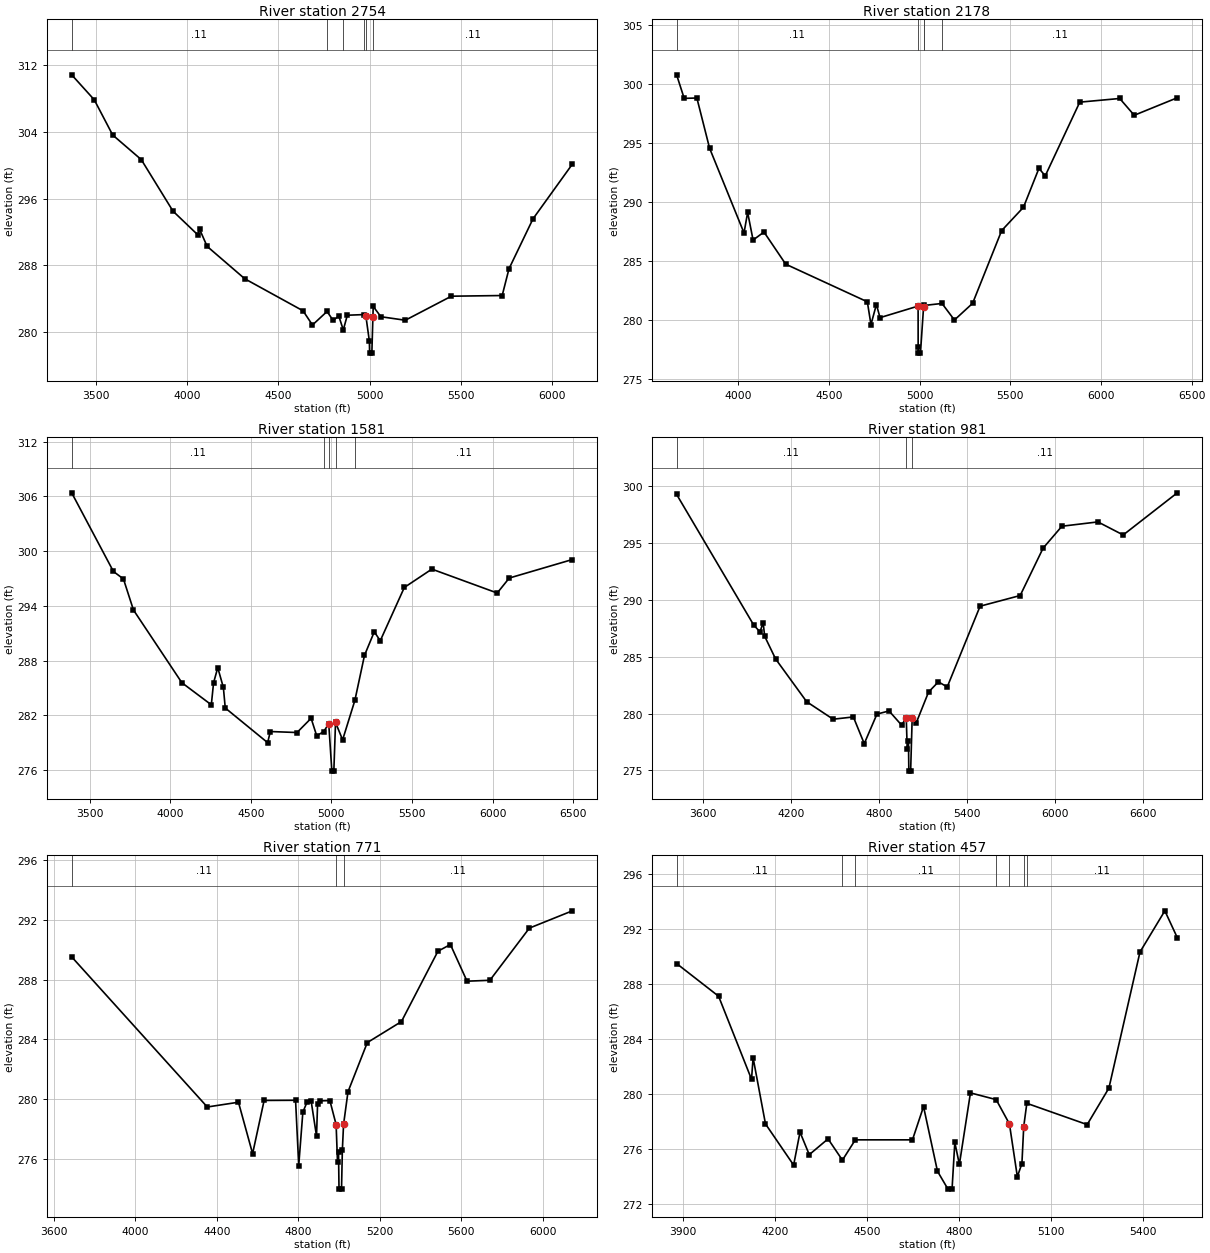
Type RM Length L Ch R = 1 ,2754    ,576,576,576
BEGIN DESCRIPTION:
FLAGTAIL CREEK 5.0
END DESCRIPTION:
XS GIS Cut Line= 3
      3704617.86     10198611.06      3704983.41     10197143.02
      3704592.81     10195976.44
#Sta/Elev= 30
  3367.9  310.82  3491.5  307.83  3592.5  303.61  3749.2  300.66  3922.9  294.49
  4058.3  291.66  4068.6  292.32  4109.9  290.27    4316  286.39  4635.4  282.55
    4687  280.85  4766.9  282.47  4800.6  281.39  4831.2  281.93    4856  280.26
    4878  282.02  4972.1   282.1    4980  281.88  4998.8  278.92  5000.2  277.48
  5012.4  277.48 5018.24281.8637  5019.9  283.07  5062.1  281.84  5195.7  281.42
  5448.2   284.3  5726.5  284.38  5763.9  287.59  5895.4  293.57    6111  300.12
#Mann= 6 ,-1 , 0
  3367.9     .11       0  4766.9     .15       0    4856     .11       0
  4972.1     .15       0    4980     .09       0 5018.24     .11       0
Bank Sta=4980,5018.24
XS Rating Curve= 0 ,0
Exp/Cntr=0.3,0.1

Type RM Length L Ch R = 1 ,2178    ,597,597,597
BEGIN DESCRIPTION:
FLAGTAIL CREEK 4.0
END DESCRIPTION:
XS GIS Cut Line= 3
      3705420.91     10198262.83      3705392.89     10196922.32
      3705306.44     10195504.25
#Sta/Elev= 30
  3659.2  300.75    3701  298.76    3771  298.79    3841  294.55    4031  287.38
    4051  289.12    4081  286.78  4141.1  287.46  4261.1  284.74  4711.2  281.56
  4731.2  279.64  4761.2  281.33  4781.2  280.22 4991.26281.1977  4991.5  277.72
    4992  277.22  5004.2  277.22  5021.3   281.1  5024.3  281.25    5123  281.42
  5191.6  280.02  5291.8  281.43  5452.1  287.58  5572.3  289.55  5657.7  292.84
  5692.5  292.21  5882.9  298.44  6103.3  298.75  6183.4  297.33  6420.7  298.81
#Mann= 5 ,-1 , 0
  3659.2     .11       0 4991.26     .06       0  5021.3     .11       0
  5024.3     .15       0    5123     .11       0
Bank Sta=4991.26,5021.3
XS Rating Curve= 0 ,0
Exp/Cntr=0.3,0.1

Type RM Length L Ch R = 1 ,1581    ,600,600,600
BEGIN DESCRIPTION:
FLAGTAIL CREEK 3.0
END DESCRIPTION:
XS GIS Cut Line= 3
      3705467.85     10198461.08       3705885.7       10196905.
      3705364.29      10195504.2
#Sta/Elev= 30
  3388.8  306.38  3647.7  297.76  3709.8  296.94  3771.9  293.54  4072.2  285.57
  4254.9  283.15  4268.9  285.56  4294.9  287.22  4329.7  285.05  4341.4   282.8
  4604.4     279    4621  280.22  4786.6  280.11    4874  281.67  4908.8  279.75
  4952.6  280.22  4983.4  281.08  5002.7  275.88    5015  275.88  5025.5  281.21
  5069.5  279.31  5145.5  283.63  5205.2  288.57  5265.9  291.15    5303  290.17
  5452.3  296.01  5623.1  298.02  6028.5   295.4  6103.2  297.04  6494.7  299.07
#Mann= 5 ,-1 , 0
  3388.8     .11       0  4952.6     .15       0  4983.4     .09       0
  5025.5     .15       0  5145.5     .11       0
Bank Sta=4983.4,5025.5
XS Rating Curve= 0 ,0
Exp/Cntr=0.3,0.1

Type RM Length L Ch R = 1 ,981     ,210,210,210
BEGIN DESCRIPTION:
FLAGTAIL CREEK 2.0
END DESCRIPTION:
XS GIS Cut Line= 3
      3705821.95     10198497.18       3706345.2     10197006.76
      3705519.88     10195372.21
#Sta/Elev= 30
  3420.4  299.29  3946.2  287.78  3988.6  287.19  4009.8  288.01  4020.4   286.8
  4094.6  284.81  4306.5  281.04  4486.7   279.5  4624.5   279.7  4698.7  277.35
  4785.2  279.95  4867.6  280.23    4953  278.98  4984.8  279.62  4991.5  276.88
    5000  277.61  5002.4  274.93  5014.7  274.93  5025.3  279.64  5053.2  279.19
  5136.8  281.89  5203.7  282.79    5264  282.34  5487.9  289.45    5761  290.39
  5917.1  294.56  6045.3  296.49  6290.5  296.87  6462.7  295.72  6831.1  299.43
#Mann= 3 , 0 , 0
  3420.4     .11       0  4984.8     .06       0  5025.3     .11       0
Bank Sta=4984.8,5025.3
XS Rating Curve= 0 ,0
Exp/Cntr=0.3,0.1

Type RM Length L Ch R = 1 ,771     ,314,314,314
BEGIN DESCRIPTION:
Mapping XS 917452ed
END DESCRIPTION:
XS GIS Cut Line= 2
      3706301.12     10198283.63      3706774.69     10195874.13
#Sta/Elev= 30
  3688.7  289.53  4353.7  279.46  4506.6  279.78    4576  276.33  4632.5   279.9
  4786.7  279.91  4802.2  275.53  4822.5  279.12  4843.2  279.79  4863.3  279.84
  4889.5  277.51  4894.6  279.63  4904.1  279.87    4955  279.89  4985.6  278.28
  4992.4  275.76  4997.4  276.43  4999.8  273.95  5012.1  273.95  5016.2  276.57
  5022.1 278.288  5043.8  280.48  5138.5  283.78  5305.9  285.19    5485  289.91
  5546.1  290.36  5627.7   287.9  5739.8  287.96  5933.4  291.46  6144.3  292.62
#Mann= 3 , 0 , 0
  3688.7     .11       0  4985.6     .06       0  5022.1     .11       0
Bank Sta=4985.6,5022.1
XS Rating Curve= 0 ,0
Exp/Cntr=0.3,0.1

Type RM Length L Ch R = 1 ,457     ,0,0,0
BEGIN DESCRIPTION:
FLAGTAIL CREEK 1.0
END DESCRIPTION:
XS GIS Cut Line= 3
      3706644.87     10198075.28      3706863.62     10196981.56
      3706946.96      10196471.1
#Sta/Elev= 30
  3879.7  289.48  4016.6   287.1    4124  281.05  4129.1  282.62  4169.5   277.8
  4261.3   274.8  4282.1   277.2  4312.3  275.56  4373.5  276.71  4420.4  275.16
  4462.4  276.64  4648.8  276.64  4684.9  279.06  4730.4  274.35  4764.6  273.05
  4777.9  273.05  4786.9  276.45  4801.8  274.85  4837.9  280.06  4921.7  279.57
    4965   277.8  4990.8  273.96  5005.7  274.91 5011.65  277.61  5021.7   279.3
  5218.5  277.75  5289.4  280.41  5390.7  290.32  5471.8  293.32  5512.3  291.37
#Mann= 7 ,-1 , 0
  3879.7     .11       0  4420.4     .15       0  4462.4     .11       0
  4921.7     .15       0    4965     .09       0 5011.65     .15       0
  5021.7     .11       0
Bank Sta=4965,5011.65
XS Rating Curve= 0 ,0
Exp/Cntr=0.3,0.1

Chan Stop Cuts=-1
Use User Specified Reach Order=0
Composite Channel Slope=5