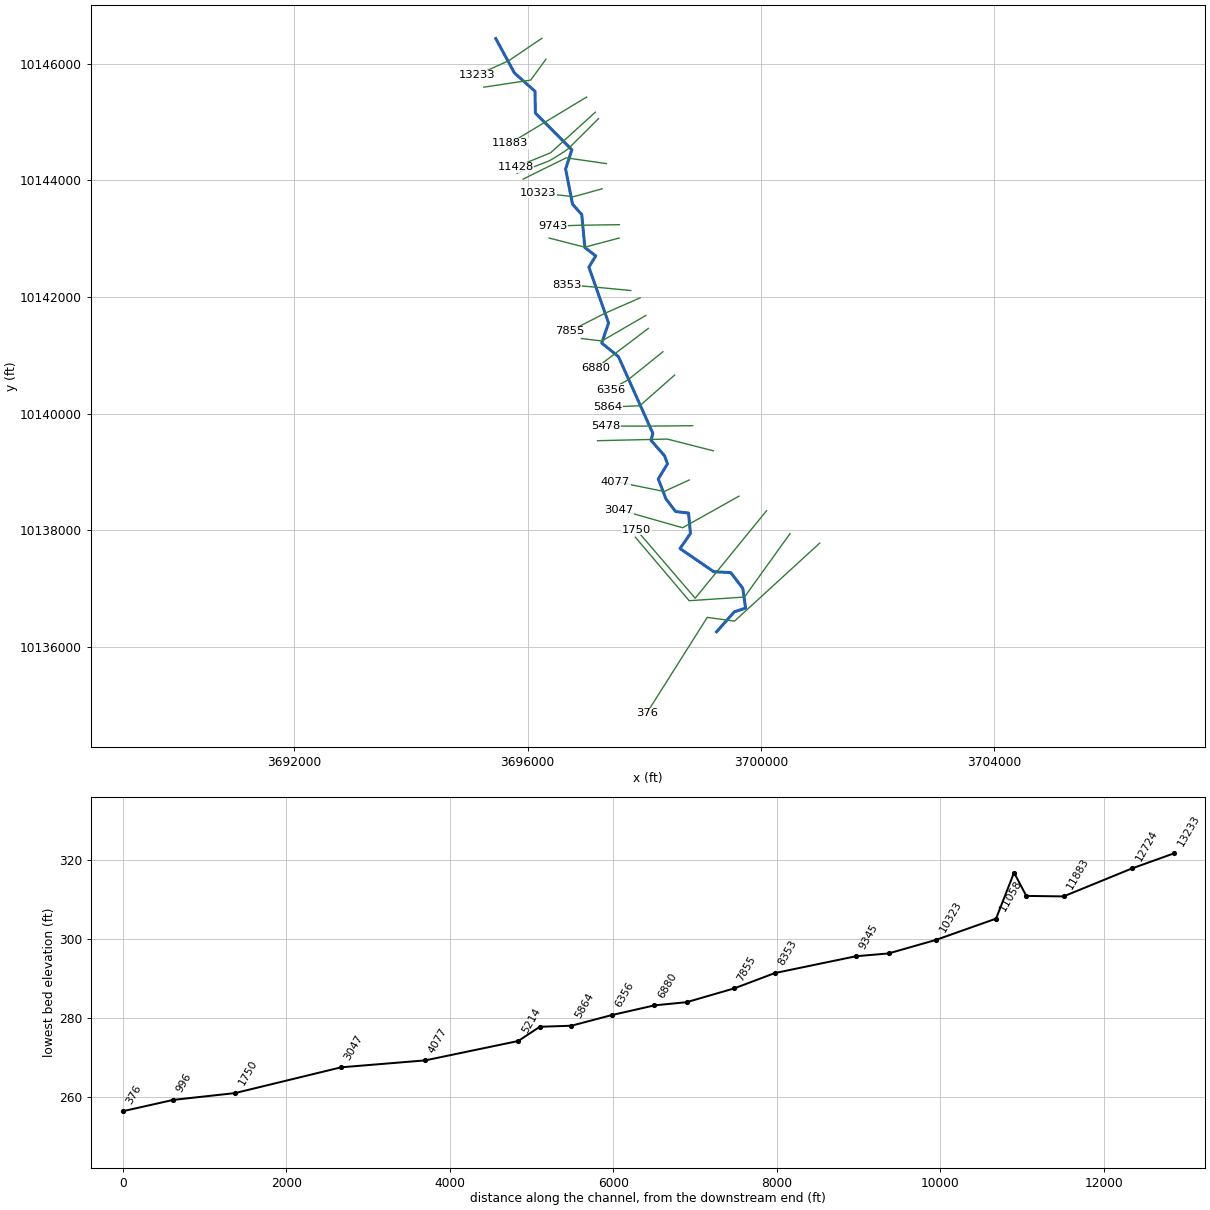
--- FLOYDS CREEK.prj (project) ---

Proj Title=FLOYDS CREEK Base Level Engineering
Current Plan=p01
Default Exp/Contr=0.3,0.1
English Units
Geom File=g01
Flow File=f01
Flow File=f02
Plan File=p01
Y Axis Title=Elevation
X Axis Title(PF)=Main Channel Distance
X Axis Title(XS)=Station
BEGIN DESCRIPTION:
FLOYDS CREEK
END DESCRIPTION:
DSS Export Rating Curves= 0
DSS Export Rating Curve Sorted= 0
DSS Export Volume Flow Curves= 0
DXF OffsetX= 0
DXF OffsetY= 0
DXF ScaleX= 1
DXF ScaleY= 10

--- FLOYDS CREEK.p01 (plan) ---

Plan Title=Multiple Run
Short Identifier=Multiple
Geom File=g01
Flow File=f01
Subcritical Flow
K Sum by GR= 0
Std Step Tol= 0.01
Critical Tol= 0.01
Num of Std Step Trials= 20
Max Error Tol= 0.3
Flow Tol Ratio= 0.001
Split Flow NTrial= 30
Split Flow Tol= 0.02
Split Flow Ratio= 0.02
Log Output Level= 0
Friction Slope Method= 1
Unsteady Friction Slope Method= 2
Unsteady Bridges Friction Slope Method= 1
Parabolic Critical Depth
Global Vel Dist=  1 , 1 , 1
Global Log Level= 0
CheckData=True
Encroach Param= -1, 0, 0, 0
BEGIN DESCRIPTION:
Multiple Run
END DESCRIPTION:

--- FLOYDS CREEK.f01 (steady flow) ---

Flow Title=Multiple
Program Version=4.10
Number of Profiles= 7
Profile Names=10-year,25-year,50-year,1pct_min,100-year,1pct_plu,500-year
River Rch & RM=FLOYDS CREEK,Reach-1         ,13233
     353     464     615     269     813    2455    1462
River Rch & RM=FLOYDS CREEK,Reach-1         ,11428
     662     900    1218     542    1638    4947    3063
River Rch & RM=FLOYDS CREEK,Reach-1         ,5478
     776    1060    1441     644    1944    5871    3657
River Rch & RM=FLOYDS CREEK,Reach-1         ,376
    4144    6045    8580    3978   12013   36279   24390
Boundary for River Rch & Prof#=FLOYDS CREEK,Reach-1         , 1
Up Type= 0
Dn Type= 3
Dn Slope=0.005
Boundary for River Rch & Prof#=FLOYDS CREEK,Reach-1         , 2
Up Type= 0
Dn Type= 3
Dn Slope=0.005
Boundary for River Rch & Prof#=FLOYDS CREEK,Reach-1         , 3
Up Type= 0
Dn Type= 3
Dn Slope=0.005
Boundary for River Rch & Prof#=FLOYDS CREEK,Reach-1         , 4
Up Type= 0
Dn Type= 3
Dn Slope=0.005
Boundary for River Rch & Prof#=FLOYDS CREEK,Reach-1         , 5
Up Type= 0
Dn Type= 3
Dn Slope=0.005
Boundary for River Rch & Prof#=FLOYDS CREEK,Reach-1         , 6
Up Type= 0
Dn Type= 3
Dn Slope=0.005
Boundary for River Rch & Prof#=FLOYDS CREEK,Reach-1         , 7
Up Type= 0
Dn Type= 3
Dn Slope=0.005
DSS Import GetInterval= 0
DSS Import GetPeak= 0
DSS Import FillOption= 0

--- FLOYDS CREEK.f02 (steady flow) ---

Flow Title=Orig_BLE_Flows
Program Version=4.10
Number of Profiles= 7
Profile Names=10-year,25-year,50-year,1pct_min,100-year,1pct_plu,500-year
River Rch & RM=FLOYDS CREEK,Reach-1         ,13233
     353     455     535     207     625    1888     850
River Rch & RM=FLOYDS CREEK,Reach-1         ,11428
     662     882    1059     417    1260    3805    1781
River Rch & RM=FLOYDS CREEK,Reach-1         ,5478
     776    1039    1253     495    1495    4515    2126
River Rch & RM=FLOYDS CREEK,Reach-1         ,376
    4144    5926    7461    3060    9241   27906   14180
Boundary for River Rch & Prof#=FLOYDS CREEK,Reach-1         , 1
Up Type= 0
Dn Type= 3
Dn Slope=0.005
Boundary for River Rch & Prof#=FLOYDS CREEK,Reach-1         , 2
Up Type= 0
Dn Type= 3
Dn Slope=0.005
Boundary for River Rch & Prof#=FLOYDS CREEK,Reach-1         , 3
Up Type= 0
Dn Type= 3
Dn Slope=0.005
Boundary for River Rch & Prof#=FLOYDS CREEK,Reach-1         , 4
Up Type= 0
Dn Type= 3
Dn Slope=0.005
Boundary for River Rch & Prof#=FLOYDS CREEK,Reach-1         , 5
Up Type= 0
Dn Type= 3
Dn Slope=0.005
Boundary for River Rch & Prof#=FLOYDS CREEK,Reach-1         , 6
Up Type= 0
Dn Type= 3
Dn Slope=0.005
Boundary for River Rch & Prof#=FLOYDS CREEK,Reach-1         , 7
Up Type= 0
Dn Type= 3
Dn Slope=0.005
DSS Import GetInterval= 0
DSS Import GetPeak= 0
DSS Import FillOption= 0

--- FLOYDS CREEK.g01 (geometry) ---

Geom Title=Existing Conditions
Program Version=4.10

River Reach=FLOYDS CREEK    ,Reach-1
Reach XY= 30
      3695453.23     10146431.84      3695773.61     10145842.17
      3696125.57     10145527.65      3696132.31     10145153.65
      3696756.76     10144525.19      3696650.25     10144193.96
      3696768.84       10143592.       3696927.2     10143413.51
      3696980.48     10142847.77      3697167.13     10142704.65
      3697048.95     10142512.01      3697386.41     10141554.32
      3697269.32     10141210.21      3697556.06     10140976.89
      3698145.31     10139662.57      3698114.46     10139541.71
      3698346.49     10139276.21      3698396.45     10139138.49
      3698238.16     10138879.54      3698370.81     10138535.87
      3698536.67     10138319.72      3698756.98     10138295.37
      3698789.69     10137944.82      3698610.89      10137686.1
       3699188.2     10137289.12      3699480.62     10137273.29
      3699686.52     10137005.19      3699734.72     10136664.42
      3699541.99     10136600.49      3699236.99     10136258.29

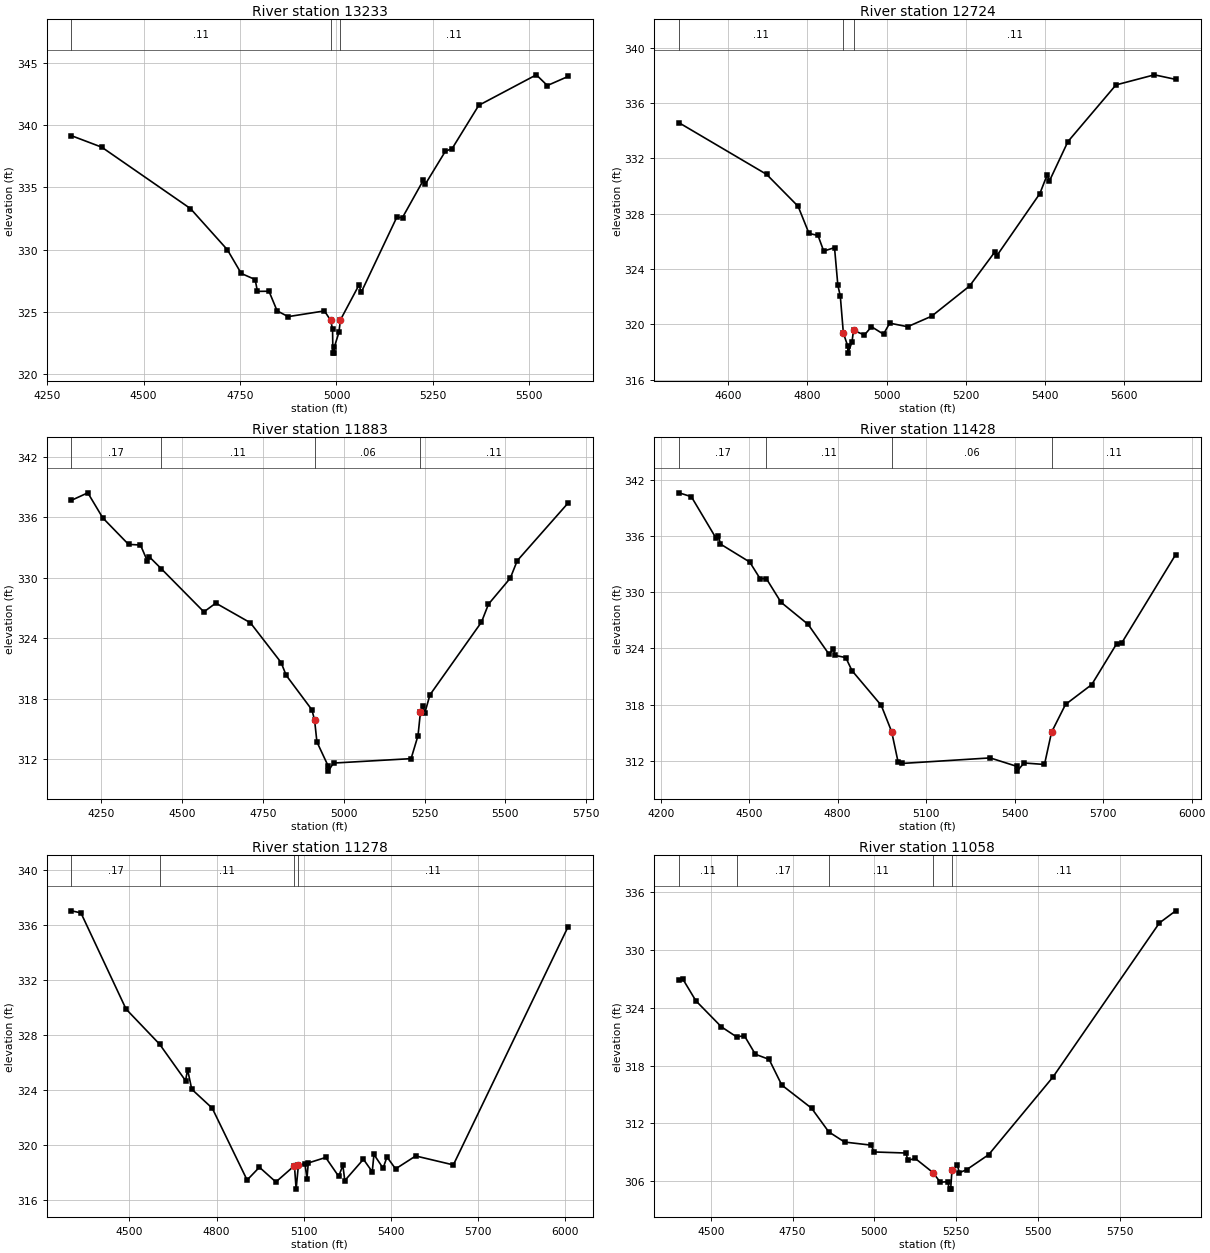
Type RM Length L Ch R = 1 ,13233   ,509,509,509
BEGIN DESCRIPTION:
FLOYDS CREEK 15.0
END DESCRIPTION:
XS GIS Cut Line= 3
      3696242.74     10146435.78      3695678.51     10146053.85
      3695127.31     10145802.12
#Sta/Elev= 30
  4313.2  339.15  4391.6  338.23  4621.5   333.3  4717.3  329.99  4753.2  328.09
  4789.2   327.6  4795.2  326.65  4825.1  326.66  4846.1  325.09  4874.6  324.62
  4968.9  325.08  4985.1324.3127  4989.9   323.6  4990.8  321.69  4994.3  321.69
  4994.6  322.19  5006.3  323.35  5010.3324.3564  5058.6  327.17  5064.1  326.57
  5156.2  332.59  5171.2  332.58  5225.3  335.58  5230.8  335.28  5282.3   337.9
  5299.9  338.12  5368.9  341.59  5518.1  344.04  5546.6  343.18  5600.5  343.91
#Mann= 3 , 0 , 0
  4313.2     .11       0  4985.1     .06       0  5010.3     .11       0
Bank Sta=4985.1,5010.3
XS Rating Curve= 0 ,0
Exp/Cntr=0.3,0.1

Type RM Length L Ch R = 1 ,12724   ,841,841,841
BEGIN DESCRIPTION:
Mapping XS 6277ce47
END DESCRIPTION:
XS GIS Cut Line= 3
      3696312.22     10146075.59      3696051.78     10145719.65
      3695248.87     10145598.13
#Sta/Elev= 30
  4476.6  334.57  4697.4  330.84  4776.9  328.53  4804.4  326.57  4827.1  326.42
  4841.5  325.29  4868.8  325.54  4877.2  322.82  4883.4  322.03  4891.1  319.36
  4902.3  318.41  4902.5  317.91  4912.8   318.7  4916.7  319.56  4944.2  319.22
  4962.1  319.82  4992.4  319.28    5008  320.08  5053.1  319.82  5113.8  320.58
  5209.4  322.76  5273.1  325.22  5278.2  324.95  5386.9  329.45  5405.7  330.83
  5410.7  330.34  5457.7  333.21    5579  337.31  5675.9  338.04  5729.7  337.71
#Mann= 3 , 0 , 0
  4476.6     .11       0  4891.1     .06       0  4916.7     .11       0
Bank Sta=4891.1,4916.7
XS Rating Curve= 0 ,0
Exp/Cntr=0.3,0.1

Type RM Length L Ch R = 1 ,11883   ,455,455,455
BEGIN DESCRIPTION:
Mapping XS ed3e2522
END DESCRIPTION:
XS GIS Cut Line= 2
      3697011.02     10145428.87      3695697.15     10144635.35
#Sta/Elev= 30
  4158.9  337.68  4209.3  338.42  4255.6  335.93  4335.2   333.3  4372.1  333.24
  4393.4  331.65  4399.3  332.07  4436.2  330.89  4568.1   326.6  4604.9  327.47
  4711.7  325.52  4806.8  321.57  4822.3  320.31  4901.9  316.88  4910.3  315.84
  4917.4  313.69  4952.3  311.29  4952.5  310.79  4968.7  311.59  5208.5  312.03
  5229.9  314.32  5237.4  316.66  5245.4  317.24  5251.2   316.6  5266.7  318.36
  5425.9  325.58  5447.7  327.37  5515.1  329.95  5536.5  331.68  5693.8  337.41
#Mann= 4 ,-1 , 0
  4158.9     .17       0  4436.2     .11       0  4910.3     .06       0
  5237.4     .11       0
Bank Sta=4910.3,5237.4
XS Rating Curve= 0 ,0
Exp/Cntr=0.3,0.1

Type RM Length L Ch R = 1 ,11428   ,150,150,150
BEGIN DESCRIPTION:
Mapping XS a667ec2b
END DESCRIPTION:
XS GIS Cut Line= 3
      3697158.57     10145168.45      3696394.66     10144473.99
      3695792.15     10144226.92
#Sta/Elev= 30
  4262.4   340.6  4303.9  340.19  4388.3  335.73  4395.8  336.04  4402.5  335.14
  4501.8  333.22    4537  331.45  4558.2  331.45  4607.9  328.93  4699.8  326.57
  4770.8  323.38    4785  323.91  4791.7  323.26  4827.5  323.03  4848.5  321.64
  4947.8  317.93    4983  315.13  5004.6  311.93  5018.8  311.74    5317  312.33
  5408.2  311.42  5408.5  310.92  5431.9  311.79  5501.1  311.63  5525.1  315.07
  5572.4  318.03  5661.3  320.15  5745.3  324.48  5762.6  324.57    5946  334.02
#Mann= 4 ,-1 , 0
  4262.4     .17       0  4558.2     .11       0    4983     .06       0
  5525.1     .11       0
Bank Sta=4983,5525.1
XS Rating Curve= 0 ,0
Exp/Cntr=0.3,0.1

Type RM Length L Ch R = 1 ,11278   ,220,220,220
BEGIN DESCRIPTION:
Mapping XS 4fd3a697
END DESCRIPTION:
XS GIS Cut Line= 6
      3697214.99     10145059.94      3696694.97     10144541.13
      3696625.53     10144491.82      3696459.76     10144387.18
      3696364.42      10144332.1      3695817.42     10144122.43
#Sta/Elev= 30
  4300.1  337.04  4332.6  336.89  4488.2   329.9  4603.8  327.35  4693.2   324.7
  4700.3   325.5  4714.5  324.08  4785.2   322.7  4905.4  317.48  4947.8  318.41
  5004.5  317.34 5068.53318.5216  5074.3  316.82  5082.1  318.54  5104.7  318.67
  5111.7  317.58  5116.2  318.72  5176.2  319.12    5221  317.75  5235.4  318.55
  5242.1  317.44  5306.3  318.99  5336.7  318.08  5342.5  319.34  5374.1  318.34
  5387.4  319.16  5417.1  318.29  5486.4  319.23  5616.2  318.58  6011.8  335.89
#Mann= 4 ,-1 , 0
  4300.1     .17       0  4603.8     .11       0 5068.53     .07       0
  5082.1     .11       0
Bank Sta=5068.53,5082.1
XS Rating Curve= 0 ,0
Exp/Cntr=0.3,0.1

Type RM Length L Ch R = 1 ,11058   ,735,735,735
BEGIN DESCRIPTION:
FLOYDS CREEK 14.0
END DESCRIPTION:
XS GIS Cut Line= 3
      3697348.69     10144287.35      3696661.15     10144386.31
      3695922.18     10144022.03
#Sta/Elev= 30
    4403  326.91  4413.9  327.01  4454.4  324.72  4532.3  322.02  4578.6  320.98
  4602.7  321.09  4636.2  319.17  4678.2  318.64    4717  315.97    4808  313.57
  4860.6  311.11    4909  310.05  4989.8  309.73  4999.9  309.02  5096.8  308.91
  5102.5  308.15    5125  308.35  5179.3  306.88  5201.6  305.88  5223.9  305.93
  5229.9  305.16  5233.4  305.16  5237.3   307.1  5254.2  307.63  5259.7  306.86
  5282.2  307.18  5349.6  308.74  5546.1   316.8  5871.6  332.81  5921.5  334.07
#Mann= 5 ,-1 , 0
    4403     .11       0  4578.6     .17       0  4860.6     .11       0
  5179.3     .07       0  5237.3     .11       0
Bank Sta=5179.3,5237.3
XS Rating Curve= 0 ,0
Exp/Cntr=0.3,0.1

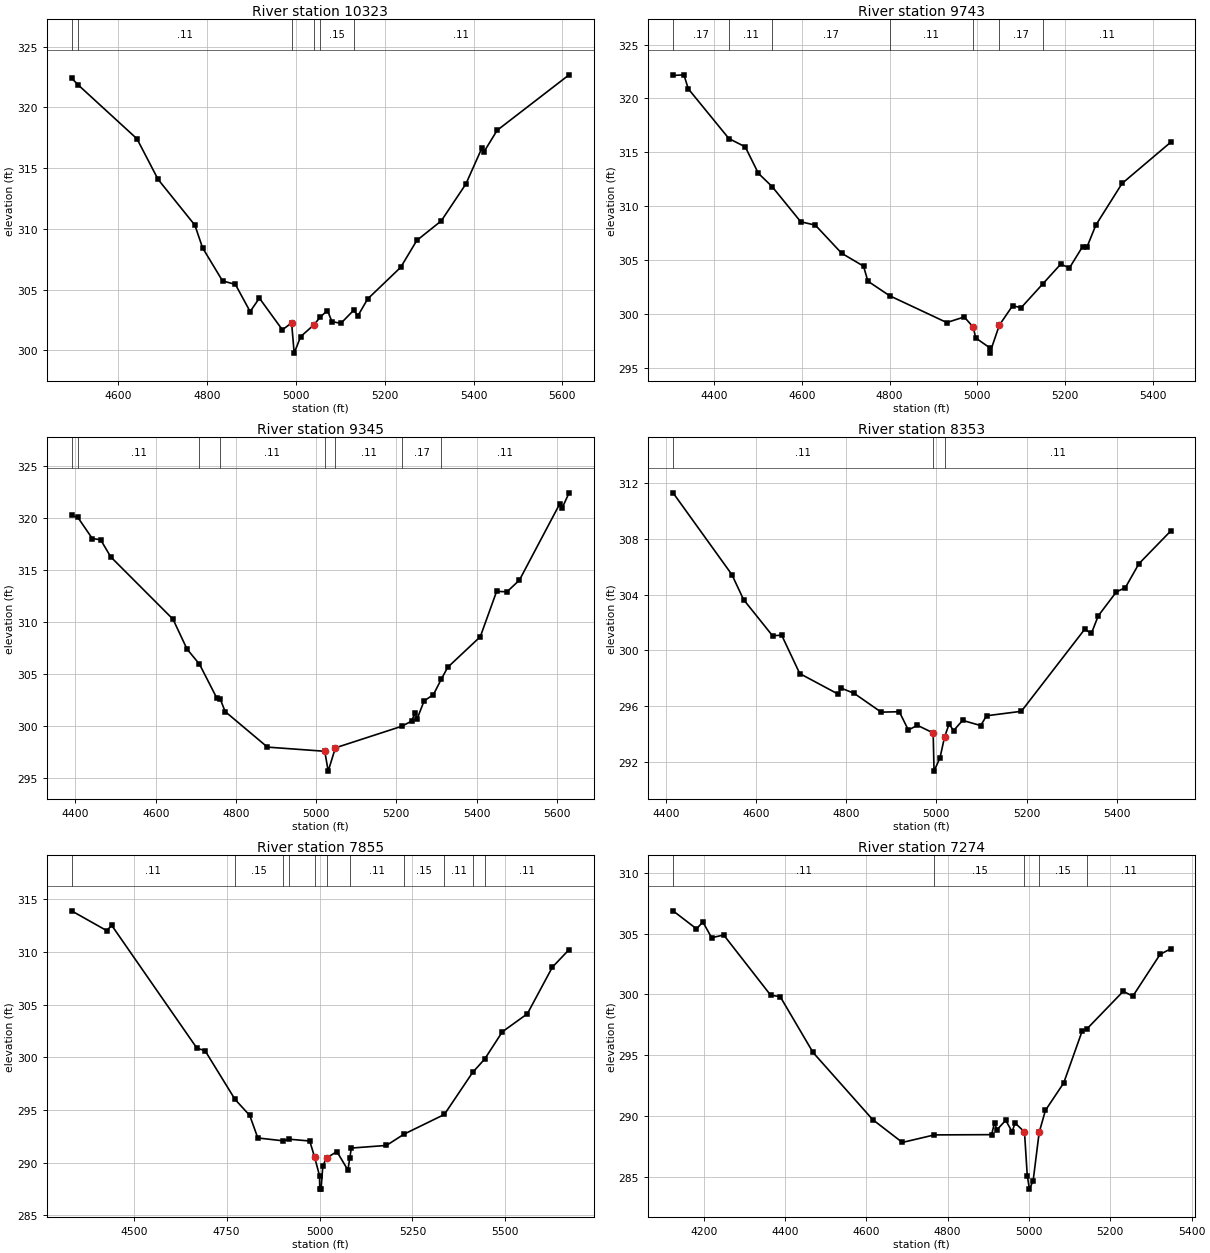
Type RM Length L Ch R = 1 ,10323   ,580,580,580
BEGIN DESCRIPTION:
FLOYDS CREEK 13.0
END DESCRIPTION:
XS GIS Cut Line= 3
      3697275.69     10143855.05       3696788.2     10143720.58
      3696176.73     10143787.36
#Sta/Elev= 30
  4494.3  322.42  4509.8  321.84  4641.7  317.42  4689.2  314.08  4772.1  310.31
  4789.5  308.44  4834.4  305.72  4863.4  305.43  4896.6  303.19  4917.4   304.3
  4969.2  301.69    4990  302.26  4995.8  299.77  5010.4  301.13  5040.6  302.11
  5054.4  302.74  5070.8  303.28  5080.8  302.37  5100.9  302.22  5129.8   303.3
  5139.4  302.85  5161.3  304.23  5235.8  306.84    5272  309.05  5327.1  310.66
  5382.6   313.7  5418.4  316.64  5423.4  316.35    5453  318.12  5615.1  322.69
#Mann= 6 ,-1 , 0
  4494.3     .15       0  4509.8     .11       0    4990     .07       0
  5040.6     .11       0  5054.4     .15       0  5129.8     .11       0
Bank Sta=4990,5040.6
XS Rating Curve= 0 ,0
Exp/Cntr=0.3,0.1

Type RM Length L Ch R = 1 ,9743    ,398,398,398
BEGIN DESCRIPTION:
FLOYDS CREEK 12.0
END DESCRIPTION:
XS GIS Cut Line= 3
       3697572.6     10143240.48       3696879.9     10143230.06
      3696437.15     10143214.44
#Sta/Elev= 30
  4305.5  322.13  4330.3  322.19  4340.3  320.89    4433  316.27  4470.3   315.5
  4500.3  313.04  4531.6  311.81    4597  308.54  4630.3  308.23  4690.3  305.62
  4740.3  304.42  4750.3  303.02  4799.9  301.67  4930.3  299.18  4970.3   299.7
  4990.3  298.77  4996.8  297.74  5028.3  296.84  5028.6  296.34  5050.4  298.94
  5080.4  300.73  5100.4  300.57  5149.3  302.76  5190.4   304.6  5210.5  304.26
  5240.5  306.24  5250.5   306.2  5270.5  308.22  5330.5   312.1  5441.3  315.92
#Mann= 7 ,-1 , 0
  4305.5     .17       0    4433     .11       0  4531.6     .17       0
  4799.9     .11       0  4990.3     .07       0  5050.4     .17       0
  5149.3     .11       0
Bank Sta=4990.3,5050.4
XS Rating Curve= 0 ,0
Exp/Cntr=0.3,0.1

Type RM Length L Ch R = 1 ,9345    ,992,992,992
BEGIN DESCRIPTION:
FLOYDS CREEK 11.0
END DESCRIPTION:
XS GIS Cut Line= 3
      3697567.89     10143011.08      3696978.68     10142853.95
      3696367.87     10143011.07
#Sta/Elev= 30
  4390.2  320.23  4405.8  320.04    4442     318  4462.7  317.89  4487.9  316.24
  4643.2  310.24  4678.1  307.37  4709.1  305.92  4752.5  302.65  4760.6  302.59
  4773.2  301.36  4878.6  297.94  5021.5  297.54  5030.1  295.63    5048  297.87
  5213.9  299.95  5238.3  300.45  5246.4  301.25  5251.6  300.64  5269.3  302.39
  5292.3  302.98  5311.9  304.46  5327.9  305.61  5409.3  308.56    5450  312.92
  5475.8  312.88  5506.8     314  5607.8  321.37  5612.9   320.9  5630.7   322.4
#Mann= 8 ,-1 , 0
  4390.2     .17       0  4405.8     .11       0  4709.1     .17       0
  4760.6     .11       0  5021.5     .07       0    5048     .11       0
  5213.9     .17       0  5311.9     .11       0
Bank Sta=5021.5,5048
XS Rating Curve= 0 ,0
Exp/Cntr=0.3,0.1

Type RM Length L Ch R = 1 ,8353    ,498,498,498
BEGIN DESCRIPTION:
FLOYDS CREEK 10.0
END DESCRIPTION:
XS GIS Cut Line= 3
      3697767.85     10142111.07      3697185.81     10142166.76
       3696667.8     10142211.08
#Sta/Elev= 30
  4415.3  311.28  4545.9  305.43  4571.9  303.64  4636.3  301.05  4656.4   301.1
  4696.6  298.35  4782.4  296.87  4787.4  297.32  4817.1  296.94  4877.4  295.59
  4917.6  295.62  4937.7  294.31  4957.8  294.65  4992.8   294.1  4994.7  291.37
    5008  292.33    5018   293.8  5028.1  294.74  5038.1  294.27  5058.2     295
  5098.3  294.63  5111.3  295.33  5188.6  295.65  5329.2  301.52    5344  301.22
  5359.3  302.48  5399.4  304.19  5419.5   304.5  5449.6  306.21  5519.9  308.54
#Mann= 3 ,-1 , 0
  4415.3     .11       0  4992.8     .07       0    5018     .11       0
Bank Sta=4992.8,5018
XS Rating Curve= 0 ,0
Exp/Cntr=0.3,0.1

Type RM Length L Ch R = 1 ,7855    ,581,581,581
BEGIN DESCRIPTION:
FLOYDS CREEK 9.0
END DESCRIPTION:
XS GIS Cut Line= 3
       3697926.8     10141985.28       3697315.9     10141716.79
      3696717.81     10141411.05
#Sta/Elev= 30
  4332.7  313.91  4427.3  312.03  4440.8  312.53  4670.2  300.86    4692  300.63
  4772.7     296  4812.2  294.48    4834  292.34  4901.3  292.07  4918.8  292.22
  4973.7  292.05  4986.9  290.51    5000  288.76  5000.7  287.48  5004.2  287.48
    5009   289.7  5019.1  290.45  5046.9  291.04  5076.4  289.29  5081.3  290.39
  5085.7  291.38  5180.2  291.63  5227.4   292.7    5336  294.57    5412  298.56
  5444.7  299.84    5492  302.42  5559.3  304.13  5626.7  308.56  5671.7  310.23
#Mann= 11 ,-1 , 0
  4332.7     .11       0  4772.7     .15       0  4901.3     .11       0
  4918.8     .15       0  4986.9     .09       0  5019.1     .15       0
  5081.3     .11       0  5227.4     .15       0    5336     .11       0
    5412     .15       0  5444.7     .11       0
Bank Sta=4986.9,5019.1
XS Rating Curve= 0 ,0
Exp/Cntr=0.3,0.1

Type RM Length L Ch R = 1 ,7274    ,394,394,394
BEGIN DESCRIPTION:
FLOYDS CREEK 8.0
END DESCRIPTION:
XS GIS Cut Line= 3
      3698025.76      10141683.2      3697270.53     10141245.69
      3696922.21     10141287.28
#Sta/Elev= 30
  4124.6  306.88  4182.2   305.4    4198  305.96  4219.5  304.67  4249.3  304.89
  4364.9  299.93    4388  299.83  4468.9  295.23  4615.5  289.71  4688.5  287.83
  4767.3  288.45    4908  288.47  4915.3  289.46  4921.1  288.87  4942.7  289.65
  4958.4  288.71  4965.8  289.43  4988.9  288.69  4995.7   285.1  5001.1  283.99
  5010.2  284.69 5024.99288.6535  5040.4  290.47  5085.3  292.72    5131  297.02
  5141.9  297.15  5231.7  300.26  5255.3  299.86  5322.4   303.3  5348.2  303.75
#Mann= 5 ,-1 , 0
  4124.6     .11       0  4767.3     .15       0  4988.9     .09       0
 5024.99     .15       0  5141.9     .11       0
Bank Sta=4988.9,5024.99
XS Rating Curve= 0 ,0
Exp/Cntr=0.3,0.1

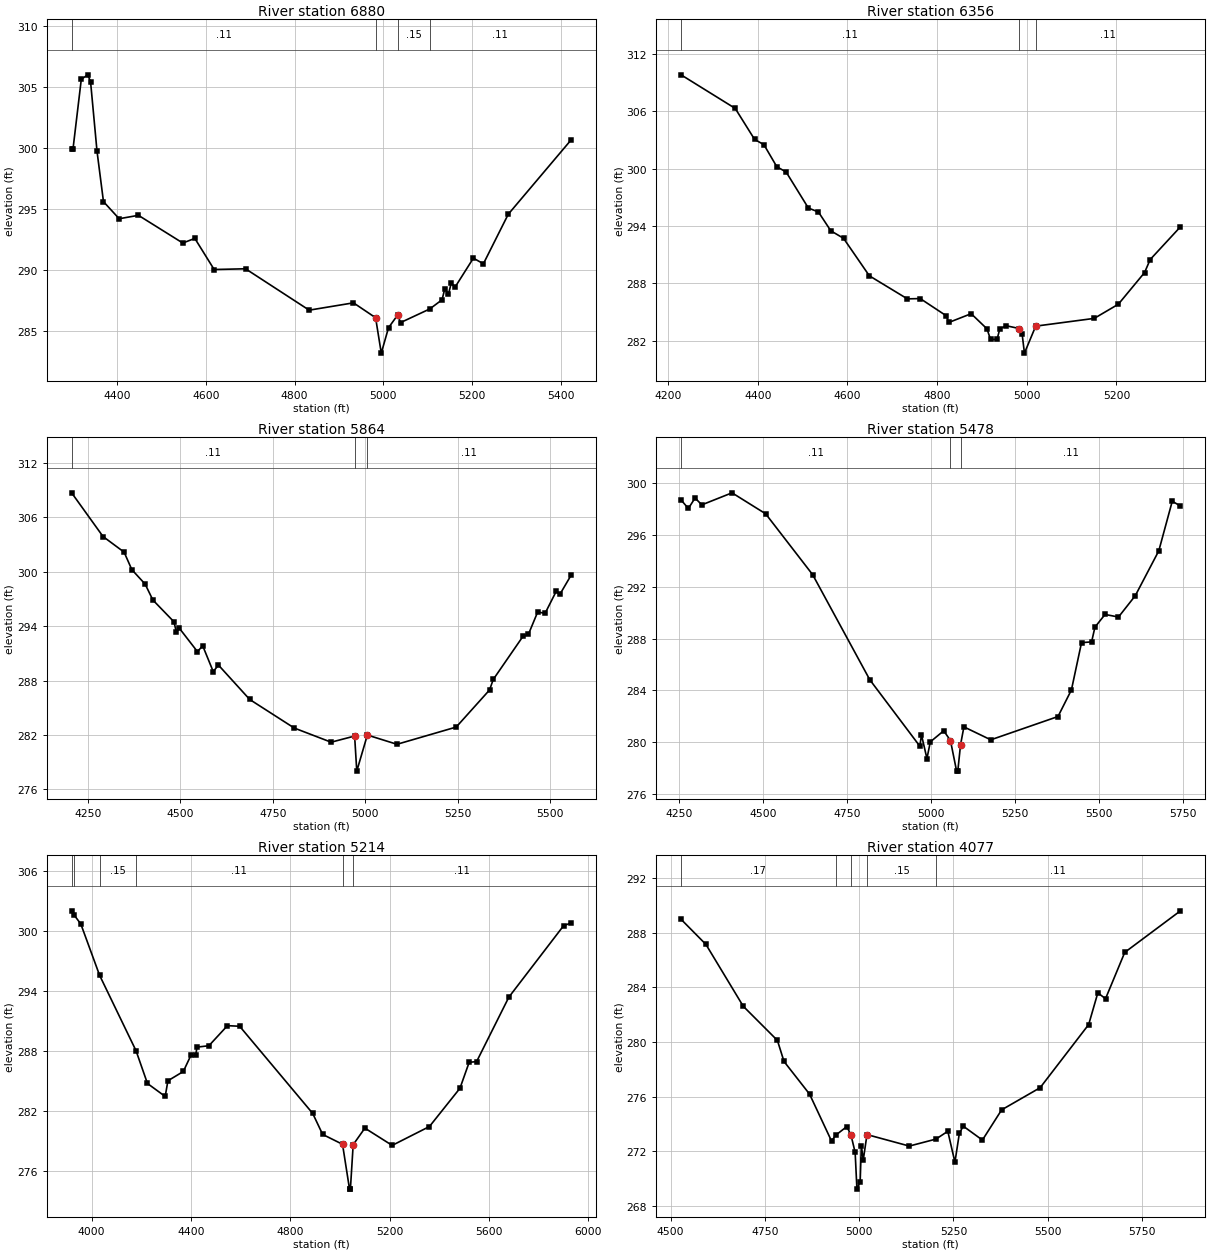
Type RM Length L Ch R = 1 ,6880    ,524,524,524
BEGIN DESCRIPTION:
FLOYDS CREEK 7.0
END DESCRIPTION:
XS GIS Cut Line= 3
      3698067.86     10141461.08      3697367.17     10140930.18
      3697172.44     10140778.07
#Sta/Elev= 30
  4297.4  299.94  4300.6  299.94  4319.2  305.62  4333.8  305.98  4340.1  305.41
  4354.6  299.73  4369.2  295.59  4404.6  294.19    4448  294.47  4548.1   292.2
  4575.2  292.58  4618.8  290.03  4689.6  290.09  4833.1   286.7    4933   287.3
  4982.9  286.08  4995.7  283.18    5012  285.26  5032.8  286.31  5039.1  285.68
  5105.1   286.8  5132.7  287.55    5139  288.45  5147.2  288.02  5153.5  288.92
  5161.8  288.57  5203.4  290.96    5226   290.5  5282.1  294.56  5423.6  300.64
#Mann= 4 ,-1 , 0
  4297.4     .11       0  4982.9     .06       0  5032.8     .15       0
  5105.1     .11       0
Bank Sta=4982.9,5032.8
XS Rating Curve= 0 ,0
Exp/Cntr=0.3,0.1

Type RM Length L Ch R = 1 ,6356    ,492,492,492
BEGIN DESCRIPTION:
FLOYDS CREEK 6.0
END DESCRIPTION:
XS GIS Cut Line= 3
      3698317.87     10141061.09      3697717.71     10140577.26
      3697417.88     10140411.09
#Sta/Elev= 30
  4229.1  309.79  4349.9  306.28  4393.1  303.04  4413.9  302.49  4442.6  300.19
  4463.5  299.63    4513  295.87  4535.4  295.46  4563.1  293.49  4591.4  292.71
    4649  288.79  4733.8  286.38  4762.5  286.41    4820  284.63  4826.5  283.92
  4876.1  284.83  4911.3  283.25  4919.3  282.14  4933.7  282.14  4940.1  283.26
  4954.5  283.57  4983.3  283.28  4989.7  282.71  4994.9  280.71    5020  283.53
  5150.5  284.34  5204.3  285.82  5262.8  289.13  5275.3  290.49  5342.8  293.91
#Mann= 3 , 0 , 0
  4229.1     .11       0  4983.3     .06       0    5020     .11       0
Bank Sta=4983.3,5020
XS Rating Curve= 0 ,0
Exp/Cntr=0.3,0.1

Type RM Length L Ch R = 1 ,5864    ,386,386,386
BEGIN DESCRIPTION:
FLOYDS CREEK 5.0
END DESCRIPTION:
XS GIS Cut Line= 3
      3698517.86     10140661.08      3697923.43     10140135.15
      3697367.85     10140111.07
#Sta/Elev= 30
  4206.3  308.71  4291.2  303.89  4348.1  302.17    4369  300.24    4405  298.64
  4425.9  296.89  4482.8  294.49  4489.4  293.35    4497   293.8  4546.3   291.2
  4560.6  291.84    4589     289  4603.2  289.71  4687.7  285.92  4808.1  282.77
  4907.7  281.21  4971.2  281.89    4977  278.02  5005.6     282  5085.7  280.98
  5245.8  282.88  5335.9  286.97  5345.9  288.13    5426  292.87  5440.8  293.09
    5466  295.57    5486  295.42  5516.1  297.85  5526.1  297.52  5556.1  299.61
#Mann= 3 , 0 , 0
  4206.3     .11       0  4971.2     .06       0  5005.6     .11       0
Bank Sta=4971.2,5005.6
XS Rating Curve= 0 ,0
Exp/Cntr=0.3,0.1

Type RM Length L Ch R = 1 ,5478    ,264,264,264
BEGIN DESCRIPTION:
FLOYDS CREEK 4.0
END DESCRIPTION:
XS GIS Cut Line= 3
      3698829.53     10139792.56      3698065.67     10139785.62
      3697343.46     10139785.62
#Sta/Elev= 30
  4256.3  298.72    4278  298.06    4298  298.87    4318  298.34    4408  299.27
    4508  297.65    4648  292.94    4818  284.82  4966.8  279.69  4971.8  280.55
    4988  278.73    4998  280.02    5038  280.88    5058  280.12  5076.3  277.76
  5079.8  277.76    5088   279.8    5098  281.18    5178  280.18    5378  281.98
    5418  284.04    5448  287.69    5478  287.75    5488  288.89    5518  289.87
    5558  289.67    5608  291.32    5678  294.79    5718  298.62  5742.4  298.25
#Mann= 3 , 0 , 0
  4256.3     .11       0    5058     .06       0    5088     .11       0
Bank Sta=5058,5088
XS Rating Curve= 0 ,0
Exp/Cntr=0.3,0.1

Type RM Length L Ch R = 1 ,5214    ,1137,1137,1137
BEGIN DESCRIPTION:
FLOYDS CREEK 3.0
END DESCRIPTION:
XS GIS Cut Line= 3
      3699183.72     10139362.01      3698392.06      10139563.4
      3697197.66     10139535.62
#Sta/Elev= 30
  3919.4  302.02  3929.1  301.61  3956.4   300.7  4031.9  295.57  4178.8  288.01
  4224.8  284.73  4296.3  283.43  4307.2     285  4369.2  285.93  4400.1  287.56
  4419.1  287.54  4424.3  288.37  4472.3  288.51    4547  290.52  4596.2  290.46
  4890.5  281.73  4930.5  279.63  5010.6  278.64  5038.8  274.15  5042.3  274.15
  5053.5   278.6  5100.6  280.26  5210.6  278.53  5360.7  280.42  5483.6  284.25
  5520.7  286.85  5550.7  286.92  5680.7  293.38  5900.8  300.52    5931  300.81
#Mann= 6 ,-1 , 0
  3919.4     .11       0  3929.1     .17       0  4031.9     .15       0
  4178.8     .11       0  5010.6     .07       0  5053.5     .11       0
Bank Sta=5010.6,5053.5
XS Rating Curve= 0 ,0
Exp/Cntr=0.3,0.1

Type RM Length L Ch R = 1 ,4077    ,1030,1030,1030
BEGIN DESCRIPTION:
FLOYDS CREEK 2.0
END DESCRIPTION:
XS GIS Cut Line= 3
      3698767.84     10138861.07      3698338.34     10138664.84
      3697503.15     10138834.24
#Sta/Elev= 30
  4527.8  288.98  4593.8  287.14  4692.7  282.62  4783.3  280.12  4800.8  278.58
  4868.6  276.19    4927  272.75  4937.7  273.18  4967.5  273.82  4978.6  273.18
  4989.5  271.92  4994.2  269.24  5002.8  269.78  5005.9  272.42    5011  271.38
  5020.9  273.23  5133.1  272.39  5203.7   272.9  5235.2  273.47  5254.1  271.21
  5265.8  273.31    5276  273.85    5327  272.83    5378  275.04  5480.1  276.66
  5608.8  281.28  5633.1   283.6  5653.5  283.17  5704.5  286.56  5852.2   289.6
#Mann= 5 ,-1 , 0
  4527.8     .17       0  4937.7     .15       0  4978.6     .09       0
  5020.9     .15       0  5203.7     .11       0
Bank Sta=4978.6,5020.9
XS Rating Curve= 0 ,0
Exp/Cntr=0.3,0.1

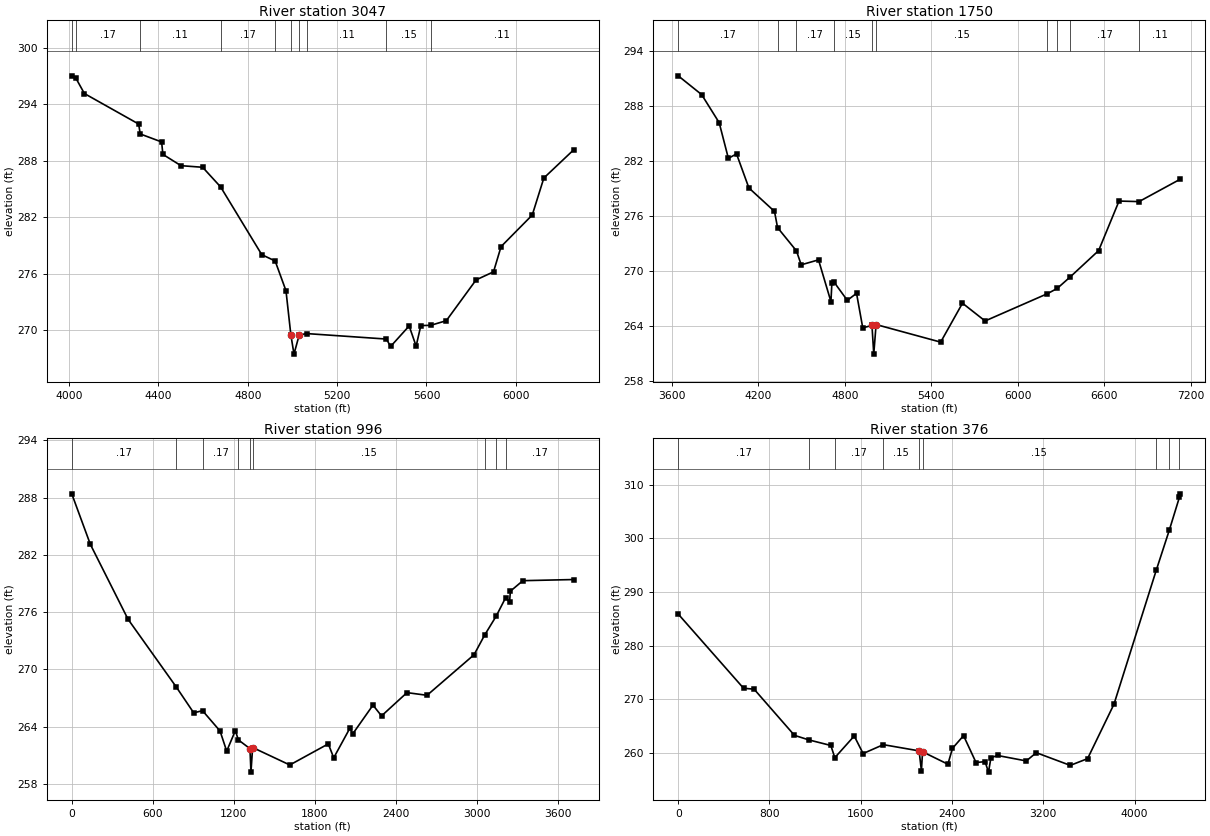
Type RM Length L Ch R = 1 ,3047    ,1297,1297,1297
BEGIN DESCRIPTION:
Mapping XS 5802aa8a
END DESCRIPTION:
XS GIS Cut Line= 3
       3699621.2     10138584.22      3698655.95     10138042.56
      3697558.73     10138355.06
#Sta/Elev= 30
  4012.2  297.03  4031.1  296.76  4068.7  295.15  4311.7  291.91  4318.5  290.86
  4414.4  290.01  4420.1  288.69  4501.1  287.49  4598.1  287.32  4678.7  285.23
  4862.8  278.04  4922.7  277.37  4971.2  274.21  4992.9  269.55    5007  267.48
  5030.5  269.53    5065  269.66  5420.9  269.08  5439.4  268.29  5522.6  270.47
  5553.8  268.33  5574.9  270.51  5619.1  270.54  5688.9  271.03  5822.2  275.36
  5900.3  276.22  5934.1   278.9  6073.7  282.25  6125.6  286.18  6259.9  289.19
#Mann= 10 ,-1 , 0
  4012.2     .11       0  4031.1     .17       0  4318.5     .11       0
  4678.7     .17       0  4922.7     .15       0  4992.9     .09       0
  5030.5     .15       0    5065     .11       0  5420.9     .15       0
  5619.1     .11       0
Bank Sta=4992.9,5030.5
XS Rating Curve= 0 ,0
Exp/Cntr=0.3,0.1

Type RM Length L Ch R = 1 ,1750    ,754,754,754
BEGIN DESCRIPTION:
FLOYDS CREEK 1.0
END DESCRIPTION:
XS GIS Cut Line= 3
      3700093.47     10138334.26      3698871.22     10136834.23
      3697865.01     10138006.99
#Sta/Elev= 30
  3645.9  291.33  3808.2  289.28  3929.6  286.22  3993.5  282.32  4049.9  282.81
  4135.7  279.09  4313.1  276.53  4334.4  274.76  4465.4  272.22  4498.3   270.7
  4618.2  271.24  4704.4  266.68  4710.9  268.72  4727.3  268.78  4817.9  266.82
  4881.8  267.59  4924.9  263.82  4988.8  264.08  5001.2  260.95  5017.3  264.18
  5464.9  262.26  5616.2  266.51  5772.9  264.57  6205.2  267.55  6272.6  268.12
  6363.9  269.39  6559.8  272.25  6701.3  277.66  6840.1   277.6  7126.1  280.05
#Mann= 10 ,-1 , 0
  3645.9     .17       0  4334.4     .11       0  4465.4     .17       0
  4727.3     .15       0  4988.8     .06       0  5017.3     .15       0
  6205.2     .17       0  6272.6     .15       0  6363.9     .17       0
  6840.1     .11       0
Bank Sta=4988.8,5017.3
XS Rating Curve= 0 ,0
Exp/Cntr=0.3,0.1

Type RM Length L Ch R = 1 ,996     ,620,620,620
BEGIN DESCRIPTION:
FLOYDS CREEK 0.5
END DESCRIPTION:
XS GIS Cut Line= 4
      3700496.84     10137942.69      3699715.59     10136854.14
      3698767.68     10136791.64       3697845.8     10137880.19
#Sta/Elev= 30
       0  288.39   137.4   283.1   416.4  275.25     775  268.12   902.7  265.44
   967.8  265.67  1097.5  263.54  1146.7  261.43  1210.9  263.58  1232.9  262.61
    1319  261.69  1326.3  259.23  1338.7  261.81  1613.9  259.98  1898.8  262.19
  1938.9  260.73  2059.2  263.85  2079.2  263.23  2229.5  266.25  2292.8  265.12
  2481.1  267.56  2629.8  267.28  2977.6  271.53  3055.6  273.58  3140.9  275.56
  3211.6  277.51  3240.2  277.04  3246.7  278.19    3339  279.29  3716.3  279.41
#Mann= 9 ,-1 , 0
       0     .17       0     775     .11       0   967.8     .17       0
  1232.9     .15       0    1319     .06       0  1338.7     .15       0
  3055.6     .17       0  3140.9     .15       0  3211.6     .17       0
Bank Sta=1319,1338.7
XS Rating Curve= 0 ,0
Exp/Cntr=0.3,0.1

Type RM Length L Ch R = 1 ,376     ,0,0,0
BEGIN DESCRIPTION:
FLOYDS CREEK 0.1
END DESCRIPTION:
XS GIS Cut Line= 4
      3701007.26     10137781.23      3699545.46     10136441.82
      3699077.57     10136505.19      3698038.51     10134859.35
#Sta/Elev= 30
       0  285.87   572.9  272.01   664.8  271.85  1018.7  263.22  1146.3  262.36
  1337.5  261.33  1372.6  259.05  1542.8   263.1  1620.5  259.82  1797.5  261.48
  2111.4  260.32  2131.6  256.61  2141.7  260.15  2363.7  257.83  2404.1   260.8
  2501.1  263.16  2610.5  258.14  2689.4  258.31  2719.8  256.35  2741.1  259.04
  2798.8  259.46    3051  258.44  3138.8  259.98  3436.5  257.61  3588.3  258.87
  3819.7  269.04  4189.6  294.01  4304.9  301.56  4393.1  307.67  4401.2  308.33
#Mann= 9 ,-1 , 0
       0     .17       0  1146.3     .11       0  1372.6     .17       0
  1797.5     .15       0  2111.4     .06       0  2141.7     .15       0
  4189.6     .17       0  4304.9     .15       0  4393.1     .17       0
Bank Sta=2111.4,2141.7
XS Rating Curve= 0 ,0
Exp/Cntr=0.3,0.1

Chan Stop Cuts=-1
Use User Specified Reach Order=0
Composite Channel Slope=5