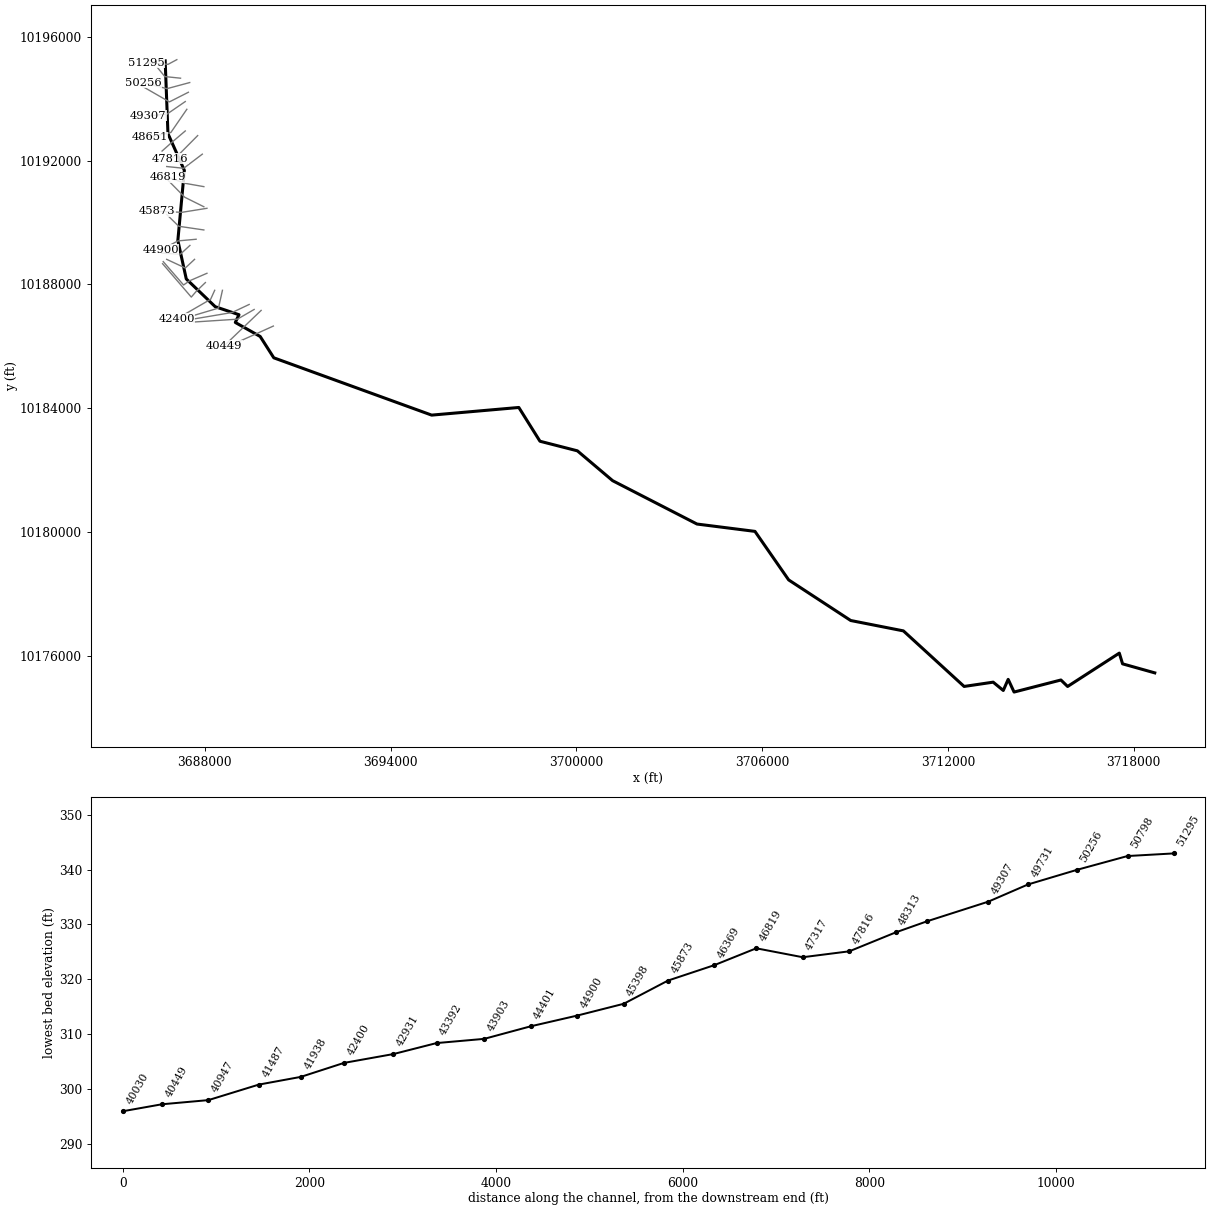
--- GARRETTS CREEK.prj (project) ---

Proj Title=GARRETTS CREEK Base Level Engineering
Current Plan=p01
Default Exp/Contr=0.3,0.1
English Units
Geom File=g01
Flow File=f01
Flow File=f02
Plan File=p01
Y Axis Title=Elevation
X Axis Title(PF)=Main Channel Distance
X Axis Title(XS)=Station
BEGIN DESCRIPTION:
GARRETTS CREEK
END DESCRIPTION:
DSS Export Rating Curves= 0
DSS Export Rating Curve Sorted= 0
DSS Export Volume Flow Curves= 0
DXF OffsetX= 0
DXF OffsetY= 0
DXF ScaleX= 1
DXF ScaleY= 10

--- GARRETTS CREEK.p01 (plan) ---

Plan Title=Multiple Run
Short Identifier=Multiple
Geom File=g01
Flow File=f01
Subcritical Flow
K Sum by GR= 0
Std Step Tol= 0.01
Critical Tol= 0.01
Num of Std Step Trials= 20
Max Error Tol= 0.3
Flow Tol Ratio= 0.001
Split Flow NTrial= 30
Split Flow Tol= 0.02
Split Flow Ratio= 0.02
Log Output Level= 0
Friction Slope Method= 1
Unsteady Friction Slope Method= 2
Unsteady Bridges Friction Slope Method= 1
Parabolic Critical Depth
Global Vel Dist=  1 , 1 , 1
Global Log Level= 0
CheckData=True
Encroach Param= -1, 0, 0, 0
BEGIN DESCRIPTION:
Multiple Run
END DESCRIPTION:

--- GARRETTS CREEK.f01 (steady flow) ---

Flow Title=Multiple
Program Version=4.10
Number of Profiles= 7
Profile Names=10-year,25-year,50-year,1pct_min,100-year,1pct_plu,500-year
River Rch & RM=GARRETTS CREEK,Reach-1         ,51295
     680     930    1265     566    1710    5164    3230
River Rch & RM=GARRETTS CREEK,Reach-1         ,45873
     813    1123    1538     692    2090    6312    3996
River Rch & RM=GARRETTS CREEK,Reach-1         ,42400
    1827    2616    3669    1685    5088   15366   10145
River Rch & RM=GARRETTS CREEK,Reach-1         ,40449
    2456    3545    4993    2302    6951   20992   13958
River Rch & RM=GARRETTS CREEK,Reach-1         ,37470
    2652    3824    5385    2481    7491   22622   15016
River Rch & RM=GARRETTS CREEK,Reach-1         ,34868
    2963    4308    6101    2826    8533   25769   17295
River Rch & RM=GARRETTS CREEK,Reach-1         ,32054
    2921    4220    5949    2742    8280   25005   16620
River Rch & RM=GARRETTS CREEK,Reach-1         ,27361
    2782    3996    5611    2575    7775   23480   15477
River Rch & RM=GARRETTS CREEK,Reach-1         ,25653
    3269    4738    6694    3091    9334   28188   18806
River Rch & RM=GARRETTS CREEK,Reach-1         ,24408
    4900    7204   10281    4791   14469   43696   29685
River Rch & RM=GARRETTS CREEK,Reach-1         ,20261
    4923    7257   10376    4844   14630   44182   30133
River Rch & RM=GARRETTS CREEK,Reach-1         ,18703
    4959    7275   10366    4824   14567   43992   29785
River Rch & RM=GARRETTS CREEK,Reach-1         ,14483
    5696    8390   11989    5592   16888   51001   34703
River Rch & RM=GARRETTS CREEK,Reach-1         ,13483
    5387    7885   11216    5207   15726   47492   32014
River Rch & RM=GARRETTS CREEK,Reach-1         ,11622
    6214    9189   13168    6159   18599   56168   38421
River Rch & RM=GARRETTS CREEK,Reach-1         ,6076
    6239    9215   13192    6163   18613   56210   38371
River Rch & RM=GARRETTS CREEK,Reach-1         ,3891
    5562    8111   11509    5329   16093   48600   32573
Boundary for River Rch & Prof#=GARRETTS CREEK,Reach-1         , 1
Up Type= 0
Dn Type= 3
Dn Slope=0.001
Boundary for River Rch & Prof#=GARRETTS CREEK,Reach-1         , 2
Up Type= 0
Dn Type= 3
Dn Slope=0.001
Boundary for River Rch & Prof#=GARRETTS CREEK,Reach-1         , 3
Up Type= 0
Dn Type= 3
Dn Slope=0.001
Boundary for River Rch & Prof#=GARRETTS CREEK,Reach-1         , 4
Up Type= 0
Dn Type= 3
Dn Slope=0.001
Boundary for River Rch & Prof#=GARRETTS CREEK,Reach-1         , 5
Up Type= 0
Dn Type= 3
Dn Slope=0.001
Boundary for River Rch & Prof#=GARRETTS CREEK,Reach-1         , 6
Up Type= 0
Dn Type= 3
Dn Slope=0.001
Boundary for River Rch & Prof#=GARRETTS CREEK,Reach-1         , 7
Up Type= 0
Dn Type= 3
Dn Slope=0.001
DSS Import GetInterval= 0
DSS Import GetPeak= 0
DSS Import FillOption= 0

--- GARRETTS CREEK.f02 (steady flow) ---

Flow Title=Orig_BLE_Flows
Program Version=4.10
Number of Profiles= 7
Profile Names=10-year,25-year,50-year,1pct_min,100-year,1pct_plu,500-year
River Rch & RM=GARRETTS CREEK,Reach-1         ,51295
     680     912    1100     436    1315    3972    1878
River Rch & RM=GARRETTS CREEK,Reach-1         ,45873
     813    1101    1337     532    1608    4855    2323
River Rch & RM=GARRETTS CREEK,Reach-1         ,42400
    1827    2565    3190    1296    3914   11821    5898
River Rch & RM=GARRETTS CREEK,Reach-1         ,40449
    2456    3475    4342    1771    5347   16147    8115
River Rch & RM=GARRETTS CREEK,Reach-1         ,37470
    2652    3749    4683    1908    5762   17401    8730
River Rch & RM=GARRETTS CREEK,Reach-1         ,34868
    2963    4224    5305    2173    6564   19822   10055
River Rch & RM=GARRETTS CREEK,Reach-1         ,32054
    2921    4137    5173    2109    6369   19235    9663
River Rch & RM=GARRETTS CREEK,Reach-1         ,27361
    2782    3918    4879    1981    5981   18063    8998
River Rch & RM=GARRETTS CREEK,Reach-1         ,25653
    3269    4645    5821    2378    7180   21684   10934
River Rch & RM=GARRETTS CREEK,Reach-1         ,24408
    4900    7063    8940    3686   11130   33613   17259
River Rch & RM=GARRETTS CREEK,Reach-1         ,20261
    4923    7115    9023    3727   11254   33987   17519
River Rch & RM=GARRETTS CREEK,Reach-1         ,18703
    4959    7132    9014    3710   11205   33837   17317
River Rch & RM=GARRETTS CREEK,Reach-1         ,14483
    5696    8225   10425    4302   12991   39233   20176
River Rch & RM=GARRETTS CREEK,Reach-1         ,13483
    5387    7730    9753    4006   12097   36533   18613
River Rch & RM=GARRETTS CREEK,Reach-1         ,11622
    6214    9009   11450    4737   14307   43205   22338
River Rch & RM=GARRETTS CREEK,Reach-1         ,6076
    6239    9034   11471    4741   14318   43240   22309
River Rch & RM=GARRETTS CREEK,Reach-1         ,3891
    5562    7952   10008    4099   12379   37384   18938
Boundary for River Rch & Prof#=GARRETTS CREEK,Reach-1         , 1
Up Type= 0
Dn Type= 3
Dn Slope=0.001
Boundary for River Rch & Prof#=GARRETTS CREEK,Reach-1         , 2
Up Type= 0
Dn Type= 3
Dn Slope=0.001
Boundary for River Rch & Prof#=GARRETTS CREEK,Reach-1         , 3
Up Type= 0
Dn Type= 3
Dn Slope=0.001
Boundary for River Rch & Prof#=GARRETTS CREEK,Reach-1         , 4
Up Type= 0
Dn Type= 3
Dn Slope=0.001
Boundary for River Rch & Prof#=GARRETTS CREEK,Reach-1         , 5
Up Type= 0
Dn Type= 3
Dn Slope=0.001
Boundary for River Rch & Prof#=GARRETTS CREEK,Reach-1         , 6
Up Type= 0
Dn Type= 3
Dn Slope=0.001
Boundary for River Rch & Prof#=GARRETTS CREEK,Reach-1         , 7
Up Type= 0
Dn Type= 3
Dn Slope=0.001
DSS Import GetInterval= 0
DSS Import GetPeak= 0
DSS Import FillOption= 0

--- GARRETTS CREEK.g01 (geometry) ---

Geom Title=Existing Conditions
Program Version=4.10

River Reach=GARRETTS CREEK  ,Reach-1
Reach XY= 30
      3686718.23     10195226.84      3686808.54     10192873.78
      3687338.13     10191686.86      3687127.93     10189422.43
       3687399.9     10188177.66      3688335.01     10187280.93
      3689101.85     10187022.24      3688983.28     10186771.89
      3689786.73     10186318.56      3690226.66     10185628.96
      3695324.33     10183777.15      3698139.75     10184024.17
      3698822.78     10182932.77      3700030.52     10182623.18
      3701169.77     10181658.11      3703893.62     10180256.92
      3705765.91     10180019.71      3706854.28      10178451.4
      3708859.08     10177138.94       3710559.9     10176803.87
      3712520.77     10175008.35       3713459.4     10175146.77
      3713785.26     10174878.28      3713943.76     10175237.33
      3714134.47     10174827.14      3715647.19     10175216.79
      3715863.25     10175007.27       3717532.6     10176085.42
      3717638.16     10175738.92      3718678.23     10175446.84

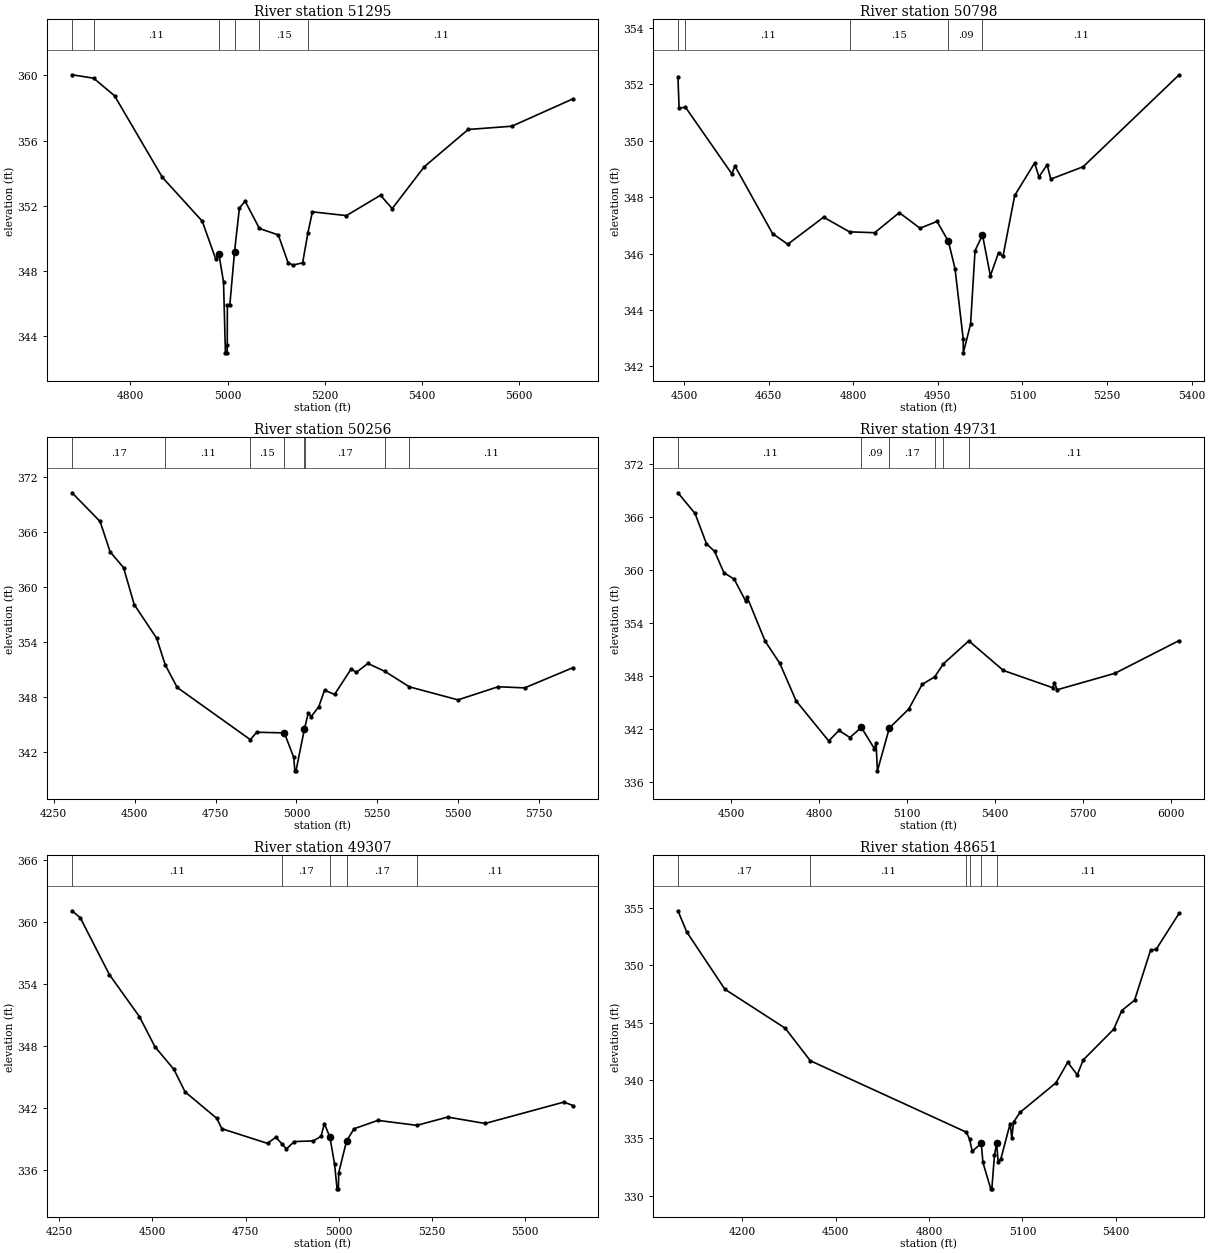
Type RM Length L Ch R = 1 ,51295   ,497,497,497
BEGIN DESCRIPTION:
GARRETTS CREEK 88.0
END DESCRIPTION:
XS GIS Cut Line= 3
      3687094.88     10195264.81      3686812.23     10195113.93
      3686101.46     10195160.55
#Sta/Elev= 30
  4679.6  360.04  4724.1  359.83  4767.2  358.75  4865.7  353.74  4947.8  351.05
  4975.4  348.74  4982.3  349.01  4991.7  347.31  4995.6  342.96  4999.1  342.96
  4999.4  343.46  4999.6  345.91  5004.7  345.91  5014.4  349.18  5024.4  351.85
  5036.1  352.28  5065.6   350.6  5104.6   350.2  5124.6   348.5  5134.7  348.35
  5154.7  348.49  5165.5  350.33  5174.8  351.62  5244.9  351.39  5315.1  352.64
  5339.2  351.82  5405.2  354.39  5495.8  356.68  5585.6  356.88  5712.3  358.57
#Mann= 6 ,-1 , 0
  4679.6     .15       0  4724.1     .11       0  4982.3     .07       0
  5014.4     .11       0  5065.6     .15       0  5165.5     .11       0
Bank Sta=4982.3,5014.4
XS Rating Curve= 0 ,0
Exp/Cntr=0.3,0.1

Type RM Length L Ch R = 1 ,50798   ,542,542,542
BEGIN DESCRIPTION:
GARRETTS CREEK 87.0
END DESCRIPTION:
XS GIS Cut Line= 3
       3687214.7     10194665.84      3686706.82     10194718.43
      3686467.86     10195011.06
#Sta/Elev= 30
  4489.4  352.27  4491.5  351.16  4502.8  351.19  4585.2  348.82  4590.3  349.11
  4657.1  346.71  4684.1  346.33  4747.6  347.29  4793.6  346.77  4838.1  346.74
  4881.7  347.45  4918.5   346.9  4948.7  347.14  4968.8  346.43  4980.5  345.47
    4995  342.98  4995.2  342.48  5008.1   343.5    5016   346.1  5029.2  346.66
  5043.2  345.21  5057.6  346.03  5065.5   345.9  5086.3  348.06  5121.5  349.21
  5129.4  348.72  5143.8  349.15  5150.2  348.64  5207.7  349.08  5377.8  352.34
#Mann= 5 ,-1 , 0
  4489.4     .17       0  4502.8     .11       0  4793.6     .15       0
  4968.8     .09       0  5029.2     .11       0
Bank Sta=4968.8,5029.2
XS Rating Curve= 0 ,0
Exp/Cntr=0.3,0.1

Type RM Length L Ch R = 1 ,50256   ,525,525,525
BEGIN DESCRIPTION:
GARRETTS CREEK 86.0
END DESCRIPTION:
XS GIS Cut Line= 3
      3687511.53     10194525.22      3686777.16      10194327.3
      3686012.19     10194519.85
#Sta/Elev= 30
  4306.5  370.29  4393.2  367.16  4424.2  363.85  4465.7  362.13  4498.6   358.1
  4568.1  354.42  4594.6  351.52  4631.4  349.06  4857.6  343.36  4877.2  344.17
  4962.8   344.1  4991.8  341.42  4995.2  339.96  4998.7  339.96  5024.9  344.53
  5025.6  344.63  5036.9  346.29  5045.6  345.87  5069.3  346.96    5087  348.76
  5117.9  348.29  5169.5  351.09  5184.9  350.69  5220.9  351.67  5273.1  350.82
  5349.4  349.12  5499.5   347.7  5623.2  349.13  5705.7  349.01  5855.9  351.23
#Mann= 8 ,-1 , 0
  4306.5     .17       0  4594.6     .11       0  4857.6     .15       0
  4962.8     .09       0  5024.9     .15       0  5025.6     .17       0
  5273.1     .15       0  5349.4     .11       0
Bank Sta=4962.8,5024.9
XS Rating Curve= 0 ,0
Exp/Cntr=0.3,0.1

Type RM Length L Ch R = 1 ,49731   ,424,424,424
BEGIN DESCRIPTION:
GARRETTS CREEK 85.0
END DESCRIPTION:
XS GIS Cut Line= 3
      3687467.89     10194211.09      3686855.28     10193900.22
      3685967.88     10194411.06
#Sta/Elev= 30
  4317.6  368.76  4376.1  366.42    4415     363  4442.9  362.12  4474.6  359.72
  4509.7  358.98  4548.6  356.52  4554.2  356.92  4615.4  351.96  4665.5  349.45
  4721.1   345.2  4832.4  340.67  4867.1  341.86  4904.8  341.06  4943.7  342.21
  4988.2   339.8  4993.9  340.42  4998.6  337.29  5039.2  342.13  5105.4  344.28
  5151.2  347.07  5194.1  347.93  5223.5  349.39  5310.6     352  5428.5  348.65
  5596.7   346.7  5602.5  347.25  5612.5  346.47  5809.3  348.33  6028.5  352.04
#Mann= 6 ,-1 , 0
  4317.6     .11       0  4943.7     .09       0  5039.2     .17       0
  5194.1     .11       0  5223.5     .17       0  5310.6     .11       0
Bank Sta=4943.7,5039.2
XS Rating Curve= 0 ,0
Exp/Cntr=0.3,0.1

Type RM Length L Ch R = 1 ,49307   ,656,656,656
BEGIN DESCRIPTION:
GARRETTS CREEK 84.0
END DESCRIPTION:
XS GIS Cut Line= 3
      3687367.84     10193911.06      3686778.36     10193505.71
       3686152.5     10193447.13
#Sta/Elev= 30
  4284.6  361.09  4306.9   360.4  4384.7  354.91  4465.2  350.84  4507.1  347.91
  4557.9  345.72  4587.7  343.55  4672.9  340.98  4686.4  339.98  4808.9  338.56
  4830.7  339.16  4847.5  338.52  4859.6  338.03  4880.6  338.74  4931.3   338.8
  4952.3  339.25  4961.1  340.48    4976  339.17  4988.5  336.56  4995.2  334.16
  4998.7  334.16  4999.7  335.73  5020.6  338.78  5040.7  339.98  5104.7  340.79
  5208.9  340.31  5291.8  341.11  5392.2  340.49  5603.1  342.56  5628.6  342.22
#Mann= 5 ,-1 , 0
  4284.6     .11       0  4847.5     .17       0    4976     .09       0
  5020.6     .17       0  5208.9     .11       0
Bank Sta=4976,5020.6
XS Rating Curve= 0 ,0
Exp/Cntr=0.3,0.1

Type RM Length L Ch R = 1 ,48651   ,338,338,338
BEGIN DESCRIPTION:
GARRETTS CREEK 83.0
END DESCRIPTION:
XS GIS Cut Line= 3
      3687417.87     10193661.09      3686902.16     10192910.64
      3686217.88     10192761.08
#Sta/Elev= 30
  3992.9  354.72  4021.3  352.88  4143.8  347.91    4338  344.52  4418.4   341.7
  4919.7   335.5  4930.4   334.9  4938.6  333.84  4967.9  334.52  4973.1  332.88
  4998.3  330.58  5001.8  330.58  5010.2  333.49  5016.9  334.53  5022.1  332.95
  5030.7  333.17  5060.8  336.25  5065.9     335  5071.7  336.37  5092.1  337.21
  5207.8  339.78  5245.7  341.57  5276.4  340.47  5295.6  341.77  5393.6  344.44
  5419.7  346.06  5460.6  346.96  5511.8  351.28  5530.4  351.39  5603.9  354.51
#Mann= 6 ,-1 , 0
  3992.9     .17       0  4418.4     .11       0  4919.7     .15       0
  4930.4     .11       0  4967.9     .06       0  5016.9     .11       0
Bank Sta=4967.9,5016.9
XS Rating Curve= 0 ,0
Exp/Cntr=0.3,0.1

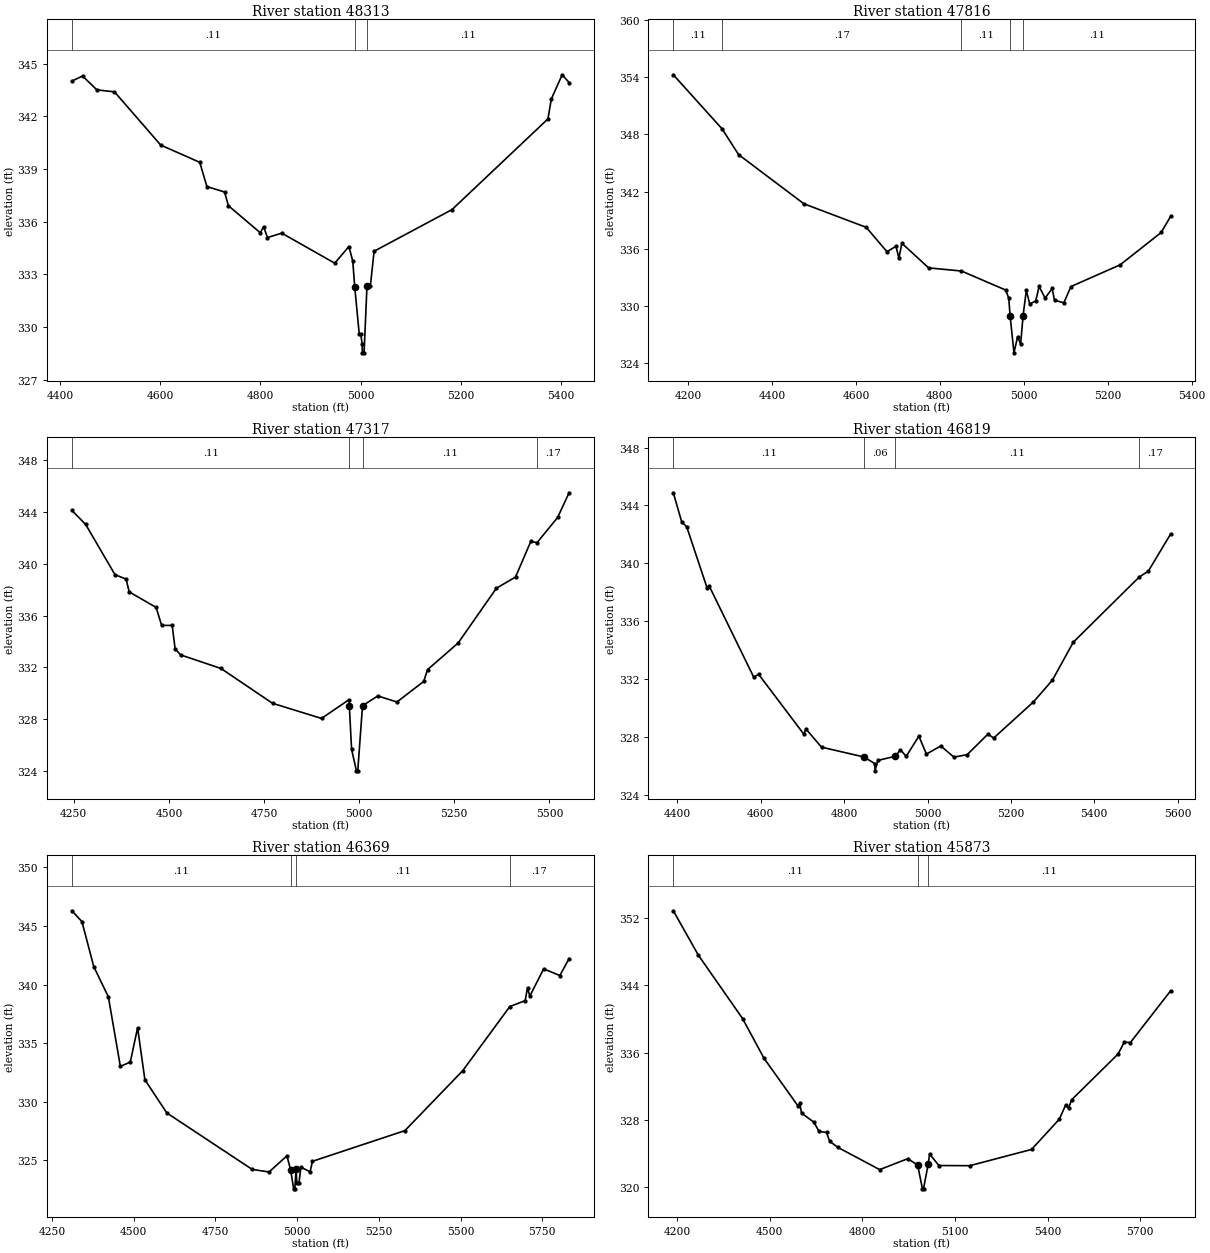
Type RM Length L Ch R = 1 ,48313   ,497,497,497
BEGIN DESCRIPTION:
GARRETTS CREEK 82.0
END DESCRIPTION:
XS GIS Cut Line= 3
      3687367.83     10192961.06      3686928.42     10192587.87
      3686617.87     10192311.08
#Sta/Elev= 30
  4423.5     344  4444.9  344.29  4473.5   343.5  4508.6  343.39  4600.9  340.36
  4678.8  339.38  4693.1     338  4728.3  337.69    4736  336.91  4799.7  335.37
  4806.2  335.72    4814   335.1  4842.5  335.35  4948.3  333.64  4976.5  334.59
  4984.2  333.76 4988.07332.3059  4997.1  329.62    5000  329.62  5003.1  329.04
  5003.3  328.54  5006.8  328.54  5012.6  332.35  5019.3  332.34  5026.8  334.32
  5182.3  336.69  5373.8  341.85  5380.5  342.98  5402.2  344.36    5416  343.92
#Mann= 3 , 0 , 0
  4423.5     .11       0 4988.07     .06       0  5012.6     .11       0
Bank Sta=4988.07,5012.6
XS Rating Curve= 0 ,0
Exp/Cntr=0.3,0.1

Type RM Length L Ch R = 1 ,47816   ,499,499,499
BEGIN DESCRIPTION:
GARRETTS CREEK 81.0
END DESCRIPTION:
XS GIS Cut Line= 3
      3687767.86     10192811.08      3687180.36     10192217.71
      3686867.83     10192061.06
#Sta/Elev= 30
    4165  354.25  4281.3  348.57  4320.5  345.88  4476.1  340.72  4624.6  338.25
  4674.1  335.69  4695.4  336.27  4702.4  335.02  4709.5  336.58  4773.1     334
  4851.4  333.67    4957  331.67  4964.1  330.81 4967.44328.9301  4976.5  325.09
  4985.2  326.78  4992.4  325.99  4998.2  328.98    5006  331.65    5014  330.21
  5028.4  330.53  5036.4  332.05  5050.7  330.83  5067.5  331.84  5073.1   330.6
  5095.4  330.34  5112.2  332.04  5229.5  334.32  5327.2  337.71  5349.6   339.4
#Mann= 5 ,-1 , 0
    4165     .11       0  4281.3     .17       0  4851.4     .11       0
 4967.44     .06       0  4998.2     .11       0
Bank Sta=4967.44,4998.2
XS Rating Curve= 0 ,0
Exp/Cntr=0.3,0.1

Type RM Length L Ch R = 1 ,47317   ,498,498,498
BEGIN DESCRIPTION:
GARRETTS CREEK 80.0
END DESCRIPTION:
XS GIS Cut Line= 3
      3687917.85     10192211.07      3687316.57      10191754.3
       3686767.8     10191811.08
#Sta/Elev= 30
  4244.9  344.14  4281.3  343.05  4358.3  339.17  4387.4  338.83  4395.6  337.84
  4466.4  336.64  4480.9  335.25  4508.6  335.25  4516.3  333.44  4530.8  332.97
  4636.9  331.92  4772.3  329.23  4901.1  328.06  4973.3  329.51 4974.17329.0186
  4980.1  325.67  4992.8  324.01  4996.3  324.01  5008.8  329.04    5049   329.8
  5099.3  329.33  5169.6  330.92  5179.7  331.83  5260.1  333.89  5360.6  338.12
  5410.9  338.99  5451.1  341.74  5467.6  341.65  5521.5  343.59  5551.7   345.5
#Mann= 4 ,-1 , 0
  4244.9     .11       0 4974.17     .06       0  5008.8     .11       0
  5467.6     .17       0
Bank Sta=4974.17,5008.8
XS Rating Curve= 0 ,0
Exp/Cntr=0.3,0.1

Type RM Length L Ch R = 1 ,46819   ,450,450,450
BEGIN DESCRIPTION:
GARRETTS CREEK 79.0
END DESCRIPTION:
XS GIS Cut Line= 3
      3687967.81     10191161.08       3687367.5     10191267.13
      3686817.82     10191461.08
#Sta/Elev= 30
  4390.4  344.88  4410.7  342.85  4422.5  342.53  4471.5  338.29  4476.6  338.42
  4583.3  332.12    4595  332.32  4703.3  328.18  4708.4  328.54  4745.8  327.28
  4847.3   326.6  4873.8  326.14  4874.1  325.64  4880.9  326.36  4922.9  326.65
    4935   327.1  4948.9  326.64  4979.3  328.04  4997.3   326.8  5031.8  327.36
  5063.3  326.59  5095.1  326.76  5144.9  328.18  5158.7  327.91  5254.1  330.41
  5299.6  331.92  5349.6  334.54  5507.3  339.04  5529.8  339.47  5582.9  342.02
#Mann= 4 ,-1 , 0
  4390.4     .11       0  4847.3     .06       0  4922.9     .11       0
  5507.3     .17       0
Bank Sta=4847.3,4922.9
XS Rating Curve= 0 ,0
Exp/Cntr=0.3,0.1

Type RM Length L Ch R = 1 ,46369   ,496,496,496
BEGIN DESCRIPTION:
GARRETTS CREEK 78.0
END DESCRIPTION:
XS GIS Cut Line= 3
      3687967.88     10190511.06      3687351.24     10190817.98
      3686767.87     10191411.05
#Sta/Elev= 30
  4311.2   346.3    4342  345.38  4378.3  341.53  4422.9  338.95  4459.6  333.01
    4490  333.39  4512.3  336.31  4534.6  331.87  4601.7  329.04  4862.6  324.22
  4914.4     324    4969  325.38 4980.18324.1891  4989.6  322.56  4993.1  322.56
    4997  324.23  4999.1  323.06  5005.7  323.06  5011.7  324.41  5039.9  324.01
    5047  324.91  5329.8  327.53  5506.7  332.65  5650.5  338.12  5697.6  338.63
  5704.7  339.73  5711.7  339.01  5754.1  341.34  5803.7  340.77  5831.9  342.22
#Mann= 4 ,-1 , 0
  4311.2     .11       0 4980.18     .06       0    4997     .11       0
  5650.5     .17       0
Bank Sta=4980.18,4997
XS Rating Curve= 0 ,0
Exp/Cntr=0.3,0.1

Type RM Length L Ch R = 1 ,45873   ,475,475,475
BEGIN DESCRIPTION:
GARRETTS CREEK 77.0
END DESCRIPTION:
XS GIS Cut Line= 3
       3688067.9     10190461.08      3687265.88     10190332.24
       3686467.8     10190361.07
#Sta/Elev= 30
  4187.7  352.91  4268.8  347.62    4412  340.06  4481.5  335.32  4592.7  329.58
  4597.7  329.93    4603  328.78  4643.5  327.69  4659.7  326.59    4684  326.48
  4694.2  325.42  4721.6  324.68  4856.2  322.04  4947.4  323.35  4979.3  322.58
  4994.7  319.75  4998.2  319.75 5013.18322.6565    5018   323.9  5048.1  322.53
  5148.1  322.51  5348.3  324.45  5438.3  328.06  5458.3  329.71  5468.3   329.4
  5478.3  330.38  5628.4  335.82  5648.5  337.24  5668.5   337.2  5798.6  343.36
#Mann= 3 , 0 , 0
  4187.7     .11       0  4979.3     .06       0 5013.18     .11       0
Bank Sta=4979.3,5013.18
XS Rating Curve= 0 ,0
Exp/Cntr=0.3,0.1

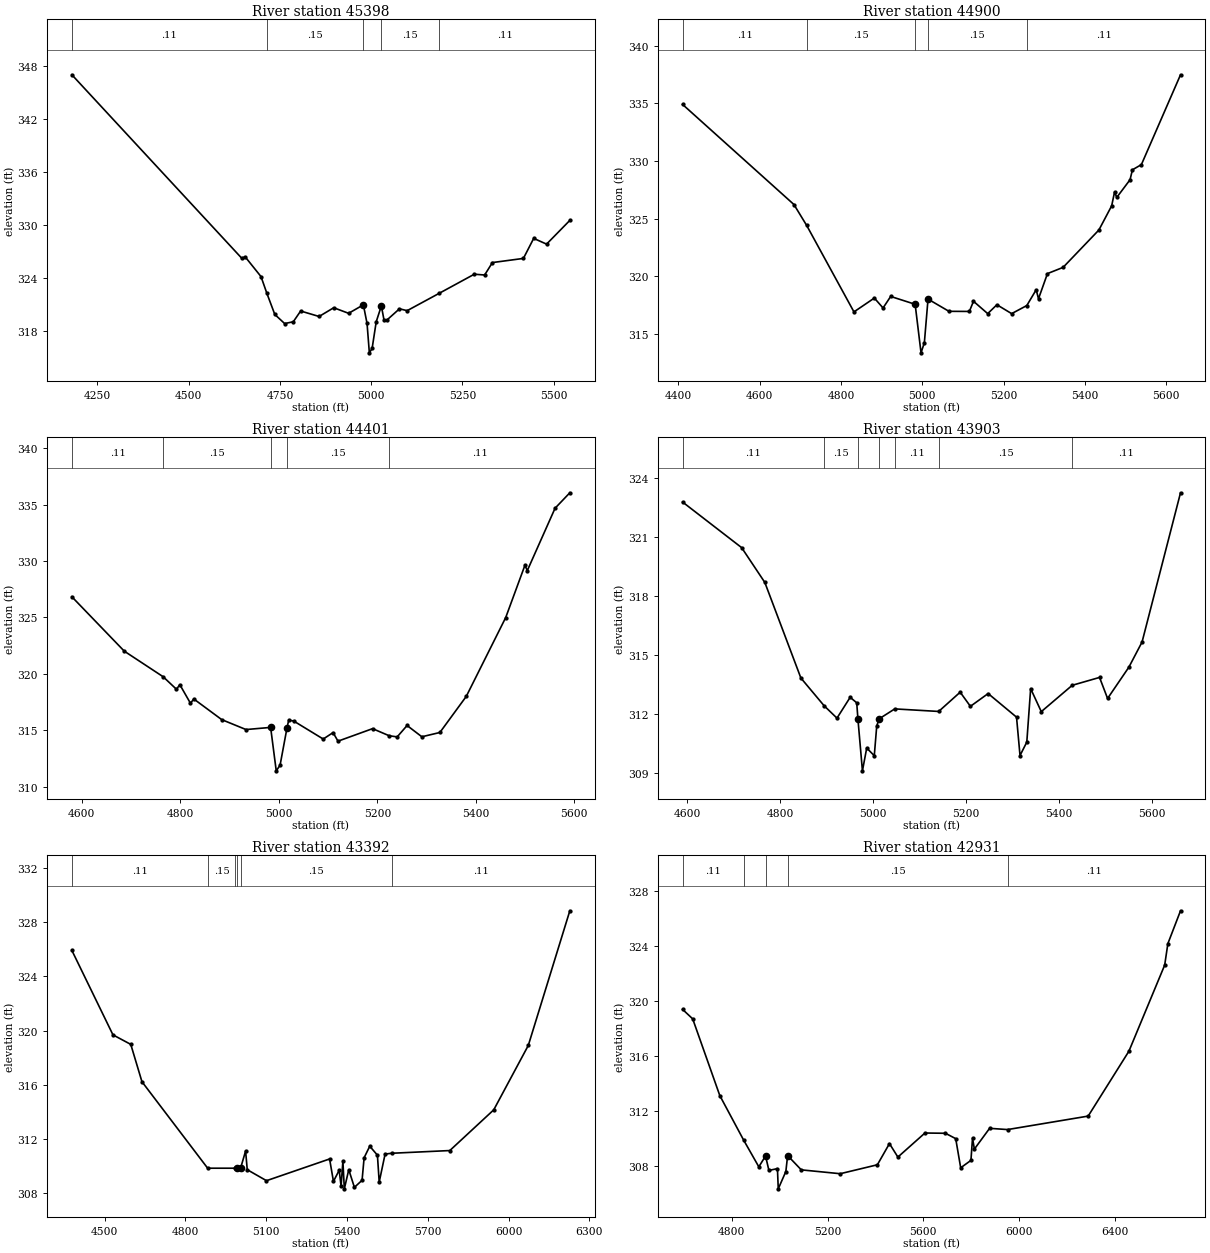
Type RM Length L Ch R = 1 ,45398   ,498,498,498
BEGIN DESCRIPTION:
GARRETTS CREEK 76.0
END DESCRIPTION:
XS GIS Cut Line= 3
      3687967.86     10189761.07      3687156.77      10189880.3
      3686767.84     10190261.08
#Sta/Elev= 30
  4180.2  347.02  4645.1  326.25  4655.3  326.37  4698.3  324.15  4714.5  322.24
  4736.1  319.86    4763  318.83  4786.7  319.03  4806.9  320.25  4857.4  319.63
  4897.5  320.62  4938.3  319.99  4978.7  320.95  4988.8  318.84  4995.1  315.51
  5002.7  316.01  5013.9  319.03    5028  320.83  5035.2  319.24  5042.2  319.19
  5077.6   320.5  5098.7  320.29  5187.1  322.27  5282.6  324.42  5310.9  324.33
  5332.2  325.74  5417.1  326.21  5445.3  328.48  5480.6  327.83  5544.3  330.52
#Mann= 5 ,-1 , 0
  4180.2     .11       0  4714.5     .15       0  4978.7     .09       0
    5028     .15       0  5187.1     .11       0
Bank Sta=4978.7,5028
XS Rating Curve= 0 ,0
Exp/Cntr=0.3,0.1

Type RM Length L Ch R = 1 ,44900   ,499,499,499
BEGIN DESCRIPTION:
GARRETTS CREEK 75.0
END DESCRIPTION:
XS GIS Cut Line= 3
      3687717.87     10189461.07      3687130.36     10189406.85
      3686567.89     10189111.09
#Sta/Elev= 30
    4410   334.9  4684.1  326.22  4715.4  324.41  4831.8  316.91    4882  318.11
  4903.4  317.25  4922.2  318.25  4982.4  317.57  4996.9  313.36  5005.1  314.24
  5014.1  318.02  5065.6  316.96  5115.8  316.95    5126  317.83    5161  316.76
  5183.6  317.53  5219.9  316.76  5257.2  317.46  5280.3  318.83    5286  318.05
    5308  320.23  5346.5  320.77  5434.6  324.01  5466.1  326.11  5473.1   327.3
  5478.7  326.84  5511.3  328.37  5517.1  329.23  5539.2  329.68  5635.5  337.47
#Mann= 5 ,-1 , 0
    4410     .11       0  4715.4     .15       0  4982.4     .09       0
  5014.1     .15       0  5257.2     .11       0
Bank Sta=4982.4,5014.1
XS Rating Curve= 0 ,0
Exp/Cntr=0.3,0.1

Type RM Length L Ch R = 1 ,44401   ,498,498,498
BEGIN DESCRIPTION:
GARRETTS CREEK 74.0
END DESCRIPTION:
XS GIS Cut Line= 3
      3687517.84     10189261.06      3687207.79     10188977.29
      3686617.86     10189011.07
#Sta/Elev= 30
  4579.7  326.83  4686.1  322.01  4765.1  319.74  4792.1  318.63  4798.9  319.04
  4820.5  317.39  4827.3  317.77    4884  315.94  4933.3  315.06  4983.3  315.25
  4994.7   311.4  5002.5   311.9 5016.64315.2281    5020  315.89    5030  315.82
  5090.1  314.22  5110.1  314.79  5120.1  314.03  5190.3  315.14  5224.1  314.51
  5240.3  314.41  5260.4  315.42  5290.4  314.42    5327   314.8  5380.6     318
  5460.7  324.99  5499.6  329.61  5504.6  329.16  5560.9  334.68  5590.9  336.05
#Mann= 5 ,-1 , 0
  4579.7     .11       0  4765.1     .15       0  4983.3     .09       0
 5016.64     .15       0  5224.1     .11       0
Bank Sta=4983.3,5016.64
XS Rating Curve= 0 ,0
Exp/Cntr=0.3,0.1

Type RM Length L Ch R = 1 ,43903   ,511,511,511
BEGIN DESCRIPTION:
GARRETTS CREEK 73.0
END DESCRIPTION:
XS GIS Cut Line= 3
      3687667.83     10188811.05      3687368.09     10188531.59
      3686767.86     10188811.07
#Sta/Elev= 30
  4590.2  322.78  4717.4  320.46  4767.3  318.69  4844.9  313.83  4894.9  312.42
  4922.6  311.79    4951  312.85  4965.1  312.57 4967.75311.7249  4977.4  309.11
  4986.6  310.27  5002.9  309.88  5008.2   311.4  5013.7  311.76    5047  312.26
  5141.5  312.13  5187.8  313.11  5209.8  312.39    5248  313.04  5309.1  311.84
  5316.6  309.89  5331.2  310.57  5339.5  313.29  5362.4  312.12    5429  313.46
  5487.8  313.86  5505.1  312.79  5550.9  314.38  5579.3  315.66  5662.1  323.25
#Mann= 7 ,-1 , 0
  4590.2     .11       0  4894.9     .15       0 4967.75     .09       0
  5013.7     .15       0    5047     .11       0  5141.5     .15       0
    5429     .11       0
Bank Sta=4967.75,5013.7
XS Rating Curve= 0 ,0
Exp/Cntr=0.3,0.1

Type RM Length L Ch R = 1 ,43392   ,461,461,461
BEGIN DESCRIPTION:
GARRETTS CREEK 72.0
END DESCRIPTION:
XS GIS Cut Line= 4
      3688067.87     10188361.08      3687508.93     10188118.97
      3687312.35     10187982.31      3686655.92     10188737.43
#Sta/Elev= 30
  4378.2   325.9  4530.8  319.68  4596.9  318.98  4638.4  316.23  4882.4  309.86
  4985.2  309.86  4989.9  309.86 5004.69  309.86  5023.3  311.13  5029.4  309.75
  5100.9  308.94  5335.2  310.54  5349.5  308.89  5370.9  309.71  5377.9  308.53
  5384.6  310.38  5389.9  308.34  5406.4  309.75  5427.3  308.45  5455.8  308.97
  5463.4  310.63  5484.3  311.48  5512.8  310.82  5519.4  308.84  5541.3   310.9
  5565.4  310.96  5781.6  311.16  5944.8  314.16    6073   318.9  6227.3  328.82
#Mann= 6 ,-1 , 0
  4378.2     .11       0  4882.4     .15       0  4985.2     .12       0
  4989.9     .09       0 5004.69     .15       0  5565.4     .11       0
Bank Sta=4989.9,5004.69
XS Rating Curve= 0 ,0
Exp/Cntr=0.3,0.1

Type RM Length L Ch R = 1 ,42931   ,531,531,531
BEGIN DESCRIPTION:
GARRETTS CREEK 71.0
END DESCRIPTION:
XS GIS Cut Line= 4
      3688017.82     10188061.04      3687725.12     10187780.69
      3687561.85     10187591.49       3686633.9     10188671.08
#Sta/Elev= 30
  4594.7  319.39    4637   318.7  4750.2  313.12  4849.5  309.89  4913.1  307.94
  4941.1  308.73  4955.2  307.68  4990.8  307.81  4994.2  306.34  5025.9   307.6
  5033.3  308.76  5090.3  307.72  5252.9  307.44    5408  308.09  5458.4  309.63
  5493.6  308.65  5606.6   310.4  5692.2  310.38    5735  309.99  5755.8  307.87
  5798.6  308.41  5805.2  310.03  5812.9  309.23  5876.5  310.74  5951.5  310.65
    6288  311.63  6458.1  316.35  6607.4  322.61  6620.7  324.17  6673.5  326.56
#Mann= 5 ,-1 , 0
  4594.7     .11       0  4849.5     .15       0  4941.1     .09       0
  5033.3     .15       0  5951.5     .11       0
Bank Sta=4941.1,5033.3
XS Rating Curve= 0 ,0
Exp/Cntr=0.3,0.1

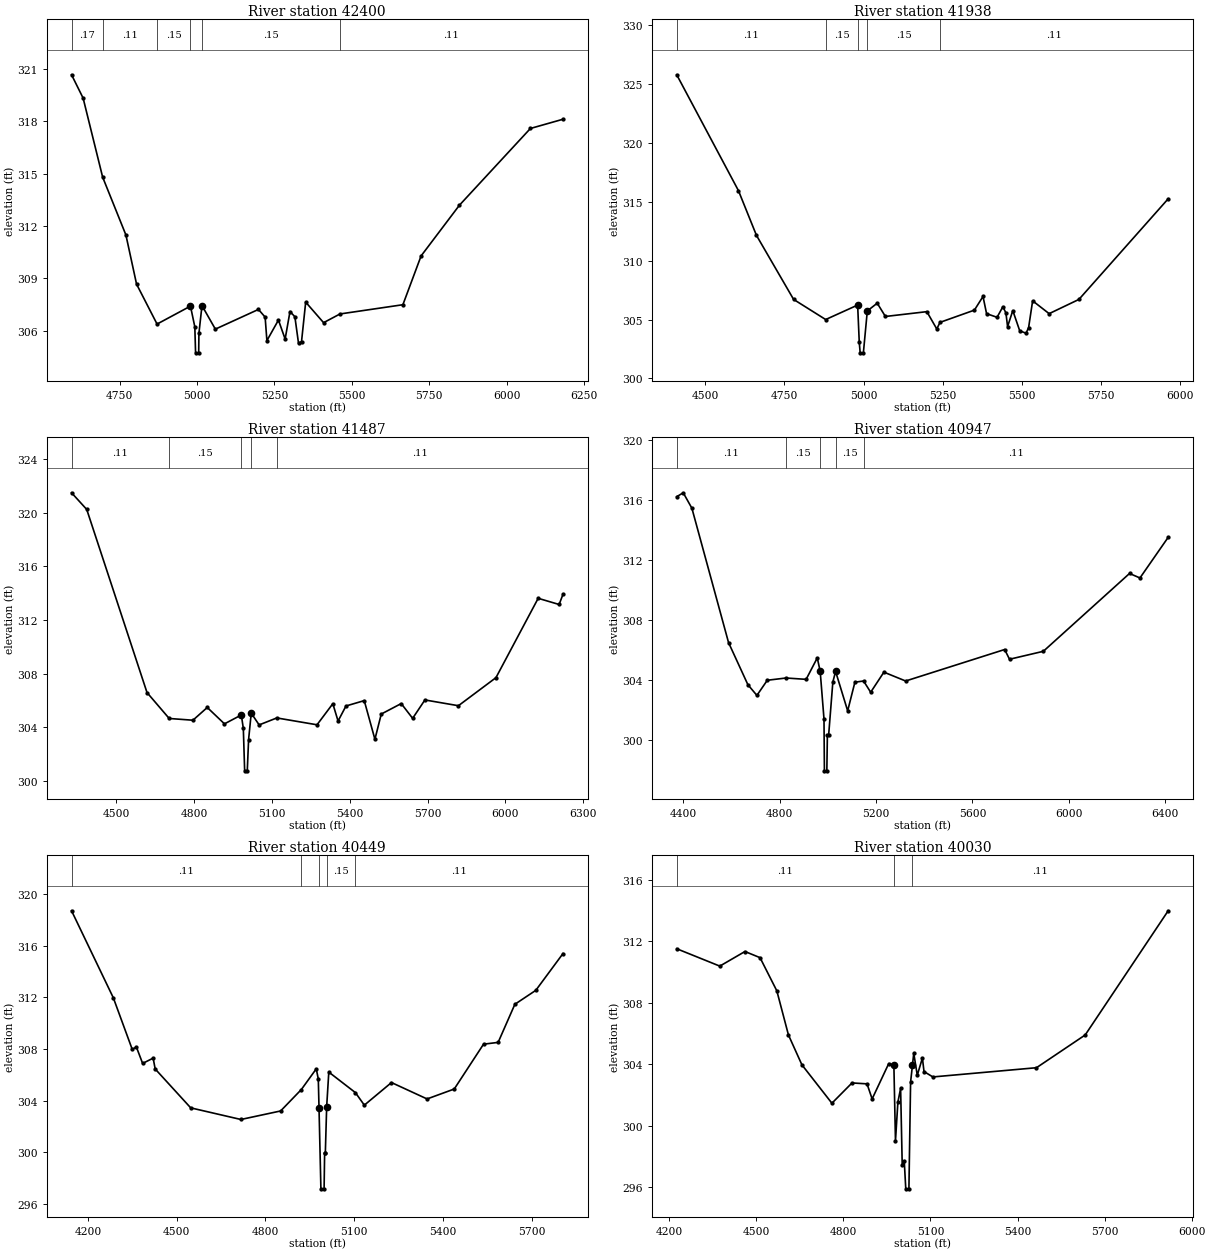
Type RM Length L Ch R = 1 ,42400   ,462,462,462
BEGIN DESCRIPTION:
GARRETTS CREEK 70.0
END DESCRIPTION:
XS GIS Cut Line= 3
      3688317.84     10187811.04      3688186.01     10187520.01
      3687088.29     10186885.31
#Sta/Elev= 30
  4594.8  320.67  4632.2  319.33  4695.2   314.8  4770.4  311.48  4804.8  308.66
    4871  306.37  4978.9   307.4    4993  306.21  4995.4  304.72  5005.5  304.72
  5006.2  305.83  5016.1  307.43  5059.3  306.08  5198.5  307.21  5220.1  306.77
  5225.8  305.42  5263.1   306.6  5284.7  305.51  5300.4  307.09  5316.2  306.79
    5328  305.26  5337.7  305.37  5351.1  307.63  5408.9  306.45  5461.9  306.95
  5665.1  307.48  5723.9  310.28  5847.8  313.19    6077  317.59  6182.3  318.12
#Mann= 6 ,-1 , 0
  4594.8     .17       0  4695.2     .11       0    4871     .15       0
  4978.9     .09       0  5016.1     .15       0  5461.9     .11       0
Bank Sta=4978.9,5016.1
XS Rating Curve= 0 ,0
Exp/Cntr=0.3,0.1

Type RM Length L Ch R = 1 ,41938   ,451,451,451
BEGIN DESCRIPTION:
GARRETTS CREEK 69.0
END DESCRIPTION:
XS GIS Cut Line= 3
      3688567.85     10187811.08      3688439.29     10187235.67
      3687517.84     10186961.07
#Sta/Elev= 30
  4410.4   325.8  4605.1  315.96  4662.1  312.15  4779.3  306.71  4880.5     305
  4981.4  306.23  4986.5  303.07  4989.4  302.17  4999.5  302.17  5011.9  305.73
  5043.2  306.39    5069  305.26  5199.8  305.67  5231.1   304.2  5241.4  304.76
  5349.9   305.8  5377.1  306.96  5388.3   305.5  5421.4  305.19  5439.8  306.09
  5449.4  305.56  5454.6   304.4  5471.1  305.76    5493  304.04  5512.8  303.84
  5520.9   304.3  5533.7  306.59  5585.8   305.5  5679.8  306.71  5961.5  315.26
#Mann= 5 ,-1 , 0
  4410.4     .11       0  4880.5     .15       0  4981.4     .09       0
  5011.9     .15       0  5241.4     .11       0
Bank Sta=4981.4,5011.9
XS Rating Curve= 0 ,0
Exp/Cntr=0.3,0.1

Type RM Length L Ch R = 1 ,41487   ,540,540,540
BEGIN DESCRIPTION:
GARRETTS CREEK 68.0
END DESCRIPTION:
XS GIS Cut Line= 3
      3689430.84     10187353.36      3688878.72     10187092.93
      3687613.07     10186879.38
#Sta/Elev= 30
  4328.1  321.47  4386.6  320.23  4618.9  306.59  4704.4  304.66  4795.9  304.53
  4851.1  305.48  4917.4  304.26  4982.4  304.92  4990.1  303.92  4995.2  300.76
  5005.3  300.76  5010.4  303.09  5020.6  305.06    5051  304.18  5119.1   304.7
  5274.1  304.19    5335  305.76  5355.2  304.47  5385.7  305.59  5456.1  305.99
  5497.2  303.11  5521.7  304.99  5598.6  305.77  5642.6  304.67  5689.9  306.04
    5819  305.61  5963.7   307.7  6126.4  313.61  6207.1  313.15  6222.1  313.91
#Mann= 5 ,-1 , 0
  4328.1     .11       0  4704.4     .15       0  4982.4     .09       0
  5020.6     .15       0  5119.1     .11       0
Bank Sta=4982.4,5020.6
XS Rating Curve= 0 ,0
Exp/Cntr=0.3,0.1

Type RM Length L Ch R = 1 ,40947   ,498,498,498
BEGIN DESCRIPTION:
GARRETTS CREEK 67.0
END DESCRIPTION:
XS GIS Cut Line= 3
      3689592.27     10187191.89      3689050.14     10186877.68
      3687641.04     10186785.76
#Sta/Elev= 30
  4373.4  316.21  4400.4  316.47  4436.3  315.44  4588.4  306.48  4668.7  303.67
    4706  302.96  4749.1  303.97  4826.8  304.12  4910.2  304.03  4956.4  305.46
  4968.5  304.57  4984.3  301.39    4986  297.93  4996.1  297.93  4998.4  300.33
  5003.7  300.33    5021  303.85  5032.4  304.56  5082.5  301.93  5112.5  303.84
  5148.5  303.92    5178  303.17  5232.8  304.51    5323  303.92  5733.8  306.02
  5753.9  305.37  5894.2   305.9  6251.8  311.09    6295  310.79  6412.1   313.5
#Mann= 5 ,-1 , 0
  4373.4     .11       0  4826.8     .15       0  4968.5     .09       0
  5032.4     .15       0  5148.5     .11       0
Bank Sta=4968.5,5032.4
XS Rating Curve= 0 ,0
Exp/Cntr=0.3,0.1

Type RM Length L Ch R = 1 ,40449   ,419,419,419
BEGIN DESCRIPTION:
GARRETTS CREEK 66.0
END DESCRIPTION:
XS GIS Cut Line= 3
      3689817.83     10187161.05      3689199.42     10186569.33
      3688617.82     10186011.04
#Sta/Elev= 30
  4144.1   318.7  4285.4  311.96  4349.3  307.97  4363.4  308.15  4384.5  306.88
    4420  307.29    4427  306.45  4547.1  303.44  4716.9  302.54  4851.2   303.2
  4921.3  304.86  4971.7  306.46  4978.6  305.68 4981.04303.4162  4987.4  297.17
  4998.2  297.17    5000  299.95  5002.4  299.95  5006.9  303.53  5014.1  306.21
  5104.1  304.62  5134.3  303.65  5226.1   305.4  5346.5  304.13  5438.4   304.9
  5537.4  308.37  5586.8  308.51  5643.4  311.46  5714.2  312.54  5806.2  315.39
#Mann= 5 ,-1 , 0
  4144.1     .11       0  4921.3     .15       0 4981.04     .09       0
  5006.9     .15       0  5104.1     .11       0
Bank Sta=4981.04,5006.9
XS Rating Curve= 0 ,0
Exp/Cntr=0.3,0.1

Type RM Length L Ch R = 1 ,40030   ,293,293,293
BEGIN DESCRIPTION:
GARRETTS CREEK 65.0
END DESCRIPTION:
XS GIS Cut Line= 3
      3690212.05     10186655.43       3689555.8     10186358.55
      3688667.88     10185961.08
#Sta/Elev= 30
    4226  311.52  4374.4  310.39  4461.1  311.34    4513  310.94  4570.9  308.78
  4610.9  305.91  4657.2  303.97  4760.6  301.47  4829.9  302.79  4881.6  302.73
  4899.2  301.75  4956.4  304.05  4974.1  303.95  4979.6  299.02  4987.9  301.54
  4997.3  302.44  5002.8  297.48  5009.8  297.73  5015.1   295.9  5025.9   295.9
  5031.7  302.85 5038.17  303.96  5042.6  304.72  5054.7  303.29  5072.4  304.41
  5077.9  303.53  5108.4  303.18  5465.4  303.78  5633.2  305.91  5919.1  313.99
#Mann= 3 , 0 , 0
    4226     .11       0  4974.1     .06       0 5038.17     .11       0
Bank Sta=4974.1,5038.17
XS Rating Curve= 0 ,0
Exp/Cntr=0.3,0.1