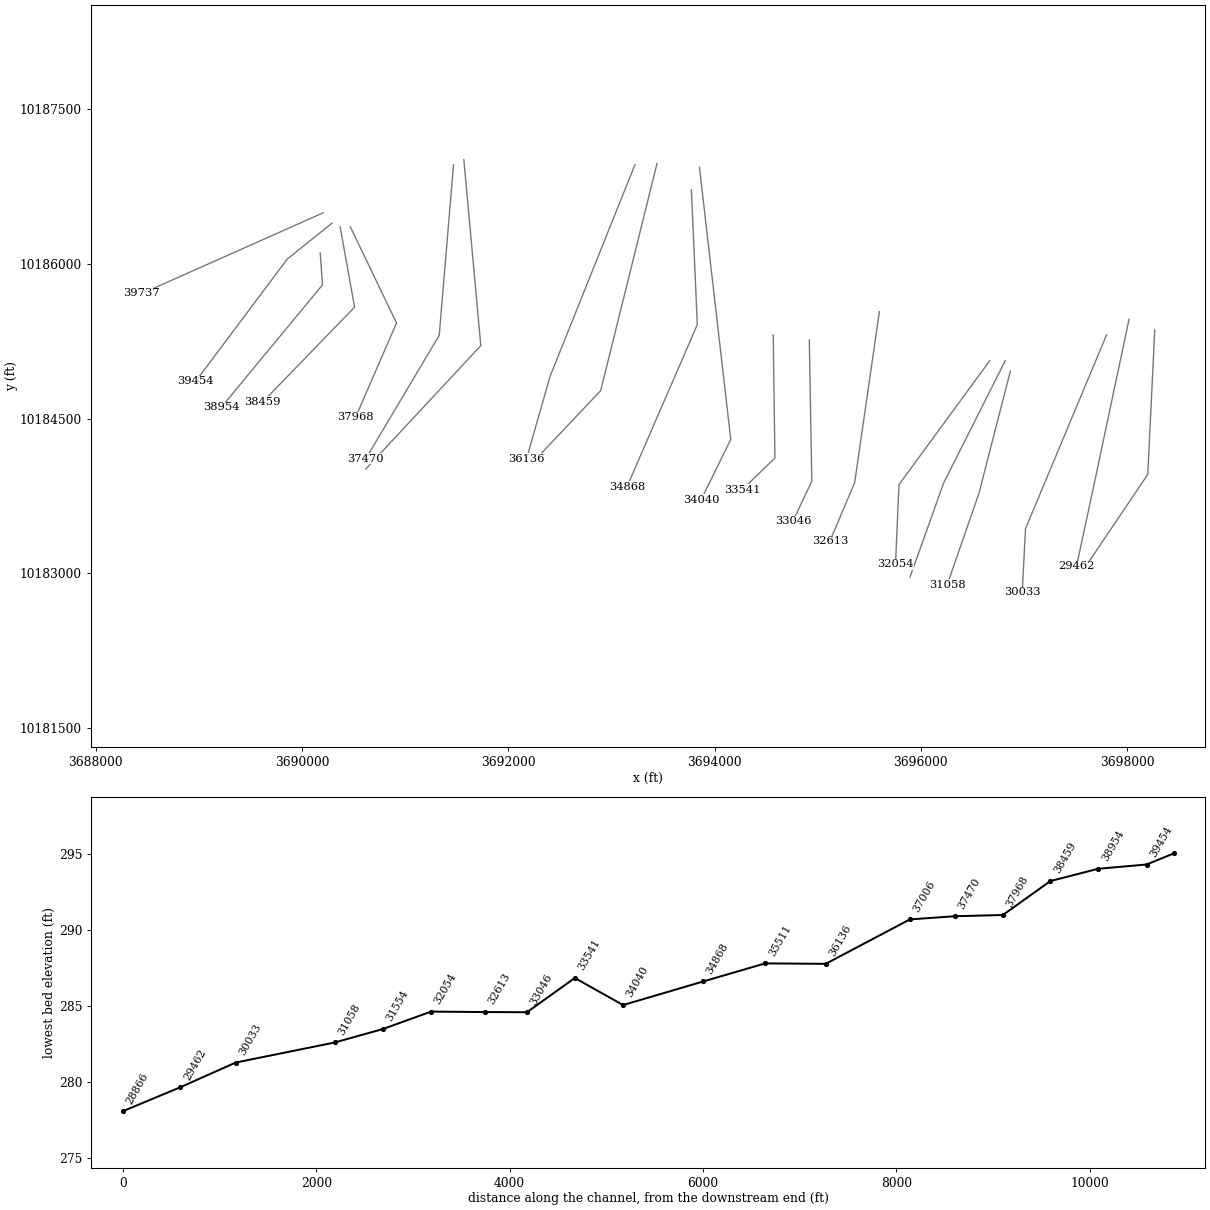
HEC-RAS study GARRETTS CREEK.prj: GARRETTS CREEK Base Level Engineering

--- GARRETTS CREEK.g01 (geometry) --- (continued)

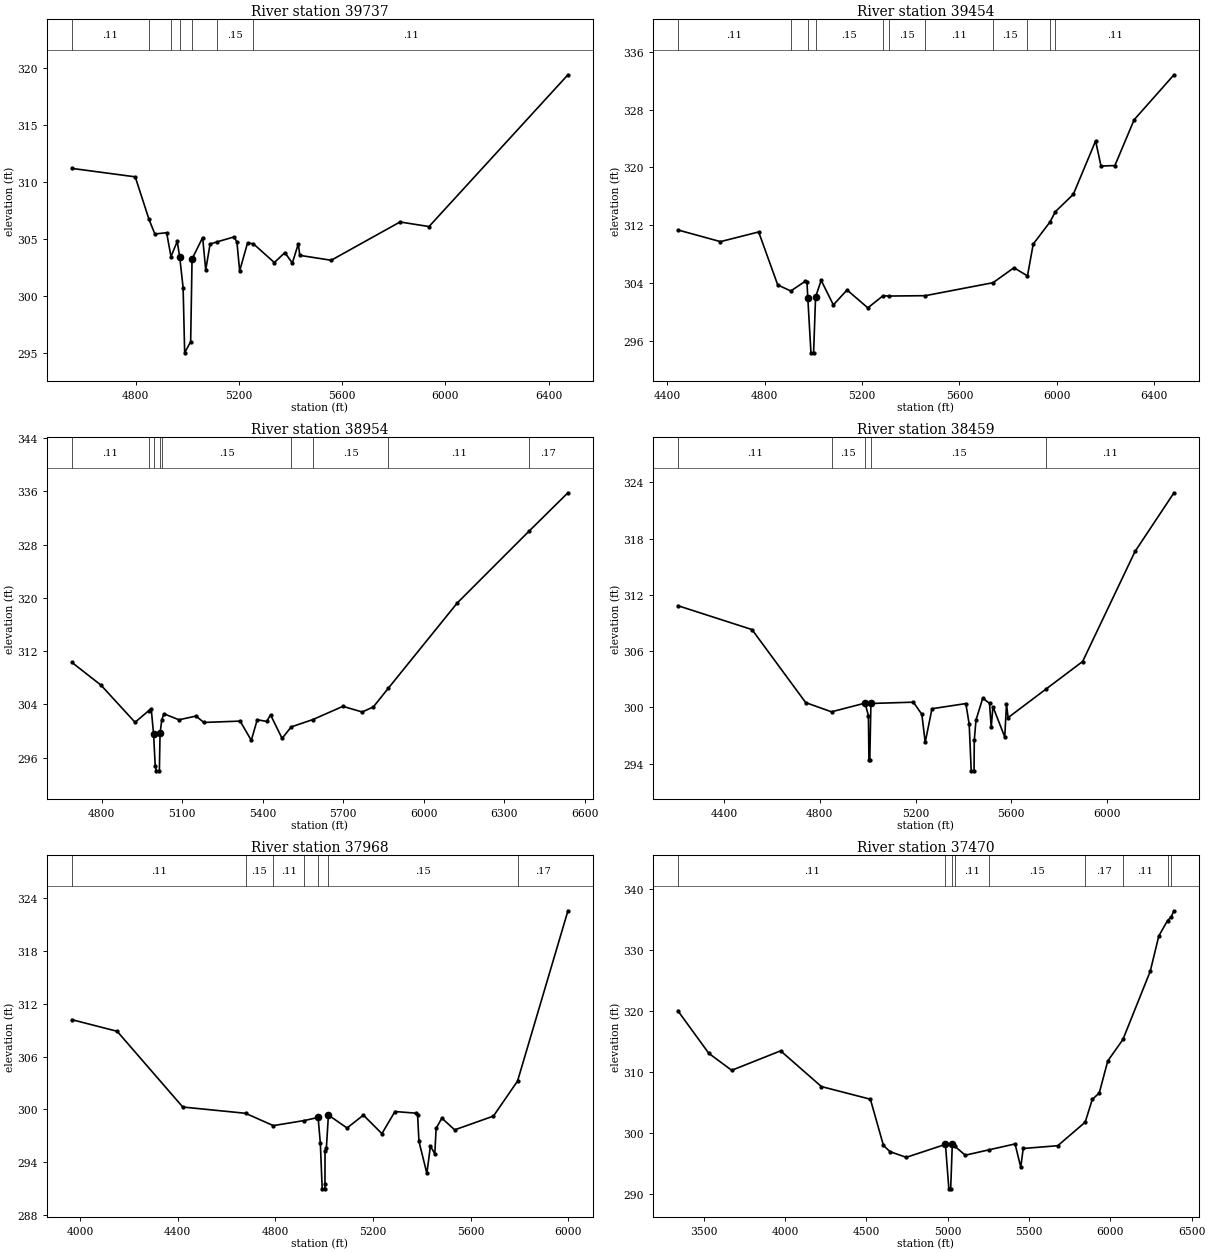
Type RM Length L Ch R = 1 ,39737   ,283,283,283
BEGIN DESCRIPTION:
Mapping XS a48eca12
END DESCRIPTION:
XS GIS Cut Line= 2
      3690201.66     10186493.98      3688446.47     10185712.74
#Sta/Elev= 30
    4553  311.18  4798.6  310.44  4852.1  306.71  4874.6  305.44  4920.3  305.55
  4937.1  303.46  4961.3  304.79 4970.89303.4121  4984.1  300.74  4990.1  295.04
  5013.3  296.02  5018.7  303.25  5059.7  305.13  5071.6  302.29  5088.5  304.56
  5116.9  304.76  5181.1  305.18  5192.4  304.74    5203  302.21  5233.4  304.64
  5255.7  304.59  5337.3  302.94  5378.1  303.81    5407   302.9  5430.3  304.59
  5435.7  303.57  5557.4  303.14    5824  306.49  5936.3  306.09  6474.2  319.37
#Mann= 7 ,-1 , 0
    4553     .11       0  4852.1     .15       0  4937.1     .11       0
 4970.89     .07       0  5018.7     .11       0  5116.9     .15       0
  5255.7     .11       0
Bank Sta=4970.89,5018.7
XS Rating Curve= 0 ,0
Exp/Cntr=0.3,0.1

Type RM Length L Ch R = 1 ,39454   ,500,500,500
BEGIN DESCRIPTION:
GARRETTS CREEK 64.0
END DESCRIPTION:
XS GIS Cut Line= 3
      3690290.21     10186395.03      3689855.78     10186046.75
      3688967.85     10184861.07
#Sta/Elev= 30
  4443.2  311.34  4618.3  309.72  4775.2  311.06  4853.6  303.72  4907.1  302.88
  4967.2  304.24  4973.6  304.13 4977.04301.9543  4990.1  294.31  5000.9  294.31
  5009.1  302.07    5032  304.35  5082.1  300.95  5138.3  303.02  5223.7  300.54
  5286.1  302.22  5309.3  302.18  5459.6  302.23    5738  304.03  5823.9   306.1
  5879.4  304.97  5903.1  309.38  5971.9  312.44  5994.2  313.88  6067.7  316.27
  6159.4  323.67  6181.5  320.19  6238.5  320.26  6317.7  326.61  6481.3  332.84
#Mann= 11 ,-1 , 0
  4443.2     .11       0  4907.1     .15       0 4977.04     .09       0
  5009.1     .15       0  5286.1     .11       0  5309.3     .15       0
  5459.6     .11       0    5738     .15       0  5879.4     .11       0
  5971.9     .15       0  5994.2     .11       0
Bank Sta=4977.04,5009.1
XS Rating Curve= 0 ,0
Exp/Cntr=0.3,0.1

Type RM Length L Ch R = 1 ,38954   ,495,495,495
BEGIN DESCRIPTION:
GARRETTS CREEK 63.0
END DESCRIPTION:
XS GIS Cut Line= 3
      3690175.25     10186106.18      3690197.37     10185796.07
      3689217.86     10184611.09
#Sta/Elev= 30
  4689.1  310.33  4797.7  306.91  4924.8  301.32  4975.5  303.06    4985  303.36
 4993.82299.5234    5000  294.69  5004.6  294.03  5015.4  294.03  5017.9  299.65
  5024.4  301.69  5032.2   302.6  5088.2   301.7    5152  302.26  5180.7   301.3
  5316.2   301.5  5357.8  298.61    5380  301.71  5415.2  301.45  5429.5  302.44
  5472.5   298.9  5506.5  300.63  5587.7  301.74  5699.1  303.72  5770.8  302.87
  5812.5  303.63  5868.2  306.44  6125.1  319.25  6391.8  330.01  6537.4   335.8
#Mann= 9 ,-1 , 0
  4689.1     .11       0  4975.5     .15       0 4993.82     .09       0
  5017.9     .12       0  5024.4     .15       0  5506.5     .11       0
  5587.7     .15       0  5868.2     .11       0  6391.8     .17       0
Bank Sta=4993.82,5017.9
XS Rating Curve= 0 ,0
Exp/Cntr=0.3,0.1

Type RM Length L Ch R = 1 ,38459   ,491,491,491
BEGIN DESCRIPTION:
GARRETTS CREEK 62.0
END DESCRIPTION:
XS GIS Cut Line= 3
      3690367.86     10186361.04      3690508.64     10185580.03
      3689617.88      10184661.1
#Sta/Elev= 30
  4206.4  310.85  4516.3   308.3  4740.9   300.5  4848.6  299.52  4988.8  300.45
  5002.8  299.11 5005.01  294.42 5008.62  294.42 5013.27  300.41  5190.8  300.55
  5226.1  299.25  5240.2  296.27  5268.5  299.85    5410   300.4  5424.1  298.17
  5432.4  293.22  5444.2  293.22  5445.3  296.48  5452.4  298.64  5480.7  300.98
    5509  300.42    5516  297.85  5523.2  300.07  5572.6  296.83  5579.8  300.32
  5586.7   298.9  5745.1  301.95    5898  304.89  6117.1  316.64  6279.8   322.9
#Mann= 5 ,-1 , 0
  4206.4     .11       0  4848.6     .15       0  4988.8     .09       0
 5013.27     .15       0  5745.1     .11       0
Bank Sta=4988.8,5013.27
XS Rating Curve= 0 ,0
Exp/Cntr=0.3,0.1

Type RM Length L Ch R = 1 ,37968   ,498,498,498
BEGIN DESCRIPTION:
GARRETTS CREEK 61.0
END DESCRIPTION:
XS GIS Cut Line= 3
      3690467.27     10186358.53       3690915.2     10185426.92
      3690517.86      10184511.1
#Sta/Elev= 30
  3966.3  310.18  4152.1  308.86  4420.8  300.27  4677.8  299.56  4791.7  298.16
  4919.1  298.74  4975.1  299.09  4984.3  296.15  4991.8  290.99  5002.7  290.99
  5003.2  291.49  5003.4   295.3  5008.9   295.6  5017.3  299.36  5093.6  297.89
  5160.5  299.35  5236.4  297.25  5289.8  299.76    5377  299.57  5382.6  299.34
  5388.1  296.37  5420.6  292.74    5435  295.84    5453  294.96  5458.5  297.85
  5481.9  299.01  5534.3  297.68  5693.1  299.24  5791.8  303.21  5998.3  322.53
#Mann= 7 ,-1 , 0
  3966.3     .11       0  4677.8     .15       0  4791.7     .11       0
  4919.1     .15       0  4975.1     .09       0  5017.3     .15       0
  5791.8     .17       0
Bank Sta=4975.1,5017.3
XS Rating Curve= 0 ,0
Exp/Cntr=0.3,0.1

Type RM Length L Ch R = 1 ,37470   ,464,464,464
BEGIN DESCRIPTION:
GARRETTS CREEK 60.0
END DESCRIPTION:
XS GIS Cut Line= 3
      3691467.85     10186961.08      3691329.12     10185306.99
      3690617.87     10184111.11
#Sta/Elev= 30
  3340.1  320.03  3530.8  313.06  3671.3  310.29  3972.3  313.47  4223.2  307.63
  4524.3  305.56  4604.5  298.01  4644.7  296.99    4745  296.06  4985.9  298.18
  5006.9  290.91  5018.1  290.91  5028.1  298.22  5044.6  297.84  5107.9  296.41
  5255.6   297.3  5414.1  298.25    5449  294.45  5464.3  297.51  5676.6  297.96
  5845.3  301.81    5889  305.53  5931.8  306.58  5984.2  311.82  6077.4  315.33
  6245.4  326.48    6298  332.25  6351.7  334.77  6372.5   335.3  6391.4  336.37
#Mann= 9 ,-1 , 0
  3340.1     .11       0  4985.9     .09       0  5028.1     .15       0
  5044.6     .11       0  5255.6     .15       0  5845.3     .17       0
  6077.4     .11       0  6351.7     .17       0  6372.5     .11       0
Bank Sta=4985.9,5028.1
XS Rating Curve= 0 ,0
Exp/Cntr=0.3,0.1

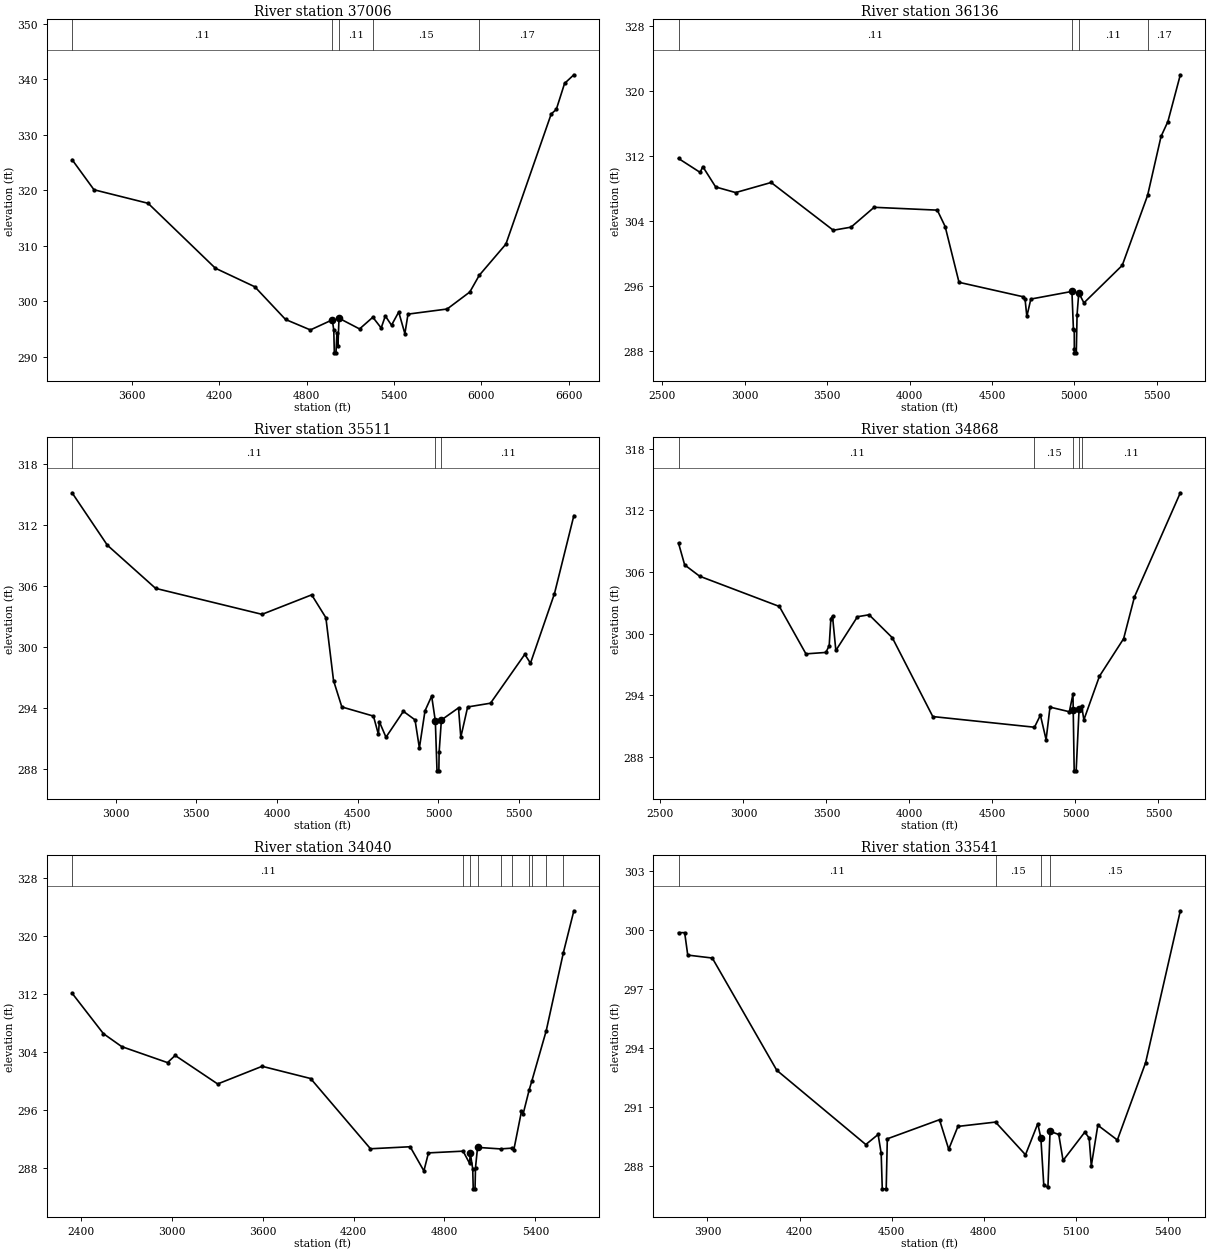
Type RM Length L Ch R = 1 ,37006   ,870,870,870
BEGIN DESCRIPTION:
GARRETTS CREEK 59.0
END DESCRIPTION:
XS GIS Cut Line= 3
      3691567.86     10187011.03       3691732.4     10185207.01
      3690617.83     10184011.05
#Sta/Elev= 30
  3188.5  325.53  3339.1   320.1  3710.6  317.66  4172.5  305.96  4443.6  302.61
  4654.5  296.72  4825.2  294.83  4975.8  296.65  4985.9  294.78  4989.8   290.7
  5001.1   290.7  5007.6  294.35  5014.5  291.91  5021.8  296.94    5163  295.01
  5254.2  297.12  5311.5  295.18  5339.9  297.35  5382.4  295.68  5431.9  298.06
  5474.2  294.16  5495.7  297.68  5764.4   298.6  5920.3  301.67  5985.1  304.68
    6168   310.3  6479.2  333.76  6514.3  334.59    6571  339.27  6634.8  340.83
#Mann= 5 ,-1 , 0
  3188.5     .11       0  4975.8     .06       0  5021.8     .11       0
  5254.2     .15       0  5985.1     .17       0
Bank Sta=4975.8,5021.8
XS Rating Curve= 0 ,0
Exp/Cntr=0.3,0.1

Type RM Length L Ch R = 1 ,36136   ,625,625,625
BEGIN DESCRIPTION:
GARRETTS CREEK 58.0
END DESCRIPTION:
XS GIS Cut Line= 3
      3693227.68     10186962.72      3692404.76     10184910.64
       3692175.6     10184108.57
#Sta/Elev= 30
  2597.9  311.67    2729  309.96  2745.2  310.67  2823.2  308.17  2944.4  307.48
  3159.9  308.72    3537  302.85  3644.8  303.23  3784.8  305.67  4168.2  305.32
  4215.8  303.31    4300  296.45  4689.9  294.67  4700.6   294.4  4711.6  292.26
  4735.8  294.39  4985.2  295.33  4994.1  290.75  4999.3  290.61  4999.8  288.28
  5000.3  287.78  5011.7  287.78  5016.4  292.48  5026.8  295.15    5058  293.92
  5290.5  298.53  5444.3  307.13    5526  314.38  5567.6  316.21    5643  321.96
#Mann= 4 ,-1 , 0
  2597.9     .11       0  4985.2     .06       0  5026.8     .11       0
  5444.3     .17       0
Bank Sta=4985.2,5026.8
XS Rating Curve= 0 ,0
Exp/Cntr=0.3,0.1

Type RM Length L Ch R = 1 ,35511   ,643,643,643
BEGIN DESCRIPTION:
GARRETTS CREEK 57.0
END DESCRIPTION:
XS GIS Cut Line= 3
      3693441.21      10186973.1      3692894.76     10184770.58
      3692317.88      10184161.1
#Sta/Elev= 30
  2730.7  315.19  2949.2  310.03    3248  305.78  3907.4  303.22  4215.1  305.14
    4303  302.89  4350.4   296.7  4401.9   294.1  4597.7   293.2  4628.6  291.39
  4633.9  292.66  4675.3  291.12  4783.1  293.67  4855.2  292.83  4882.2  290.06
  4917.1  293.72  4958.3  295.17 4981.04292.7228  4991.4  287.81  5002.9  287.81
  5004.5  289.63  5018.6  292.82  5124.6  294.01  5138.8  291.12  5181.3   294.1
  5322.9  294.47  5535.2  299.28  5570.4  298.41  5718.9  305.25  5839.2  312.94
#Mann= 3 , 0 , 0
  2730.7     .11       0 4981.04     .06       0  5018.6     .11       0
Bank Sta=4981.04,5018.6
XS Rating Curve= 0 ,0
Exp/Cntr=0.3,0.1

Type RM Length L Ch R = 1 ,34868   ,828,828,828
BEGIN DESCRIPTION:
Mapping XS 5c9b23c9
END DESCRIPTION:
XS GIS Cut Line= 3
      3693774.55     10186717.92      3693831.84     10185410.64
      3693149.54     10183837.68
#Sta/Elev= 30
  2609.1  308.81    2646  306.69  2736.1  305.59  3216.5  302.64  3376.7  298.02
  3496.8  298.16  3516.8  298.82  3526.8  301.46  3536.8  301.69  3556.9  298.35
    3687  301.64    3757  301.83  3897.2  299.59  4140.9  291.91  4753.6  290.87
  4789.2  292.05  4823.5  289.66    4847  292.83  4963.6  292.38  4985.4  294.11
 4986.94292.5498  4992.8  286.62  5004.6  286.62  5022.2  292.62  5037.6  292.96
  5051.1  291.59  5144.9  295.84  5290.6   299.5    5356  303.58  5632.2  313.72
#Mann= 5 ,-1 , 0
  2609.1     .11       0  4753.6     .15       0 4986.94     .09       0
  5022.2     .15       0  5037.6     .11       0
Bank Sta=4986.94,5022.2
XS Rating Curve= 0 ,0
Exp/Cntr=0.3,0.1

Type RM Length L Ch R = 1 ,34040   ,499,499,499
BEGIN DESCRIPTION:
GARRETTS CREEK 56.0
END DESCRIPTION:
XS GIS Cut Line= 3
      3693852.68     10186936.63      3694156.31     10184297.44
      3693867.84     10183711.05
#Sta/Elev= 30
  2343.4  312.12  2550.3  306.52  2671.1  304.73  2973.1  302.52  3023.4  303.51
  3303.8  299.57  3597.2  302.01    3917  300.32  4311.9  290.61  4573.6  290.89
  4664.2  287.55  4694.4  290.04  4922.9  290.28  4965.4   288.6  4970.4     290
  4986.3  287.83  4989.8  285.07  5001.6  285.07  5004.7  288.01  5018.2   290.8
  5169.6  290.59  5247.6   290.7  5257.4  290.46    5308  295.79  5319.1  295.44
  5359.2  298.78  5376.9  300.02  5470.9   306.9  5584.1   317.7  5653.5  323.51
#Mann= 10 ,-1 , 0
  2343.4     .11       0  4922.9     .15       0  4970.4     .09       0
  5018.2     .15       0  5169.6     .11       0  5247.6     .17       0
  5359.2     .15       0  5376.9     .17       0  5470.9     .15       0
  5584.1     .17       0
Bank Sta=4970.4,5018.2
XS Rating Curve= 0 ,0
Exp/Cntr=0.3,0.1

Type RM Length L Ch R = 1 ,33541   ,495,495,495
BEGIN DESCRIPTION:
GARRETTS CREEK 55.0
END DESCRIPTION:
XS GIS Cut Line= 3
      3694567.85     10185311.02      3694584.51     10184117.04
      3694267.87     10183811.09
#Sta/Elev= 30
  3805.9  299.86  3825.9  299.86  3835.9  298.72  3915.9  298.57  4125.9  292.87
  4415.9   289.1  4455.9  289.61  4465.9  288.66  4469.5  286.85  4482.3  286.85
  4485.9  289.39  4655.9  290.36  4685.9  288.86  4715.9  290.02  4838.4  290.24
    4936  288.58    4976  290.16    4986  289.44  4995.5  287.05    5009  286.92
    5016  289.77  5044.3  289.61  5058.4  288.29  5129.2  289.73  5143.3  289.43
  5150.3  288.01  5171.6  290.08  5235.2  289.33  5327.3  293.26  5440.3  300.97
#Mann= 4 ,-1 , 0
  3805.9     .11       0  4838.4     .15       0    4986     .09       0
    5016     .15       0
Bank Sta=4986,5016
XS Rating Curve= 0 ,0
Exp/Cntr=0.3,0.1

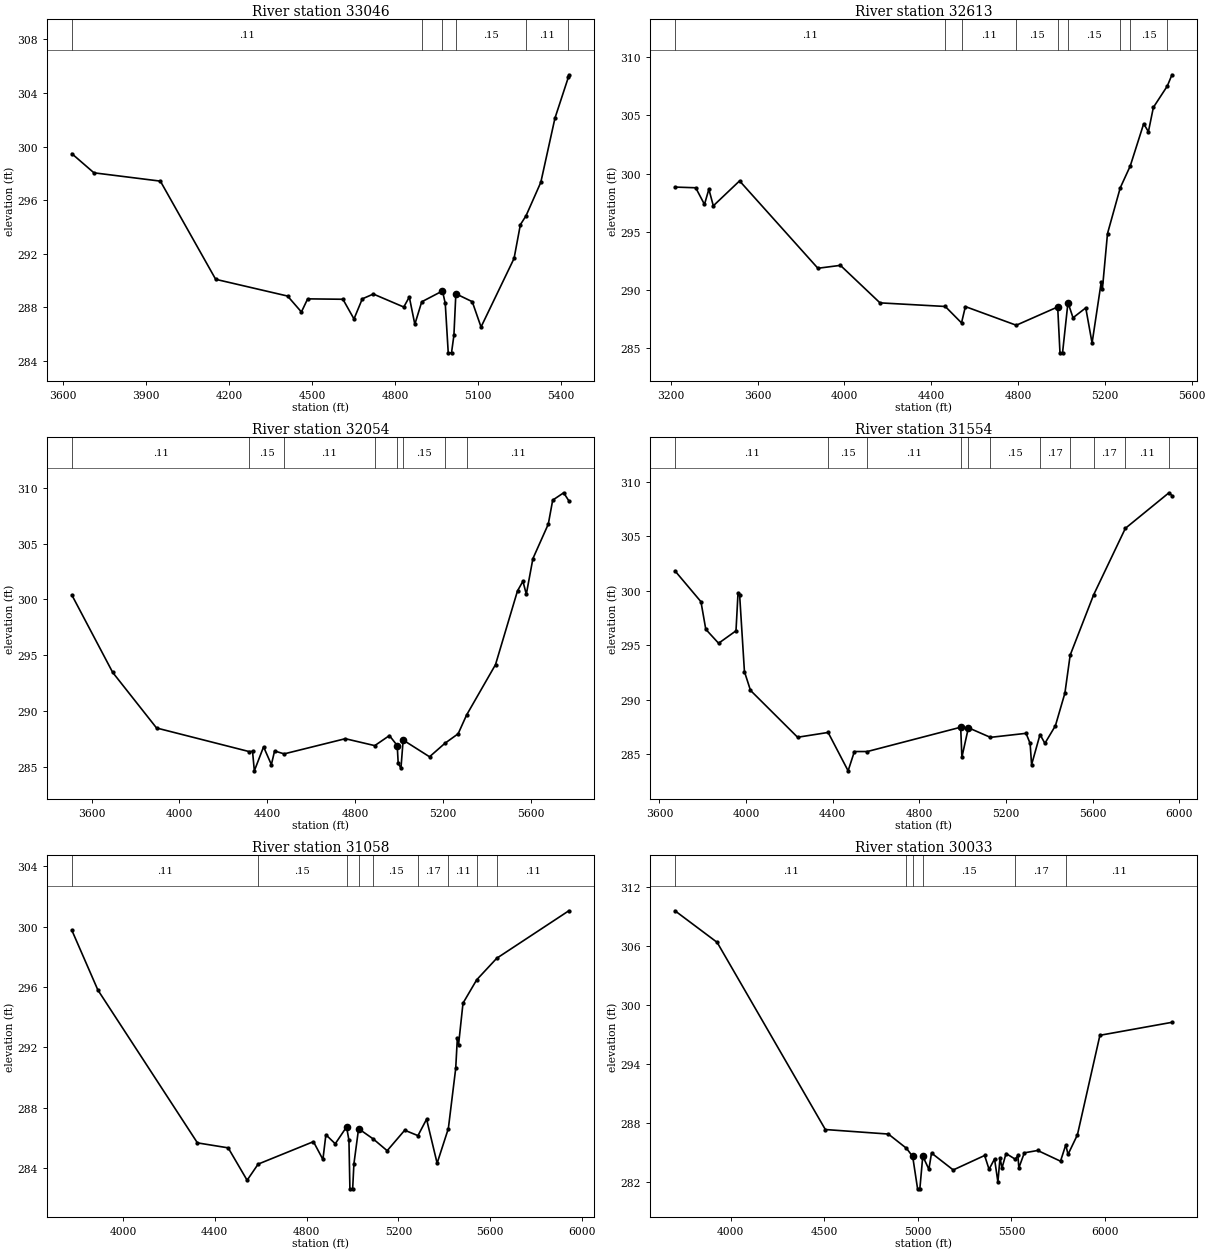
Type RM Length L Ch R = 1 ,33046   ,433,433,433
BEGIN DESCRIPTION:
GARRETTS CREEK 54.0
END DESCRIPTION:
XS GIS Cut Line= 3
      3694917.85     10185261.08      3694941.99     10183892.79
       3694759.3     10183505.19
#Sta/Elev= 30
  3631.5  299.47  3711.5  298.04  3951.6  297.42  4151.6  290.09  4411.6  288.84
  4461.6  287.65  4484.2  288.63  4611.7   288.6  4651.7  287.13  4681.7  288.63
  4721.7  288.99  4831.7  288.02  4851.7  288.77  4871.7  286.73  4896.6  288.41
  4971.7  289.22  4981.7  288.29  4992.5   284.6  5004.3   284.6    5013  285.91
    5020  289.01  5079.3  288.42  5111.1  286.53  5230.5  291.65  5253.3  294.17
  5273.7  294.83  5327.2  297.33  5378.3  302.12  5426.7  305.17  5428.5  305.36
#Mann= 6 ,-1 , 0
  3631.5     .11       0  4896.6     .15       0  4971.7     .09       0
    5020     .15       0  5273.7     .11       0  5426.7     .15       0
Bank Sta=4971.7,5020
XS Rating Curve= 0 ,0
Exp/Cntr=0.3,0.1

Type RM Length L Ch R = 1 ,32613   ,559,559,559
BEGIN DESCRIPTION:
GARRETTS CREEK 53.0
END DESCRIPTION:
XS GIS Cut Line= 3
      3695597.48     10185535.68      3695357.89     10183879.39
      3695117.84     10183311.03
#Sta/Elev= 30
  3218.8  298.84  3314.4  298.78  3354.8  297.35    3375  298.66  3395.5  297.23
  3516.5  299.37  3877.5  291.87  3981.3  292.12  4163.7   288.9  4464.5  288.59
  4539.4  287.18  4557.2  288.58  4791.7  286.98  4982.6  288.55  4993.2  284.61
    5005  284.61    5030  288.93  5053.3  287.62    5112  288.47  5141.1  285.45
  5183.1  290.66  5188.5  290.05  5212.2  294.85  5270.8  298.77    5317  300.65
    5379  304.28  5400.7  303.59  5423.6  305.68  5487.7  307.51  5509.3  308.48
#Mann= 9 ,-1 , 0
  3218.8     .11       0  4464.5     .17       0  4539.4     .11       0
  4791.7     .15       0  4982.6     .09       0    5030     .15       0
  5270.8     .11       0    5317     .15       0  5487.7     .11       0
Bank Sta=4982.6,5030
XS Rating Curve= 0 ,0
Exp/Cntr=0.3,0.1

Type RM Length L Ch R = 1 ,32054   ,500,500,500
BEGIN DESCRIPTION:
GARRETTS CREEK 52.0
END DESCRIPTION:
XS GIS Cut Line= 3
      3696667.85     10185061.07      3695787.44     10183859.37
      3695753.72     10183087.71
#Sta/Elev= 30
  3510.3   300.4  3696.3  293.46  3895.9  288.48  4318.6  286.36  4332.8  286.39
    4341  284.64    4383  286.79  4418.5   285.2  4433.2  286.42  4476.7  286.16
  4755.1  287.52  4889.1   286.9  4955.8   287.8  4991.3  286.91  4995.8  285.32
  5008.3  284.87  5018.3   287.4  5138.4   285.9  5208.5  287.11  5268.6  287.96
    5307  289.64  5438.7  294.16  5538.8  300.77  5563.5  301.63  5578.9  300.47
  5608.9  303.66  5678.9  306.75    5699   308.9    5749  309.56  5772.4  308.84
#Mann= 8 ,-1 , 0
  3510.3     .11       0  4318.6     .15       0  4476.7     .11       0
  4889.1     .15       0  4991.3     .09       0  5018.3     .15       0
  5208.5     .17       0    5307     .11       0
Bank Sta=4991.3,5018.3
XS Rating Curve= 0 ,0
Exp/Cntr=0.3,0.1

Type RM Length L Ch R = 1 ,31554   ,496,496,496
BEGIN DESCRIPTION:
GARRETTS CREEK 51.0
END DESCRIPTION:
XS GIS Cut Line= 3
      3696817.87      10185061.1      3696220.54     10183874.46
      3695894.93     10182964.35
#Sta/Elev= 30
  3671.5  301.83  3791.5     299  3813.8  296.47    3873  295.19  3953.3  296.33
  3962.6  299.77    3970  299.65  3992.3  292.59  4020.2  290.87  4237.8  286.57
  4378.7  287.01  4471.1  283.49    4500  285.26  4559.6  285.26  4990.9  287.49
  4996.5  284.74  5026.5  287.44  5128.2  286.56  5292.8  286.93  5311.6     286
  5318.3  284.05  5357.3  286.82  5379.8  286.01  5428.4  287.63  5472.2  290.62
  5496.5   294.1  5604.8  299.63  5751.4  305.73  5952.7  308.99  5966.6  308.74
#Mann= 11 ,-1 , 0
  3671.5     .11       0  4378.7     .15       0  4559.6     .11       0
  4990.9     .06       0  5026.5     .11       0  5128.2     .15       0
  5357.3     .17       0  5496.5     .11       0  5604.8     .17       0
  5751.4     .11       0  5952.7     .17       0
Bank Sta=4990.9,5026.5
XS Rating Curve= 0 ,0
Exp/Cntr=0.3,0.1

Type RM Length L Ch R = 1 ,31058   ,1025,1025,1025
BEGIN DESCRIPTION:
GARRETTS CREEK 50.0
END DESCRIPTION:
XS GIS Cut Line= 3
      3696867.86      10184961.1      3696563.48     10183776.37
      3696253.96      10182885.3
#Sta/Elev= 30
  3776.8  299.77  3890.4   295.8  4324.3  285.66  4458.3  285.33  4540.9  283.18
  4588.9  284.25    4830  285.74  4871.3  284.56  4884.3   286.2  4925.1   285.6
  4974.5  286.72  4984.8  285.83    4989  282.61    5001  282.61  5006.4  284.26
  5026.8   286.6  5090.7  285.92  5151.4  285.14  5227.9   286.5  5285.6  286.14
  5323.2  287.23  5369.2  284.31  5418.1  286.61  5450.2   290.6  5457.3  292.59
  5462.6  292.17    5482  294.93  5541.7  296.48  5629.1  297.91  5943.3  301.06
#Mann= 9 ,-1 , 0
  3776.8     .11       0  4588.9     .15       0  4974.5     .09       0
  5026.8     .11       0  5090.7     .15       0  5285.6     .17       0
  5418.1     .11       0  5541.7     .17       0  5629.1     .11       0
Bank Sta=4974.5,5026.8
XS Rating Curve= 0 ,0
Exp/Cntr=0.3,0.1

Type RM Length L Ch R = 1 ,30033   ,571,571,571
BEGIN DESCRIPTION:
Mapping XS 171f1eb6
END DESCRIPTION:
XS GIS Cut Line= 3
      3697800.58     10185311.64      3697014.14     10183431.47
      3696982.89     10182816.88
#Sta/Elev= 30
  3703.4  309.56  3928.5  306.35  4506.2  287.32  4842.7  286.86  4939.4  285.41
  4972.5  284.58  4998.7  281.29  5010.8  281.29  5026.4  284.61    5059  283.28
  5073.1  284.93    5189  283.21  5356.5  284.68  5380.3  283.28  5409.6  284.33
  5427.5  281.98  5438.8  284.44  5449.2   283.4  5470.9  284.88  5520.6   284.3
    5534  284.69  5539.4  283.42  5568.6  284.95    5640  285.19  5761.8   284.1
  5789.8  285.76  5801.9  284.79    5852  286.78  5972.1   296.9  6356.8  298.22
#Mann= 6 ,-1 , 0
  3703.4     .11       0  4939.4     .15       0  4972.5     .09       0
  5026.4     .15       0  5520.6     .17       0  5789.8     .11       0
Bank Sta=4972.5,5026.4
XS Rating Curve= 0 ,0
Exp/Cntr=0.3,0.1

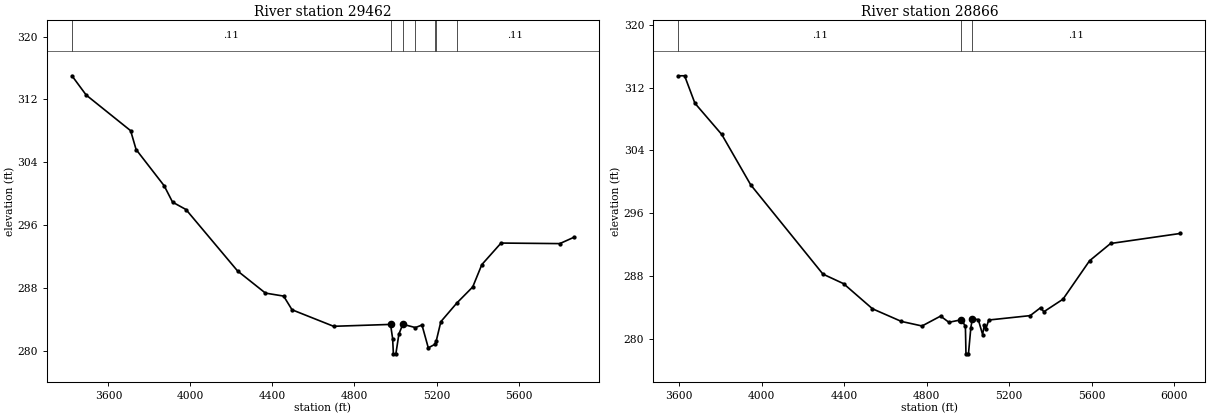
Type RM Length L Ch R = 1 ,29462   ,596,596,596
BEGIN DESCRIPTION:
GARRETTS CREEK 49.0
END DESCRIPTION:
XS GIS Cut Line= 3
      3698017.86     10185461.09      3697691.08      10183917.4
      3697508.93     10183066.88
#Sta/Elev= 30
  3422.1  315.01  3491.6  312.56  3708.3  308.03  3734.9  305.64  3871.9  301.03
  3912.8  298.95  3978.3  298.01  4229.6  290.21  4365.7  287.39  4454.5  287.01
  4495.4  285.27  4698.2  283.17  4975.8  283.41    4986  281.61  4989.7  279.67
  5001.8  279.67  5016.7  282.19  5035.7  283.43  5096.8  283.01  5129.2  283.33
  5159.9  280.43  5192.1  280.88  5198.1  281.24  5221.2  283.76  5299.5  286.14
  5376.6  288.17    5421  291.01  5514.7  293.75  5801.2  293.68  5869.8  294.48
#Mann= 7 ,-1 , 0
  3422.1     .11       0  4975.8     .06       0  5035.7     .15       0
  5096.8     .17       0  5192.1     .15       0  5198.1     .17       0
  5299.5     .11       0
Bank Sta=4975.8,5035.7
XS Rating Curve= 0 ,0
Exp/Cntr=0.3,0.1

Type RM Length L Ch R = 1 ,28866   ,500,500,500
BEGIN DESCRIPTION:
GARRETTS CREEK 48.0
END DESCRIPTION:
XS GIS Cut Line= 3
      3698267.85     10185361.02      3698199.85     10183958.37
      3697624.42      10183104.7
#Sta/Elev= 30
  3595.7  313.52  3625.7  313.52  3675.7  310.02  3805.9  306.04  3946.1  299.63
  4296.5  288.25  4396.6  287.03  4536.8  283.83  4676.9  282.22    4777  281.64
  4867.1   282.9  4907.2  282.11  4967.3  282.43  4987.3  281.62  4990.1  278.09
  5002.2  278.09  5013.7  281.43  5020.9  282.54  5049.7  282.46  5070.7  280.55
  5079.6  281.81  5085.6   281.2  5100.6   282.4  5301.5  282.96  5352.5  283.98
  5367.5  283.45  5460.4  285.05  5589.4  289.95  5691.3  292.15  6029.5  293.43
#Mann= 3 , 0 , 0
  3595.7     .11       0  4967.3     .06       0  5020.9     .11       0
Bank Sta=4967.3,5020.9
XS Rating Curve= 0 ,0
Exp/Cntr=0.3,0.1