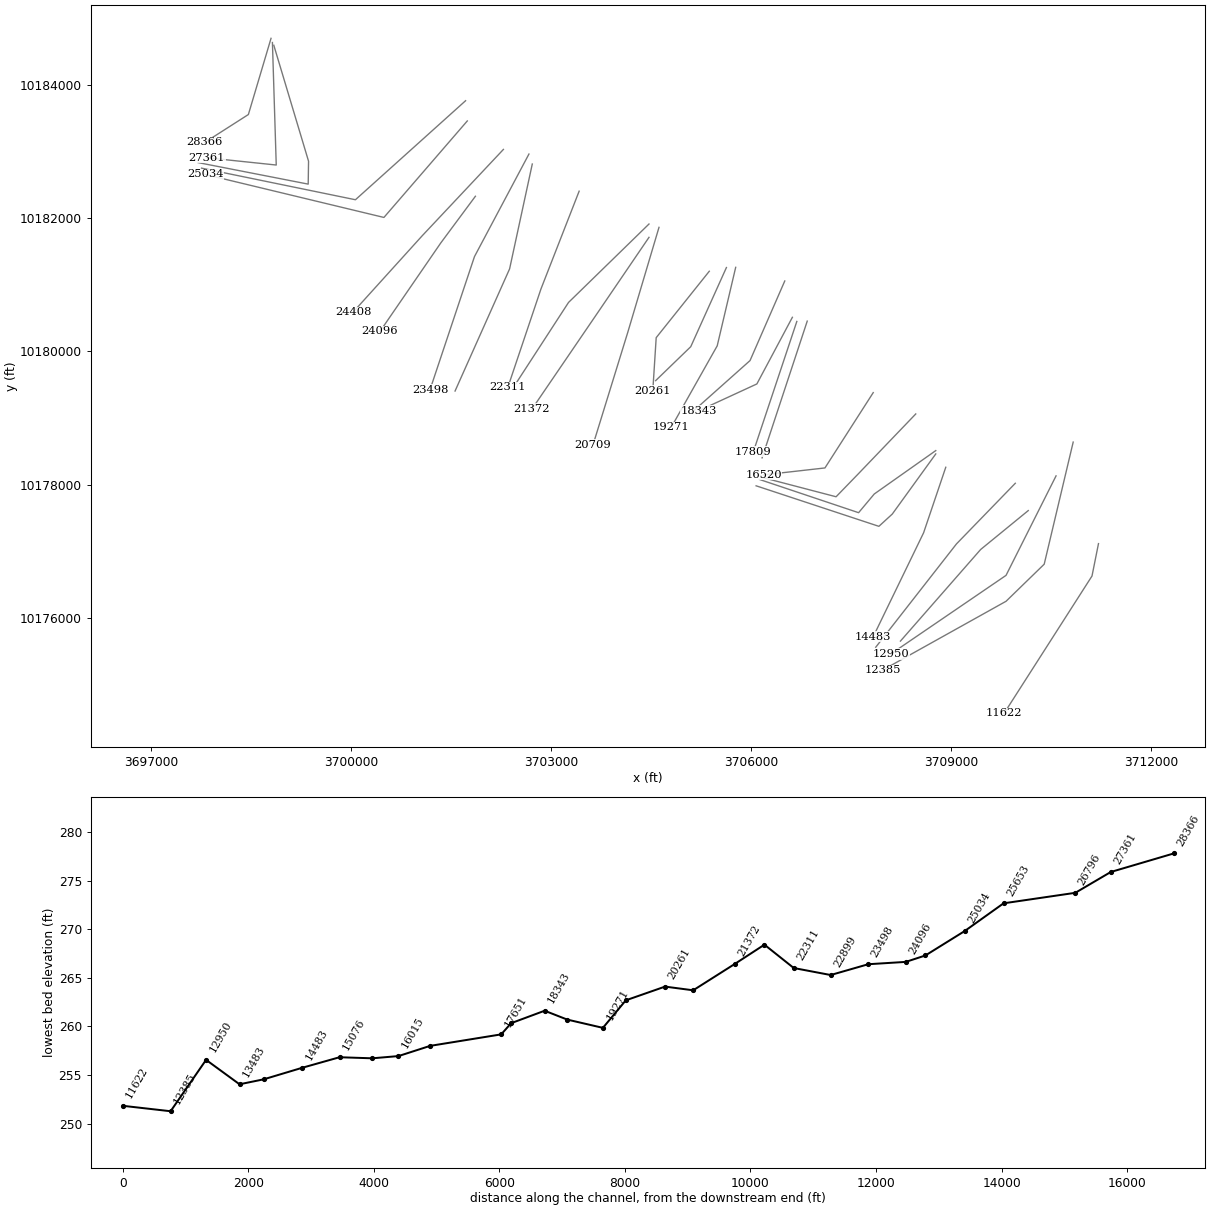
HEC-RAS study GARRETTS CREEK.prj: GARRETTS CREEK Base Level Engineering

--- GARRETTS CREEK.g01 (geometry) --- (continued)

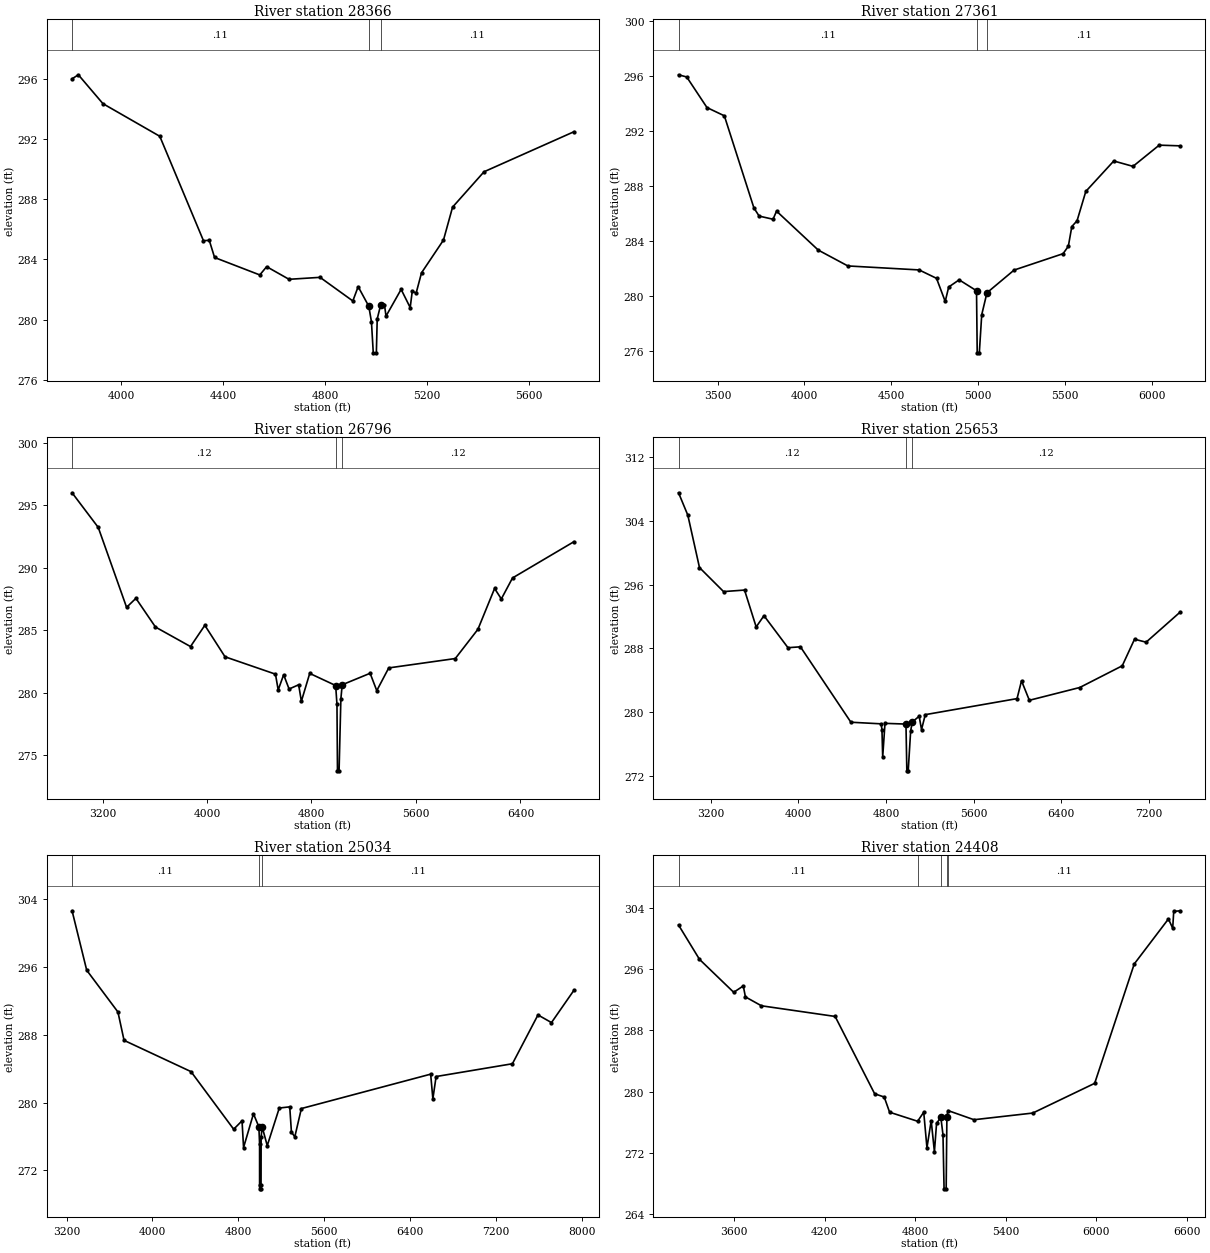
Type RM Length L Ch R = 1 ,28366   ,1005,1005,1005
BEGIN DESCRIPTION:
GARRETTS CREEK 47.0
END DESCRIPTION:
XS GIS Cut Line= 3
       3698800.6     10184697.12      3698460.83     10183553.84
      3697806.99     10183135.35
#Sta/Elev= 30
  3807.3  296.01  3831.9  296.28  3928.4  294.36  4151.5  292.19  4322.8  285.25
  4345.7  285.27  4366.5  284.13  4543.9  282.97  4570.8  283.52  4658.6  282.68
  4780.4  282.81    4909  281.24  4929.9  282.19  4971.6  280.89    4982  279.86
  4989.2  277.79  5001.3  277.79  5004.7  280.05  5017.9  280.95  5033.1  280.99
  5039.2  280.23  5098.5  282.01  5134.1   280.8  5142.2  281.89  5157.4  281.76
  5178.5  283.11  5264.7  285.29  5300.4  287.48  5423.8  289.83  5776.3  292.49
#Mann= 3 , 0 , 0
  3807.3     .11       0  4971.6     .06       0  5017.9     .11       0
Bank Sta=4971.6,5017.9
XS Rating Curve= 0 ,0
Exp/Cntr=0.3,0.1

Type RM Length L Ch R = 1 ,27361   ,565,565,565
BEGIN DESCRIPTION:
GARRETTS CREEK 46.0
END DESCRIPTION:
XS GIS Cut Line= 3
      3698821.43     10184634.56      3698878.72     10182796.05
      3697837.04     10182905.43
#Sta/Elev= 30
  3275.5  296.07  3322.6  295.91  3439.1  293.69  3539.1  293.09  3709.2   286.4
  3739.2  285.81  3819.2  285.58  3839.3  286.17  4079.4  283.34  4249.5  282.19
  4659.7   281.9  4759.7  281.29  4809.7  279.61  4829.7  280.66  4889.8  281.18
  4989.8  280.39  4993.8  275.88  5005.9  275.88  5019.8  278.65  5049.8  280.24
    5206  281.89  5487.8  283.08    5518  283.62  5538.1  285.05  5568.2  285.47
  5618.5   287.6  5779.4  289.81    5890  289.42  6040.8  290.96  6162.3  290.91
#Mann= 3 , 0 , 0
  3275.5     .11       0  4989.8     .07       0  5049.8     .11       0
Bank Sta=4989.8,5049.8
XS Rating Curve= 0 ,0
Exp/Cntr=0.3,0.1

Type RM Length L Ch R = 1 ,26796   ,1143,1143,1143
BEGIN DESCRIPTION:
GARRETTS CREEK 45.0
END DESCRIPTION:
XS GIS Cut Line= 4
      3698842.25     10184592.97      3699363.09     10182853.35
      3699357.89      10182509.6      3697706.88      10182832.5
#Sta/Elev= 30
    2967     296  3167.3  293.23  3384.4  286.83  3455.8  287.55  3605.7  285.25
  3873.8  283.69  3983.5  285.39  4138.1  282.87  4524.3  281.48  4545.2  280.22
    4587  281.43  4628.7  280.29  4701.8  280.63  4722.7  279.31  4786.6  281.54
  4985.2  280.57  4995.2  279.06  4999.1  273.74  5011.3  273.74  5025.2  279.51
  5035.2  280.63    5249  281.55    5300  280.16  5391.7  281.98  5901.1  282.73
  6074.4  285.07  6202.1  288.34  6253.6   287.5  6339.3  289.18    6809  292.08
#Mann= 3 , 0 , 0
    2967     .12       0  4985.2     .08       0  5035.2     .12       0
Bank Sta=4985.2,5035.2
XS Rating Curve= 0 ,0
Exp/Cntr=0.3,0.1

Type RM Length L Ch R = 1 ,25653   ,619,619,619
BEGIN DESCRIPTION:
GARRETTS CREEK 43.0
END DESCRIPTION:
XS GIS Cut Line= 3
      3701717.85     10183761.07      3700066.22     10182275.22
      3697758.92     10182749.18
#Sta/Elev= 30
  2908.2   307.5    2993  304.69  3099.2  298.13  3318.9  295.12  3510.3  295.31
  3616.4  290.69  3687.4   292.1  3906.4  288.09    4020   288.2  4480.4  278.75
  4756.2  278.55  4763.7  277.83  4770.4  274.39  4791.4  278.61  4982.7  278.52
  4990.7  272.66  5003.2  272.66  5025.3  277.61  5039.5  278.77    5103   279.5
  5124.7  277.83  5158.8   279.7  5995.9  281.71  6036.7  283.94  6108.2   281.5
  6567.6   283.1  6955.5  285.82  7067.5  289.15  7173.3  288.78  7485.3  292.57
#Mann= 3 , 0 , 0
  2908.2     .12       0  4982.7     .08       0  5039.5     .12       0
Bank Sta=4982.7,5039.5
XS Rating Curve= 0 ,0
Exp/Cntr=0.3,0.1

Type RM Length L Ch R = 1 ,25034   ,626,626,626
BEGIN DESCRIPTION:
GARRETTS CREEK 42.0
END DESCRIPTION:
XS GIS Cut Line= 3
      3701743.33     10183457.54       3700493.3      10182009.6
      3697811.91     10182655.21
#Sta/Elev= 30
  3251.7  302.64    3388  295.62  3678.6  290.69  3735.7  287.34  4358.8  283.65
  4755.9  276.85  4833.8  277.84    4848  274.69  4940.2  278.67  4990.6  277.13
  4997.2   275.1  4997.3  270.31  4997.8  269.81  5010.3  269.81  5010.8  270.31
  5011.5  275.91 5020.98277.1384  5068.5  274.91  5180.5  279.35  5277.9  279.49
  5293.6  276.51    5325  275.95  5386.2  279.29  6589.6  283.35  6610.2  280.44
  6640.3  283.07  7350.8  284.58  7588.5  290.34  7714.3  289.44  7922.6  293.24
#Mann= 3 , 0 , 0
  3251.7     .11       0  4990.6     .07       0 5020.98     .11       0
Bank Sta=4990.6,5020.98
XS Rating Curve= 0 ,0
Exp/Cntr=0.3,0.1

Type RM Length L Ch R = 1 ,24408   ,312,312,312
BEGIN DESCRIPTION:
GARRETTS CREEK 41.0
END DESCRIPTION:
XS GIS Cut Line= 3
      3702284.98     10183030.44      3701066.22     10181733.55
      3700029.79     10180587.75
#Sta/Elev= 30
  3231.2  301.73  3370.1  297.25  3596.7  292.95  3660.2  293.78  3674.4  292.35
  3780.4  291.19  4268.7   289.8  4530.5  279.71    4594  279.28  4629.7   277.3
  4815.2  276.12  4855.8   277.3  4877.1  272.66  4905.2   276.2  4926.6  272.14
  4940.8  275.84  4969.1  276.64  4983.3  274.37  4990.5   267.3  5004.5   267.3
  5009.2  276.66  5016.1  277.52  5188.8  276.32  5578.1  277.19  5988.4  281.07
  6250.6  296.65    6477  302.52  6505.4  301.32  6512.2  303.51  6555.9  303.59
#Mann= 5 ,-1 , 0
  3231.2     .11       0  4815.2     .15       0  4969.1     .09       0
  5009.2     .15       0  5016.1     .11       0
Bank Sta=4969.1,5009.2
XS Rating Curve= 0 ,0
Exp/Cntr=0.3,0.1

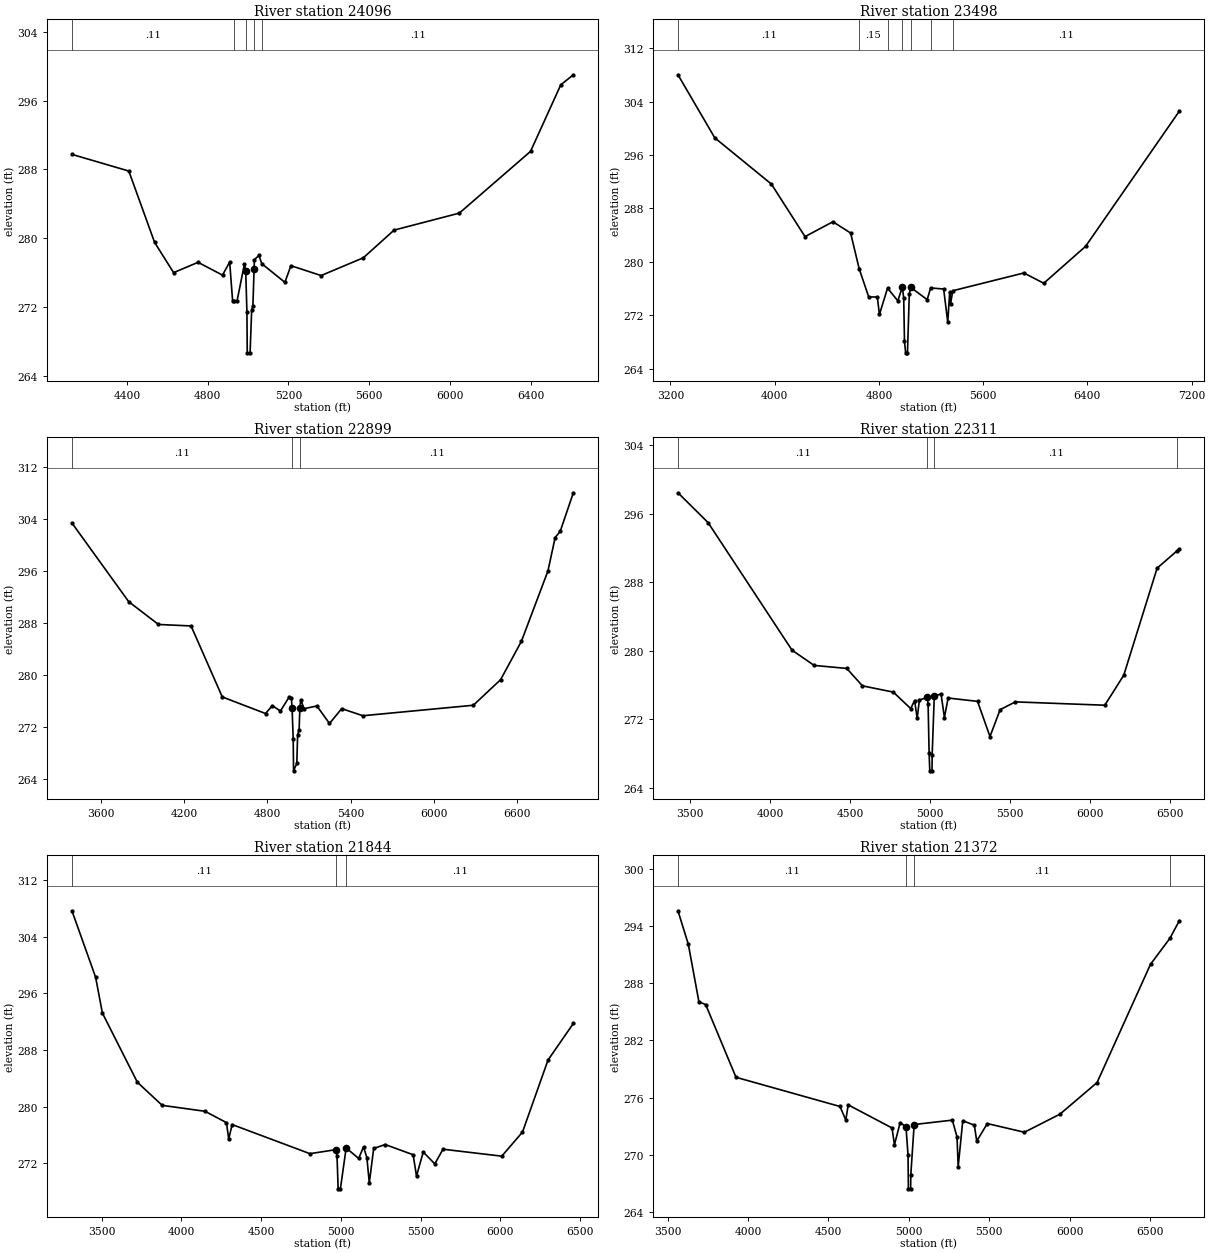
Type RM Length L Ch R = 1 ,24096   ,598,598,598
BEGIN DESCRIPTION:
GARRETTS CREEK 40.0
END DESCRIPTION:
XS GIS Cut Line= 3
      3701864.92     10182327.31      3701345.66      10181626.9
      3700434.36     10180299.52
#Sta/Elev= 30
  4128.1  289.75  4409.7  287.81  4537.5  279.49  4631.4  275.98  4752.5  277.18
  4873.5  275.69  4908.9  277.21  4923.6  272.66    4929  272.71    4945  272.62
    4982  276.99  4988.3  276.22  4994.3  271.43    4996  266.64    5010  266.64
  5017.9  271.63  5023.9  272.08 5029.86276.4373  5031.3  277.49  5053.7  277.98
    5068  277.02  5182.3  274.85  5212.1  276.79  5361.6  275.64  5570.7  277.71
  5722.7  280.93  6045.8  282.91  6398.3   290.1  6547.9  297.85  6610.1  299.02
#Mann= 5 ,-1 , 0
  4128.1     .11       0    4929     .15       0  4988.3     .09       0
 5029.86     .15       0    5068     .11       0
Bank Sta=4988.3,5029.86
XS Rating Curve= 0 ,0
Exp/Cntr=0.3,0.1

Type RM Length L Ch R = 1 ,23498   ,599,599,599
BEGIN DESCRIPTION:
GARRETTS CREEK 39.0
END DESCRIPTION:
XS GIS Cut Line= 3
      3702667.83     10182961.03       3701851.2     10181422.53
      3701184.63     10179425.33
#Sta/Elev= 30
  3258.2     308  3540.8  298.56  3974.9  291.65    4233  283.79  4447.2  286.01
  4582.8  284.33  4648.4  278.99  4721.7  274.77  4787.7  274.75    4804  272.14
  4866.3  276.08    4945  274.18  4979.9  276.23  4990.3  274.58  4996.2   268.1
  5005.1   266.4  5019.1   266.4  5033.2  275.17  5043.7   276.2  5170.2  274.36
  5197.2  276.11  5296.7  275.95  5328.3     271  5343.2  275.46  5349.4  273.68
  5366.7  275.69  5912.1  278.35  6064.9  276.81  6386.2  282.34  7105.5  302.57
#Mann= 7 ,-1 , 0
  3258.2     .11       0  4648.4     .15       0  4866.3     .11       0
  4979.9     .06       0  5043.7     .11       0  5197.2     .15       0
  5366.7     .11       0
Bank Sta=4979.9,5043.7
XS Rating Curve= 0 ,0
Exp/Cntr=0.3,0.1

Type RM Length L Ch R = 1 ,22899   ,588,588,588
BEGIN DESCRIPTION:
GARRETTS CREEK 38.0
END DESCRIPTION:
XS GIS Cut Line= 3
      3702717.85     10182811.08      3702377.62     10181237.44
       3701559.9      10179404.9
#Sta/Elev= 30
    3390  303.39  3799.2   291.3  4014.1  287.79  4249.4  287.56  4474.5  276.65
  4786.3   274.1  4835.5   275.3    4894  274.49  4955.4  276.59    4973  276.45
  4978.1  274.92  4986.1  270.18  4988.6  265.29  5012.1  266.43  5017.9  270.81
  5028.9  271.63 5034.02274.8861  5040.8  276.23    5064  274.84  5156.9  275.26
  5247.9  272.57  5335.8  274.85  5488.8  273.76  6285.2  275.37    6482   279.3
  6632.2   285.2  6823.5  296.01  6875.4  301.14  6912.3  302.12  7006.7  308.03
#Mann= 3 , 0 , 0
    3390     .11       0  4978.1     .06       0 5034.02     .11       0
Bank Sta=4978.1,5034.02
XS Rating Curve= 0 ,0
Exp/Cntr=0.3,0.1

Type RM Length L Ch R = 1 ,22311   ,467,467,467
BEGIN DESCRIPTION:
GARRETTS CREEK 37.0
END DESCRIPTION:
XS GIS Cut Line= 3
      3703420.47     10182403.69      3702848.16       10180937.
      3702351.04     10179459.28
#Sta/Elev= 30
  3425.6  298.43  3613.9  294.95  4138.3  280.08  4276.8   278.3  4480.4  277.95
  4578.4  275.92  4771.3  275.19    4880  273.27  4904.5  274.21  4920.5  272.12
  4934.3  274.26  4983.3  274.58  4988.7  273.83  4995.1  268.09  4999.3  266.01
  5013.3  266.01  5014.1  267.87  5027.4  274.69  5069.6  274.99  5090.7  272.22
  5113.9   274.5  5297.7  274.11  5375.5  270.01  5438.8  273.14  5533.8  274.05
    6093  273.66  6211.4  277.15    6420  289.64  6543.3  291.64  6559.1  291.85
#Mann= 4 ,-1 , 0
  3425.6     .11       0  4983.3     .06       0  5027.4     .11       0
  6543.3     .17       0
Bank Sta=4983.3,5027.4
XS Rating Curve= 0 ,0
Exp/Cntr=0.3,0.1

Type RM Length L Ch R = 1 ,21844   ,472,472,472
BEGIN DESCRIPTION:
GARRETTS CREEK 36.0
END DESCRIPTION:
XS GIS Cut Line= 3
      3704467.87     10181911.09      3703261.31     10180734.17
      3702467.87      10179511.1
#Sta/Elev= 30
  3314.5  307.64  3463.1  298.26  3505.5  293.21  3724.7  283.45  3880.3  280.19
    4149  279.35  4283.3  277.75  4297.5  275.43  4318.8  277.48  4806.7  273.37
  4969.3  273.94  4976.4  273.03  4983.6  268.41  4997.6  268.41  5033.7  274.18
  5112.2   272.7  5142.5  274.32  5163.6  272.83  5178.7  269.25  5206.3  274.11
  5278.3  274.66  5453.6  273.22  5474.7  270.21  5516.9   273.6  5589.4  271.93
  5640.8     274  6009.3  273.02  6139.2  276.42  6299.4  286.59  6457.9  291.74
#Mann= 3 , 0 , 0
  3314.5     .11       0  4969.3     .06       0  5033.7     .11       0
Bank Sta=4969.3,5033.7
XS Rating Curve= 0 ,0
Exp/Cntr=0.3,0.1

Type RM Length L Ch R = 1 ,21372   ,663,663,663
BEGIN DESCRIPTION:
GARRETTS CREEK 35.0
END DESCRIPTION:
XS GIS Cut Line= 3
      3704467.87      10181711.1      3703663.53     10180528.69
      3702713.59     10179134.99
#Sta/Elev= 30
  3564.7  295.57  3629.1  292.05  3694.9  286.03  3736.9  285.74  3925.4  278.12
  4571.9  275.06  4607.9  273.64  4622.8  275.23  4895.2  272.81  4910.2  271.05
  4946.1  273.38    4982  272.92  4994.8  269.96    4997  266.43    5011  266.43
  5011.9  267.88  5032.8  273.17  5270.2  273.63  5299.1  271.87  5306.5  268.76
    5335  273.57  5406.9   273.1  5421.8  271.43  5487.6  273.27  5717.9  272.36
  5939.4  274.26  6169.8  277.57  6501.9  289.96  6623.1   292.7  6681.4  294.54
#Mann= 4 ,-1 , 0
  3564.7     .11       0    4982     .06       0  5032.8     .11       0
  6623.1     .17       0
Bank Sta=4982,5032.8
XS Rating Curve= 0 ,0
Exp/Cntr=0.3,0.1

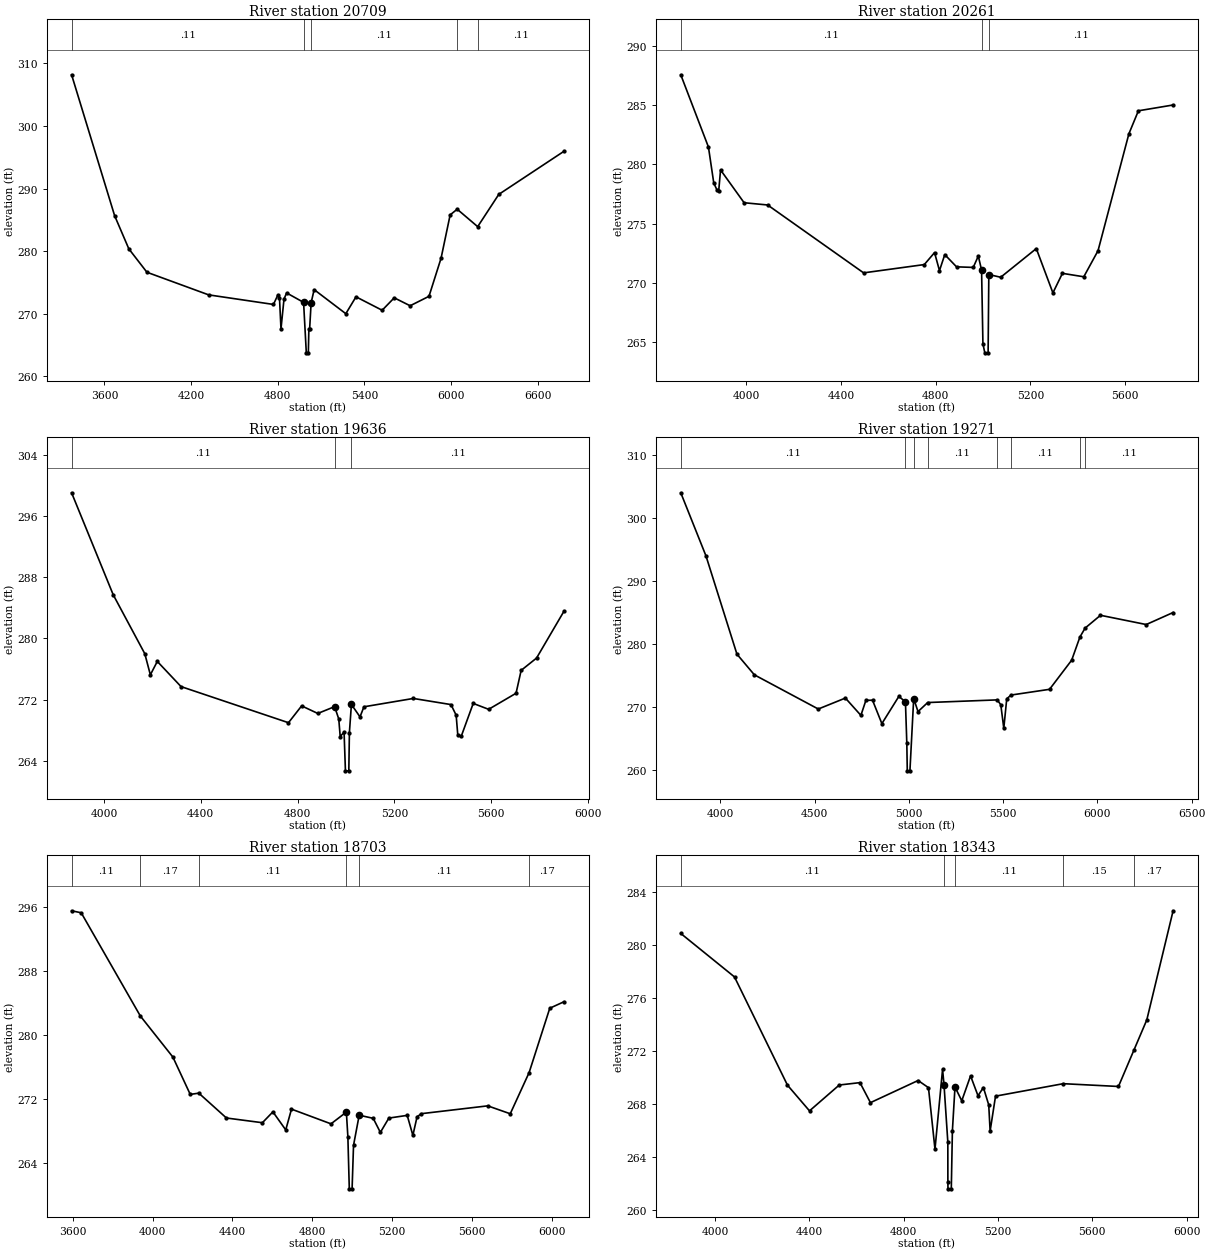
Type RM Length L Ch R = 1 ,20709   ,448,448,448
BEGIN DESCRIPTION:
GARRETTS CREEK 34.0
END DESCRIPTION:
XS GIS Cut Line= 3
      3704617.86     10181861.09      3704149.64     10180285.64
      3703628.81     10178598.14
#Sta/Elev= 30
  3372.4  308.19  3670.3  285.66  3768.8  280.35    3894  276.61  4321.8  272.99
  4770.3  271.46  4801.6  273.01  4812.1  272.52  4822.5  267.55  4843.4  272.32
  4861.6   273.3    4979  271.79  4997.9  263.72  5011.9  263.72  5015.7  267.58
    5021  267.58  5031.2  271.72  5052.1  273.83  5271.5  269.98    5342  272.68
  5523.1  270.53  5606.8  272.52  5716.9  271.25  5847.5  272.76  5931.2  278.86
    5994  285.78  6042.8  286.69  6184.7   283.9  6330.8  289.06    6782  295.95
#Mann= 5 ,-1 , 0
  3372.4     .11       0    4979     .06       0  5031.2     .11       0
  6042.8     .17       0  6184.7     .11       0
Bank Sta=4979,5031.2
XS Rating Curve= 0 ,0
Exp/Cntr=0.3,0.1

Type RM Length L Ch R = 1 ,20261   ,625,625,625
BEGIN DESCRIPTION:
GARRETTS CREEK 33.0
END DESCRIPTION:
XS GIS Cut Line= 3
      3705371.85     10181202.28      3704575.77     10180205.71
      3704524.71     10179404.83
#Sta/Elev= 30
  3724.5  287.57  3841.3  281.47  3863.8  278.43  3878.2  277.81  3884.6  277.76
  3892.4  279.54  3991.8  276.77  4091.1  276.58  4496.2  270.85  4752.3  271.55
  4795.6  272.56  4816.4  271.04  4838.8  272.39  4888.4  271.36  4958.9  271.31
  4980.3  272.27  4994.1  271.09  4999.8  264.87  5007.7   264.1  5021.7   264.1
  5024.7  270.71  5074.8  270.48  5225.1   272.9  5295.2  269.16  5335.3  270.81
  5425.5  270.52  5485.6  272.72  5615.9  282.59    5656  284.53  5802.5  285.02
#Mann= 3 , 0 , 0
  3724.5     .11       0  4994.1     .06       0  5024.7     .11       0
Bank Sta=4994.1,5024.7
XS Rating Curve= 0 ,0
Exp/Cntr=0.3,0.1

Type RM Length L Ch R = 1 ,19636   ,365,365,365
BEGIN DESCRIPTION:
GARRETTS CREEK 32.0
END DESCRIPTION:
XS GIS Cut Line= 3
      3705628.82      10181257.9      3705094.08     10180070.36
      3704567.85     10179561.07
#Sta/Elev= 30
  3866.2  299.03  4038.2   285.7  4168.7     278  4191.7  275.24  4220.4  276.99
  4318.5   273.7  4762.5  268.98  4816.9  271.18  4883.7  270.19  4953.2  271.08
  4970.4  269.46  4976.3  267.17  4992.3  267.76  4997.9  262.69  5011.9  262.69
  5014.3  267.69  5022.6  271.37  5058.1  269.74  5074.4  271.06  5278.5  272.15
  5434.1  271.35  5455.5  269.96  5462.4  267.31  5476.6  267.21    5526   271.5
  5589.8  270.73    5703  272.83  5724.1  275.82  5787.8  277.43  5900.9  283.54
#Mann= 3 , 0 , 0
  3866.2     .11       0  4953.2     .06       0  5022.6     .11       0
Bank Sta=4953.2,5022.6
XS Rating Curve= 0 ,0
Exp/Cntr=0.3,0.1

Type RM Length L Ch R = 1 ,19271   ,568,568,568
BEGIN DESCRIPTION:
GARRETTS CREEK 31.0
END DESCRIPTION:
XS GIS Cut Line= 3
      3705767.86     10181261.11      3705490.87     10180083.35
      3704802.61     10178862.37
#Sta/Elev= 30
  3790.1  304.03  3923.7  294.01  4088.1  278.39  4180.5  275.11  4519.5  269.68
  4663.3  271.42  4745.5  268.67  4772.1  271.06  4807.2  271.08  4856.8  267.36
  4946.8  271.68  4981.8  270.83  4989.1  264.24  4991.6  259.86  5005.6  259.86
  5025.6  271.35  5048.5  269.27  5099.9  270.71  5468.5  271.13  5487.6  270.36
  5503.5  266.62  5519.2  271.31  5542.1   271.9  5746.2  272.81  5863.6  277.44
  5907.2  281.11  5934.7  282.53  6016.4  284.57  6259.1   283.1  6401.6  285.01
#Mann= 8 ,-1 , 0
  3790.1     .11       0  4981.8     .09       0  5025.6     .15       0
  5099.9     .11       0  5468.5     .15       0  5542.1     .11       0
  5907.2     .17       0  5934.7     .11       0
Bank Sta=4981.8,5025.6
XS Rating Curve= 0 ,0
Exp/Cntr=0.3,0.1

Type RM Length L Ch R = 1 ,18703   ,360,360,360
BEGIN DESCRIPTION:
GARRETTS CREEK 30.0
END DESCRIPTION:
XS GIS Cut Line= 3
       3706503.8     10181056.46      3705982.97     10179862.03
      3705112.71     10179086.24
#Sta/Elev= 30
  3593.3  295.49  3641.5  295.24    3938  282.33  4101.3  277.19  4188.3  272.52
  4231.2  272.68  4369.8  269.57  4550.1  268.98  4602.8  270.34  4667.2  268.08
    4696  270.68  4894.1  268.84  4971.2  270.31  4978.7  267.24  4985.9  260.71
  4999.9  260.71  5007.1  266.15  5035.5  269.92  5105.8  269.53  5141.7  267.77
  5184.3  269.56  5276.3   269.9  5304.7   267.4  5325.6  269.71  5346.6  270.11
  5680.1  271.09    5793   270.1  5887.6  275.25  5991.2   283.3  6062.2  284.11
#Mann= 6 ,-1 , 0
  3593.3     .11       0    3938     .17       0  4231.2     .11       0
  4971.2     .06       0  5035.5     .11       0  5887.6     .17       0
Bank Sta=4971.2,5035.5
XS Rating Curve= 0 ,0
Exp/Cntr=0.3,0.1

Type RM Length L Ch R = 1 ,18343   ,534,534,534
BEGIN DESCRIPTION:
GARRETTS CREEK 29.0
END DESCRIPTION:
XS GIS Cut Line= 3
      3706617.87      10180511.1       3706085.4     10179511.33
      3705217.81     10179111.05
#Sta/Elev= 30
  3854.8  280.88  4082.7   277.6  4307.3  269.44  4400.8   267.5    4527  269.45
  4614.8  269.63  4659.3  268.12  4861.4  269.79  4905.4  269.25    4933  264.61
  4965.2  270.63  4971.3  269.47  4987.5  265.15  4987.7  262.12  4988.2  261.62
  5002.2  261.62  5006.9  266.01  5017.9   269.3  5046.6  268.26  5083.9  270.14
  5115.5  268.64  5138.4  269.26    5161  267.95  5166.9  265.98  5189.8  268.61
    5477  269.55  5711.2  269.34    5777  272.09  5831.4  274.36    5943  282.59
#Mann= 5 ,-1 , 0
  3854.8     .11       0  4971.3     .06       0  5017.9     .11       0
    5477     .15       0    5777     .17       0
Bank Sta=4971.3,5017.9
XS Rating Curve= 0 ,0
Exp/Cntr=0.3,0.1

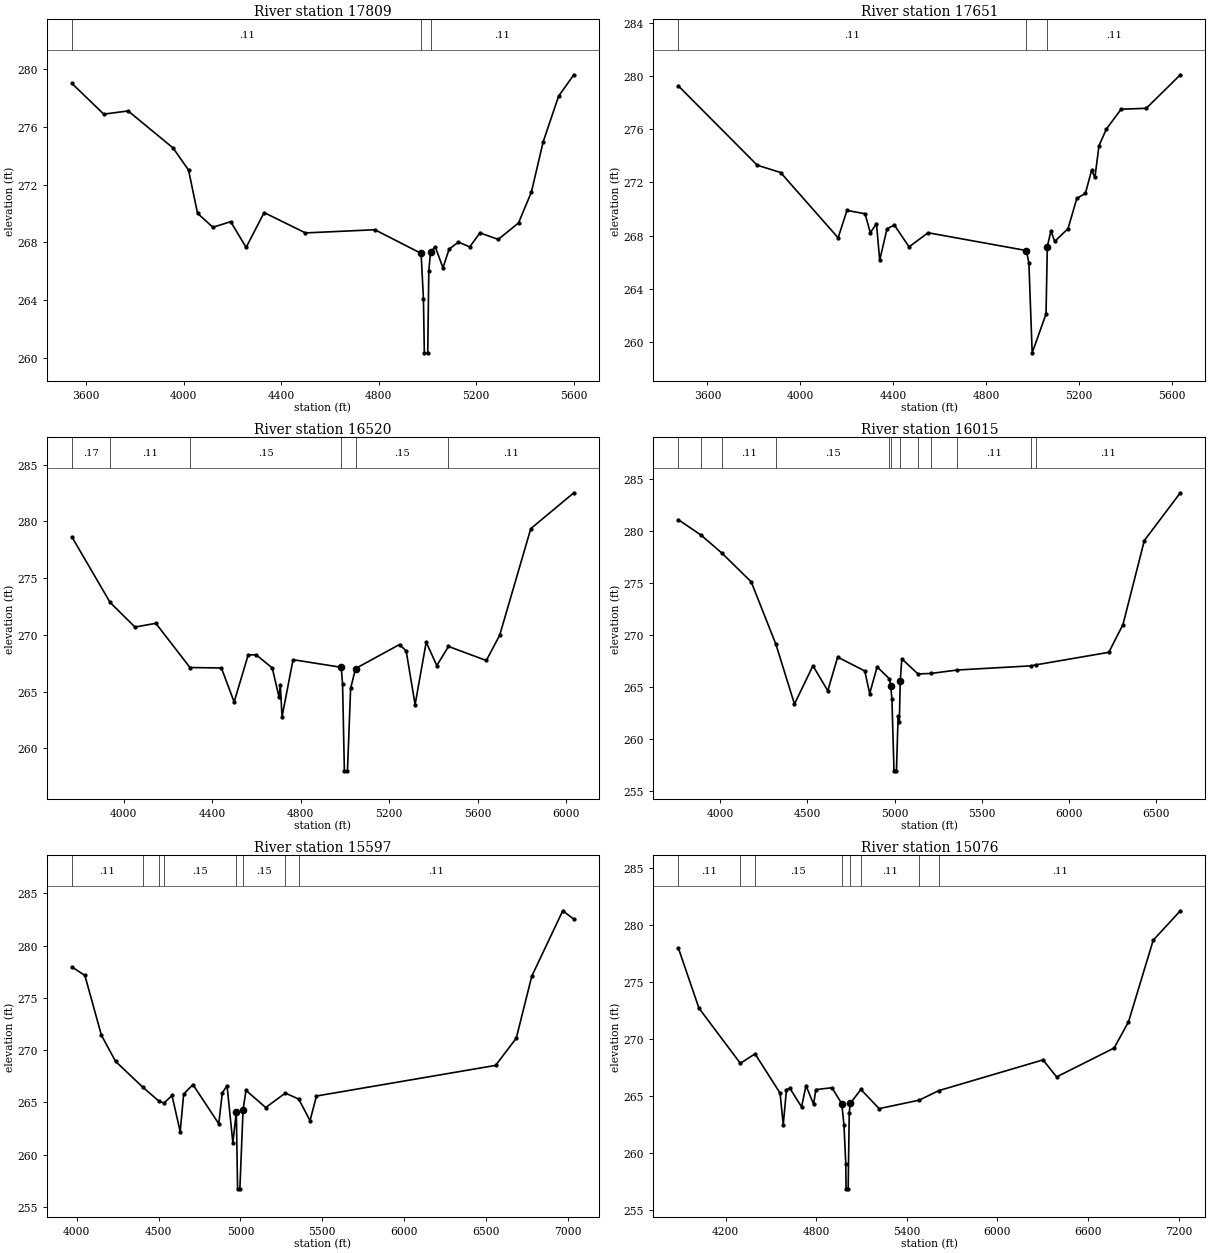
Type RM Length L Ch R = 1 ,17809   ,158,158,158
BEGIN DESCRIPTION:
Mapping XS 2e27e6fc
END DESCRIPTION:
XS GIS Cut Line= 2
      3706684.36     10180448.82      3706033.37     10178495.86
#Sta/Elev= 30
  3541.8  279.03  3672.1   276.9  3772.3  277.12  3956.7  274.55    4020  273.02
  4056.9  270.02  4120.1  269.05    4193  269.44  4256.2  267.65    4330  270.07
  4499.6  268.66  4784.2  268.88  4973.9  267.24  4983.5  264.07  4987.1  260.34
  5001.1  260.34  5005.5  266.04 5012.61  267.33  5031.9   267.7  5063.5  266.24
  5088.9  267.54  5126.8  268.02  5173.3  267.69  5215.4  268.66  5290.2  268.21
  5373.5  269.35  5426.3   271.5  5474.6  274.98  5537.9  278.15  5600.4  279.63
#Mann= 3 , 0 , 0
  3541.8     .11       0  4973.9     .06       0 5012.61     .11       0
Bank Sta=4973.9,5012.61
XS Rating Curve= 0 ,0
Exp/Cntr=0.3,0.1

Type RM Length L Ch R = 1 ,17651   ,1131,1131,1131
BEGIN DESCRIPTION:
Mapping XS 0dbecfff
END DESCRIPTION:
XS GIS Cut Line= 2
      3706840.62     10180454.07      3706163.54     10178401.99
#Sta/Elev= 30
  3475.3  279.26  3814.7   273.3  3915.2  272.75  4162.9  267.84    4201   269.9
  4278.8  269.65  4301.5  268.22    4328   268.9  4341.9  266.16  4373.5  268.52
  4405.1   268.8  4468.3  267.16  4550.3  268.22  4973.8  266.88  4984.3  265.92
  4998.4  259.19    5058  262.11  5063.6  267.18  5079.1  268.36  5095.4  267.57
  5152.8  268.53  5190.6  270.81  5227.6  271.18  5254.1  272.91  5268.6  272.39
  5285.9  274.76  5317.6  276.01  5381.1  277.51  5489.7  277.58  5636.2   280.1
#Mann= 3 , 0 , 0
  3475.3     .11       0  4973.8     .06       0  5063.6     .11       0
Bank Sta=4973.8,5063.6
XS Rating Curve= 0 ,0
Exp/Cntr=0.3,0.1

Type RM Length L Ch R = 1 ,16520   ,505,505,505
BEGIN DESCRIPTION:
GARRETTS CREEK 28.0
END DESCRIPTION:
XS GIS Cut Line= 3
      3707830.18     10179381.11      3707106.24     10178250.91
      3706184.38     10178146.75
#Sta/Elev= 30
  3765.4  278.63    3938  272.86  4050.5  270.69  4144.7  271.02  4299.2  267.12
  4441.4  267.08  4498.9  264.08  4562.4  268.23  4598.7  268.24  4671.4  267.08
  4701.8  264.52  4707.8   265.6  4715.5  262.77  4765.3  267.81  4983.4  267.14
  4989.3  265.65  4997.5  258.01  5011.5  258.01  5025.7  265.28    5048  267.03
  5246.8  269.15    5277  268.58  5317.3  263.85  5367.6  269.36  5415.4  267.29
  5468.3  268.98  5639.3  267.74  5699.7  269.96  5840.6  279.37  6035.3  282.53
#Mann= 6 ,-1 , 0
  3765.4     .17       0    3938     .11       0  4299.2     .15       0
  4983.4     .09       0    5048     .15       0  5468.3     .11       0
Bank Sta=4983.4,5048
XS Rating Curve= 0 ,0
Exp/Cntr=0.3,0.1

Type RM Length L Ch R = 1 ,16015   ,418,418,418
BEGIN DESCRIPTION:
GARRETTS CREEK 27.0
END DESCRIPTION:
XS GIS Cut Line= 4
      3708467.85     10179061.07      3707606.24     10178162.37
      3707273.07     10177818.49      3706158.34     10178110.28
#Sta/Elev= 30
  3760.7  281.09  3890.5  279.61  4010.1  277.88  4177.9  275.12  4319.6  269.11
  4425.7  263.38  4531.7  267.06  4616.6  264.65  4673.2  267.89  4828.5  266.56
  4856.8  264.39  4899.3  266.95  4970.1   265.8  4977.3  265.16  4984.2  263.83
  4996.1  256.96  5010.1  256.96  5019.7  262.22  5026.7  261.63 5031.74265.5572
  5040.8  267.72  5133.9  266.27  5208.2  266.32  5359.2  266.65  5782.5  267.05
    5811  267.15  6227.1  268.35    6308  271.01  6430.6  279.09  6636.8  283.68
#Mann= 12 ,-1 , 0
  3760.7     .11       0  3890.5     .17       0  4010.1     .11       0
  4319.6     .15       0  4970.1     .12       0  4977.3     .09       0
 5031.74     .15       0  5133.9     .17       0  5208.2     .15       0
  5359.2     .11       0  5782.5     .17       0    5811     .11       0
Bank Sta=4977.3,5031.74
XS Rating Curve= 0 ,0
Exp/Cntr=0.3,0.1

Type RM Length L Ch R = 1 ,15597   ,521,521,521
BEGIN DESCRIPTION:
GARRETTS CREEK 26.0
END DESCRIPTION:
XS GIS Cut Line= 4
      3708767.86     10178511.08      3707845.82     10177860.29
      3707610.68     10177579.53      3706122.31     10178078.89
#Sta/Elev= 30
  3971.2  277.95    4050  277.15    4151  271.43  4237.2  268.93  4403.3  266.46
    4500  265.15  4532.5  264.93    4582  265.66  4632.2   262.2  4653.4   265.8
    4710   266.7  4867.6  262.96  4889.2   265.9  4918.1  266.61  4953.8  261.13
  4974.9  264.11  4982.5  256.73  4996.5  256.73 5016.03264.2862  5033.9  266.15
  5154.3  264.51  5274.4  265.89  5356.3  265.31  5424.9  263.25  5464.3  265.61
  6558.1  268.54  6684.2  271.14  6778.9  277.07  6968.1  283.33  7035.9  282.53
#Mann= 8 ,-1 , 0
  3971.2     .11       0  4403.3     .15       0    4500     .17       0
  4532.5     .15       0  4974.9     .09       0 5016.03     .15       0
  5274.4     .17       0  5356.3     .11       0
Bank Sta=4974.9,5016.03
XS Rating Curve= 0 ,0
Exp/Cntr=0.3,0.1

Type RM Length L Ch R = 1 ,15076   ,593,593,593
BEGIN DESCRIPTION:
GARRETTS CREEK 25.0
END DESCRIPTION:
XS GIS Cut Line= 4
      3708767.87      10178461.1      3708115.99      10177559.1
      3707914.94     10177374.85      3706074.06     10177982.89
#Sta/Elev= 30
  3887.1  277.93  4022.9  272.68  4297.3  267.84  4394.6  268.67  4560.5  265.23
  4581.4  262.45  4602.7  265.54  4625.5  265.65  4702.8  264.02  4732.2  265.89
  4782.5  264.25  4797.2  265.54    4904   265.7    4969  264.31  4983.7  262.41
  4995.7     259  4997.4  256.84  5011.4  256.84  5018.6  263.51  5025.3  264.32
  5095.6  265.55  5216.5  263.87  5481.4  264.61    5612  265.45  6301.9  268.14
  6391.9  266.65  6772.8  269.18    6868  271.47  7031.9  278.63  7211.4  281.21
#Mann= 8 ,-1 , 0
  3887.1     .11       0  4297.3     .17       0  4394.6     .15       0
    4969     .09       0  5025.3     .15       0  5095.6     .11       0
  5481.4     .15       0    5612     .11       0
Bank Sta=4969,5025.3
XS Rating Curve= 0 ,0
Exp/Cntr=0.3,0.1

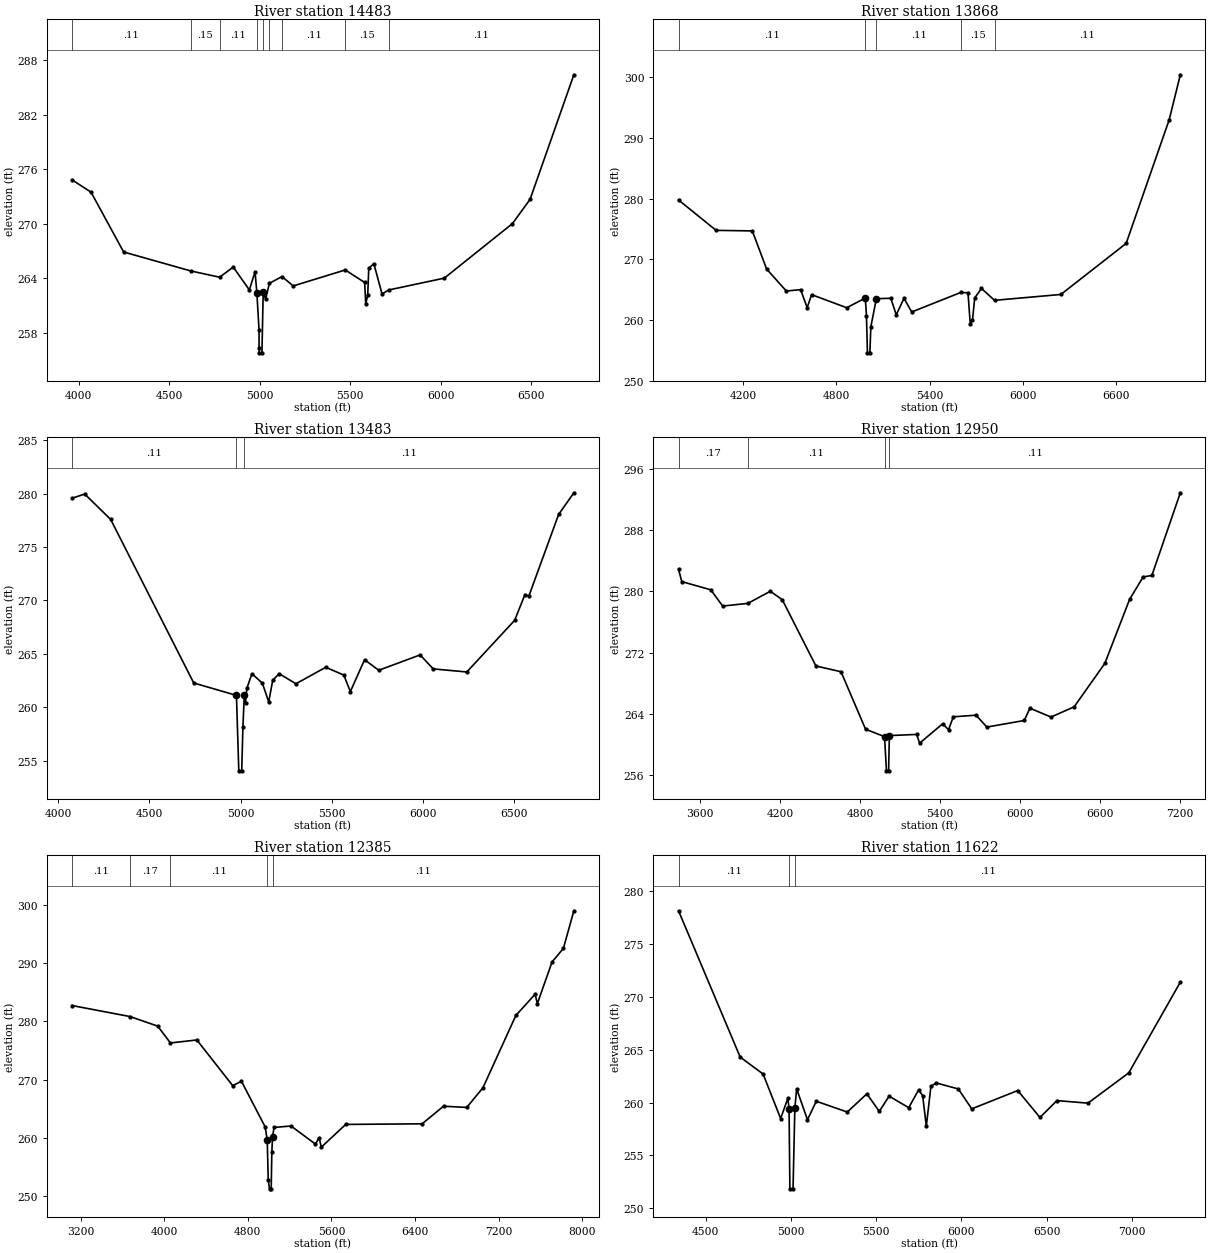
Type RM Length L Ch R = 1 ,14483   ,615,615,615
BEGIN DESCRIPTION:
GARRETTS CREEK 24.0
END DESCRIPTION:
XS GIS Cut Line= 3
      3708917.85     10178261.06       3708585.4     10177277.82
      3707828.64     10175715.69
#Sta/Elev= 30
  3963.4  274.81  4068.2  273.46  4248.4  266.87  4619.8  264.78  4779.2  264.09
  4854.3  265.21  4943.3  262.69  4974.8  264.69 4984.82262.3815    4997  258.26
  4997.1  256.26  4997.6  255.76  5012.9  255.76  5019.9  262.43  5033.4  261.68
  5054.1  263.42  5123.8  264.16  5185.9  263.13  5473.4  264.89  5580.8  263.51
  5586.6  261.13  5597.7  262.15  5603.4  265.07  5631.5  265.59  5676.7  262.24
  5712.9  262.68    6021  263.99  6397.8     270  6495.1  272.67  6737.1  286.39
#Mann= 9 ,-1 , 0
  3963.4     .11       0  4619.8     .15       0  4779.2     .11       0
 4984.82     .06       0  5019.9     .11       0  5054.1     .15       0
  5123.8     .11       0  5473.4     .15       0  5712.9     .11       0
Bank Sta=4984.82,5019.9
XS Rating Curve= 0 ,0
Exp/Cntr=0.3,0.1

Type RM Length L Ch R = 1 ,13868   ,385,385,385
BEGIN DESCRIPTION:
GARRETTS CREEK 23.0
END DESCRIPTION:
XS GIS Cut Line= 3
      3709960.44     10178020.92      3709078.46     10177111.16
      3707867.86     10175561.08
#Sta/Elev= 30
  3782.6  279.78  4024.7  274.77  4258.1  274.68  4350.1   268.4  4477.5  264.76
  4569.3     265  4611.7  262.01    4640  264.17  4866.4  262.01  4986.5  263.61
  4993.7  260.69    5000  254.57  5015.7  254.57    5022  258.86  5057.5   263.5
  5150.6  263.57  5185.9  260.84  5235.7  263.56  5285.4  261.31  5601.8  264.53
  5648.1  264.47  5662.6  259.35    5677  259.96  5691.5  263.63  5734.9  265.19
  5819.1  263.23  6246.8   264.2  6667.4  272.62  6945.1  293.04  7016.5  300.43
#Mann= 5 ,-1 , 0
  3782.6     .11       0  4986.5     .06       0  5057.5     .11       0
  5601.8     .15       0  5819.1     .11       0
Bank Sta=4986.5,5057.5
XS Rating Curve= 0 ,0
Exp/Cntr=0.3,0.1

Type RM Length L Ch R = 1 ,13483   ,533,533,533
BEGIN DESCRIPTION:
GARRETTS CREEK 22.0
END DESCRIPTION:
XS GIS Cut Line= 3
      3710154.88     10177611.18      3709440.62     10177027.05
      3708238.19     10175652.84
#Sta/Elev= 30
  4077.3  279.57  4146.5  279.96  4288.7  277.59  4743.8  262.28  4977.7  261.12
  4990.6  254.06  5006.6  254.06  5013.2   258.2  5020.8  261.17  5027.4  260.39
  5034.5  261.77  5062.5  263.15  5119.5  262.27  5154.6  260.51  5176.4  262.53
  5211.6  263.15  5303.6  262.21  5466.9  263.75    5566  263.02  5601.6  261.47
  5679.5  264.46  5757.3  263.47  5984.1  264.91  6055.3   263.6  6239.5  263.31
  6501.4  268.14  6558.4  270.56  6579.2   270.4  6742.5  278.05    6826  280.08
#Mann= 3 , 0 , 0
  4077.3     .11       0  4977.7     .06       0  5020.8     .11       0
Bank Sta=4977.7,5020.8
XS Rating Curve= 0 ,0
Exp/Cntr=0.3,0.1

Type RM Length L Ch R = 1 ,12950   ,565,565,565
BEGIN DESCRIPTION:
GARRETTS CREEK 21.0
END DESCRIPTION:
XS GIS Cut Line= 3
      3710571.52       10178132.      3709821.51     10176638.94
      3708092.59     10175458.54
#Sta/Elev= 30
  3438.7  282.87  3462.9  281.26  3680.6  280.19  3769.9  278.07    3959  278.42
  4127.2     280  4216.5  278.91  4469.3  270.25  4657.5   269.5  4841.7     262
  4984.1  261.03  4998.4  256.57  5014.5  256.57  5020.4  261.17    5225  261.32
  5247.2  260.18  5419.4   262.7  5464.2  261.94  5500.1  263.62    5671  263.83
  5751.4  262.28  6032.5  263.14  6074.5  264.74    6233  263.59  6406.4  264.92
  6636.7  270.59  6822.3  278.93  6923.9  281.87  6989.6  282.06    7203  292.85
#Mann= 4 ,-1 , 0
  3438.7     .17       0    3959     .11       0  4984.1     .06       0
  5020.4     .11       0
Bank Sta=4984.1,5020.4
XS Rating Curve= 0 ,0
Exp/Cntr=0.3,0.1

Type RM Length L Ch R = 1 ,12385   ,763,763,763
BEGIN DESCRIPTION:
GARRETTS CREEK 20.0
END DESCRIPTION:
XS GIS Cut Line= 4
      3710828.47     10178638.98      3710393.87     10176806.82
      3709821.51     10176250.05      3707967.99     10175215.68
#Sta/Elev= 30
    3117   282.7    3673  280.81  3937.1  279.17  4058.8  276.29  4311.7   276.8
  4654.6  268.98  4738.7  269.72  4965.5  261.91  4985.4  259.66  4995.2  252.78
  5007.3  251.29  5023.4  251.29  5029.5  257.54  5036.5  260.24  5050.7  261.81
  5213.4  262.06  5446.8  258.96  5482.2  260.05  5503.3  258.43  5736.7  262.33
    6468  262.43  6673.6  265.45  6895.3  265.24  7050.9  268.62    7366     281
    7550  284.64  7571.7  283.03  7712.2  290.17  7820.8  292.49  7921.1  298.94
#Mann= 5 ,-1 , 0
    3117     .11       0    3673     .17       0  4058.8     .11       0
  4985.4     .06       0  5036.5     .11       0
Bank Sta=4985.4,5036.5
XS Rating Curve= 0 ,0
Exp/Cntr=0.3,0.1

Type RM Length L Ch R = 1 ,11622   ,540,540,540
BEGIN DESCRIPTION:
GARRETTS CREEK 18.0
END DESCRIPTION:
XS GIS Cut Line= 3
      3711207.81     10177115.54      3711110.58     10176629.39
        3709792.     10174568.25
#Sta/Elev= 30
  4341.5   278.1    4703  264.29  4837.3  262.69  4940.3  258.49  4982.6   260.4
  4989.6   259.4  4994.5  251.85    5013  251.85 5023.55259.4719  5034.2  261.29
  5097.6  258.37  5149.2  260.12    5331   259.1    5446  260.82  5518.8  259.16
  5576.3   260.6  5691.3  259.51  5749.4  261.19  5773.1  260.65  5794.5  257.76
  5821.5  261.52    5852  261.85  5982.2  261.28  6060.9   259.4  6330.6  261.13
  6460.9  258.59  6560.7  260.18  6742.5  259.94  6981.8   262.8  7284.1  271.36
#Mann= 3 , 0 , 0
  4341.5     .11       0  4989.6     .06       0 5023.55     .11       0
Bank Sta=4989.6,5023.55
XS Rating Curve= 0 ,0
Exp/Cntr=0.3,0.1