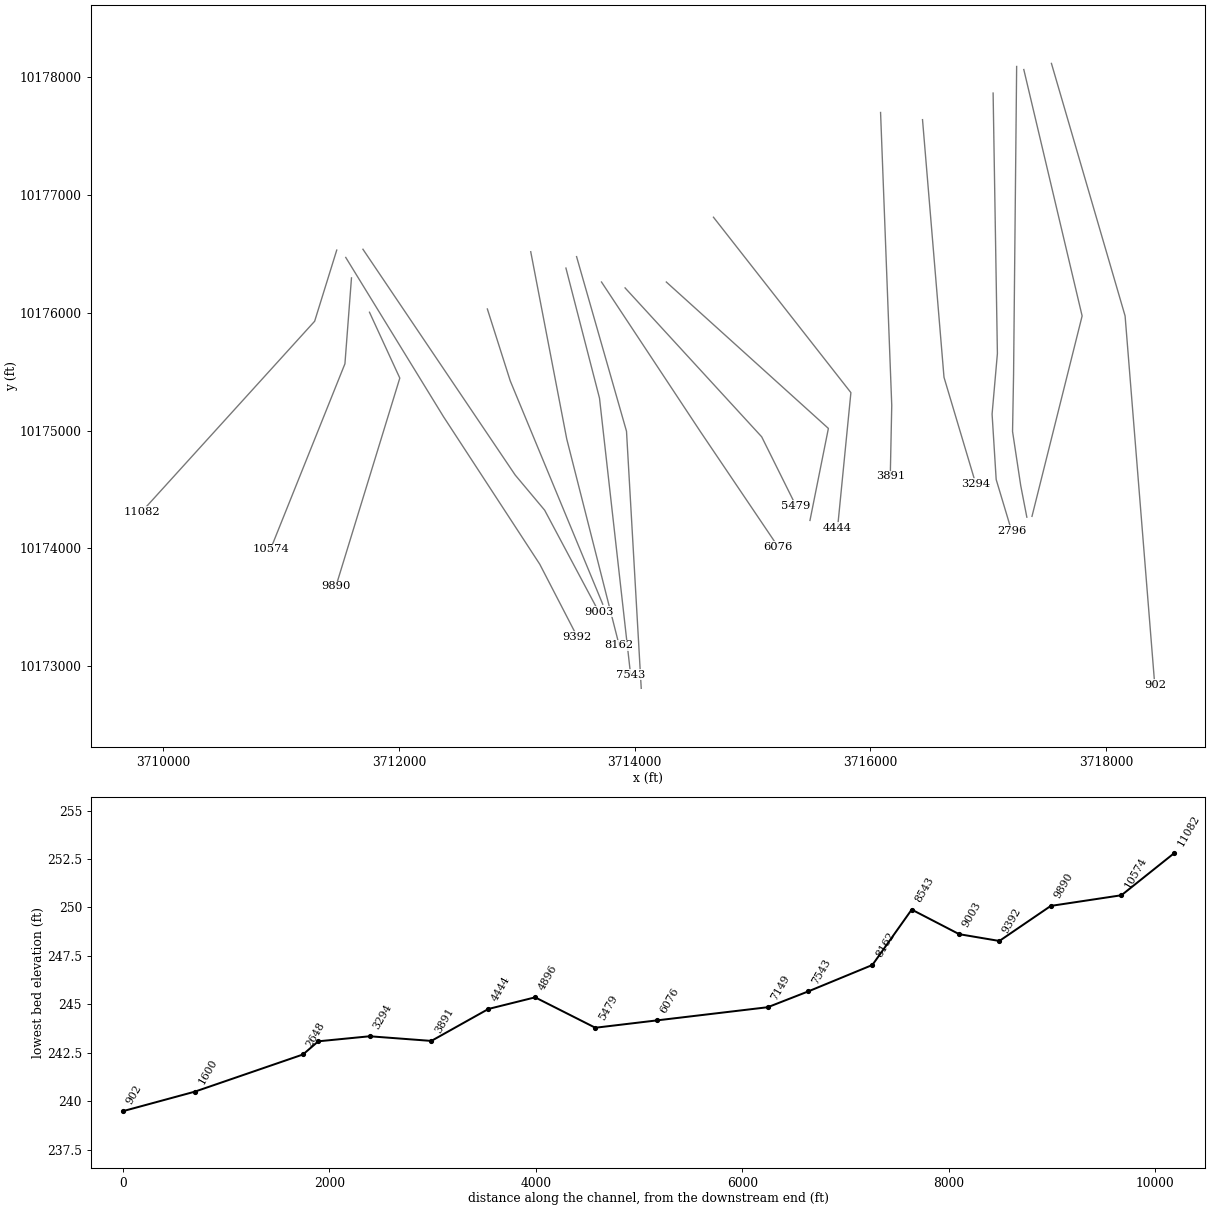
HEC-RAS study GARRETTS CREEK.prj: GARRETTS CREEK Base Level Engineering

--- GARRETTS CREEK.g01 (geometry) --- (continued)

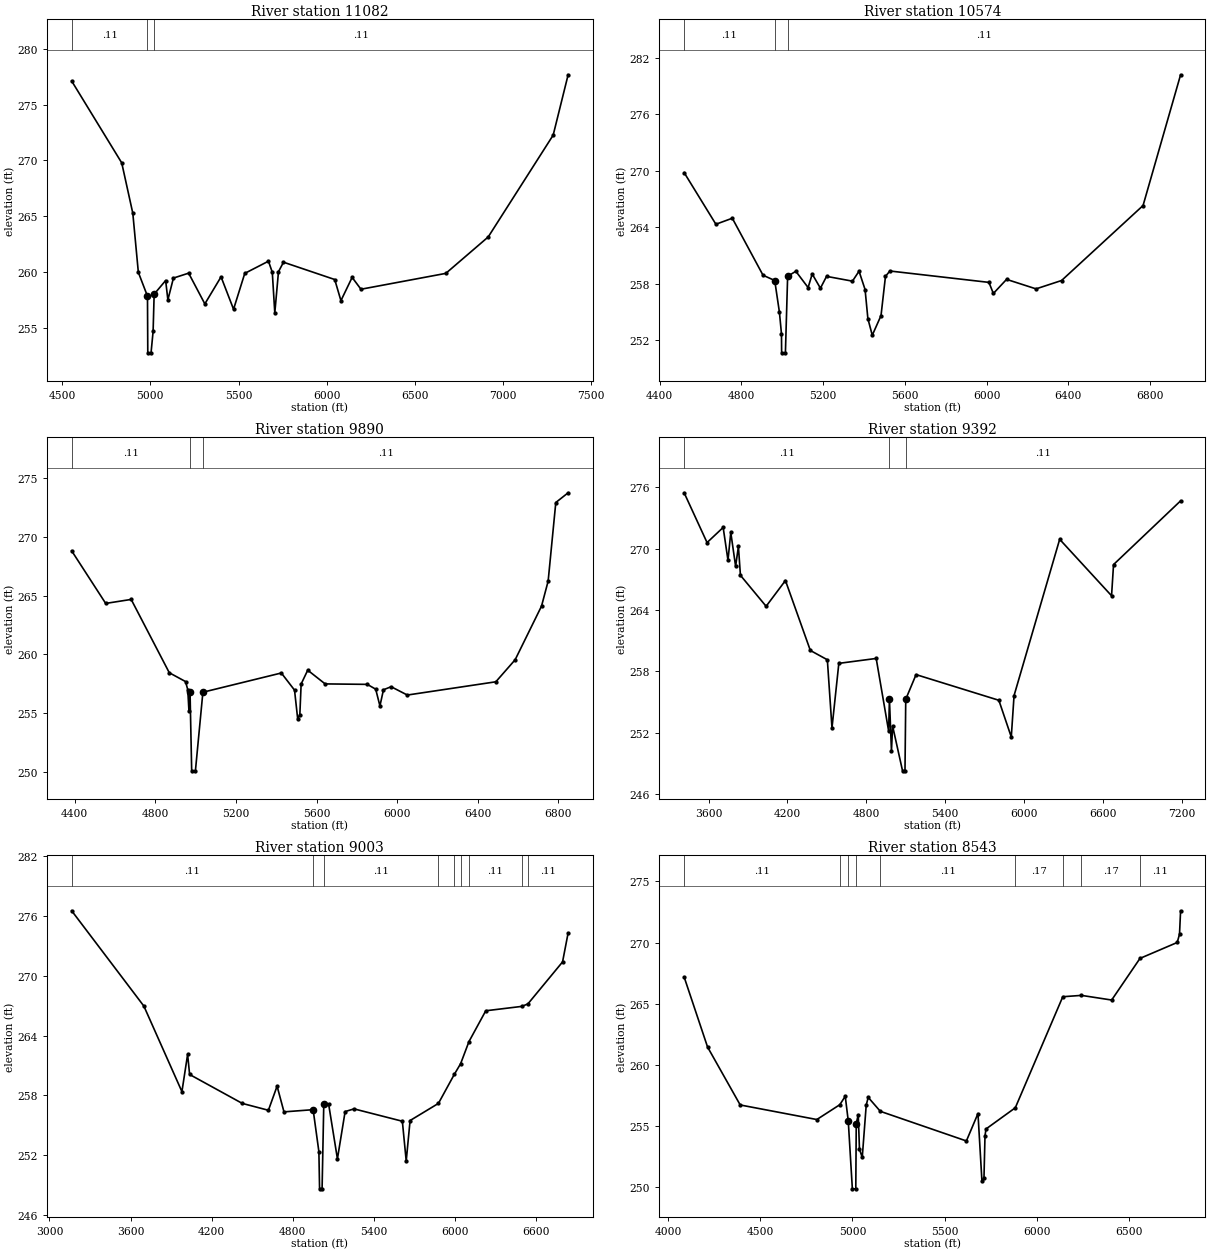
Type RM Length L Ch R = 1 ,11082   ,508,508,508
BEGIN DESCRIPTION:
GARRETTS CREEK 17.0
END DESCRIPTION:
XS GIS Cut Line= 3
      3711471.68     10176532.15      3711284.19       10175928.
      3709817.83     10174311.05
#Sta/Elev= 30
  4553.8  277.11  4837.6  269.79  4900.5  265.28  4931.9  259.99  4983.7  257.86
  4985.4  252.79  5003.9  252.79  5015.6  254.71  5021.5  258.04  5086.7  259.26
  5099.4  257.53  5130.8  259.48  5217.1  259.92    5309  257.17  5400.9  259.59
  5471.8  256.69  5535.4   259.9  5669.8  260.99  5691.5     260  5705.7  256.36
  5726.6  260.05    5755   260.9  6045.6  259.35  6080.7  257.46  6144.3  259.54
  6194.3  258.48  6675.5   259.9    6916  263.16  7284.4  272.27  7369.2  277.67
#Mann= 3 , 0 , 0
  4553.8     .11       0  4983.7     .06       0  5021.5     .11       0
Bank Sta=4983.7,5021.5
XS Rating Curve= 0 ,0
Exp/Cntr=0.3,0.1

Type RM Length L Ch R = 1 ,10574   ,684,684,684
BEGIN DESCRIPTION:
GARRETTS CREEK 16.0
END DESCRIPTION:
XS GIS Cut Line= 3
      3711596.69     10176296.07      3711541.13     10175566.89
       3710909.2     10173990.53
#Sta/Elev= 30
  4519.6  269.79    4675   264.3  4755.3  264.94  4905.7  258.88  4962.9  258.32
  4985.9  254.95    4996  252.64  4996.7  250.63  5015.2  250.63  5026.1  258.77
  5066.2   259.3  5126.3  257.57  5146.4  259.01  5186.5   257.5  5216.6  258.76
  5343.3  258.25  5375.5  259.31  5405.1  257.36  5418.8  254.27  5440.3   252.5
  5483.1  254.59  5504.9  258.76  5526.5  259.33  6011.3  258.12  6032.9  256.94
  6097.5  258.44  6241.8  257.43  6366.8  258.32  6765.5  266.29  6949.2  280.19
#Mann= 3 , 0 , 0
  4519.6     .11       0  4962.9     .06       0  5026.1     .11       0
Bank Sta=4962.9,5026.1
XS Rating Curve= 0 ,0
Exp/Cntr=0.3,0.1

Type RM Length L Ch R = 1 ,9890    ,498,498,498
BEGIN DESCRIPTION:
GARRETTS CREEK 15.0
END DESCRIPTION:
XS GIS Cut Line= 3
      3711749.46     10176004.39      3712006.64     10175445.42
      3711464.75     10173678.02
#Sta/Elev= 30
  4384.7  268.83  4553.5  264.35    4680  264.69  4869.2  258.44  4949.7  257.69
  4960.8     257  4966.6  255.22  4972.1  256.81  4980.3  250.08  4998.8  250.08
  5035.9  256.78  5425.2  258.42  5490.7  256.96  5506.6  254.48  5517.1  254.87
  5523.5  257.48  5556.2  258.66  5642.6  257.49  5851.8  257.45  5893.6  257.04
  5914.5  255.61  5932.1  256.99  5970.1  257.25  6050.5  256.54  6489.8  257.67
  6585.7  259.55  6716.6  264.12  6749.4  266.25  6787.4  272.95  6848.6  273.78
#Mann= 3 , 0 , 0
  4384.7     .11       0  4972.1     .06       0  5035.9     .11       0
Bank Sta=4972.1,5035.9
XS Rating Curve= 0 ,0
Exp/Cntr=0.3,0.1

Type RM Length L Ch R = 1 ,9392    ,389,389,389
BEGIN DESCRIPTION:
GARRETTS CREEK 14.0
END DESCRIPTION:
XS GIS Cut Line= 4
      3711548.07     10176469.67      3712377.07     10175118.04
      3713193.91      10173865.5      3713513.08     10173247.97
#Sta/Elev= 30
  3414.4  275.46  3588.7  270.59  3711.2  272.07  3747.9  268.86  3769.2  271.58
  3805.9  268.27  3827.2  270.21  3842.6  267.39    4038  264.36  4184.9  266.88
  4374.4  260.04  4503.7  259.13  4538.9  252.47    4591  258.78  4875.2  259.26
    4970  252.15  4975.8  255.31  4991.3   250.2    5000  252.66  5075.6  248.27
  5094.2  248.27    5100  255.27  5178.4  257.68  5808.2  255.17  5902.7  251.58
  5923.8  255.63  6270.8  270.91  6665.4  265.39  6680.5  268.44  7190.5  274.67
#Mann= 3 , 0 , 0
  3414.4     .11       0  4975.8     .06       0    5100     .11       0
Bank Sta=4975.8,5100
XS Rating Curve= 0 ,0
Exp/Cntr=0.3,0.1

Type RM Length L Ch R = 1 ,9003    ,460,460,460
BEGIN DESCRIPTION:
Mapping XS 88005e4d
END DESCRIPTION:
XS GIS Cut Line= 4
      3711693.89     10176539.14      3712985.58     10174622.44
      3713235.58     10174323.83      3713693.93     10173462.68
#Sta/Elev= 30
  3164.3  276.51  3698.9  266.95  3980.7  258.37  4022.8   262.1  4037.7  260.09
  4427.5  257.19  4621.1   256.5  4685.4  258.92  4736.4  256.34  4952.3  256.56
  4994.9  252.35    5000  248.62  5018.6  248.62  5031.1  257.09  5067.3   257.1
  5132.2  251.63  5189.2  256.37  5255.1  256.64    5613   255.4  5641.6  251.41
  5670.2  255.47  5880.2  257.19  5997.3  260.09  6044.4  261.17  6106.3  263.39
  6230.7  266.48  6497.5  266.92  6542.7  267.17  6799.3  271.38  6840.6  274.29
#Mann= 9 ,-1 , 0
  3164.3     .11       0  4952.3     .06       0  5031.1     .11       0
  5880.2     .17       0  5997.3     .11       0  6044.4     .17       0
  6106.3     .11       0  6497.5     .17       0  6542.7     .11       0
Bank Sta=4952.3,5031.1
XS Rating Curve= 0 ,0
Exp/Cntr=0.3,0.1

Type RM Length L Ch R = 1 ,8543    ,381,381,381
BEGIN DESCRIPTION:
GARRETTS CREEK 13.0
END DESCRIPTION:
XS GIS Cut Line= 3
      3712749.46     10176032.17      3712943.91     10175421.05
      3713728.47     10173525.62
#Sta/Elev= 30
  4087.3  267.19  4214.4  261.47  4391.4  256.74    4807  255.55  4931.5  256.76
  4961.2  257.45  4977.5  255.43  4999.7  249.89  5018.3  249.89  5020.8  255.22
  5031.6  255.95  5038.3  253.13  5053.3  252.45  5074.9  256.73  5085.7  257.36
  5151.5  256.22  5618.2   253.8    5681  256.04  5702.6  250.51  5713.5  250.75
  5719.1  254.22  5724.6  254.78  5883.5  256.51    6141  265.58  6242.2  265.69
  6406.1  265.31  6559.7  268.71  6761.6  270.01  6774.1  270.68    6780   272.6
#Mann= 9 ,-1 , 0
  4087.3     .11       0  4931.5     .15       0  4977.5     .09       0
  5020.8     .15       0  5151.5     .11       0  5883.5     .17       0
    6141     .11       0  6242.2     .17       0  6559.7     .11       0
Bank Sta=4977.5,5020.8
XS Rating Curve= 0 ,0
Exp/Cntr=0.3,0.1

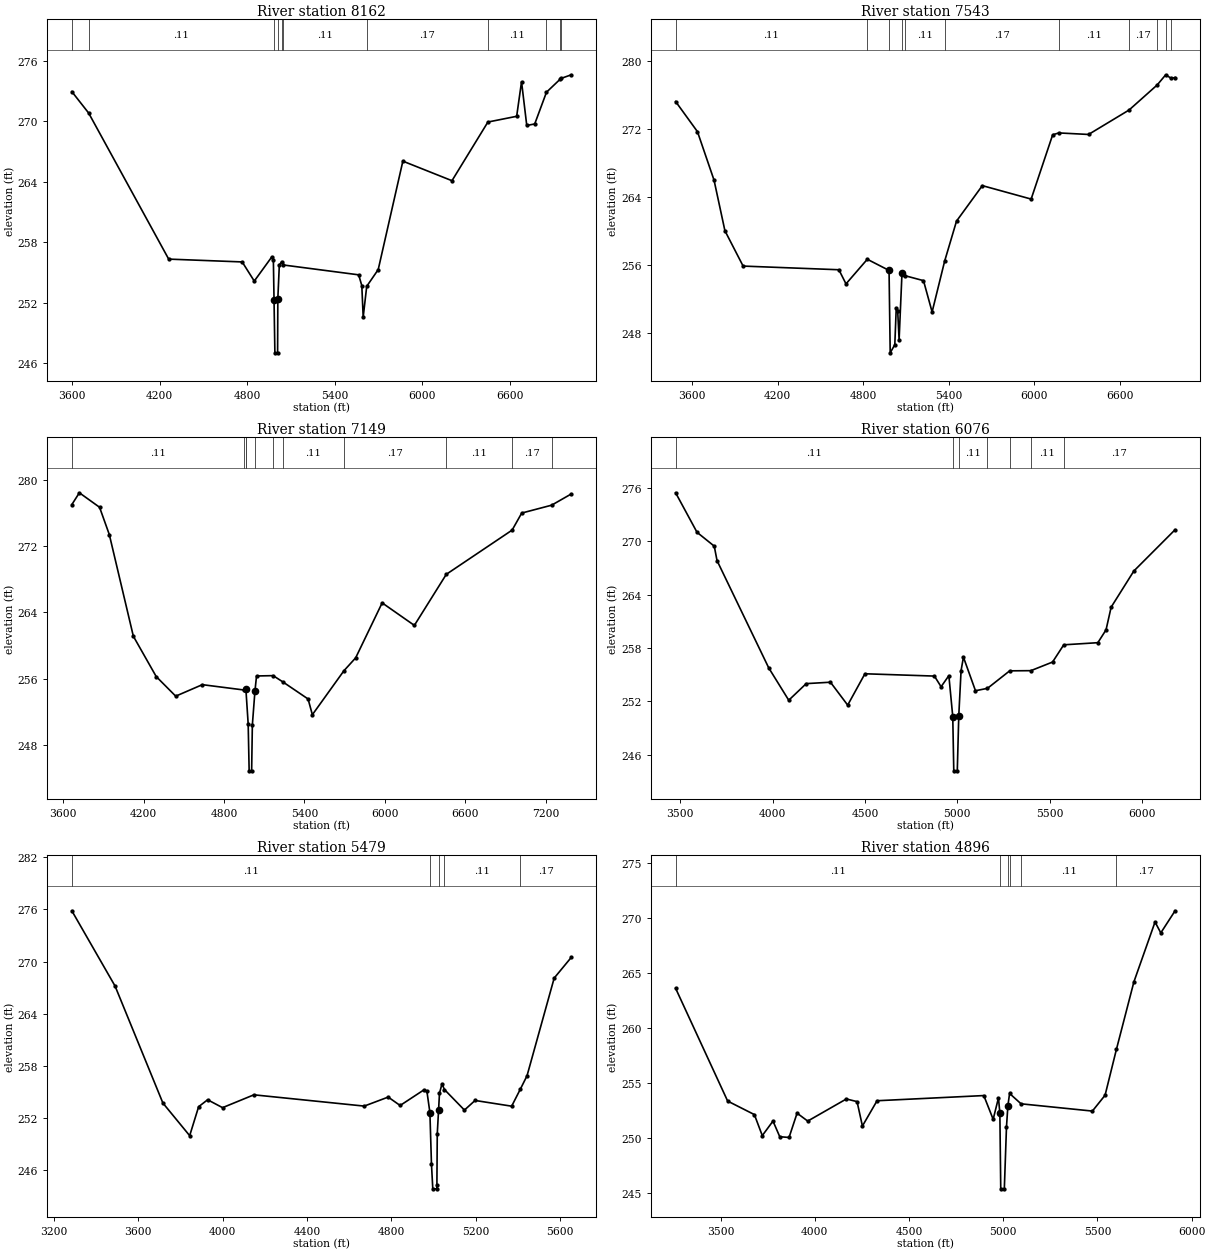
Type RM Length L Ch R = 1 ,8162    ,619,619,619
BEGIN DESCRIPTION:
GARRETTS CREEK 12.0
END DESCRIPTION:
XS GIS Cut Line= 3
      3713117.52     10176518.27      3713423.08       10174928.
      3713867.52     10173178.01
#Sta/Elev= 30
  3596.9  272.95    3712  270.83  4261.1  256.33  4765.1  256.05  4847.9  254.15
  4968.7  256.56  4978.9  256.26 4983.38252.3094  4989.3  247.03  5007.9  247.03
  5009.5  252.41  5019.7  255.74  5036.2  256.08  5045.9  255.75  5563.9  254.77
  5585.3   253.7  5594.8  250.58    5619  253.63  5697.8  255.29  5866.8  266.05
  6203.6  264.11  6449.9  269.93  6647.2   270.5  6680.6  273.93  6716.4  269.59
    6771  269.74  6851.6  272.89  6945.3  274.18    6952  274.26  7021.8  274.62
#Mann= 11 ,-1 , 0
  3596.9     .17       0    3712     .11       0 4983.38     .06       0
  5009.5     .11       0  5036.2     .15       0  5045.9     .11       0
    5619     .17       0  6449.9     .11       0  6851.6     .17       0
  6945.3     .11       0    6952     .17       0
Bank Sta=4983.38,5009.5
XS Rating Curve= 0 ,0
Exp/Cntr=0.3,0.1

Type RM Length L Ch R = 1 ,7543    ,394,394,394
BEGIN DESCRIPTION:
GARRETTS CREEK 11.0
END DESCRIPTION:
XS GIS Cut Line= 3
      3713416.14     10176379.34      3713700.86     10175275.22
      3713964.74     10172928.05
#Sta/Elev= 30
  3484.3  275.19  3637.4  271.65  3753.8  265.95    3830  260.01  3957.6  255.86
  4629.1  255.43    4679  253.77  4828.4  256.66  4980.9  255.35  4988.9  245.67
  5021.2  246.62  5031.2  250.93  5041.3  250.64  5051.4  247.22  5071.5     255
  5095.1  254.72  5222.4  254.15  5282.8  250.47  5370.8  256.45  5453.9  261.14
    5635  265.31  5977.2  263.73  6128.1  271.28  6171.4   271.5  6379.7  271.32
  6663.8  274.19  6860.8  277.13  6920.8  278.33  6959.2  277.91  6986.5  278.01
#Mann= 11 ,-1 , 0
  3484.3     .11       0  4828.4     .15       0  4980.9     .09       0
  5071.5     .15       0  5095.1     .11       0  5370.8     .17       0
  6171.4     .11       0  6663.8     .17       0  6860.8     .11       0
  6920.8     .17       0  6959.2     .11       0
Bank Sta=4980.9,5071.5
XS Rating Curve= 0 ,0
Exp/Cntr=0.3,0.1

Type RM Length L Ch R = 1 ,7149    ,1073,1073,1073
BEGIN DESCRIPTION:
GARRETTS CREEK 10.0
END DESCRIPTION:
XS GIS Cut Line= 3
       3713506.4     10176476.63      3713930.02     10174993.97
      3714055.02     10172811.64
#Sta/Elev= 30
  3664.3  277.01  3720.5  278.44  3871.3  276.69  3944.1  273.39  4123.5  261.11
  4294.1  256.24  4439.7  253.87  4638.3  255.26  4947.2  254.62  4961.8  254.72
  4963.3  254.75  4980.5  250.52  4987.8  244.85  5006.4  244.85  5011.7  250.39
  5030.9  254.46  5042.9  256.31  5166.8  256.35  5237.9  255.61  5427.6  253.53
  5459.6  251.63  5695.1  256.94  5782.8   258.5  5980.5  265.14  6220.9  262.42
  6459.3  268.59  6950.5  273.93  7022.2  275.99  7245.2  276.94  7392.2   278.3
#Mann= 11 ,-1 , 0
  3664.3     .11       0  4947.2     .15       0  4961.8     .11       0
  4963.3     .06       0  5030.9     .11       0  5166.8     .15       0
  5237.9     .11       0  5695.1     .17       0  6459.3     .11       0
  6950.5     .17       0  7245.2     .11       0
Bank Sta=4963.3,5030.9
XS Rating Curve= 0 ,0
Exp/Cntr=0.3,0.1

Type RM Length L Ch R = 1 ,6076    ,597,597,597
BEGIN DESCRIPTION:
GARRETTS CREEK 9.0
END DESCRIPTION:
XS GIS Cut Line= 3
      3713717.84      10176261.1      3714558.25     10174988.93
      3715217.84     10174011.09
#Sta/Elev= 30
  3475.3  275.48  3591.2  271.03  3684.5  269.47  3699.6  267.84  3979.5  255.76
  4087.8  252.12  4182.4  253.99  4313.6  254.15  4406.9  251.57  4500.2   255.1
  4876.5  254.84  4912.6  253.64  4954.7  254.89  4975.8  250.28  4981.3  244.17
  5000.3  244.17 5008.33250.3658  5020.8  255.46  5033.6  256.97  5098.8  253.19
  5163.8  253.46    5284  255.43  5398.7  255.45  5516.1  256.42  5576.7  258.36
  5761.3   258.6  5805.6  260.04  5833.3   262.6  5956.2  266.67  6179.5  271.32
#Mann= 7 ,-1 , 0
  3475.3     .11       0  4975.8     .09       0 5008.33     .11       0
  5163.8     .11       0    5284     .17       0  5398.7     .11       0
  5576.7     .17       0
Bank Sta=4975.8,5008.33
XS Rating Curve= 0 ,0
Exp/Cntr=0.3,0.1

Type RM Length L Ch R = 1 ,5479    ,583,583,583
BEGIN DESCRIPTION:
GARRETTS CREEK 8.0
END DESCRIPTION:
XS GIS Cut Line= 3
      3713917.83     10176211.09      3715077.03     10174946.77
      3715367.84     10174361.09
#Sta/Elev= 30
  3284.7  275.85  3489.8  267.17  3716.7  253.68  3843.7  249.92  3886.2  253.26
  3928.8  254.06  3999.7  253.15  4148.3  254.63  4671.8  253.33  4785.3  254.37
    4842   253.4  4954.8   255.2    4969  255.04  4983.2  252.59  4990.6  246.66
  4996.9  243.79  5015.9  243.79  5016.4  244.29  5018.1  250.12 5024.23 252.838
  5028.7  254.82  5040.5  255.89  5052.1  255.24    5147  252.87  5197.4  253.98
    5371  253.32  5411.7  255.26  5443.8  256.82  5572.7  268.09  5653.9  270.48
#Mann= 5 ,-1 , 0
  3284.7     .11       0  4983.2     .06       0 5024.23     .15       0
  5052.1     .11       0  5411.7     .17       0
Bank Sta=4983.2,5024.23
XS Rating Curve= 0 ,0
Exp/Cntr=0.3,0.1

Type RM Length L Ch R = 1 ,4896    ,452,452,452
BEGIN DESCRIPTION:
GARRETTS CREEK 7.0
END DESCRIPTION:
XS GIS Cut Line= 3
      3714267.87     10176261.06      3715642.86     10175018.07
      3715486.61     10174236.78
#Sta/Elev= 30
  3261.8  263.59  3537.9  253.34  3679.7  252.11  3721.7   250.2  3778.5  251.52
  3814.4   250.1  3863.7  250.03  3906.3  252.24  3962.8  251.52  4167.8  253.53
  4224.6  253.29    4253  251.07  4330.7  253.37  4897.1  253.84  4946.8  251.68
  4974.9  253.63  4982.3  252.25    4987  245.36    5006  245.36  5017.5     251
  5024.9  252.91  5033.9  254.03  5094.8  253.09  5473.3  252.43  5540.6  253.87
  5600.8  258.04  5693.6  264.18  5805.7  269.62  5836.3  268.63  5912.1  270.64
#Mann= 6 ,-1 , 0
  3261.8     .11       0  4982.3     .06       0  5024.9     .11       0
  5033.9     .15       0  5094.8     .11       0  5600.8     .17       0
Bank Sta=4982.3,5024.9
XS Rating Curve= 0 ,0
Exp/Cntr=0.3,0.1

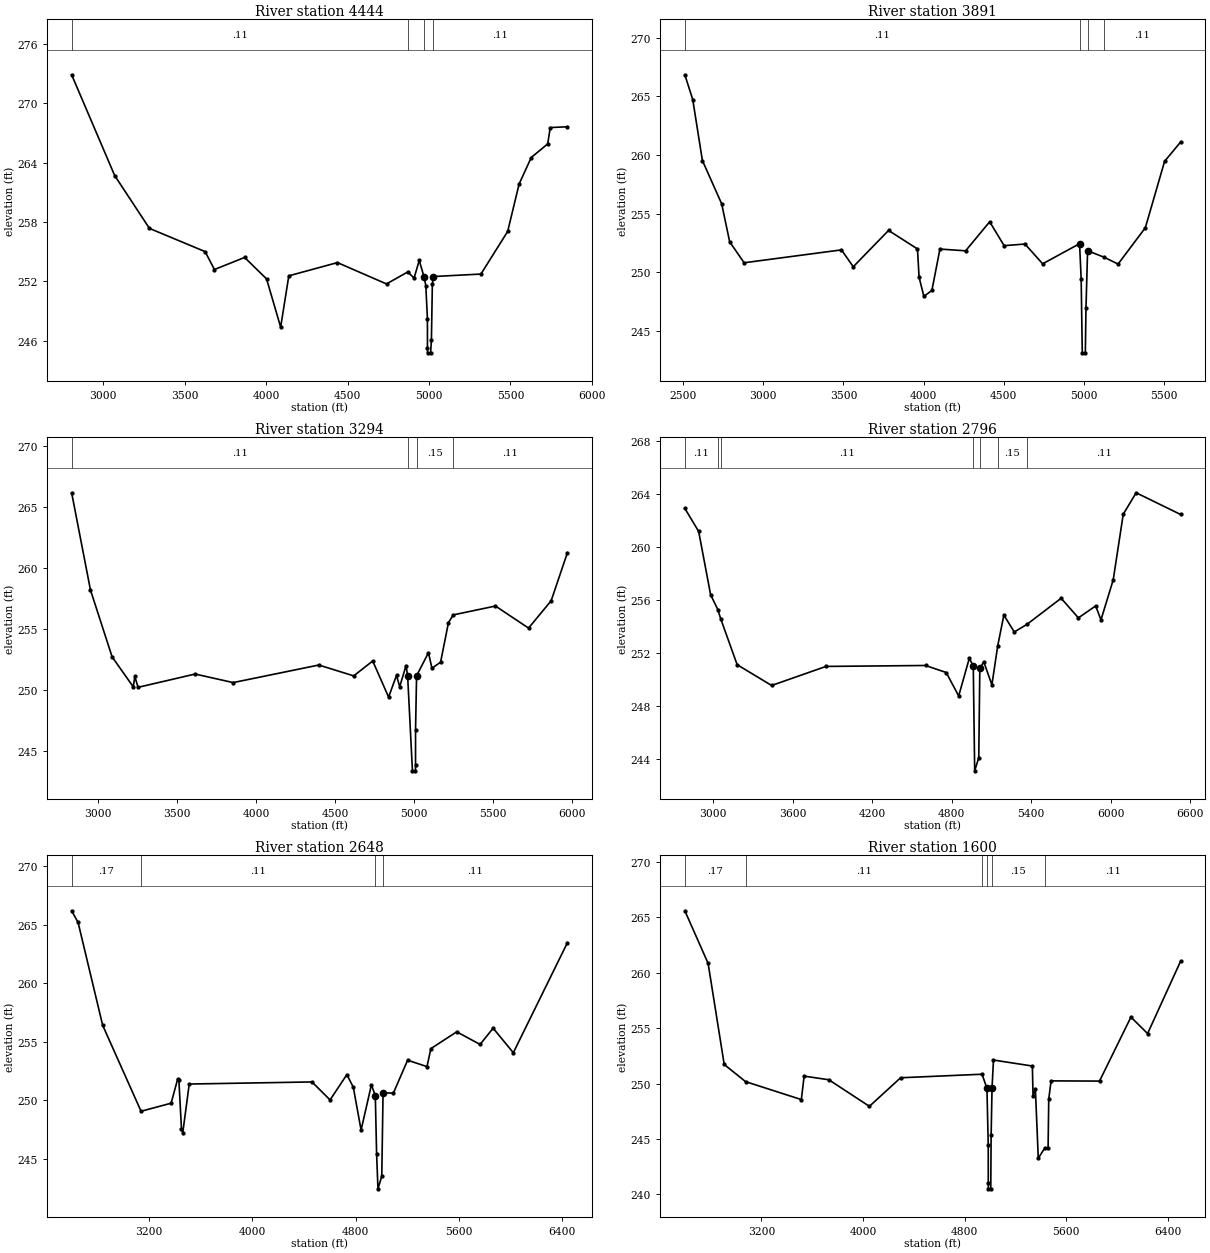
Type RM Length L Ch R = 1 ,4444    ,553,553,553
BEGIN DESCRIPTION:
GARRETTS CREEK 6.0
END DESCRIPTION:
XS GIS Cut Line= 3
      3714667.83      10176811.1      3715833.83     10175321.89
      3715720.98     10174176.01
#Sta/Elev= 30
  2806.8  272.89  3070.8   262.7  3284.2  257.35    3626     255  3683.2  253.19
  3868.3  254.41  4003.1  252.24  4089.6  247.36  4139.6  252.55    4438  253.89
  4739.2  251.73  4869.2  252.94  4908.6  252.33  4940.2  254.11  4970.3   252.4
  4980.4  251.57  4990.4  248.21  4990.5  245.26    4991  244.76    5010  244.76
  5014.9   246.1  5020.6  251.69  5026.8  252.48  5318.7  252.73  5482.8  257.04
  5553.1  261.84  5627.5  264.52  5728.7   265.9    5744  267.55  5849.6  267.63
#Mann= 4 ,-1 , 0
  2806.8     .11       0  4869.2     .15       0  4970.3     .09       0
  5026.8     .11       0
Bank Sta=4970.3,5026.8
XS Rating Curve= 0 ,0
Exp/Cntr=0.3,0.1

Type RM Length L Ch R = 1 ,3891    ,597,597,597
BEGIN DESCRIPTION:
GARRETTS CREEK 5.0
END DESCRIPTION:
XS GIS Cut Line= 3
      3716085.57     10177700.38      3716180.45     10175213.39
      3716167.85     10174611.12
#Sta/Elev= 30
  2511.2  266.85  2560.5  264.73  2620.6  259.53  2740.7  255.84  2790.7  252.59
  2880.8   250.8  3487.7   251.9  3561.3  250.46  3781.4  253.56  3961.6  251.98
  3971.6  249.57  4001.6  247.93  4051.6  248.44  4101.7  251.97  4261.8  251.82
  4411.9   254.3    4502  252.26    4632   252.4  4742.1  250.71  4972.3  252.43
  4982.3  249.41  4989.2  243.11  5008.2  243.11  5012.3  246.94  5022.3  251.83
  5125.7  251.27  5212.4  250.69  5382.4  253.79  5502.4  259.46  5602.4  261.11
#Mann= 4 ,-1 , 0
  2511.2     .11       0  4972.3     .06       0  5022.3     .11       0
  5125.7     .11       0
Bank Sta=4972.3,5022.3
XS Rating Curve= 0 ,0
Exp/Cntr=0.3,0.1

Type RM Length L Ch R = 1 ,3294    ,498,498,498
BEGIN DESCRIPTION:
GARRETTS CREEK 4.0
END DESCRIPTION:
XS GIS Cut Line= 3
      3716441.47     10177639.63      3716623.76     10175452.09
      3716892.85     10174549.37
#Sta/Elev= 30
  2833.7  266.16  2952.7  258.19  3089.7   252.7  3223.6  250.24  3233.6  251.09
  3253.7   250.2    3615  251.29  3855.8  250.59  4397.7  252.03  4618.4  251.14
  4738.8  252.36  4839.2   249.4  4889.4  251.18  4909.4  250.25  4949.6  251.99
  4959.6  251.16  4990.2  243.35  5009.2  243.35  5009.7  243.85  5009.8  246.72
  5016.3  251.15  5091.5  253.04  5113.4  251.77  5168.2  252.26  5217.7  255.49
  5247.9  256.14  5515.4  256.87  5724.8  255.06  5867.8   257.3  5970.8  261.25
#Mann= 4 ,-1 , 0
  2833.7     .11       0  4959.6     .09       0  5016.3     .15       0
  5247.9     .11       0
Bank Sta=4959.6,5016.3
XS Rating Curve= 0 ,0
Exp/Cntr=0.3,0.1

Type RM Length L Ch R = 1 ,2796    ,148,148,148
BEGIN DESCRIPTION:
GARRETTS CREEK 3.0
END DESCRIPTION:
XS GIS Cut Line= 5
      3717040.43     10177865.27      3717076.81     10175653.57
      3717031.75     10175139.59      3717066.47     10174584.04
      3717196.67     10174150.04
#Sta/Elev= 30
    2788  262.92  2892.2  261.18  2982.2   256.4  3036.3  255.28  3059.4  254.55
  3182.3  251.11  3442.3  249.54  3852.3  250.98  4602.4  251.05  4758.4  250.52
  4852.5  248.75  4932.5  251.59  4962.5  251.01    4973  243.09  5003.8  244.08
 5011.86250.8244  5041.5  251.33  5102.9  249.59    5147  252.55  5193.2  254.86
  5271.4  253.58  5367.6  254.16  5624.7  256.13  5754.9  254.65  5885.2  255.55
  5925.3   254.5  6017.5  257.52  6093.1  262.48  6190.5   264.1  6525.7  262.46
#Mann= 7 ,-1 , 0
    2788     .11       0  3036.3     .17       0  3059.4     .11       0
  4962.5     .06       0 5011.86     .11       0    5147     .15       0
  5367.6     .11       0
Bank Sta=4962.5,5011.86
XS Rating Curve= 0 ,0
Exp/Cntr=0.3,0.1

Type RM Length L Ch R = 1 ,2648    ,1048,1048,1048
BEGIN DESCRIPTION:
Mapping XS aac3baec
END DESCRIPTION:
XS GIS Cut Line= 5
      3717240.08     10178091.01      3717214.04     10175478.14
      3717205.36     10174992.02      3717274.81     10174531.95
      3717326.57     10174264.49
#Sta/Elev= 30
  2602.3  266.21  2652.2  265.21  2842.3  256.41  3139.5  249.05  3372.3  249.74
  3422.3  251.79  3432.3   251.7  3452.3  247.53  3462.3  247.21  3512.3  251.38
  4462.3  251.56  4602.3  250.02  4732.3  252.19  4782.3   251.1  4842.3  247.44
  4922.4  251.32  4952.4  250.38  4962.4  245.42  4972.9  242.41  5002.4  243.49
  5012.4  250.62  5092.4  250.61  5202.4  253.42  5352.4  252.87  5382.4  254.41
  5582.4  255.85  5763.1  254.77  5864.3  256.16  6020.4  254.06  6439.2  263.48
#Mann= 4 ,-1 , 0
  2602.3     .17       0  3139.5     .11       0  4952.4     .06       0
  5012.4     .11       0
Bank Sta=4952.4,5012.4
XS Rating Curve= 0 ,0
Exp/Cntr=0.3,0.1

Type RM Length L Ch R = 1 ,1600    ,698,698,698
BEGIN DESCRIPTION:
GARRETTS CREEK 2.0
END DESCRIPTION:
XS GIS Cut Line= 3
      3717300.84     10178064.99      3717795.64     10175972.93
       3717370.3     10174271.57
#Sta/Elev= 30
  2596.5   265.6  2779.7  260.85  2906.5  251.72  3074.8  250.17  3513.8  248.55
  3535.6  250.67  3730.3  250.34  4049.4  247.94  4295.3  250.52  4936.7  250.84
    4975  249.56  4985.3  244.44  4985.6  240.99  4986.1  240.49  5005.1  240.49
  5008.1  245.34 5015.15249.5959  5026.5  252.12  5332.8  251.58  5337.9  248.86
  5356.4  249.53  5379.2  243.25  5428.5  244.14  5456.5  244.17  5461.6  248.58
    5480  250.24  5861.4  250.22  6108.8     256  6239.9  254.51    6500  261.05
#Mann= 6 ,-1 , 0
  2596.5     .17       0  3074.8     .11       0  4936.7     .15       0
    4975     .09       0 5015.15     .15       0  5428.5     .11       0
Bank Sta=4975,5015.15
XS Rating Curve= 0 ,0
Exp/Cntr=0.3,0.1

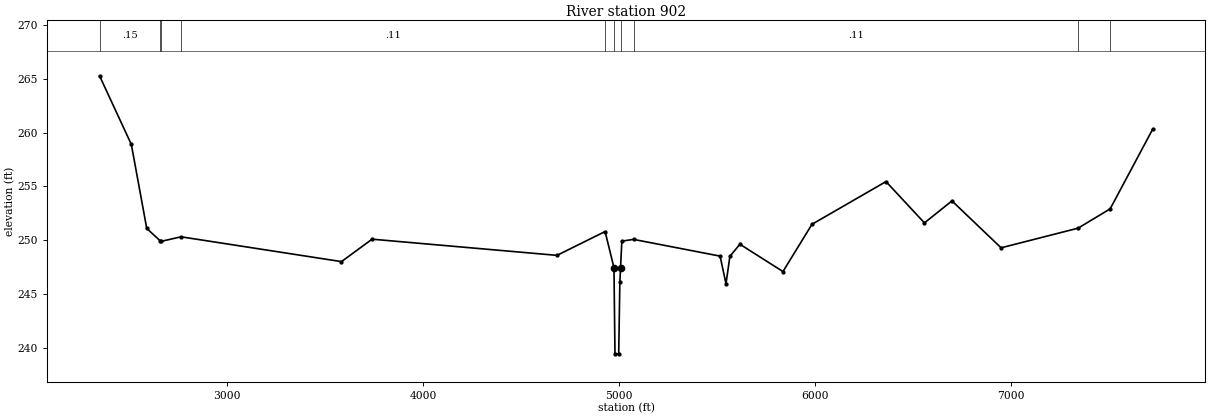
Type RM Length L Ch R = 1 ,902     ,0,0,0
BEGIN DESCRIPTION:
GARRETTS CREEK 1.0
END DESCRIPTION:
XS GIS Cut Line= 3
      3717535.23       10178117.      3718160.22     10175972.93
      3718411.96     10172839.23
#Sta/Elev= 30
  2348.9  265.26  2511.3   258.9    2590  251.11  2658.5  249.96  2663.9  249.91
  2765.2  250.33  3584.2  248.03  3740.4  250.11  4684.4  248.61    4930  250.82
  4975.3  247.47  4980.5  239.48  4999.5  239.48  5005.4  246.13 5008.91247.4507
  5015.5  249.93  5075.4  250.09  5517.1  248.54  5547.2  245.98  5567.2  248.52
  5618.3  249.64  5838.1  247.11  5986.2  251.49  6364.1  255.45  6560.4  251.62
  6700.9  253.66  6951.7  249.31  7344.5  251.13  7508.5  252.92    7726  260.32
#Mann= 10 ,-1 , 0
  2348.9     .15       0  2658.5     .17       0  2663.9     .15       0
  2765.2     .11       0    4930     .15       0  4975.3     .09       0
 5008.91     .15       0  5075.4     .11       0  7344.5     .15       0
  7508.5     .11       0
Bank Sta=4975.3,5008.91
XS Rating Curve= 0 ,0
Exp/Cntr=0.3,0.1

Chan Stop Cuts=-1
Use User Specified Reach Order=0
Composite Channel Slope=5