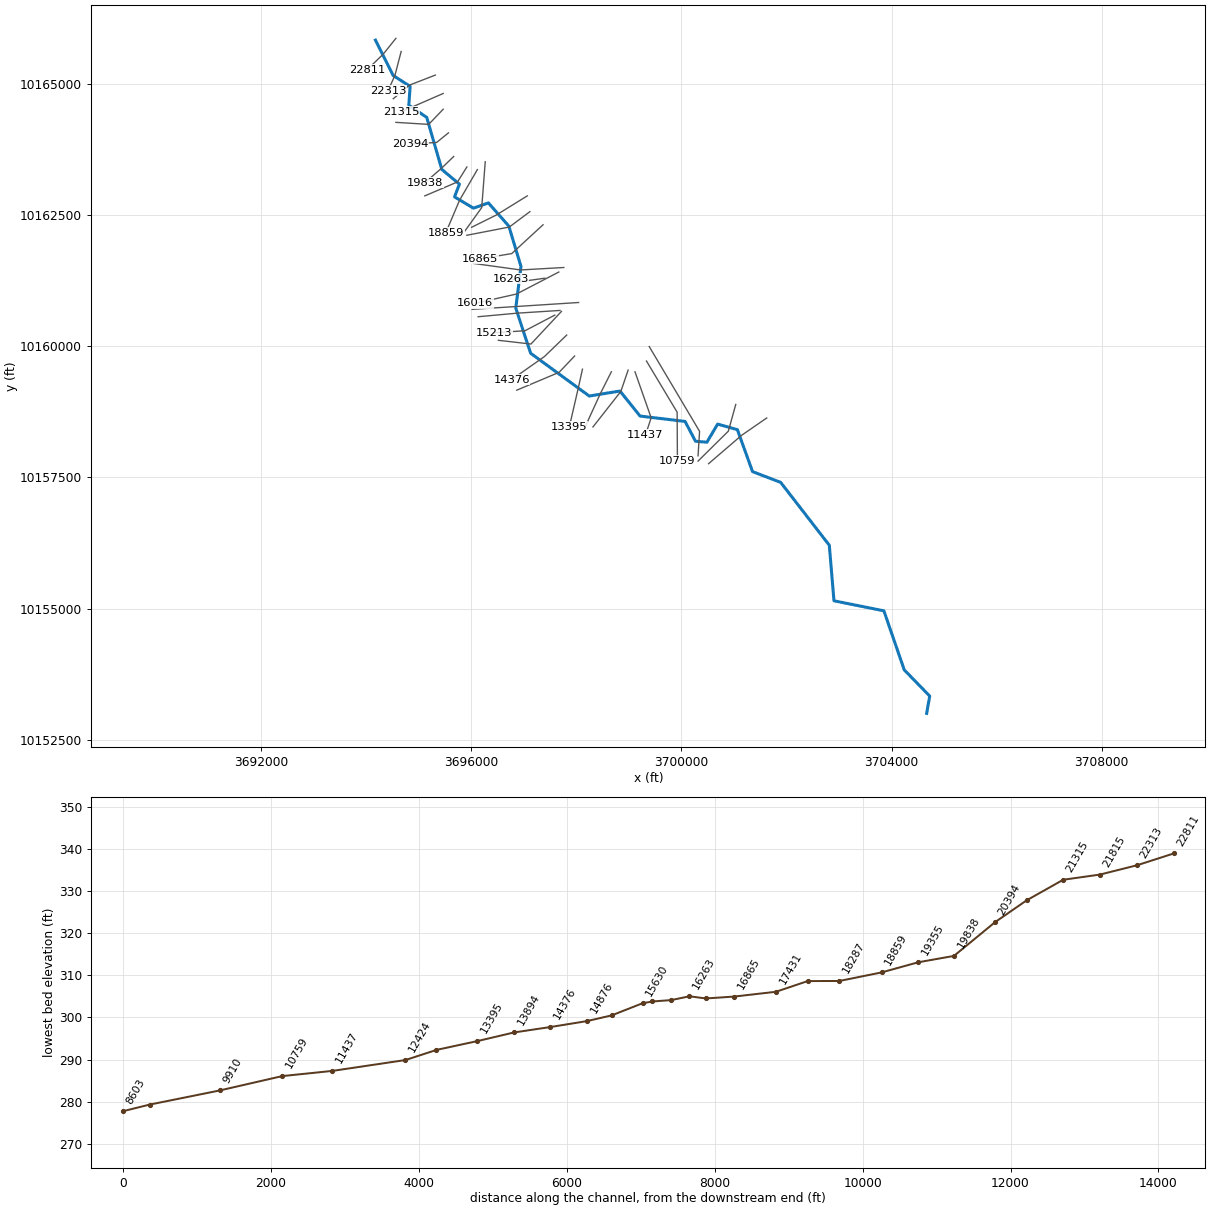
--- GETER CREEK.prj (project) ---

Proj Title=GETER CREEK Base Level Engineering
Current Plan=p01
Default Exp/Contr=0.3,0.1
English Units
Geom File=g01
Flow File=f01
Flow File=f02
Plan File=p01
Y Axis Title=Elevation
X Axis Title(PF)=Main Channel Distance
X Axis Title(XS)=Station
BEGIN DESCRIPTION:
GETER CREEK
END DESCRIPTION:
DSS Export Rating Curves= 0
DSS Export Rating Curve Sorted= 0
DSS Export Volume Flow Curves= 0
DXF OffsetX= 0
DXF OffsetY= 0
DXF ScaleX= 1
DXF ScaleY= 10

--- GETER CREEK.p01 (plan) ---

Plan Title=Multiple Run
Short Identifier=Multiple
Geom File=g01
Flow File=f01
Subcritical Flow
K Sum by GR= 0
Std Step Tol= 0.01
Critical Tol= 0.01
Num of Std Step Trials= 20
Max Error Tol= 0.3
Flow Tol Ratio= 0.001
Split Flow NTrial= 30
Split Flow Tol= 0.02
Split Flow Ratio= 0.02
Log Output Level= 0
Friction Slope Method= 1
Unsteady Friction Slope Method= 2
Unsteady Bridges Friction Slope Method= 1
Parabolic Critical Depth
Global Vel Dist=  1 , 1 , 1
Global Log Level= 0
CheckData=True
Encroach Param= -1, 0, 0, 0
BEGIN DESCRIPTION:
Multiple Run
END DESCRIPTION:

--- GETER CREEK.f01 (steady flow) ---

Flow Title=Multiple
Program Version=4.10
Number of Profiles= 7
Profile Names=10-year,25-year,50-year,1pct_min,100-year,1pct_plu,500-year
River Rch & RM=GETER CREEK,Reach-1         ,22811
     737    1016    1389     625    1886    5696    3600
River Rch & RM=GETER CREEK,Reach-1         ,19838
    1060    1485    2050     930    2808    8480    5454
River Rch & RM=GETER CREEK,Reach-1         ,12843
    1301    1825    2523    1144    3455   10434    6708
River Rch & RM=GETER CREEK,Reach-1         ,8603
    1472    2066    2857    1294    3908   11802    7573
Boundary for River Rch & Prof#=GETER CREEK,Reach-1         , 1
Up Type= 0
Dn Type= 3
Dn Slope=0.005
Boundary for River Rch & Prof#=GETER CREEK,Reach-1         , 2
Up Type= 0
Dn Type= 3
Dn Slope=0.005
Boundary for River Rch & Prof#=GETER CREEK,Reach-1         , 3
Up Type= 0
Dn Type= 3
Dn Slope=0.005
Boundary for River Rch & Prof#=GETER CREEK,Reach-1         , 4
Up Type= 0
Dn Type= 3
Dn Slope=0.005
Boundary for River Rch & Prof#=GETER CREEK,Reach-1         , 5
Up Type= 0
Dn Type= 3
Dn Slope=0.005
Boundary for River Rch & Prof#=GETER CREEK,Reach-1         , 6
Up Type= 0
Dn Type= 3
Dn Slope=0.005
Boundary for River Rch & Prof#=GETER CREEK,Reach-1         , 7
Up Type= 0
Dn Type= 3
Dn Slope=0.005
DSS Import GetInterval= 0
DSS Import GetPeak= 0
DSS Import FillOption= 0

--- GETER CREEK.f02 (steady flow) ---

Flow Title=Orig_BLE_Flows
Program Version=4.10
Number of Profiles= 7
Profile Names=10-year,25-year,50-year,1pct_min,100-year,1pct_plu,500-year
River Rch & RM=GETER CREEK,Reach-1         ,22811
     737     996    1208     480    1451    4382    2093
River Rch & RM=GETER CREEK,Reach-1         ,19838
    1060    1456    1783     715    2160    6524    3171
River Rch & RM=GETER CREEK,Reach-1         ,12843
    1301    1789    2194     880    2658    8027    3900
River Rch & RM=GETER CREEK,Reach-1         ,8603
    1472    2025    2484     995    3006    9077    4403
Boundary for River Rch & Prof#=GETER CREEK,Reach-1         , 1
Up Type= 0
Dn Type= 3
Dn Slope=0.005
Boundary for River Rch & Prof#=GETER CREEK,Reach-1         , 2
Up Type= 0
Dn Type= 3
Dn Slope=0.005
Boundary for River Rch & Prof#=GETER CREEK,Reach-1         , 3
Up Type= 0
Dn Type= 3
Dn Slope=0.005
Boundary for River Rch & Prof#=GETER CREEK,Reach-1         , 4
Up Type= 0
Dn Type= 3
Dn Slope=0.005
Boundary for River Rch & Prof#=GETER CREEK,Reach-1         , 5
Up Type= 0
Dn Type= 3
Dn Slope=0.005
Boundary for River Rch & Prof#=GETER CREEK,Reach-1         , 6
Up Type= 0
Dn Type= 3
Dn Slope=0.005
Boundary for River Rch & Prof#=GETER CREEK,Reach-1         , 7
Up Type= 0
Dn Type= 3
Dn Slope=0.005
DSS Import GetInterval= 0
DSS Import GetPeak= 0
DSS Import FillOption= 0

--- GETER CREEK.g01 (geometry) ---

Geom Title=Existing Conditions
Program Version=4.10

River Reach=GETER CREEK     ,Reach-1
Reach XY= 30
      3694178.23     10165826.84      3694517.33     10165151.93
      3694838.23     10164946.84      3694813.51     10164587.64
      3695154.22     10164355.44      3695441.48     10163364.47
      3695776.94     10163084.37      3695683.07      10162842.2
      3696043.43     10162627.27      3696328.23     10162726.84
      3696716.91     10162285.28      3696948.23     10161515.46
      3696849.06     10160722.03      3697132.09      10159863.9
      3698247.47     10159049.42      3698831.32     10159144.96
       3699213.8     10158668.13      3700070.58     10158566.27
      3700269.07     10158188.72      3700485.91     10158170.23
      3700690.69     10158515.53      3701066.28     10158408.82
      3701354.55     10157610.59      3701890.23     10157405.13
      3702815.21     10156208.43      3702904.42     10155150.41
      3703854.08     10154959.99      3704241.38     10153835.26
      3704725.95     10153336.91      3704668.23     10153006.84

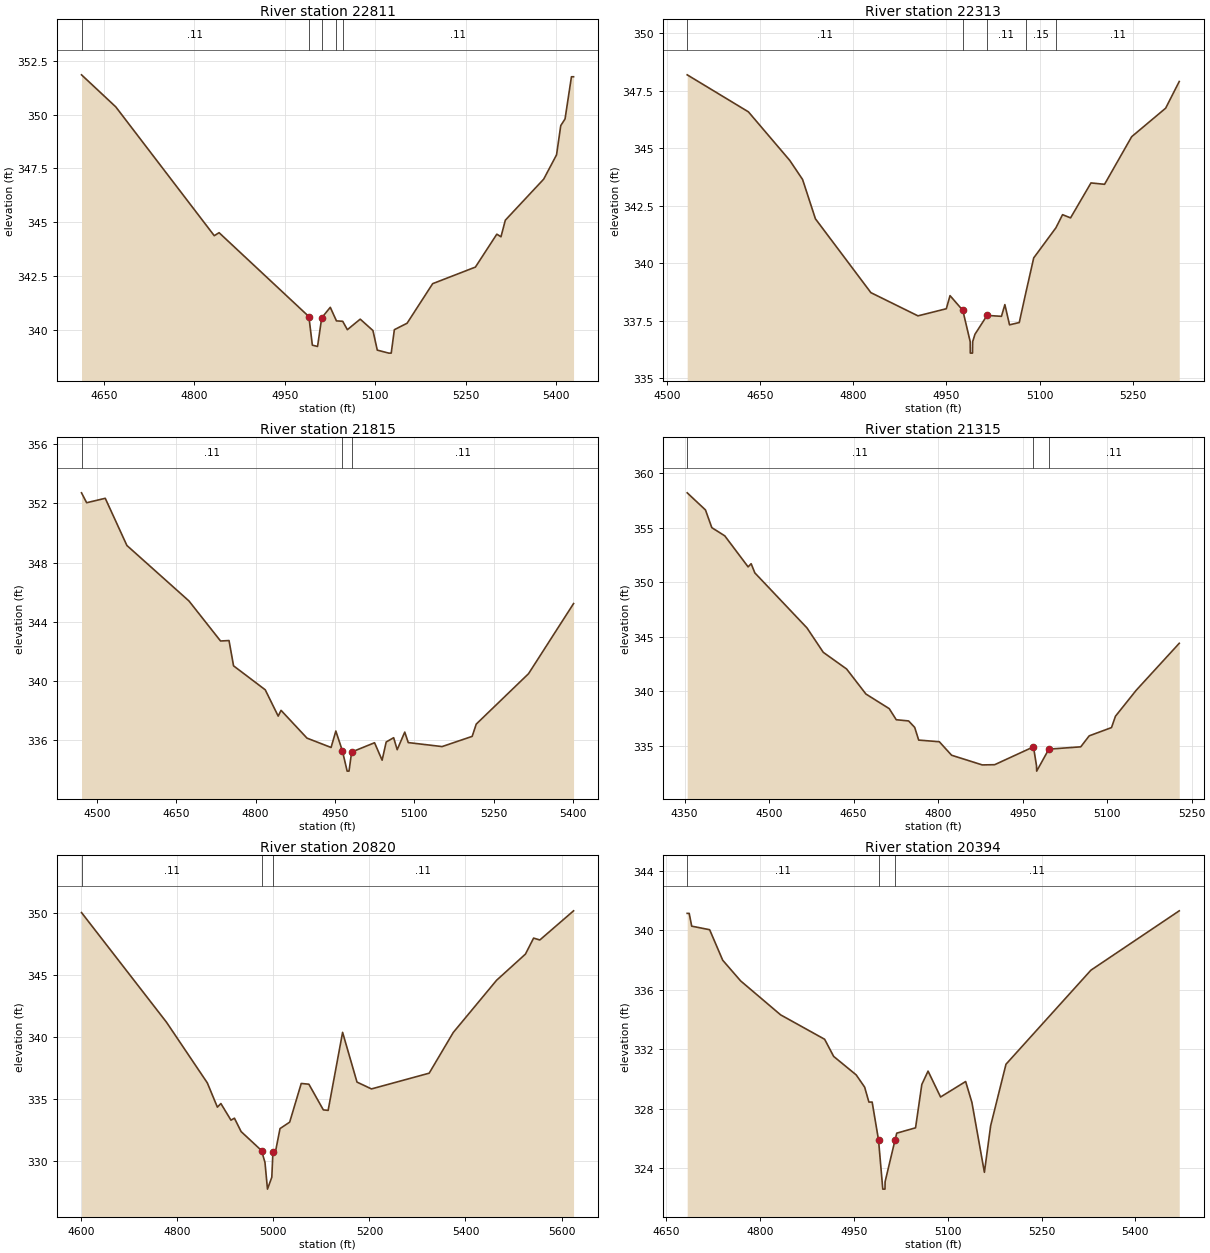
Type RM Length L Ch R = 1 ,22811   ,498,498,498
BEGIN DESCRIPTION:
GETER CREEK 39.0
END DESCRIPTION:
XS GIS Cut Line= 3
      3694567.82     10165861.04      3694325.59     10165559.35
      3694017.83     10165261.05
#Sta/Elev= 30
  4613.1  351.85  4669.9  350.36  4833.1  344.37  4841.1  344.51  4989.9  340.61
  4995.7  339.28  5004.3  339.22  5011.2  340.55  5025.4  341.04  5035.6  340.41
    5046  340.39  5053.7     340    5075  340.49  5096.1  339.96  5103.3  339.05
  5122.4  338.91  5126.4  338.91  5131.6     340  5152.7   340.3  5195.1  342.14
  5265.9  342.91  5301.4  344.44  5308.3  344.32  5315.5  345.09  5379.1     347
  5400.4  348.13  5407.4  349.49  5414.5   349.8  5425.1  351.76  5428.6  351.76
#Mann= 5 ,-1 , 0
  4613.1     .11       0  4989.9     .06       0  5011.2     .11       0
  5035.6     .15       0    5046     .11       0
Bank Sta=4989.9,5011.2
XS Rating Curve= 0 ,0
Exp/Cntr=0.3,0.1

Type RM Length L Ch R = 1 ,22313   ,498,498,498
BEGIN DESCRIPTION:
GETER CREEK 38.0
END DESCRIPTION:
XS GIS Cut Line= 3
      3694667.85     10165611.08      3694549.97     10165158.18
      3694417.83     10164861.03
#Sta/Elev= 30
    4532   348.2  4630.7  346.59  4697.3  344.48    4718  343.65  4738.7  341.94
  4828.1  338.73    4904  337.72  4949.7  338.03  4955.7   338.6  4976.3  337.96
  4988.2   336.6  4988.4   336.1  4991.9   336.1  4992.2   336.6  4995.9  336.92
  5015.4  337.74  5038.6   337.7  5044.1  338.21  5051.6  337.33  5067.3  337.43
  5077.6  338.69  5090.6  340.24  5126.4  341.55  5137.1  342.12    5150  341.98
  5182.9   343.5  5204.8  343.44  5248.5  345.51  5303.3  346.75  5325.2  347.91
#Mann= 5 ,-1 , 0
    4532     .11       0  4976.3     .06       0  5015.4     .11       0
  5077.6     .15       0  5126.4     .11       0
Bank Sta=4976.3,5015.4
XS Rating Curve= 0 ,0
Exp/Cntr=0.3,0.1

Type RM Length L Ch R = 1 ,21815   ,500,500,500
BEGIN DESCRIPTION:
GETER CREEK 37.0
END DESCRIPTION:
XS GIS Cut Line= 3
       3695317.9     10165161.09      3694824.51     10164969.99
      3694517.89      10164711.1
#Sta/Elev= 30
  4470.9  352.72  4480.6  352.05  4515.8  352.35  4556.7  349.16    4674  345.41
  4733.8   342.7  4749.8  342.73  4758.4  341.02  4818.3   339.4  4842.8  337.62
  4848.2  338.01  4897.3  336.13  4942.8   335.5  4951.8  336.61  4964.2  335.27
  4973.2   333.9  4976.7   333.9  4981.7  335.19    5025  335.82  5039.3  334.64
    5047  335.87  5061.1  336.16  5067.8  335.35  5082.1  336.54  5088.7  335.83
  5152.7  335.56  5209.6  336.25  5217.3  337.08  5316.2  340.49  5401.3  345.23
#Mann= 3 , 0 , 0
  4470.9     .11       0  4964.2     .06       0  4981.7     .11       0
Bank Sta=4964.2,4981.7
XS Rating Curve= 0 ,0
Exp/Cntr=0.3,0.1

Type RM Length L Ch R = 1 ,21315   ,495,495,495
BEGIN DESCRIPTION:
GETER CREEK 36.0
END DESCRIPTION:
XS GIS Cut Line= 3
      3695467.86     10164811.07      3694876.45     10164552.92
      3694667.87     10164461.08
#Sta/Elev= 30
  4354.7  358.22  4387.1  356.65  4398.4  355.02  4421.4  354.27  4462.8  351.42
  4468.2  351.71  4474.7  350.87  4567.3  345.81  4596.2  343.57  4637.6  342.04
  4671.9  339.74  4713.2   338.4  4725.7  337.38  4747.6  337.27  4758.4  336.68
  4765.5  335.51  4802.1  335.36  4823.9  334.12  4878.4  333.23  4900.3  333.25
  4969.2  334.89  4974.6  333.16  4974.9  332.66  4996.5  334.68  5053.1  334.89
  5068.1   335.9  5107.7  336.66  5114.7   337.7  5151.4  340.08  5227.9   344.4
#Mann= 3 , 0 , 0
  4354.7     .11       0  4969.2     .06       0  4996.5     .11       0
Bank Sta=4969.2,4996.5
XS Rating Curve= 0 ,0
Exp/Cntr=0.3,0.1

Type RM Length L Ch R = 1 ,20820   ,426,426,426
BEGIN DESCRIPTION:
GETER CREEK 35.0
END DESCRIPTION:
XS GIS Cut Line= 3
      3695467.88      10164511.1      3695191.74     10164222.55
      3694567.83     10164261.07
#Sta/Elev= 30
  4600.6  350.07  4777.5  341.23  4862.5  336.34  4883.5  334.38  4890.8  334.67
  4911.8  333.33    4919  333.49  4932.9  332.41  4975.4  330.88  4982.6  329.92
  4987.8  327.77  4996.8  328.73  4999.2   330.8  5004.5   330.8  5013.9  332.65
    5034  333.17  5058.1  336.29    5074  336.23  5104.1  334.16  5114.1  334.12
  5144.2  340.41  5174.2   336.4  5204.3  335.85  5324.5  337.12  5374.6   340.4
  5464.8  344.61  5524.9  346.72  5541.9  348.01  5554.9  347.86  5625.1  350.21
#Mann= 3 ,-1 , 0
  4600.6     .11       0  4975.4     .07       0  4999.2     .11       0
Bank Sta=4975.4,4999.2
XS Rating Curve= 0 ,0
Exp/Cntr=0.3,0.1

Type RM Length L Ch R = 1 ,20394   ,556,556,556
BEGIN DESCRIPTION:
GETER CREEK 34.0
END DESCRIPTION:
XS GIS Cut Line= 3
      3695567.85     10164061.07      3695341.49     10163877.52
       3694846.7     10163851.48
#Sta/Elev= 30
  4683.2  341.13  4686.4  341.13  4690.4  340.27  4719.1  340.03    4740  337.98
  4768.7  336.59  4832.6  334.31    4903  332.67  4917.4  331.52  4953.6  330.27
    4967  329.45  4973.8  328.45    4979  328.45 4989.19325.8975    4996   322.6
  4999.5   322.6  4999.7   323.1 5015.77325.9299  5018.3  326.36  5048.4  326.72
  5058.4  329.63  5068.4  330.53  5088.4  328.79  5128.5  329.83  5138.5  328.43
  5158.5  323.73  5168.5  326.86    5193  330.99  5328.8  337.31  5470.1   341.3
#Mann= 3 , 0 , 0
  4683.2     .11       0 4989.19     .06       0 5015.77     .11       0
Bank Sta=4989.19,5015.77
XS Rating Curve= 0 ,0
Exp/Cntr=0.3,0.1

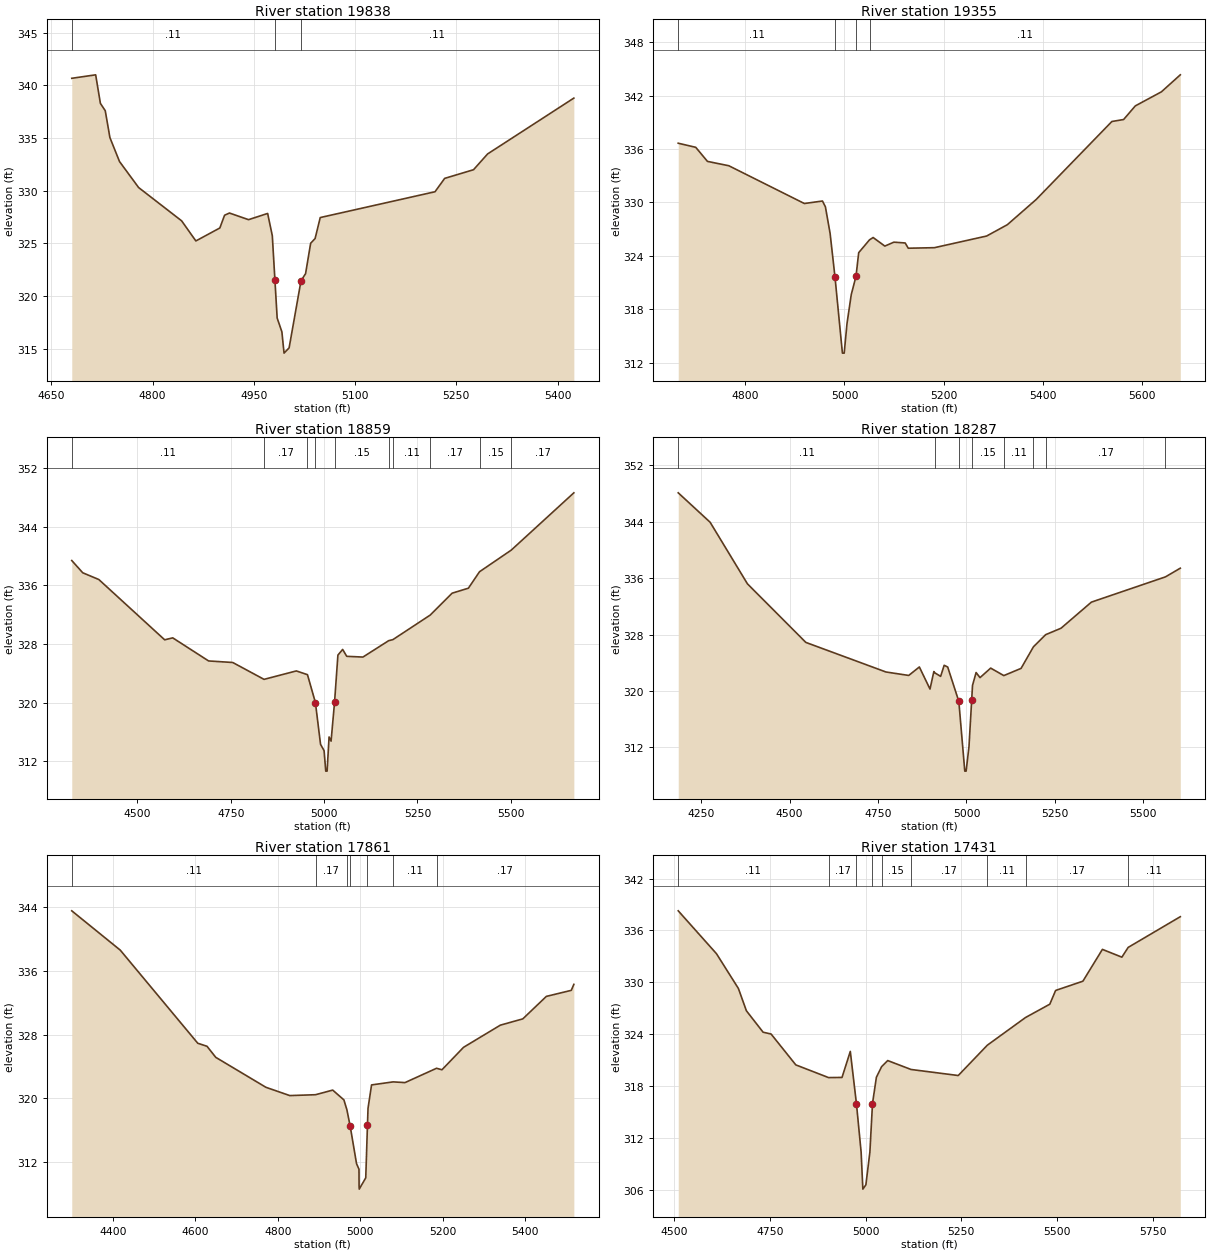
Type RM Length L Ch R = 1 ,19838   ,483,483,483
BEGIN DESCRIPTION:
GETER CREEK 33.0
END DESCRIPTION:
XS GIS Cut Line= 3
      3695667.88      10163611.1      3695437.99     10163389.07
      3695117.85     10163111.07
#Sta/Elev= 30
  4680.4  340.68  4715.8  341.01  4722.8   338.3    4730   337.6  4736.9  335.05
  4751.1  332.78  4779.4  330.31  4843.1  327.15  4864.2  325.24  4899.7  326.47
  4906.7  327.68  4913.9  327.89  4942.2  327.26  4970.5  327.85  4977.4  325.74
  4981.3321.5044  4984.6  317.92  4991.6  316.61  4994.8  314.59  5002.3  315.09
  5019.9  321.45  5026.7  322.14  5034.2  325.02  5040.8  325.47  5048.4  327.46
  5218.4  329.91  5232.7  331.18  5275.4     332  5296.3   333.5    5424   338.8
#Mann= 3 , 0 , 0
  4680.4     .11       0  4981.3     .06       0  5019.9     .11       0
Bank Sta=4981.3,5019.9
XS Rating Curve= 0 ,0
Exp/Cntr=0.3,0.1

Type RM Length L Ch R = 1 ,19355   ,496,496,496
BEGIN DESCRIPTION:
GETER CREEK 32.0
END DESCRIPTION:
XS GIS Cut Line= 3
      3695917.84     10163411.05      3695740.43     10163126.87
      3695117.89     10162861.09
#Sta/Elev= 30
    4665  336.65  4700.3  336.19  4723.9  334.61    4767  334.12  4919.2  329.88
  4955.7  330.16  4961.6  329.51  4971.1  326.52 4980.96321.6131  4995.9  313.08
  4999.5  313.08  5005.1  316.38  5013.7  319.65  5023.3  321.71  5028.7  324.36
  5050.5   325.8  5057.8  326.06  5081.4   325.1  5099.6  325.54  5122.4  325.45
  5128.6  324.86  5181.3  324.92  5286.6  326.23  5328.3   327.5  5386.4  330.33
    5539  339.09  5562.6  339.31  5586.2  340.84  5638.8  342.42  5676.9  344.33
#Mann= 4 ,-1 , 0
    4665     .11       0 4980.96     .09       0  5023.3     .15       0
  5050.5     .11       0
Bank Sta=4980.96,5023.3
XS Rating Curve= 0 ,0
Exp/Cntr=0.3,0.1

Type RM Length L Ch R = 1 ,18859   ,572,572,572
BEGIN DESCRIPTION:
GETER CREEK 31.0
END DESCRIPTION:
XS GIS Cut Line= 3
      3696117.87     10163361.11      3695778.64     10162776.85
      3695517.86      10162161.1
#Sta/Elev= 30
  4324.4  339.38  4353.8  337.71  4396.9  336.79  4573.2  328.57  4594.7  328.84
  4690.8  325.69  4755.4  325.48  4839.2  323.18  4925.7  324.33  4955.5  323.82
 4976.74320.0246  4990.5  314.32    5000  313.46  5004.4  310.67  5008.1  310.67
  5013.3  315.33  5018.7  314.76    5028  320.06    5037  326.49  5049.7  327.26
  5060.6  326.32    5104  326.22  5172.8  328.45  5184.3   328.6    5284  331.94
  5342.9  334.93  5386.4  335.61  5416.1  337.85  5501.1   340.8  5668.7  348.61
#Mann= 10 ,-1 , 0
  4324.4     .11       0  4839.2     .17       0  4955.5     .15       0
 4976.74     .09       0    5028     .15       0  5172.8     .17       0
  5184.3     .11       0    5284     .17       0  5416.1     .15       0
  5501.1     .17       0
Bank Sta=4976.74,5028
XS Rating Curve= 0 ,0
Exp/Cntr=0.3,0.1

Type RM Length L Ch R = 1 ,18287   ,426,426,426
BEGIN DESCRIPTION:
GETER CREEK 30.0
END DESCRIPTION:
XS GIS Cut Line= 3
      3696267.85     10163511.05      3696200.86     10162637.94
      3695883.44     10162195.63
#Sta/Elev= 30
  4184.8  348.08    4275  343.91  4380.6  335.18  4545.8  326.88  4772.3  322.69
  4836.7   322.2  4866.8   323.4  4896.9  320.27  4907.8  322.75  4911.1  322.55
    4927  322.07    4937  323.64    4947  323.39 4978.43318.5266  4995.3  308.64
  4999.1  308.64  5007.2  312.13  5014.8318.7188  5017.2   320.8  5027.3  322.61
  5038.4  321.89  5068.5  323.24  5105.7  322.18  5154.5   323.2  5189.5  326.26
  5224.1  327.98  5267.5  328.89  5353.4  332.59  5562.9  336.17  5604.9   337.4
#Mann= 8 ,-1 , 0
  4184.8     .11       0  4911.1     .15       0 4978.43     .09       0
  5014.8     .15       0  5105.7     .11       0  5189.5     .15       0
  5224.1     .17       0  5562.9     .11       0
Bank Sta=4978.43,5014.8
XS Rating Curve= 0 ,0
Exp/Cntr=0.3,0.1

Type RM Length L Ch R = 1 ,17861   ,430,430,430
BEGIN DESCRIPTION:
GETER CREEK 29.0
END DESCRIPTION:
XS GIS Cut Line= 3
      3697067.88     10162861.09      3696472.59      10162493.2
      3696008.13     10162262.93
#Sta/Elev= 30
  4300.2  343.55  4417.8  338.62  4605.9  326.93  4628.3  326.55  4649.6  325.16
  4771.3   321.4  4829.2  320.36  4891.7  320.47  4933.3  321.05  4960.5  319.82
  4967.7  318.59  4975.8   316.5  4991.2  311.81  4997.1  311.12  4997.3  309.12
  4997.7  308.62  5013.5  310.04 5017.72 316.731    5019  318.76  5027.6   321.7
    5080  322.08  5108.7  321.99  5185.3  323.79  5198.4   323.6  5250.8  326.42
  5340.1   329.2  5394.6  329.99  5451.7  332.81  5512.2  333.57  5518.4  334.32
#Mann= 7 ,-1 , 0
  4300.2     .11       0  4891.7     .17       0  4967.7     .15       0
  4975.8     .09       0 5017.72     .15       0    5080     .11       0
  5185.3     .17       0
Bank Sta=4975.8,5017.72
XS Rating Curve= 0 ,0
Exp/Cntr=0.3,0.1

Type RM Length L Ch R = 1 ,17431   ,566,566,566
BEGIN DESCRIPTION:
GETER CREEK 28.0
END DESCRIPTION:
XS GIS Cut Line= 3
      3697117.87     10162561.09       3696726.9     10162268.15
      3695917.85     10162111.07
#Sta/Elev= 30
    4510  338.27    4610  333.31  4667.3  329.29  4688.2  326.71  4731.9  324.23
  4752.8  324.02  4817.4  320.45  4903.1  318.98  4938.2     319  4959.9  322.01
 4975.98315.9437  4988.2  310.35  4992.7  306.08  5000.6  306.58  5011.1  310.37
  5017.9  315.98  5028.1  319.02  5041.8  320.25  5057.7  320.95  5118.6  319.92
  5242.1  319.22  5318.2  322.73    5418  325.93  5481.5  327.47  5496.7  329.06
    5568  330.13    5619  333.81  5669.9  332.91  5686.4  334.04  5822.7  337.59
#Mann= 9 ,-1 , 0
    4510     .11       0  4903.1     .17       0 4975.98     .09       0
  5017.9     .17       0  5041.8     .15       0  5118.6     .17       0
  5318.2     .11       0    5418     .17       0  5686.4     .11       0
Bank Sta=4975.98,5017.9
XS Rating Curve= 0 ,0
Exp/Cntr=0.3,0.1

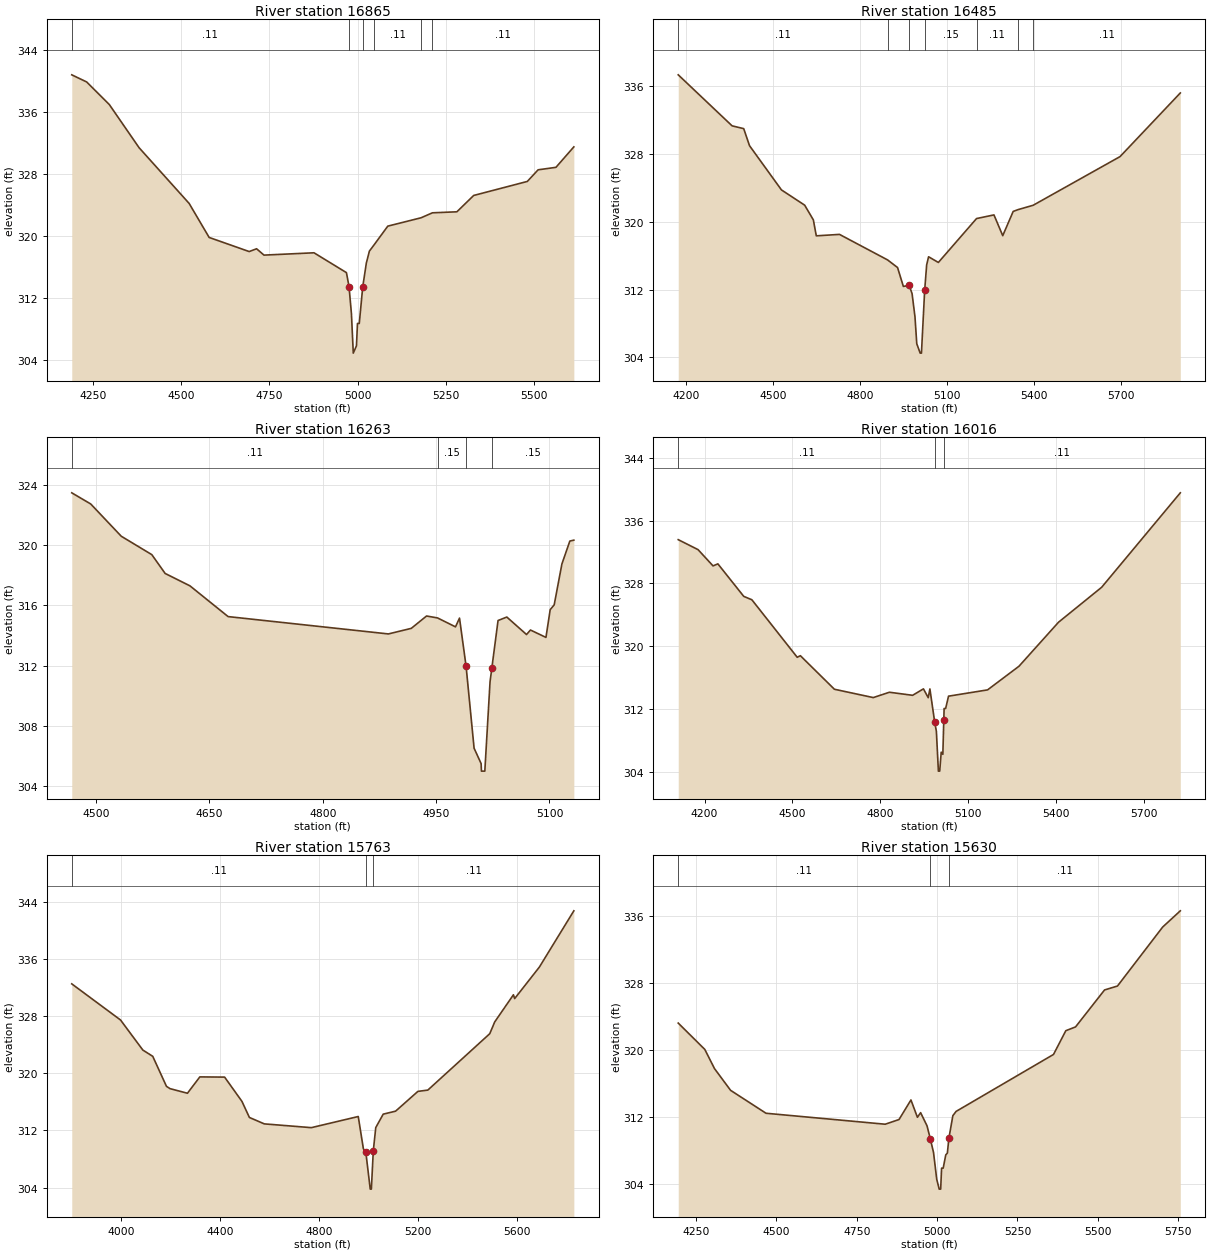
Type RM Length L Ch R = 1 ,16865   ,380,380,380
BEGIN DESCRIPTION:
GETER CREEK 27.0
END DESCRIPTION:
XS GIS Cut Line= 3
      3697367.84     10162311.06       3696772.2     10161762.14
      3696167.89     10161661.08
#Sta/Elev= 30
    4190  340.86  4232.2  339.94  4296.3  337.03  4380.8  331.45  4522.6  324.26
  4579.3  319.87  4692.7  318.05  4713.7  318.41  4734.7  317.59  4876.4  317.89
  4968.3  315.33  4975.7  313.52  4982.5     310  4987.7  304.94  4996.7  305.88
  4999.6  308.77  5004.7  308.77  5014.5  313.49  5024.7  316.56  5033.3   318.1
  5046.1  318.88  5085.5  321.33  5179.9  322.41    5212  323.05  5281.3  323.18
  5328.9  325.29  5480.9   327.1  5511.4   328.6    5562  328.92  5612.7  331.56
#Mann= 6 ,-1 , 0
    4190     .11       0  4975.7     .09       0  5014.5     .15       0
  5046.1     .11       0  5179.9     .15       0    5212     .11       0
Bank Sta=4975.7,5014.5
XS Rating Curve= 0 ,0
Exp/Cntr=0.3,0.1

Type RM Length L Ch R = 1 ,16485   ,222,222,222
BEGIN DESCRIPTION:
GETER CREEK 26.0
END DESCRIPTION:
XS GIS Cut Line= 3
      3697763.34     10161497.31      3696940.45     10161450.44
      3696041.09      10161575.2
#Sta/Elev= 30
  4173.5  337.34  4359.3  331.32  4399.4  330.99  4419.4  328.98  4529.6  323.76
  4609.7  321.96  4639.7  320.22  4649.8  318.34  4729.9  318.51  4895.7   315.5
  4930.2   314.6  4950.2  312.37  4970.3  312.49  4980.3  311.52  4990.3  308.79
  4996.5   305.6  5008.3   304.5  5012.6   304.5 5023.71311.9152  5030.6  314.91
  5037.2  315.87    5071   315.2  5202.7  320.38  5262.8  320.81  5293.1  318.36
  5329.1  321.22  5345.7  321.43  5398.2  321.95  5697.8  327.69  5905.7   335.2
#Mann= 7 ,-1 , 0
  4173.5     .11       0  4895.7     .15       0  4970.3     .09       0
 5023.71     .15       0  5202.7     .11       0  5345.7     .15       0
  5398.2     .11       0
Bank Sta=4970.3,5023.71
XS Rating Curve= 0 ,0
Exp/Cntr=0.3,0.1

Type RM Length L Ch R = 1 ,16263   ,247,247,247
BEGIN DESCRIPTION:
Mapping XS 5f6da24c
END DESCRIPTION:
XS GIS Cut Line= 3
      3697402.67     10161293.75      3696927.45     10161226.49
      3696752.91     10161286.09
#Sta/Elev= 30
  4467.9  323.47    4493  322.73  4533.4  320.59  4573.8  319.37  4591.5  318.12
  4624.3   317.3  4674.8  315.26  4886.9  314.11  4917.2  314.48  4937.4   315.3
    4952  315.17  4975.7  314.58    4981  315.16  4989.7  311.97  5000.3  306.53
  5009.6  305.51    5010  305.01  5014.5  305.01  5021.4  310.93 5023.79311.8477
    5032     315  5043.6  315.23  5069.7  314.07  5074.9  314.37  5095.4  313.88
    5101  315.72  5106.3  316.04  5116.5  318.75    5127  320.27  5132.3  320.33
#Mann= 4 ,-1 , 0
  4467.9     .11       0    4952     .15       0  4989.7     .09       0
 5023.79     .15       0
Bank Sta=4989.7,5023.79
XS Rating Curve= 0 ,0
Exp/Cntr=0.3,0.1

Type RM Length L Ch R = 1 ,16016   ,253,253,253
BEGIN DESCRIPTION:
GETER CREEK 25.0
END DESCRIPTION:
XS GIS Cut Line= 3
      3697667.87     10161411.08      3696862.32      10160992.1
      3696075.91     10160815.03
#Sta/Elev= 30
    4110  333.57  4177.7   332.3  4228.8  330.23  4245.3  330.49  4333.7  326.35
  4361.4  325.92  4516.2   318.6    4527   318.8  4643.2  314.53  4775.9  313.47
  4830.9  314.15  4910.3  313.76  4947.1  314.58  4963.5  313.46  4969.2  314.57
  4985.7  310.31  4991.3  309.18  4998.2  304.11  5002.7  304.11  5007.8  306.52
  5013.4  306.25 5016.58310.5614  5017.7  312.08  5022.9  312.08  5032.8  313.65
  5166.1  314.45  5273.4  317.46  5408.3  323.06  5555.6  327.51  5824.1  339.53
#Mann= 3 , 0 , 0
    4110     .11       0  4985.7     .06       0 5016.58     .11       0
Bank Sta=4985.7,5016.58
XS Rating Curve= 0 ,0
Exp/Cntr=0.3,0.1

Type RM Length L Ch R = 1 ,15763   ,133,133,133
BEGIN DESCRIPTION:
Mapping XS 84aa14e5
END DESCRIPTION:
XS GIS Cut Line= 2
      3698044.65     10160830.65      3696018.53     10160700.43
#Sta/Elev= 30
    3801  332.53  3998.2  327.47  4088.4  323.26  4128.5  322.38  4183.9  318.18
  4198.6  317.85  4268.8  317.21  4318.9   319.5  4419.1  319.47  4489.2  316.07
  4519.3  313.82  4579.4  312.92  4769.8  312.39  4959.5  313.95  4980.2  309.44
  4990.2  308.93    5008  303.78  5012.5  303.78  5020.3  309.14  5030.3   312.4
  5060.4  314.28  5110.5   314.7  5200.7  317.47  5240.8  317.65  5491.3  325.55
  5511.3   327.2    5587     331    5592  330.47  5691.7  334.87  5831.3  342.76
#Mann= 3 , 0 , 0
    3801     .11       0  4990.2     .06       0  5020.3     .11       0
Bank Sta=4990.2,5020.3
XS Rating Curve= 0 ,0
Exp/Cntr=0.3,0.1

Type RM Length L Ch R = 1 ,15630   ,417,417,417
BEGIN DESCRIPTION:
GETER CREEK 24.0
END DESCRIPTION:
XS GIS Cut Line= 3
      3697690.42      10160679.6      3696872.74     10160627.52
      3696133.17     10160559.81
#Sta/Elev= 30
  4194.6  323.22  4277.3  320.07  4307.4  317.78  4357.5  315.18  4467.7  312.44
  4838.5  311.13  4881.5  311.69  4918.6  314.03  4938.7  311.96  4948.7  312.51
  4968.7  310.93  4978.8  309.39  4988.8  307.76  4998.8  304.55  5006.5  303.37
  5011.1  303.37  5013.9  305.88  5018.9  305.88  5026.9  307.46  5031.9  307.68
 5036.66309.4617    5049  312.15    5059  312.66  5362.1  319.47  5400.4  322.31
  5430.6  322.76  5520.9  327.18  5561.1  327.65  5701.7   334.7  5756.6  336.64
#Mann= 3 , 0 , 0
  4194.6     .11       0  4978.8     .06       0 5036.66     .11       0
Bank Sta=4978.8,5036.66
XS Rating Curve= 0 ,0
Exp/Cntr=0.3,0.1

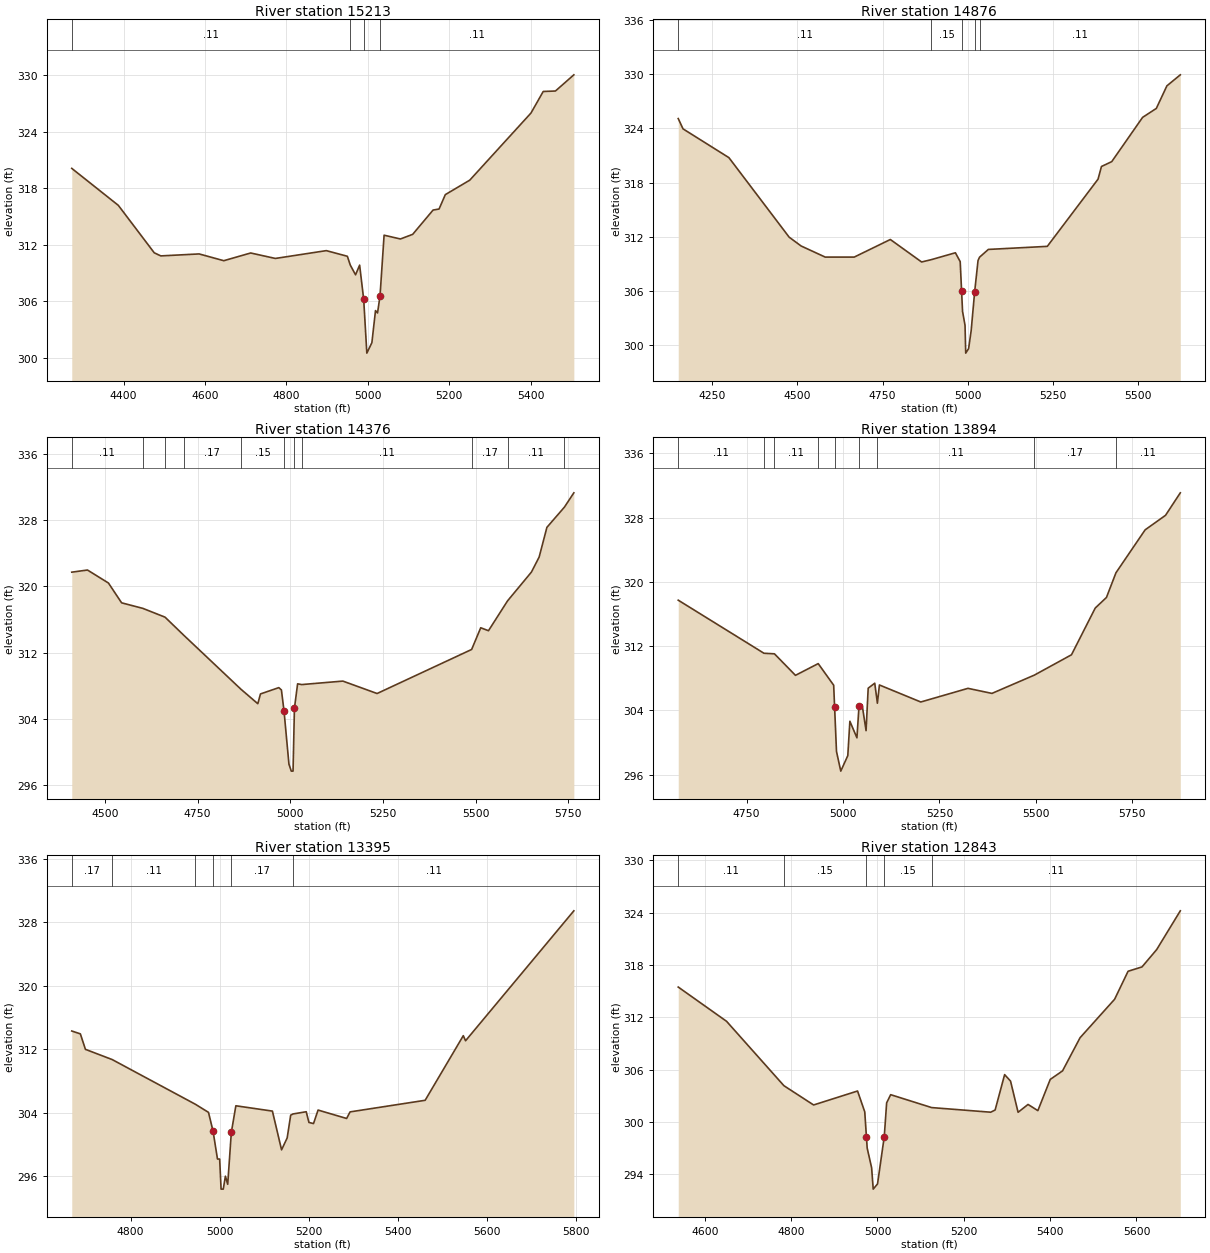
Type RM Length L Ch R = 1 ,15213   ,337,337,337
BEGIN DESCRIPTION:
Mapping XS fc2fac8a
END DESCRIPTION:
XS GIS Cut Line= 3
      3697591.51     10160590.63      3697025.11     10160293.33
      3696432.79     10160254.27
#Sta/Elev= 30
  4272.9  320.12  4387.3  316.19  4475.5  311.15  4491.6  310.82  4585.8  311.03
  4646.3  310.31  4712.4  311.13    4773  310.55  4898.2  311.38  4949.9  310.78
  4956.9  309.86    4970  308.81    4980  309.84    4990   306.2  4997.7  300.49
  5010.1   301.6    5019  305.01    5024  304.76  5030.1  306.57  5040.1  313.02
  5080.2  312.62  5110.3  313.11  5160.4  315.69  5175.1   315.8  5190.5  317.33
  5250.6  318.87  5400.9     326    5431  328.29    5461  328.34  5506.2  330.06
#Mann= 4 ,-1 , 0
  4272.9     .11       0  4956.9     .15       0    4990     .06       0
  5030.1     .11       0
Bank Sta=4990,5030.1
XS Rating Curve= 0 ,0
Exp/Cntr=0.3,0.1

Type RM Length L Ch R = 1 ,14876   ,500,500,500
BEGIN DESCRIPTION:
GETER CREEK 23.0
END DESCRIPTION:
XS GIS Cut Line= 3
      3697717.87     10160661.09      3697137.71     10160039.74
       3696517.9     10160111.07
#Sta/Elev= 30
  4149.9  325.09  4163.9  323.95  4298.7  320.76  4475.5  311.96  4510.7  310.98
  4581.5  309.75  4666.5  309.75  4772.6   311.7  4864.4  309.21  4893.1  309.47
  4963.6  310.23  4977.7  309.25 4981.84305.9442  4984.6  303.74  4991.9  302.19
  4993.9  299.12  5002.4  299.62  5009.9  301.61    5020  305.86  5030.1  309.38
  5034.5  309.74  5060.3   310.6  5233.4  310.94  5382.4  318.38  5392.4  319.78
  5422.6  320.32  5513.2  325.22  5553.5  326.21  5584.5  328.71  5623.9  329.93
#Mann= 5 ,-1 , 0
  4149.9     .11       0  4893.1     .15       0 4981.84     .09       0
    5020     .15       0  5034.5     .11       0
Bank Sta=4981.84,5020
XS Rating Curve= 0 ,0
Exp/Cntr=0.3,0.1

Type RM Length L Ch R = 1 ,14376   ,482,482,482
BEGIN DESCRIPTION:
GETER CREEK 22.0
END DESCRIPTION:
XS GIS Cut Line= 3
      3697817.89      10160211.1      3697394.11     10159801.18
      3696767.88     10159361.09
#Sta/Elev= 30
  4410.4  321.72  4452.8  321.98  4509.4  320.41  4544.9  318.02  4602.2  317.35
  4662.1  316.29  4712.1  314.13  4866.9  307.59  4912.5  305.84  4919.7  307.02
  4969.1  307.78  4976.2   307.5  4983.2  304.98  4996.5  298.54  5002.8   297.7
  5007.6   297.7  5011.3  305.28  5019.9  308.24    5031  308.15    5142  308.57
  5234.4  307.07  5489.6  312.39  5514.1  315.01    5535  314.65  5586.4  318.25
  5650.9  321.73  5671.8  323.55  5692.7  327.13  5739.9  329.57  5765.4   331.3
#Mann= 11 ,-1 , 0
  4410.4     .11       0  4602.2     .17       0  4662.1     .11       0
  4712.1     .17       0  4866.9     .15       0  4983.2     .09       0
  5011.3     .15       0    5031     .11       0  5489.6     .17       0
  5586.4     .11       0  5739.9     .17       0
Bank Sta=4983.2,5011.3
XS Rating Curve= 0 ,0
Exp/Cntr=0.3,0.1

Type RM Length L Ch R = 1 ,13894   ,499,499,499
BEGIN DESCRIPTION:
GETER CREEK 21.0
END DESCRIPTION:
XS GIS Cut Line= 3
      3697967.85     10159811.07      3697673.69     10159501.15
      3696867.81     10159161.05
#Sta/Elev= 30
  4572.7  317.73    4795  311.12  4822.2  311.05  4876.7  308.37  4935.7  309.83
  4975.8  307.14 4978.19 304.439  4983.1  298.89  4994.2  296.44  5012.4  298.37
  5017.8  302.65  5036.1  300.59  5041.5  304.54  5049.7  304.66  5059.8  301.48
  5065.3  306.77  5082.3  307.39  5089.2   304.9  5094.4  307.17  5201.7  305.05
  5324.1  306.75  5386.2  306.12  5496.3   308.4  5592.5  310.93  5654.1  316.75
  5683.2  318.07  5707.9  321.15  5783.5  326.49  5836.4   328.3  5874.7   331.1
#Mann= 9 ,-1 , 0
  4572.7     .11       0    4795     .17       0  4822.2     .11       0
  4935.7     .17       0 4978.19     .09       0  5041.5     .17       0
  5089.2     .11       0  5496.3     .17       0  5707.9     .11       0
Bank Sta=4978.19,5041.5
XS Rating Curve= 0 ,0
Exp/Cntr=0.3,0.1

Type RM Length L Ch R = 1 ,13395   ,552,552,552
BEGIN DESCRIPTION:
GETER CREEK 20.0
END DESCRIPTION:
XS GIS Cut Line= 3
      3698117.85     10159561.08      3698046.23     10159236.59
      3697867.84     10158461.04
#Sta/Elev= 30
  4667.7   314.3    4687  313.94  4698.4  311.99  4758.6   310.7  4945.5  305.07
  4974.9  304.05  4985.2  301.67  4995.1  298.17    5000  298.17  5003.2  294.38
  5008.1  294.38  5012.9  296.01  5018.1  294.99  5026.2  301.52  5036.4  304.88
  5118.5  304.21  5139.1  299.33  5151.7  300.83  5159.6   303.7  5164.9  303.85
  5194.5  304.13  5200.6  302.78  5210.9  302.64  5221.1  304.34  5285.3  303.28
    5293  304.11  5461.7  305.57  5547.4  313.71  5552.5  313.07  5795.8  329.44
#Mann= 6 ,-1 , 0
  4667.7     .17       0  4758.6     .11       0  4945.5     .17       0
  4985.2     .09       0  5026.2     .17       0  5164.9     .11       0
Bank Sta=4985.2,5026.2
XS Rating Curve= 0 ,0
Exp/Cntr=0.3,0.1

Type RM Length L Ch R = 1 ,12843   ,419,419,419
BEGIN DESCRIPTION:
GETER CREEK 19.0
END DESCRIPTION:
XS GIS Cut Line= 3
      3698667.84     10159511.04      3698461.28     10159101.48
      3698167.86      10158461.1
#Sta/Elev= 30
  4538.5  315.46  4650.5  311.53  4783.3  304.15  4852.1  301.94  4953.9  303.54
  4970.6  301.15 4974.46298.2896  4976.2     297  4986.5  294.74  4990.2  292.29
  5000.2  292.89  5015.8  298.32  5021.3  302.18  5030.6  303.12  5125.5  301.64
  5262.3  301.11  5272.6  301.36  5294.6  305.42  5308.3  304.68  5325.8   301.1
  5348.8     302  5371.6  301.29  5400.3  304.87  5428.8  305.85  5469.4  309.65
  5549.4  314.06  5580.6  317.27  5612.9  317.77  5646.9  319.76  5701.6   324.2
#Mann= 5 ,-1 , 0
  4538.5     .11       0  4783.3     .15       0 4974.46     .09       0
  5015.8     .15       0  5125.5     .11       0
Bank Sta=4974.46,5015.8
XS Rating Curve= 0 ,0
Exp/Cntr=0.3,0.1

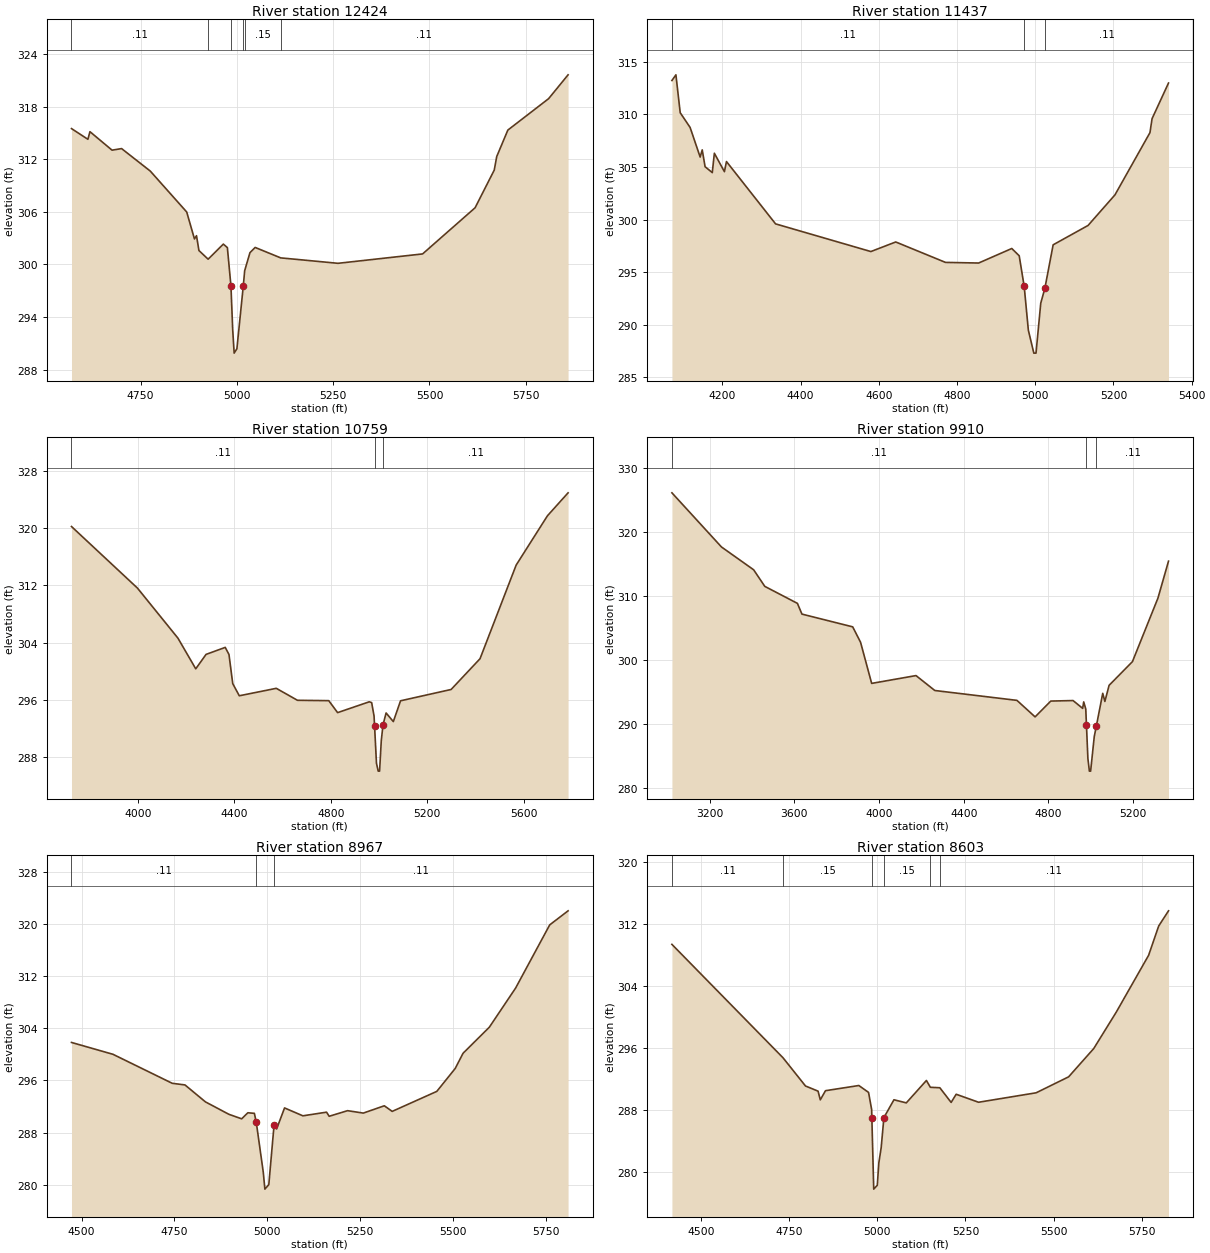
Type RM Length L Ch R = 1 ,12424   ,987,987,987
BEGIN DESCRIPTION:
GETER CREEK 18.0
END DESCRIPTION:
XS GIS Cut Line= 3
      3698987.33     10159544.23      3698848.64     10159137.74
      3698317.86     10158461.08
#Sta/Elev= 30
  4570.5  315.49  4613.1  314.27  4618.4  315.14  4675.8  313.03  4700.6  313.21
    4775  310.65  4869.7  305.98  4889.8  302.91  4895.1  303.28  4901.4  301.59
  4925.3   300.6  4964.8  302.32  4975.3  301.92 4984.58297.5262  4989.1  292.58
  4992.9  289.89    5000  290.39 5016.65297.5675  5020.2  299.29  5033.9  301.34
  5047.4  301.94  5113.7  300.75  5262.5  300.13  5482.2   301.2  5618.5  306.46
  5668.3  310.76  5674.7   312.3  5703.6  315.32  5809.4   318.9    5860  321.62
#Mann= 6 ,-1 , 0
  4570.5     .11       0  4925.3     .15       0 4984.58     .09       0
 5016.65     .12       0  5020.2     .15       0  5113.7     .11       0
Bank Sta=4984.58,5016.65
XS Rating Curve= 0 ,0
Exp/Cntr=0.3,0.1

Type RM Length L Ch R = 1 ,11437   ,678,678,678
BEGIN DESCRIPTION:
GETER CREEK 17.0
END DESCRIPTION:
XS GIS Cut Line= 3
      3699117.84     10159511.11      3699425.38      10158634.5
      3699317.86      10158311.1
#Sta/Elev= 30
    4071  313.21  4081.2  313.75  4092.2  310.15  4117.5  308.75  4143.2  305.94
  4148.5  306.62  4155.8  305.02  4174.2  304.46  4179.5   306.3  4205.2  304.55
  4210.5  305.51    4336  299.59  4579.7  296.96  4643.3  297.87  4770.5  295.93
  4855.3  295.87    4940  297.25    4959  296.56  4971.8  293.64  4982.4  289.49
  4996.4  287.31    5002  287.31  5014.1  292.05  5024.7  293.48  5045.8   297.6
  5135.1  299.44  5203.8  302.34  5293.4  308.26  5298.7  309.58  5340.8  312.97
#Mann= 3 , 0 , 0
    4071     .11       0  4971.8     .06       0  5024.7     .11       0
Bank Sta=4971.8,5024.7
XS Rating Curve= 0 ,0
Exp/Cntr=0.3,0.1

Type RM Length L Ch R = 1 ,10759   ,849,849,849
BEGIN DESCRIPTION:
Mapping XS dbb2ed74
END DESCRIPTION:
XS GIS Cut Line= 3
      3699336.27     10159716.08      3699919.61      10158742.1
      3699924.82     10157815.52
#Sta/Elev= 30
  3723.2   320.2  3997.1  311.61  4165.2  304.63  4239.1  300.35  4281.8  302.36
  4361.5  303.34  4377.1  302.35  4392.7  298.29  4419.9  296.59  4573.5  297.63
  4661.5  295.96  4791.3  295.91  4828.2  294.24  4959.5  295.75  4969.5  295.64
  4979.5  293.76 4981.53292.4244  4989.5  287.18  4996.7  286.08  5002.4  286.08
  5009.5  290.34 5016.69292.5401  5029.5  294.19  5059.5  292.99  5089.5  295.89
  5299.5  297.47  5419.5  301.76  5569.5  314.82  5699.5   321.7  5785.1   324.9
#Mann= 3 , 0 , 0
  3723.2     .11       0 4981.53     .06       0 5016.69     .11       0
Bank Sta=4981.53,5016.69
XS Rating Curve= 0 ,0
Exp/Cntr=0.3,0.1

Type RM Length L Ch R = 1 ,9910    ,943,943,943
BEGIN DESCRIPTION:
GETER CREEK 16.0
END DESCRIPTION:
XS GIS Cut Line= 3
      3699388.35     10159992.13       3700346.7     10158377.52
      3700317.85     10157911.11
#Sta/Elev= 30
    3022  326.12  3255.8  317.67  3407.9   314.1  3460.6  311.51  3614.5  308.86
    3636  307.18  3875.6  305.19  3912.7  302.79  3965.2  296.36  4174.5  297.58
  4263.4  295.25  4651.2  293.71  4736.9  291.13    4811   293.6  4916.1  293.68
  4961.5  292.46  4966.5  293.47  4976.2  292.35 4979.49289.8134  4986.2  284.64
  4993.3  282.66  4999.1  282.66  5016.3  288.06  5026.3  289.72  5056.3  294.81
  5066.4  293.54  5086.4  296.06  5196.6  299.76  5316.8  309.66  5366.9  315.45
#Mann= 3 ,-1 , 0
    3022     .11       0 4979.49     .06       0  5026.3     .11       0
Bank Sta=4979.49,5026.3
XS Rating Curve= 0 ,0
Exp/Cntr=0.3,0.1

Type RM Length L Ch R = 1 ,8967    ,364,364,364
BEGIN DESCRIPTION:
GETER CREEK 15.0
END DESCRIPTION:
XS GIS Cut Line= 3
      3701035.05     10158888.77      3700894.18     10158380.74
      3700317.82     10157811.04
#Sta/Elev= 30
  4472.8  301.83  4584.6  300.01  4744.2  295.56  4778.5  295.31  4833.6  292.71
  4896.9   290.8  4931.2  290.11  4947.8  291.04  4965.4  290.95  4970.6  289.55
  4989.3  281.95  4993.7  279.32  5004.3  280.01  5018.4  289.13  5025.4  288.56
  5046.7  291.78  5096.1  290.57  5159.8  291.13  5166.9   290.5  5216.4  291.36
  5258.8  290.99  5315.4  292.11  5336.6  291.25  5456.8  294.32  5506.3  297.83
  5527.5  300.17  5598.3  304.17    5669  310.17  5760.9  319.87  5810.4  322.03
#Mann= 3 , 0 , 0
  4472.8     .11       0  4970.6     .06       0  5018.4     .11       0
Bank Sta=4970.6,5018.4
XS Rating Curve= 0 ,0
Exp/Cntr=0.3,0.1

Type RM Length L Ch R = 1 ,8603    ,631,631,631
BEGIN DESCRIPTION:
GETER CREEK 14.0
END DESCRIPTION:
XS GIS Cut Line= 3
      3701624.47     10158631.86      3701147.04       10158302.
      3700517.89      10157761.1
#Sta/Elev= 30
  4416.5  309.32  4732.1  294.68  4795.7  291.05  4831.5  290.38  4837.8  289.26
  4852.5  290.44  4947.2  291.11  4974.8  290.22  4983.6  288.01 4984.21286.9066
  4989.5  277.74  4999.6  278.24  5004.1  281.16  5010.7  283.11  5018.4  286.97
  5046.9  289.27    5082  288.87  5139.1  291.76  5150.3  290.88  5177.2  290.82
  5209.3  288.93  5223.6  289.98  5287.2  288.95  5450.7  290.17  5542.9  292.23
  5614.2  295.88  5677.9  300.56    5770  307.91  5798.6  311.69  5826.5  313.65
#Mann= 6 ,-1 , 0
  4416.5     .11       0  4732.1     .15       0 4984.21     .09       0
  5018.4     .15       0  5150.3     .17       0  5177.2     .11       0
Bank Sta=4984.21,5018.4
XS Rating Curve= 0 ,0
Exp/Cntr=0.3,0.1