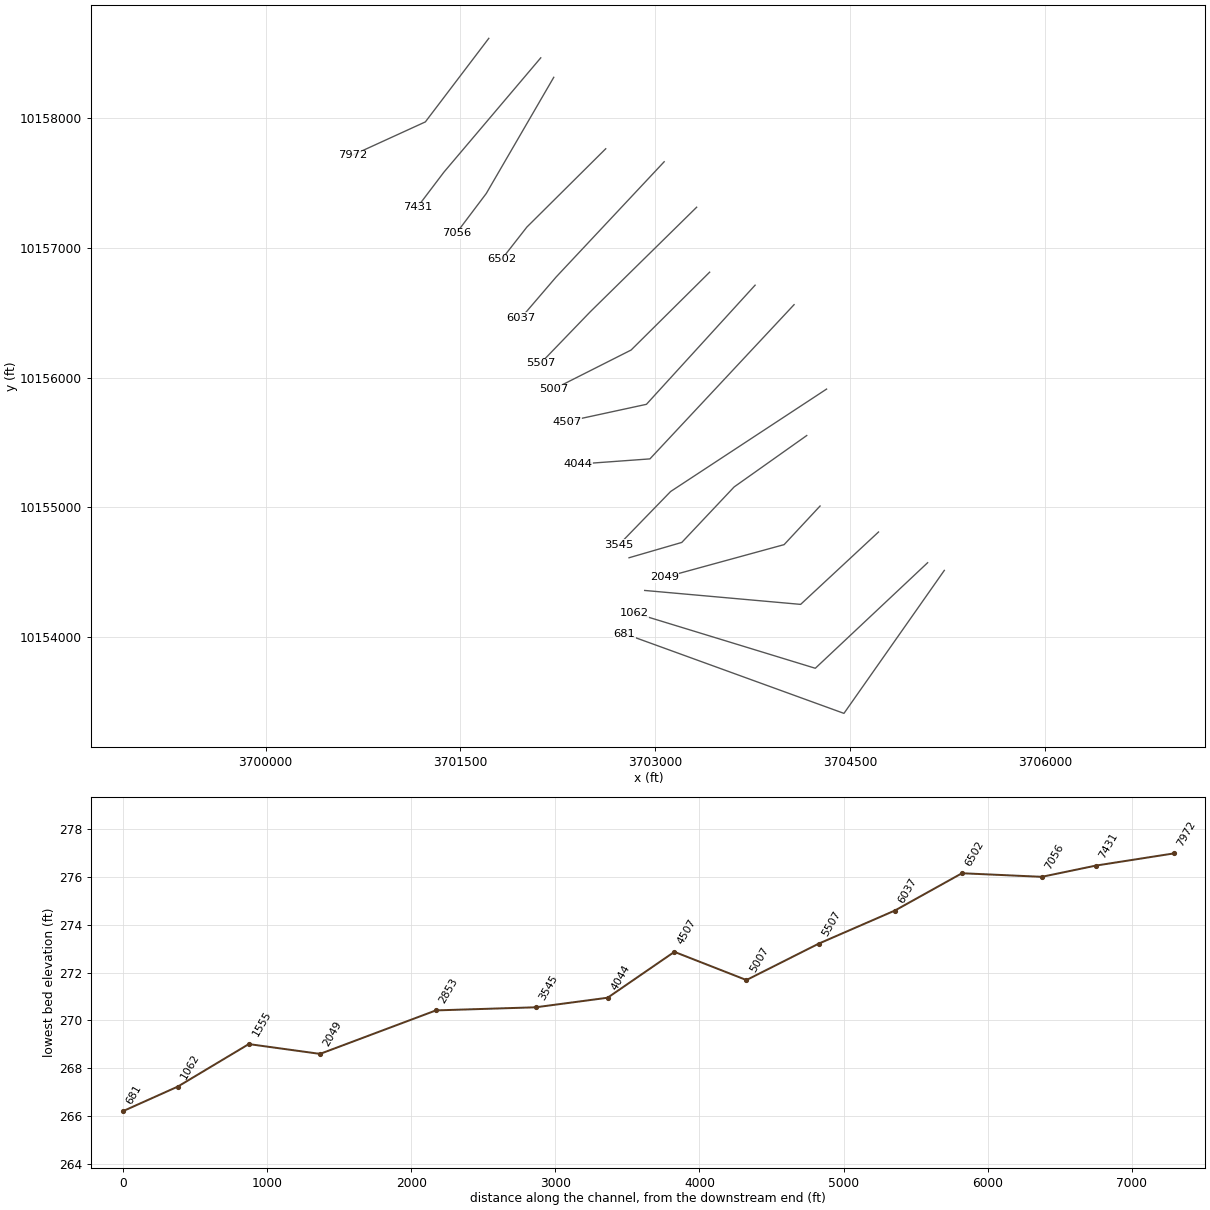
HEC-RAS study GETER CREEK.prj: GETER CREEK Base Level Engineering

--- GETER CREEK.g01 (geometry) --- (continued)

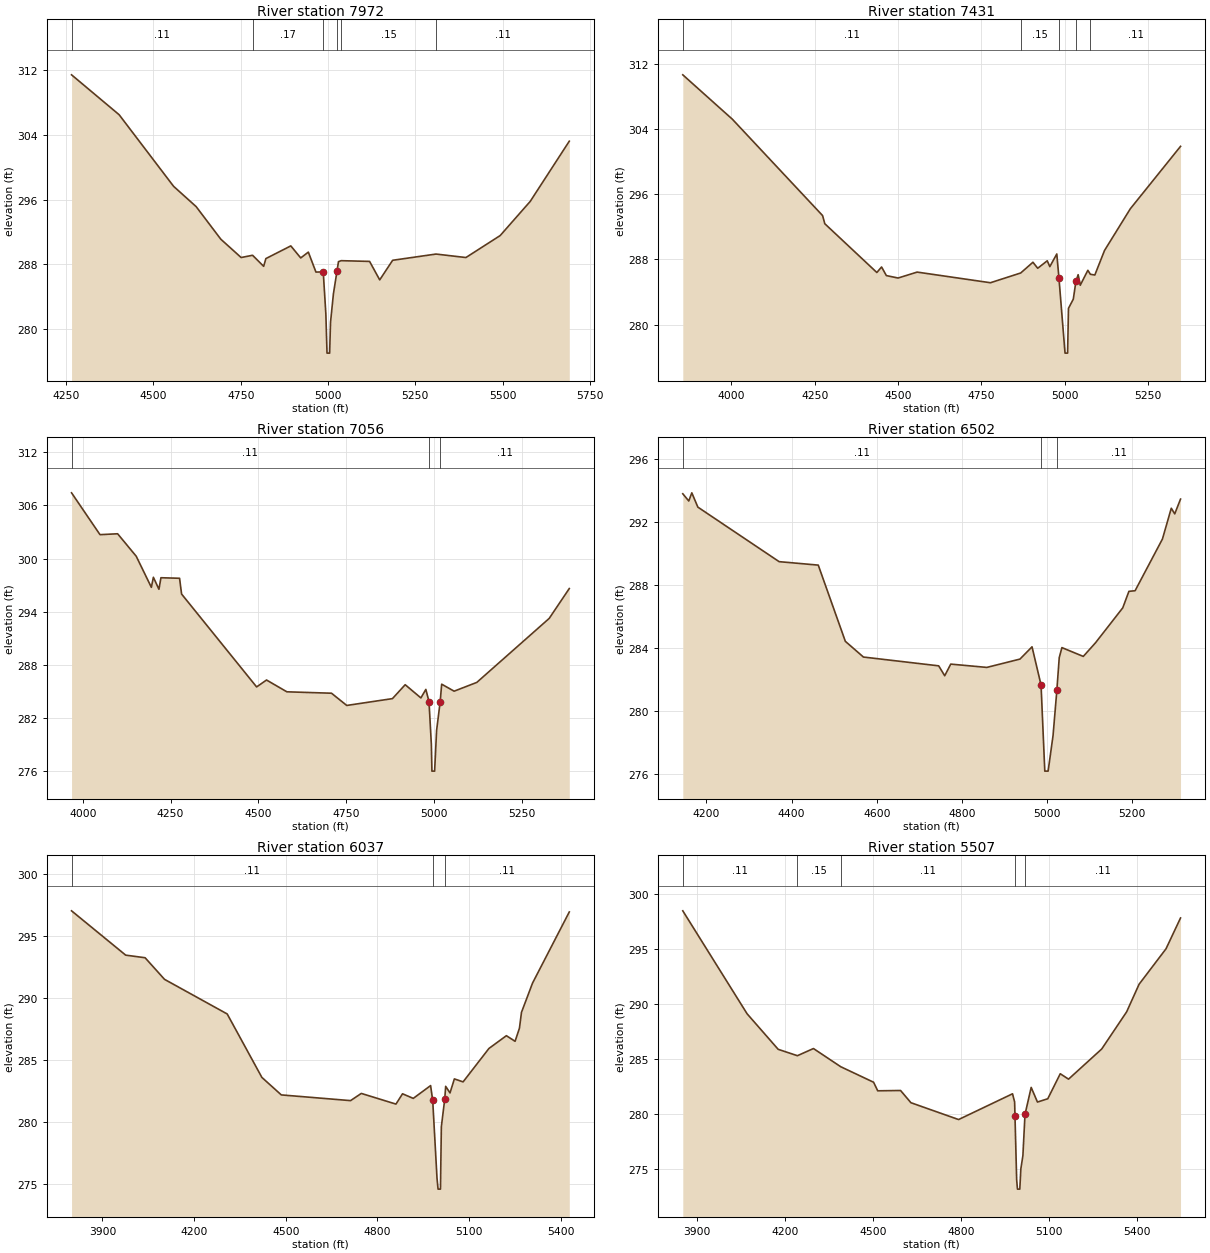
Type RM Length L Ch R = 1 ,7972    ,541,541,541
BEGIN DESCRIPTION:
GETER CREEK 13.0
END DESCRIPTION:
XS GIS Cut Line= 3
      3701717.85     10158611.08      3701229.51      10157967.8
      3700667.84     10157711.07
#Sta/Elev= 30
  4265.6  311.46  4401.8  306.52  4557.8  297.65  4622.3  295.14    4693   291.1
  4751.2  288.83  4783.9  289.11  4815.7  287.74    4822   288.7  4893.4  290.27
  4921.8  288.78  4943.6   289.5  4965.4  287.03  4986.3  287.05  4993.8  281.81
  4997.1  276.99  5004.6  276.99  5007.1   280.8  5015.4  284.33 5025.71 287.164
  5029.9  288.32  5037.7  288.44    5119  288.35    5148  286.06    5185  288.49
  5309.2  289.26  5394.8  288.83  5492.9  291.55  5578.9  295.78  5690.8  303.24
#Mann= 6 ,-1 , 0
  4265.6     .11       0  4783.9     .17       0  4986.3     .09       0
 5025.71     .17       0  5037.7     .15       0  5309.2     .11       0
Bank Sta=4986.3,5025.71
XS Rating Curve= 0 ,0
Exp/Cntr=0.3,0.1

Type RM Length L Ch R = 1 ,7431    ,375,375,375
BEGIN DESCRIPTION:
GETER CREEK 12.0
END DESCRIPTION:
XS GIS Cut Line= 3
      3702117.83     10158461.05      3701372.74     10157581.51
      3701167.85     10157311.07
#Sta/Elev= 30
  3854.8  310.72  4003.6  305.25  4273.9   293.4  4280.5   292.4  4436.5   286.4
  4450.7  287.08    4465  286.02  4500.2  285.72  4557.3  286.45    4777  285.14
  4867.7  286.34  4904.4  287.66  4918.7  286.92  4947.3  287.84    4955  287.12
  4975.9  288.68  4982.4  285.71  5000.6  276.48  5008.3  276.48  5010.9  281.99
  5025.4  283.12  5033.2   285.3  5039.9  286.13  5046.2  284.83    5069  286.67
  5076.6  286.18  5089.9  286.09    5119  289.11  5196.3  294.24  5346.8  301.92
#Mann= 5 ,-1 , 0
  3854.8     .11       0  4867.7     .15       0  4982.4     .09       0
  5033.2     .15       0  5076.6     .11       0
Bank Sta=4982.4,5033.2
XS Rating Curve= 0 ,0
Exp/Cntr=0.3,0.1

Type RM Length L Ch R = 1 ,7056    ,554,554,554
BEGIN DESCRIPTION:
GETER CREEK 11.0
END DESCRIPTION:
XS GIS Cut Line= 3
      3702217.85     10158311.07      3701698.26     10157416.58
      3701467.86     10157111.08
#Sta/Elev= 30
    3968  307.41    4049  302.69  4099.2  302.79  4152.2  300.25  4195.2  296.75
    4201  297.88  4216.8  296.53  4222.5  297.83  4275.5  297.77  4281.3  295.99
  4494.9  285.51  4523.1  286.29    4581  284.96  4708.1   284.8  4751.5  283.42
  4881.6  284.19  4917.9  285.76  4962.6  284.27  4976.7  285.23  4985.7  283.86
  4992.4  279.02    4994  276.01  5001.7  276.01  5007.3  280.59 5017.31283.7644
  5021.8  285.82  5057.2  285.03  5121.8  286.02  5327.9  293.24  5385.1  296.61
#Mann= 3 , 0 , 0
    3968     .11       0  4985.7     .06       0 5017.31     .11       0
Bank Sta=4985.7,5017.31
XS Rating Curve= 0 ,0
Exp/Cntr=0.3,0.1

Type RM Length L Ch R = 1 ,6502    ,465,465,465
BEGIN DESCRIPTION:
GETER CREEK 10.0
END DESCRIPTION:
XS GIS Cut Line= 3
      3702617.87     10157761.09      3702010.83     10157158.14
      3701817.85     10156911.07
#Sta/Elev= 30
  4144.4  293.81  4158.5  293.35  4165.6  293.87  4179.8  292.96  4370.7  289.49
  4462.6  289.27  4526.2  284.42  4568.7  283.42  4745.5  282.86  4759.6  282.23
  4773.8  282.97  4858.6  282.76  4936.4  283.29  4964.7  284.07  4985.9  281.64
  4994.7  276.16  5002.5  276.16  5014.1  278.43 5022.98281.2948  5028.6  283.38
  5034.9  284.02  5085.1  283.46  5113.6  284.32  5177.8  286.55  5192.3   287.6
  5206.8  287.64    5271  290.93  5291.8  292.89  5299.9  292.53  5313.5  293.47
#Mann= 3 , 0 , 0
  4144.4     .11       0  4985.9     .06       0 5022.98     .11       0
Bank Sta=4985.9,5022.98
XS Rating Curve= 0 ,0
Exp/Cntr=0.3,0.1

Type RM Length L Ch R = 1 ,6037    ,530,530,530
BEGIN DESCRIPTION:
GETER CREEK 9.0
END DESCRIPTION:
XS GIS Cut Line= 3
      3703067.86     10157661.08      3702236.45     10156774.22
      3701967.85     10156461.06
#Sta/Elev= 30
  3799.2  297.02  3976.3  293.45  4039.8  293.24  4103.3   291.5  4308.4  288.71
  4421.8   283.6  4485.3  282.19  4711.9  281.73  4747.1  282.31  4860.4  281.45
  4881.9  282.28    4917  281.91  4973.7  282.94  4980.6  281.75  4994.7  275.47
  4998.1   274.6    5006   274.6  5008.9  279.63 5019.94281.8373    5023  282.88
  5037.2  282.35  5051.5  283.48    5080  283.24  5164.5  285.93  5221.6  286.96
  5250.1  286.51  5264.4  287.57    5271  288.84  5307.2   291.2  5427.4  296.93
#Mann= 3 , 0 , 0
  3799.2     .11       0  4980.6     .06       0 5019.94     .11       0
Bank Sta=4980.6,5019.94
XS Rating Curve= 0 ,0
Exp/Cntr=0.3,0.1

Type RM Length L Ch R = 1 ,5507    ,500,500,500
BEGIN DESCRIPTION:
GETER CREEK 8.0
END DESCRIPTION:
XS GIS Cut Line= 3
      3703317.82     10157311.04      3702499.29     10156506.68
      3702117.89     10156111.11
#Sta/Elev= 30
  3852.4  298.49  4071.6  289.14  4177.6  285.91  4243.2  285.33  4297.9  285.98
  4390.8  284.33  4502.9  282.92  4517.1  282.14  4594.9  282.17  4630.2  281.06
  4792.8  279.53  4976.7  281.87  4983.8  281.13  4985.1279.8148  4990.8  274.05
  4993.5  273.21  5001.5  273.21  5005.1  275.06    5012  276.24  5019.2  279.99
  5040.3  282.45  5061.7  281.12  5096.9  281.42  5139.4  283.69  5167.7   283.2
  5280.8  285.94  5365.7  289.31  5408.2  291.82    5500  295.04  5549.5  297.84
#Mann= 5 ,-1 , 0
  3852.4     .11       0  4243.2     .15       0  4390.8     .11       0
  4985.1     .06       0  5019.2     .11       0
Bank Sta=4985.1,5019.2
XS Rating Curve= 0 ,0
Exp/Cntr=0.3,0.1

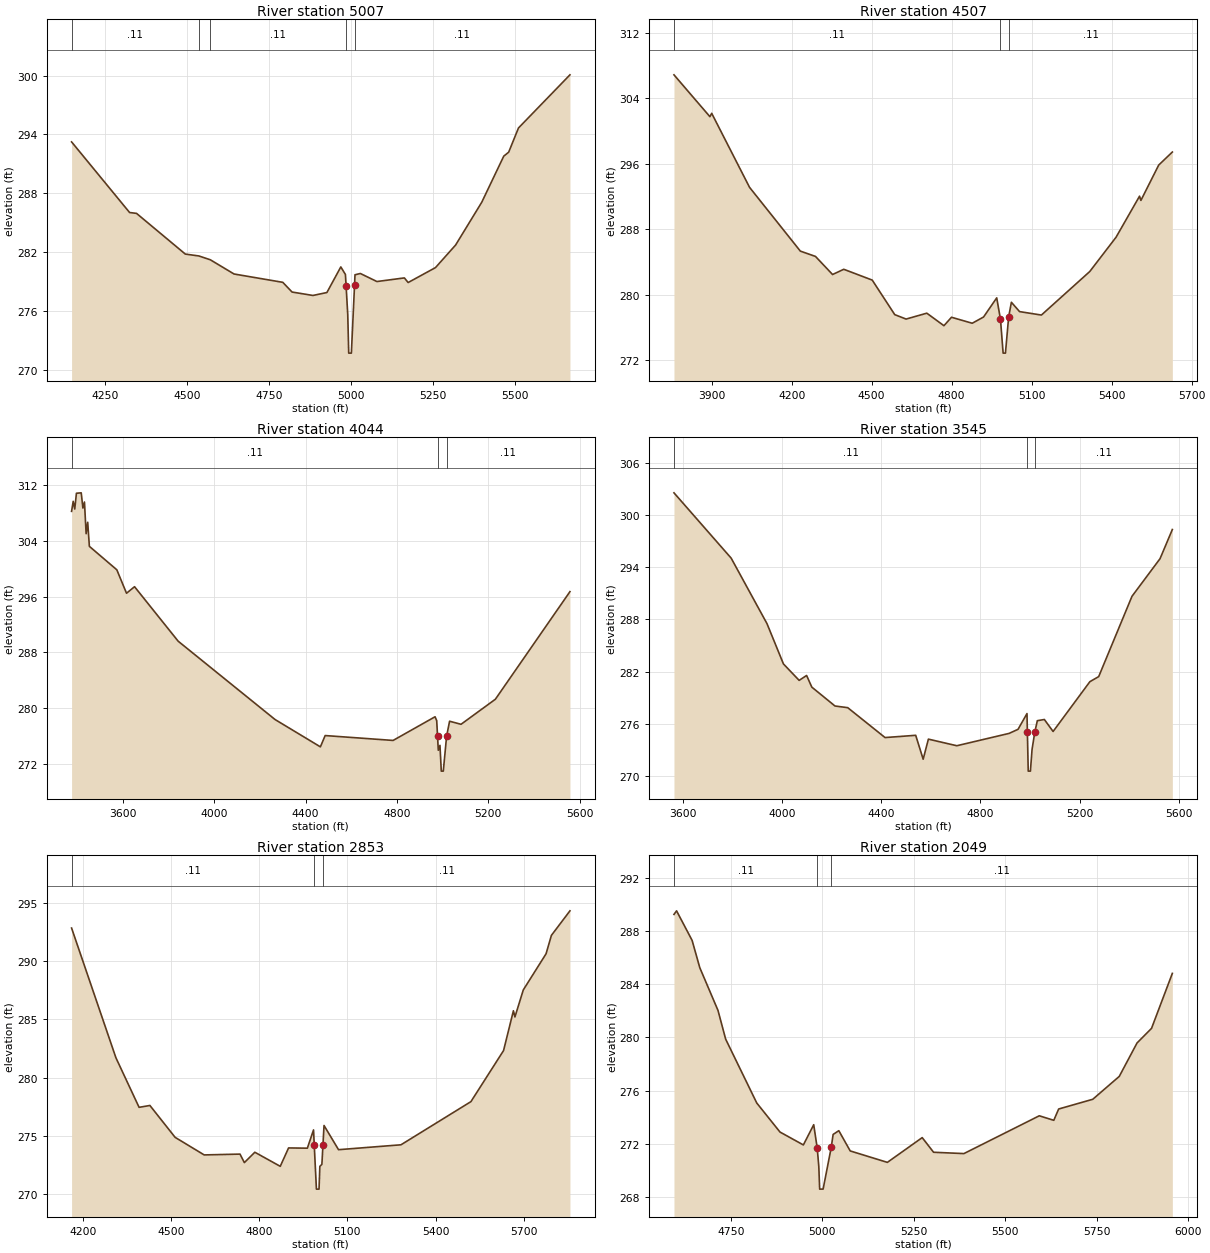
Type RM Length L Ch R = 1 ,5007    ,500,500,500
BEGIN DESCRIPTION:
GETER CREEK 7.0
END DESCRIPTION:
XS GIS Cut Line= 3
      3703417.83     10156811.05       3702813.1     10156211.58
      3702217.85     10155911.07
#Sta/Elev= 30
  4148.5  293.23  4325.2  286.03  4346.4  285.94    4495  281.79  4536.1   281.6
  4571.1  281.21  4643.4  279.76  4791.9  278.91  4820.2  277.92  4883.8  277.57
  4926.3  277.87  4968.7  280.48  4982.8  279.71 4984.82278.5378  4989.9  275.59
  4992.8  271.69  5000.9  271.69 5010.51278.5911  5011.9  279.68  5028.3  279.81
  5078.7  278.99  5162.3  279.36  5173.9  278.89  5257.1  280.41  5318.4  282.71
    5398  287.07  5465.2  291.78  5480.1  292.18    5510  294.65  5666.8  300.07
#Mann= 5 ,-1 , 0
  4148.5     .11       0  4536.1     .15       0  4571.1     .11       0
 4984.82     .06       0 5010.51     .11       0
Bank Sta=4984.82,5010.51
XS Rating Curve= 0 ,0
Exp/Cntr=0.3,0.1

Type RM Length L Ch R = 1 ,4507    ,463,463,463
BEGIN DESCRIPTION:
GETER CREEK 6.0
END DESCRIPTION:
XS GIS Cut Line= 3
      3703767.83     10156711.05      3702931.29     10155793.84
      3702317.89     10155661.08
#Sta/Elev= 30
  3758.6  306.86  3893.3  301.75  3900.1  302.16    4042  293.12  4232.5  285.33
  4289.3  284.68  4353.4  282.47  4395.4  283.11  4502.1  281.79  4586.6  277.57
  4629.1  277.03  4706.8  277.75    4771  276.22  4799.4  277.25  4877.1  276.52
  4919.6  277.28    4969  279.62  4983.1  276.99    4993  272.87  5001.7  272.87
  5013.7  277.28    5024  279.08  5054.7  277.94  5136.5  277.52    5318  282.84
  5416.4  287.02  5504.6  292.04  5509.7  291.52  5576.5  295.84  5627.6  297.43
#Mann= 3 , 0 , 0
  3758.6     .11       0  4983.1     .06       0  5013.7     .11       0
Bank Sta=4983.1,5013.7
XS Rating Curve= 0 ,0
Exp/Cntr=0.3,0.1

Type RM Length L Ch R = 1 ,4044    ,499,499,499
BEGIN DESCRIPTION:
GETER CREEK 5.0
END DESCRIPTION:
XS GIS Cut Line= 3
      3704067.84     10156561.06      3702958.28     10155373.83
      3702402.15     10155333.31
#Sta/Elev= 30
    3375  308.28  3382.1  309.72  3388.9  308.61  3396.2  310.88  3417.2  310.94
  3424.6  308.75  3431.4  309.62  3438.7  305.07  3445.6  306.71  3452.9  303.25
  3573.1  299.88  3615.6  296.51  3650.7  297.45  3841.8  289.62  4266.3  278.36
  4464.6  274.44  4485.6  276.06  4783.1  275.36  4966.8  278.76  4974.1   278.2
 4977.69275.9888    4981  273.95  4988.3  274.65  4994.1  270.95  5002.9  270.95
 5017.43275.9748  5030.5  278.12  5080.6  277.68    5231  281.28  5557.6  296.74
#Mann= 3 , 0 , 0
    3375     .11       0 4977.69     .06       0 5017.43     .11       0
Bank Sta=4977.69,5017.43
XS Rating Curve= 0 ,0
Exp/Cntr=0.3,0.1

Type RM Length L Ch R = 1 ,3545    ,692,692,692
BEGIN DESCRIPTION:
GETER CREEK 4.0
END DESCRIPTION:
XS GIS Cut Line= 3
      3704317.89      10155911.1      3703117.52     10155122.76
      3702717.83     10154711.05
#Sta/Elev= 30
  3563.9  302.56  3794.5  295.05  3939.1  287.51  4005.4  282.88  4068.7  280.99
  4098.8  281.55  4119.9  280.21  4213.3  278.04  4264.6  277.85  4415.2  274.41
  4538.8  274.67  4568.9  271.92    4590  274.23  4704.5  273.47  4915.5  274.89
  4951.6  275.36  4987.6  277.17 4989.17 275.035  4992.6  270.55  5001.4  270.55
    5008  273.04 5018.92275.0062  5029.3  276.35  5057.6  276.49  5092.9  275.11
  5241.3  280.84  5276.8  281.42  5411.1  290.66  5524.3  294.99  5573.8  298.34
#Mann= 3 , 0 , 0
  3563.9     .11       0 4989.17     .06       0 5018.92     .11       0
Bank Sta=4989.17,5018.92
XS Rating Curve= 0 ,0
Exp/Cntr=0.3,0.1

Type RM Length L Ch R = 1 ,2853    ,804,804,804
BEGIN DESCRIPTION:
Mapping XS 48349ef2
END DESCRIPTION:
XS GIS Cut Line= 4
      3704165.27     10155553.63      3703606.27     10155157.82
       3703203.5     10154730.74      3702797.29     10154612.69
#Sta/Elev= 30
  4162.1  292.86  4312.9  281.71  4391.7  277.45  4428.5  277.61  4514.3  274.87
  4613.1  273.36  4734.9  273.43  4749.7   272.7  4785.4  273.59  4871.8  272.38
  4900.1  273.96    4964  273.94    4985  275.51 4987.47274.1835  4994.8  270.42
  5003.7  270.42  5006.5  272.38  5013.4  272.55 5017.11274.2474  5020.7  275.89
    5070  273.81  5282.4  274.23  5520.3  277.94  5631.3  282.33  5664.8  285.75
    5670  285.22  5698.4  287.54  5775.9  290.65    5794  292.23  5857.1  294.34
#Mann= 3 , 0 , 0
  4162.1     .11       0 4987.47     .06       0 5017.11     .11       0
Bank Sta=4987.47,5017.11
XS Rating Curve= 0 ,0
Exp/Cntr=0.3,0.1

Type RM Length L Ch R = 1 ,2049    ,494,494,494
BEGIN DESCRIPTION:
GETER CREEK 3.0
END DESCRIPTION:
XS GIS Cut Line= 3
      3704267.85     10155011.07      3703991.17     10154713.81
      3703067.84     10154461.07
#Sta/Elev= 30
  4593.9  289.24    4601  289.51  4643.5  287.29  4664.5  285.24  4714.3  282.03
  4735.3  279.87  4820.4  275.07  4883.9  272.89  4947.9  271.92  4976.2  273.44
 4985.81271.6767  4990.1  270.31  4992.5   268.6  5001.9   268.6  5024.1  271.73
  5029.3  272.71  5044.9  272.99    5076  271.47  5177.7  270.61    5273  272.47
  5304.1  271.37  5387.1  271.27  5593.3  274.11    5633  273.77  5646.3  274.62
  5739.6  275.35  5812.1  277.07  5860.7  279.58  5900.4  280.68  5957.3  284.81
#Mann= 3 , 0 , 0
  4593.9     .11       0 4985.81     .06       0  5024.1     .11       0
Bank Sta=4985.81,5024.1
XS Rating Curve= 0 ,0
Exp/Cntr=0.3,0.1

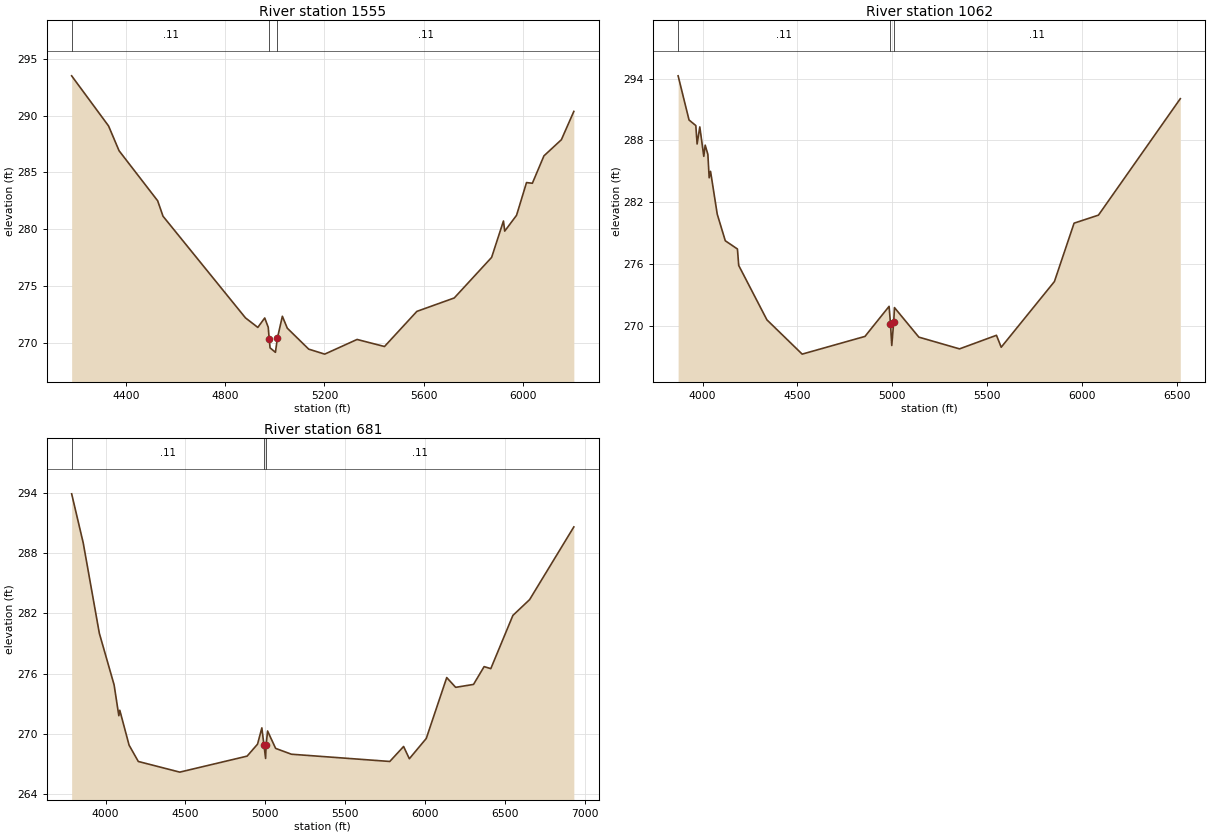
Type RM Length L Ch R = 1 ,1555    ,493,493,493
BEGIN DESCRIPTION:
GETER CREEK 2.0
END DESCRIPTION:
XS GIS Cut Line= 3
      3704717.84     10154811.06      3704118.28     10154253.85
      3702917.86     10154361.07
#Sta/Elev= 30
  4181.5  293.49  4330.3  289.08  4372.6   286.9  4528.1   282.5  4549.7  281.14
  4881.9   272.2  4931.7  271.36  4959.6  272.19  4973.7  271.37  4977.7  270.32
  4981.1  269.56  5002.7  269.17  5010.5   270.4  5030.6  272.34  5050.6  271.29
  5136.7  269.45  5201.2  269.01  5331.7   270.3  5442.2  269.68  5572.7  272.77
  5723.3  273.95  5873.9  277.52  5921.6  280.72  5926.7  279.83  5974.3  281.22
  6014.5   284.1  6038.1  284.04  6084.7  286.45    6155  287.87  6205.2  290.36
#Mann= 3 ,-1 , 0
  4181.5     .11       0  4977.7     .06       0  5010.5     .11       0
Bank Sta=4977.7,5010.5
XS Rating Curve= 0 ,0
Exp/Cntr=0.3,0.1

Type RM Length L Ch R = 1 ,1062    ,381,381,381
BEGIN DESCRIPTION:
Mapping XS 1353f0f2
END DESCRIPTION:
XS GIS Cut Line= 3
      3705095.86      10154574.6      3704231.24     10153762.07
      3702835.41     10154189.15
#Sta/Elev= 30
  3871.3  294.26  3928.9  289.97  3964.6  289.43  3971.4  287.64  3985.6   289.3
  4006.6  286.44  4013.9  287.53  4028.1  286.63  4034.9  284.36  4042.2  284.98
  4077.4  280.83  4119.9  278.24  4183.9  277.44  4190.7  275.84  4339.2  270.56
    4525  267.23  4855.9  268.95    4983  271.87  4990.3   270.2  4997.1  268.07
 5007.25  270.32  5011.3  271.75  5139.8  268.88  5354.2  267.74  5548.8  269.06
  5573.8   267.9  5854.2  274.28  5957.8  279.95  6086.2  280.73  6517.5  292.04
#Mann= 3 , 0 , 0
  3871.3     .11       0  4990.3     .06       0 5007.25     .11       0
Bank Sta=4990.3,5007.25
XS Rating Curve= 0 ,0
Exp/Cntr=0.3,0.1

Type RM Length L Ch R = 1 ,681     ,0,0,0
BEGIN DESCRIPTION:
GETER CREEK 1.0
END DESCRIPTION:
XS GIS Cut Line= 3
       3705224.3     10154515.54      3704451.73     10153414.85
      3702759.01     10154029.43
#Sta/Elev= 30
  3787.5  293.87  3859.9     289    3961     280  4053.4  274.88    4083  271.81
  4089.1  272.35  4147.3  268.88    4205  267.26  4464.7   266.2  4886.5  267.79
  4951.9  268.98  4978.9   270.6 4992.19  268.87  5002.4  267.56 5005.54  268.87
  5014.7  270.29  5065.2  268.56  5164.1  267.98  5780.3  267.26  5866.8  268.75
  5902.7  267.53  6008.8  269.55  6136.9   275.6  6192.8  274.63  6304.6  274.92
  6371.2  276.69    6413  276.49  6551.3  281.78    6656  283.35  6933.1  290.58
#Mann= 3 , 0 , 0
  3787.5     .11       0 4992.19     .06       0 5005.54     .11       0
Bank Sta=4992.19,5005.54
XS Rating Curve= 0 ,0
Exp/Cntr=0.3,0.1

Chan Stop Cuts=-1
Use User Specified Reach Order=0
Composite Channel Slope=5