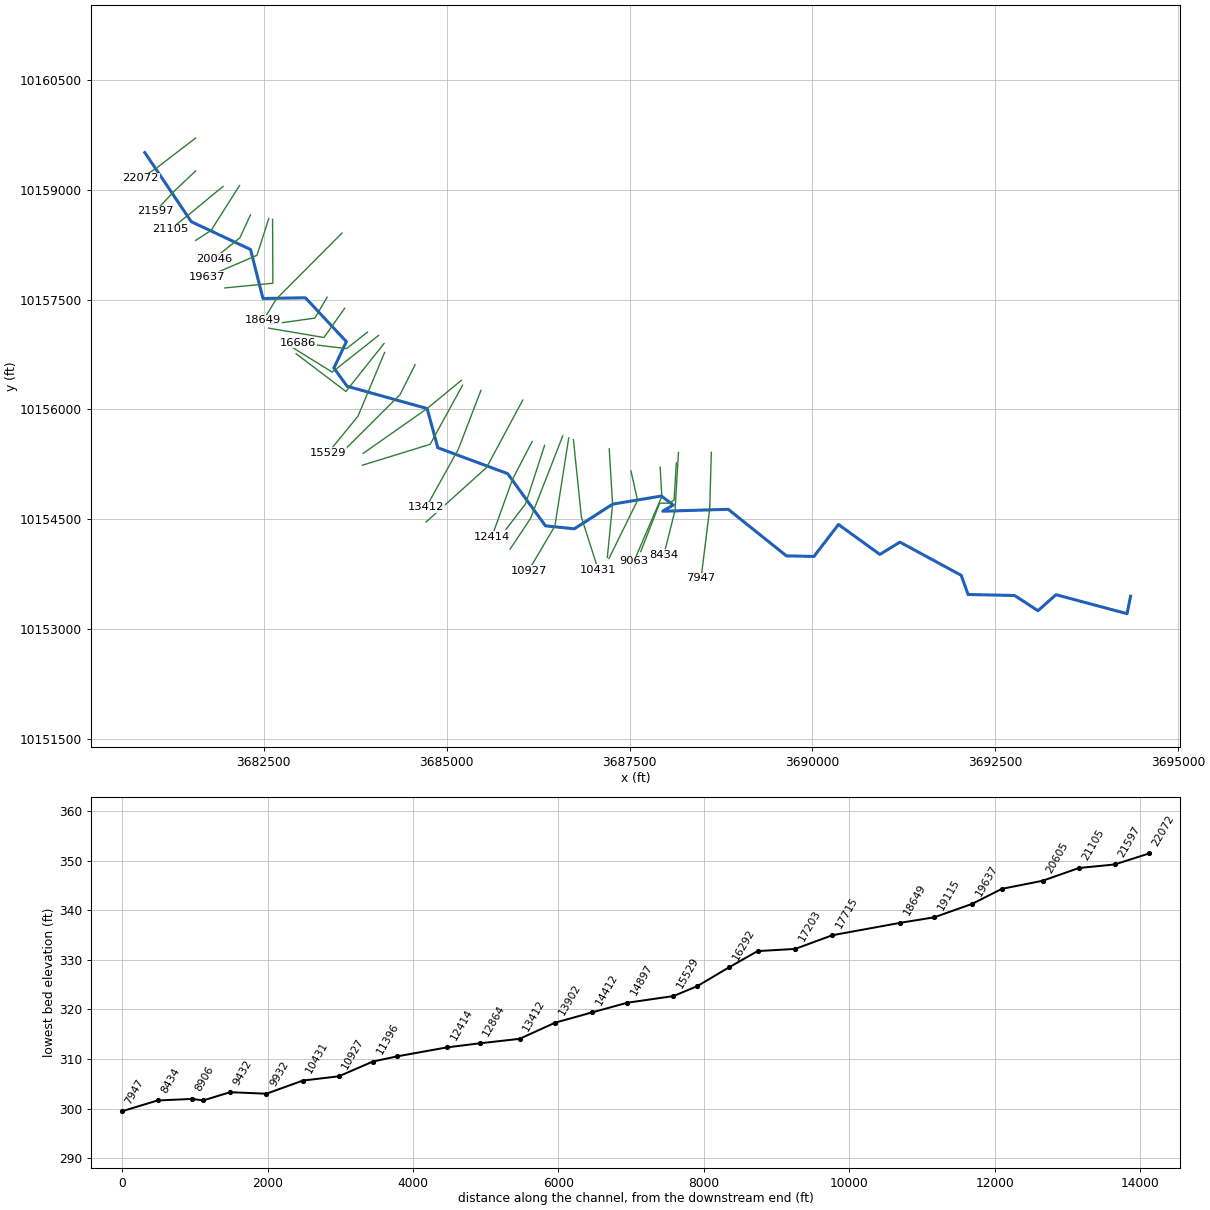
--- HAYNIE CREEK.prj (project) ---

Proj Title=HAYNIE CREEK Base Level Engineering
Current Plan=p01
Default Exp/Contr=0.3,0.1
English Units
Geom File=g01
Flow File=f01
Flow File=f02
Plan File=p01
Y Axis Title=Elevation
X Axis Title(PF)=Main Channel Distance
X Axis Title(XS)=Station
BEGIN DESCRIPTION:
HAYNIE CREEK
END DESCRIPTION:
DSS Export Rating Curves= 0
DSS Export Rating Curve Sorted= 0
DSS Export Volume Flow Curves= 0
DXF OffsetX= 0
DXF OffsetY= 0
DXF ScaleX= 1
DXF ScaleY= 10

--- HAYNIE CREEK.p01 (plan) ---

Plan Title=Multiple Run
Short Identifier=Multiple
Geom File=g01
Flow File=f01
Subcritical Flow
K Sum by GR= 0
Std Step Tol= 0.01
Critical Tol= 0.01
Num of Std Step Trials= 20
Max Error Tol= 0.3
Flow Tol Ratio= 0.001
Split Flow NTrial= 30
Split Flow Tol= 0.02
Split Flow Ratio= 0.02
Log Output Level= 0
Friction Slope Method= 1
Unsteady Friction Slope Method= 2
Unsteady Bridges Friction Slope Method= 1
Parabolic Critical Depth
Global Vel Dist=  1 , 1 , 1
Global Log Level= 0
CheckData=True
Encroach Param= -1, 0, 0, 0
BEGIN DESCRIPTION:
Multiple Run
END DESCRIPTION:

--- HAYNIE CREEK.f01 (steady flow) ---

Flow Title=Multiple
Program Version=4.10
Number of Profiles= 7
Profile Names=10-year,25-year,50-year,1pct_min,100-year,1pct_plu,500-year
River Rch & RM=HAYNIE CREEK,Reach-1         ,22072
     614     833    1127     502    1515    4575    2829
River Rch & RM=HAYNIE CREEK,Reach-1         ,15529
    1203    1687    2332    1058    3194    9646    6202
River Rch & RM=HAYNIE CREEK,Reach-1         ,10431
    1547    2202    3076    1408    4252   12841    8423
River Rch & RM=HAYNIE CREEK,Reach-1         ,5389
    1585    2237    3106    1412    4264   12877    8328
Boundary for River Rch & Prof#=HAYNIE CREEK,Reach-1         , 1
Up Type= 0
Dn Type= 3
Dn Slope=0.005
Boundary for River Rch & Prof#=HAYNIE CREEK,Reach-1         , 2
Up Type= 0
Dn Type= 3
Dn Slope=0.005
Boundary for River Rch & Prof#=HAYNIE CREEK,Reach-1         , 3
Up Type= 0
Dn Type= 3
Dn Slope=0.005
Boundary for River Rch & Prof#=HAYNIE CREEK,Reach-1         , 4
Up Type= 0
Dn Type= 3
Dn Slope=0.005
Boundary for River Rch & Prof#=HAYNIE CREEK,Reach-1         , 5
Up Type= 0
Dn Type= 3
Dn Slope=0.005
Boundary for River Rch & Prof#=HAYNIE CREEK,Reach-1         , 6
Up Type= 0
Dn Type= 3
Dn Slope=0.005
Boundary for River Rch & Prof#=HAYNIE CREEK,Reach-1         , 7
Up Type= 0
Dn Type= 3
Dn Slope=0.005
DSS Import GetInterval= 0
DSS Import GetPeak= 0
DSS Import FillOption= 0

--- HAYNIE CREEK.f02 (steady flow) ---

Flow Title=Orig_BLE_Flows
Program Version=4.10
Number of Profiles= 7
Profile Names=10-year,25-year,50-year,1pct_min,100-year,1pct_plu,500-year
River Rch & RM=HAYNIE CREEK,Reach-1         ,22072
     614     817     980     386    1165    3519    1645
River Rch & RM=HAYNIE CREEK,Reach-1         ,15529
    1203    1654    2028     814    2457    7419    3606
River Rch & RM=HAYNIE CREEK,Reach-1         ,10431
    1547    2159    2675    1083    3271    9879    4897
River Rch & RM=HAYNIE CREEK,Reach-1         ,5389
    1585    2193    2701    1086    3280    9905    4842
Boundary for River Rch & Prof#=HAYNIE CREEK,Reach-1         , 1
Up Type= 0
Dn Type= 3
Dn Slope=0.005
Boundary for River Rch & Prof#=HAYNIE CREEK,Reach-1         , 2
Up Type= 0
Dn Type= 3
Dn Slope=0.005
Boundary for River Rch & Prof#=HAYNIE CREEK,Reach-1         , 3
Up Type= 0
Dn Type= 3
Dn Slope=0.005
Boundary for River Rch & Prof#=HAYNIE CREEK,Reach-1         , 4
Up Type= 0
Dn Type= 3
Dn Slope=0.005
Boundary for River Rch & Prof#=HAYNIE CREEK,Reach-1         , 5
Up Type= 0
Dn Type= 3
Dn Slope=0.005
Boundary for River Rch & Prof#=HAYNIE CREEK,Reach-1         , 6
Up Type= 0
Dn Type= 3
Dn Slope=0.005
Boundary for River Rch & Prof#=HAYNIE CREEK,Reach-1         , 7
Up Type= 0
Dn Type= 3
Dn Slope=0.005
DSS Import GetInterval= 0
DSS Import GetPeak= 0
DSS Import FillOption= 0

--- HAYNIE CREEK.g01 (geometry) ---

Geom Title=Existing Conditions
Program Version=4.10

River Reach=HAYNIE CREEK    ,Reach-1
Reach XY= 30
      3680873.23     10159511.84      3681508.23     10158566.84
      3682318.23     10158186.84      3682488.23     10157516.84
      3683068.23     10157526.84      3683628.23     10156926.84
      3683458.23     10156566.84      3683638.23     10156316.84
      3684732.17     10156012.27      3684878.47     10155476.11
       3685832.9      10155121.9      3686349.12     10154408.75
        3686744.     10154367.42      3687269.03     10154705.09
      3687934.86     10154815.52      3688096.89     10154693.42
      3687952.33      10154607.8      3688848.93     10154634.08
      3689643.38     10153997.71      3690019.87     10153989.85
      3690355.47     10154426.65      3690921.48      10154017.6
      3691195.79     10154185.53      3692032.98     10153731.71
      3692127.36     10153469.47       3692763.9     10153455.84
      3693082.67     10153247.55      3693328.63     10153466.77
      3694301.13     10153206.99      3694348.23     10153446.84

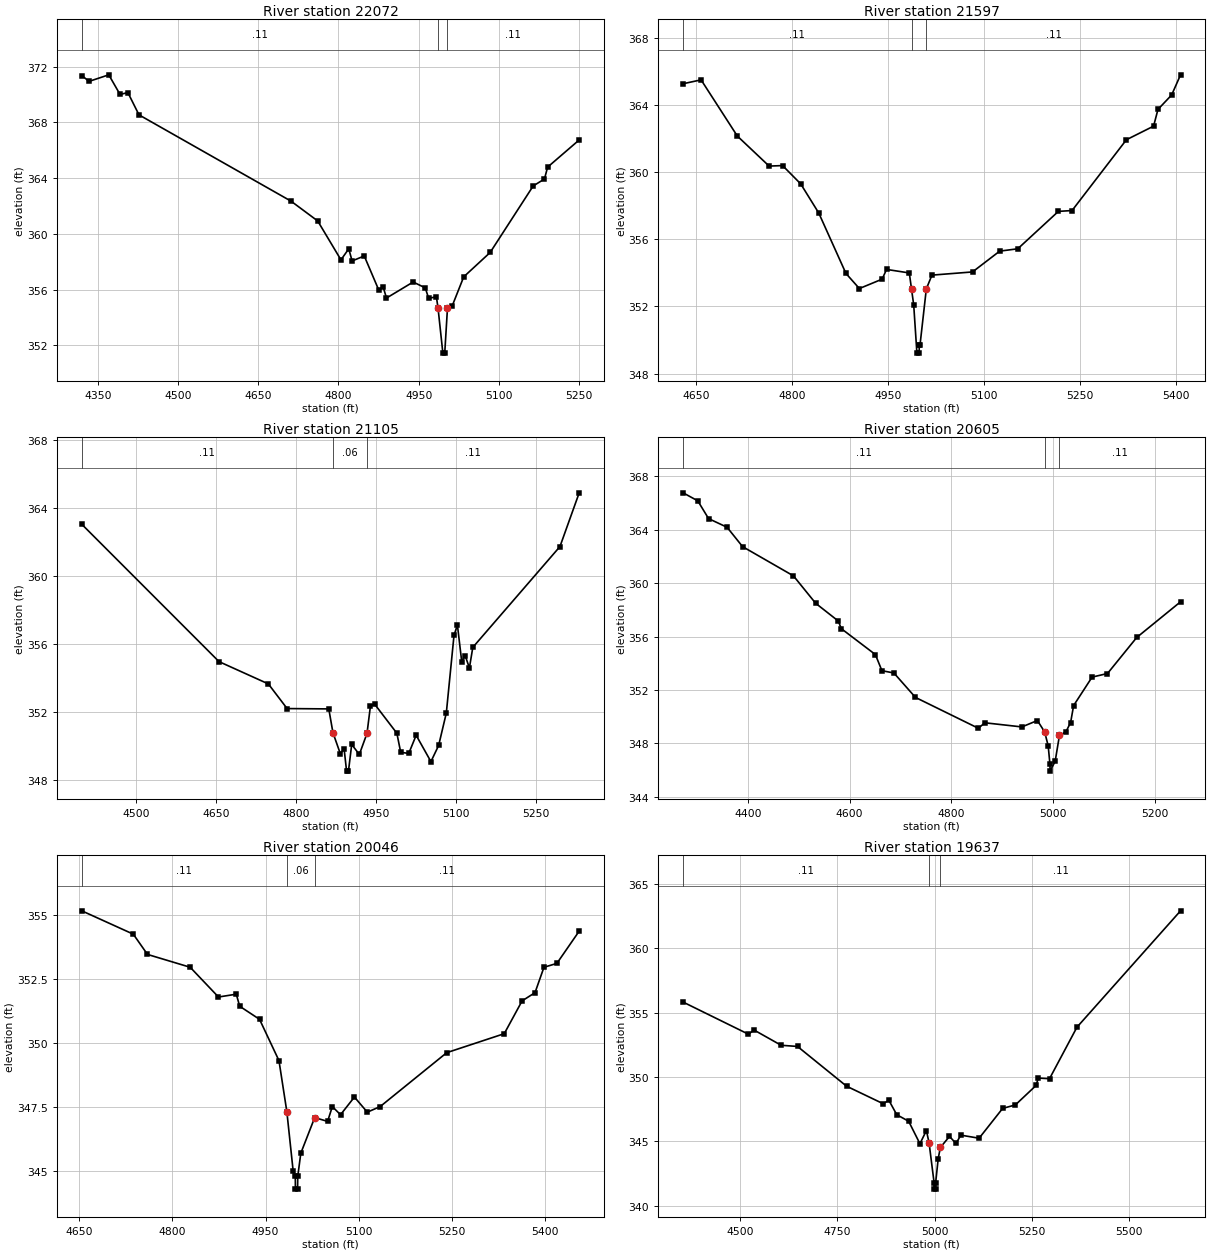
Type RM Length L Ch R = 1 ,22072   ,475,475,475
BEGIN DESCRIPTION:
HAYNIE CREEK 40.0
END DESCRIPTION:
XS GIS Cut Line= 3
      3681567.87     10159711.09      3681028.23     10159296.84
      3680817.84     10159161.06
#Sta/Elev= 30
  4319.7  371.36  4333.3  370.94  4370.2  371.41  4391.3     370  4405.9  370.14
  4426.7  368.54  4711.2  362.35  4761.1  360.93  4804.6  358.14  4819.2  358.93
  4825.5  358.06  4848.2  358.42  4875.3  355.98  4883.5  356.21  4889.8   355.4
  4939.7  356.55  4962.4  356.13  4968.7  355.38  4983.2  355.49  4986.3354.6683
  4995.3  351.45  4998.8  351.45  5003.9  354.66  5012.4   354.8  5034.3  356.92
  5083.8  358.67  5164.3  363.44  5185.4  363.94  5191.3  364.79  5250.4  366.74
#Mann= 3 , 0 , 0
  4319.7     .11       0  4986.3     .06       0  5003.9     .11       0
Bank Sta=4986.3,5003.9
XS Rating Curve= 0 ,0
Exp/Cntr=0.3,0.1

Type RM Length L Ch R = 1 ,21597   ,492,492,492
BEGIN DESCRIPTION:
HAYNIE CREEK 39.0
END DESCRIPTION:
XS GIS Cut Line= 3
      3681567.87     10159261.09      3681298.23     10159006.84
      3681017.88      10158711.1
#Sta/Elev= 30
  4629.4  365.28  4657.5  365.51  4714.2  362.16  4763.9  360.37    4785   360.4
  4813.3  359.31  4841.6  357.57  4884.1  353.97  4905.1  353.07  4940.7  353.63
  4947.6  354.21  4983.2     354 4986.65353.0451  4990.1  352.09  4995.1  349.22
  4998.6  349.22  4998.8  349.72    5000  349.72 5009.84353.0524  5018.6  353.87
  5082.1  354.06  5124.6   355.3  5152.9  355.44  5216.4  357.67  5237.8  357.72
  5322.8  361.94  5365.3  362.75  5372.2  363.75  5393.6  364.61  5407.5  365.81
#Mann= 3 , 0 , 0
  4629.4     .11       0 4986.65     .06       0 5009.84     .11       0
Bank Sta=4986.65,5009.84
XS Rating Curve= 0 ,0
Exp/Cntr=0.3,0.1

Type RM Length L Ch R = 1 ,21105   ,500,500,500
BEGIN DESCRIPTION:
HAYNIE CREEK 38.0
END DESCRIPTION:
XS GIS Cut Line= 3
      3681942.16     10159049.38      3681478.23     10158666.84
      3681217.83     10158461.05
#Sta/Elev= 30
  4398.7  363.03  4656.2  354.95  4748.7  353.64  4783.9  352.19  4862.1  352.17
  4869.9  350.77  4883.8  349.53  4890.8  349.83  4895.5  348.51    4899  348.51
  4905.1  350.08  4919.4  349.49  4933.8  350.73  4940.3  352.36  4948.1  352.45
  4989.8  350.74    4997  349.62  5012.1  349.55    5026  350.62  5053.7  349.07
  5068.2  350.02  5082.6  351.93    5097  356.49  5103.4  357.11  5111.5  354.95
  5117.9  355.31  5125.9  354.58  5132.3  355.79  5295.8  361.72  5331.9  364.88
#Mann= 3 , 0 , 0
  4398.7     .11       0  4869.9     .06       0  4933.8     .11       0
#Block Obstruct= 2 , 0
                         5027.33          350.63
Bank Sta=4869.9,4933.8
XS Rating Curve= 0 ,0
Exp/Cntr=0.3,0.1

Type RM Length L Ch R = 1 ,20605   ,559,559,559
BEGIN DESCRIPTION:
HAYNIE CREEK 37.0
END DESCRIPTION:
XS GIS Cut Line= 3
      3682167.86     10159061.09      3681778.23     10158446.84
      3681567.84     10158311.06
#Sta/Elev= 30
  4272.6  366.77  4301.4  366.17  4322.6  364.84    4359  364.19  4389.5  362.74
  4489.5  360.55  4533.1   358.5  4577.6  357.17  4583.5   356.6  4650.5  354.66
  4663.4  353.45  4686.9  353.28  4729.3  351.45  4852.9  349.14  4865.7  349.55
  4938.5  349.24    4969  349.72  4983.2  348.87  4990.2  347.83  4993.7  346.43
  4993.9  345.93  5003.9  346.66  5012.4  348.61    5025  348.87  5034.3  349.57
  5040.2  350.84  5076.5  352.97  5106.8  353.24  5164.3  355.94  5250.4  358.61
#Mann= 3 , 0 , 0
  4272.6     .11       0  4983.2     .06       0  5012.4     .11       0
Bank Sta=4983.2,5012.4
XS Rating Curve= 0 ,0
Exp/Cntr=0.3,0.1

Type RM Length L Ch R = 1 ,20046   ,409,409,409
BEGIN DESCRIPTION:
HAYNIE CREEK 36.0
END DESCRIPTION:
XS GIS Cut Line= 3
      3682317.84     10158661.05      3682172.22     10158346.27
      3681817.86     10158061.08
#Sta/Elev= 30
  4653.8  355.16  4736.8  354.25  4759.7  353.46  4828.5  352.96  4874.1   351.8
  4902.8  351.91  4908.3  351.44  4940.3  350.93  4971.6  349.32  4984.3  347.33
  4994.5  345.01  4997.9  344.81  4998.1  344.31  5001.6  344.31  5001.9  344.81
  5006.8  345.71  5029.2   347.1    5050  346.95  5057.6  347.53  5070.8  347.21
  5093.2   347.9    5114  347.31  5134.8  347.53    5242  349.63  5334.7  350.37
  5363.5  351.65  5384.3  351.97  5398.7  352.96  5419.5  353.11  5455.5  354.37
#Mann= 3 , 0 , 0
  4653.8     .11       0  4984.3     .06       0  5029.2     .11       0
Bank Sta=4984.3,5029.2
XS Rating Curve= 0 ,0
Exp/Cntr=0.3,0.1

Type RM Length L Ch R = 1 ,19637   ,522,522,522
BEGIN DESCRIPTION:
HAYNIE CREEK 35.0
END DESCRIPTION:
XS GIS Cut Line= 3
      3682567.86     10158611.09      3682406.59     10158107.56
      3681717.82     10157811.06
#Sta/Elev= 30
  4353.3  355.83  4521.3  353.33  4535.4  353.66  4605.3  352.47  4647.3  352.38
  4773.3  349.29  4867.8  347.92    4882   348.2  4902.4  347.07    4933  346.56
    4962  344.81  4978.6  345.84  4985.5  344.88  4998.4  341.78  4998.7  341.28
  5002.2  341.28  5002.4  341.78    5009  343.66  5014.5  344.52    5038  345.38
  5054.8  344.83    5067  345.48  5114.1  345.24  5174.6  347.56  5207.3  347.83
  5260.7  349.35  5266.1  349.92  5295.1  349.87  5365.7  353.88  5631.9  362.93
#Mann= 3 , 0 , 0
  4353.3     .11       0  4985.5     .06       0  5014.5     .11       0
Bank Sta=4985.5,5014.5
XS Rating Curve= 0 ,0
Exp/Cntr=0.3,0.1

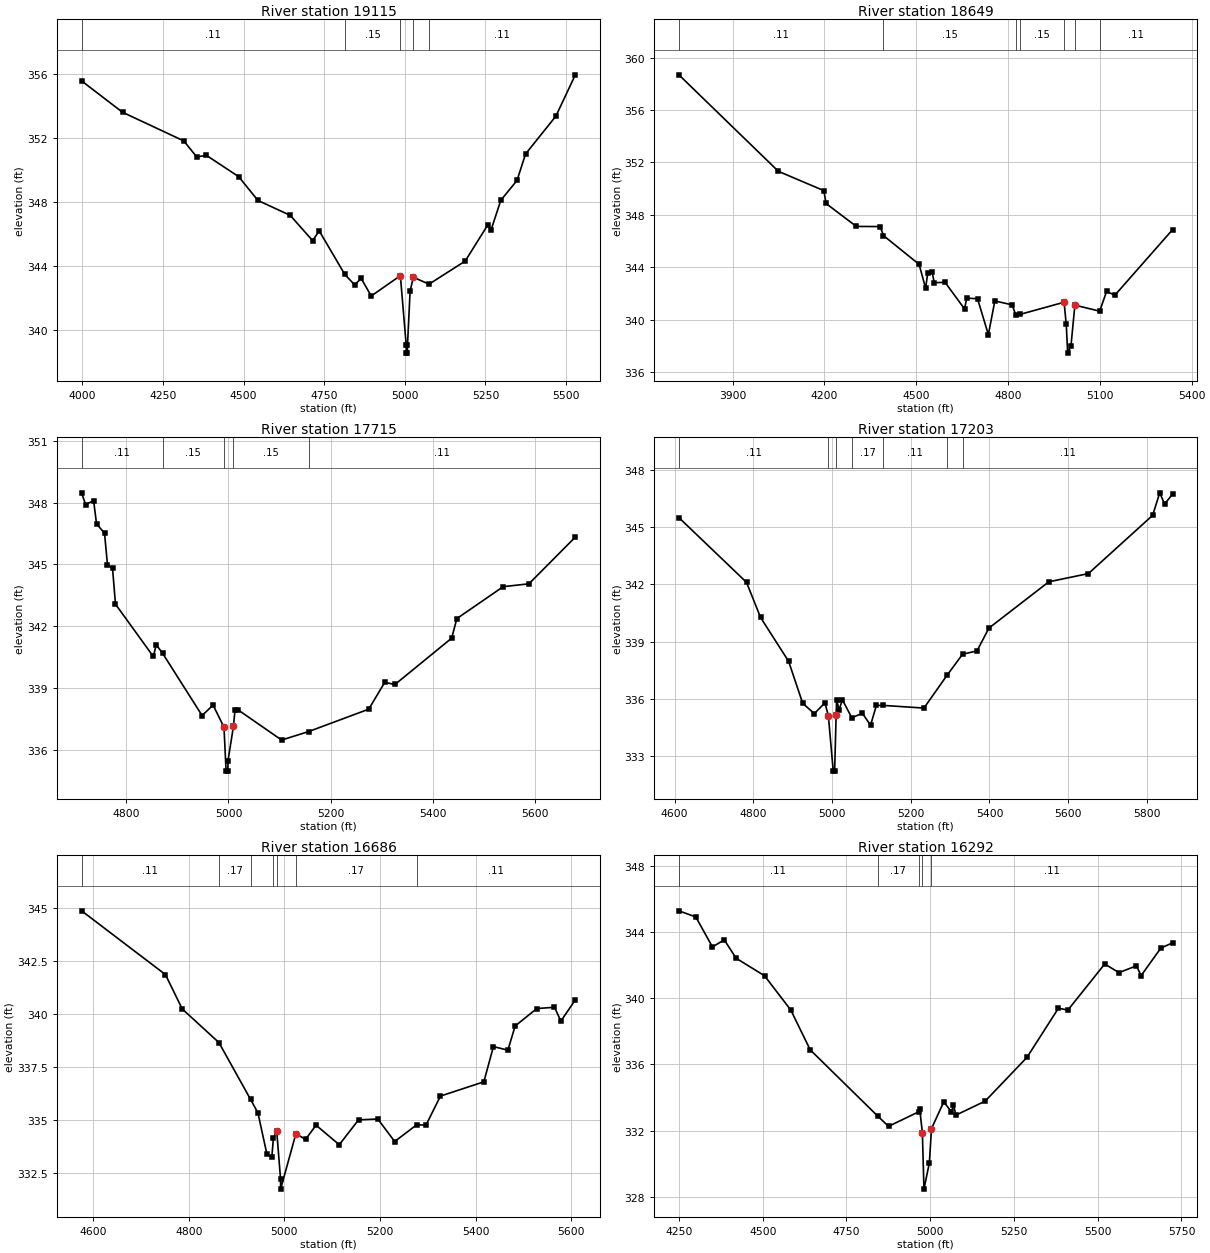
Type RM Length L Ch R = 1 ,19115   ,466,466,466
BEGIN DESCRIPTION:
HAYNIE CREEK 34.0
END DESCRIPTION:
XS GIS Cut Line= 3
      3682619.26     10158598.04      3682623.61     10157725.61
      3681967.81     10157661.07
#Sta/Elev= 30
  3997.6  355.58  4124.6  353.62  4314.6  351.83  4354.6  350.83  4384.6  350.93
  4484.6   349.6  4544.6  348.11  4644.6  347.18  4714.1   345.6  4734.6  346.21
  4813.6   343.5  4844.6  342.83  4864.6  343.24  4895.9  342.14  4986.3  343.41
  5004.4  339.07  5004.7  338.57  5008.2  338.57  5008.4  339.07  5016.5  342.44
  5026.5  343.31  5075.2  342.88  5187.3  344.32  5257.7  346.59  5267.7  346.27
  5297.8  348.12  5348.1  349.36  5374.5  351.01  5468.7  353.38    5529  355.96
#Mann= 5 ,-1 , 0
  3997.6     .11       0  4813.6     .15       0  4986.3     .09       0
  5026.5     .15       0  5075.2     .11       0
Bank Sta=4986.3,5026.5
XS Rating Curve= 0 ,0
Exp/Cntr=0.3,0.1

Type RM Length L Ch R = 1 ,18649   ,934,934,934
BEGIN DESCRIPTION:
HAYNIE CREEK 33.0
END DESCRIPTION:
XS GIS Cut Line= 3
      3683567.84     10158411.06      3682668.23     10157506.84
       3682493.4     10157217.81
#Sta/Elev= 30
  3724.5  358.68  4049.7  351.32  4198.2  349.85  4205.3  348.87  4304.3  347.12
  4382.1  347.11    4393  346.42  4509.4  344.23  4530.6  342.41  4537.7  343.57
  4551.8  343.67  4558.9  342.83  4594.2  342.86  4657.9  340.83  4664.9  341.65
  4700.3  341.61  4735.7  338.87  4756.9  341.44  4813.4  341.14  4825.8  340.34
  4838.5  340.41  4983.1  341.34  4990.2  339.65    4995  337.46  5005.6     338
  5018.4  341.12  5099.4  340.66    5122  342.16  5149.2  341.88  5337.8  346.88
#Mann= 7 ,-1 , 0
  3724.5     .11       0    4393     .15       0  4825.8     .11       0
  4838.5     .15       0  4983.1     .09       0  5018.4     .15       0
  5099.4     .11       0
Bank Sta=4983.1,5018.4
XS Rating Curve= 0 ,0
Exp/Cntr=0.3,0.1

Type RM Length L Ch R = 1 ,17715   ,512,512,512
BEGIN DESCRIPTION:
HAYNIE CREEK 32.0
END DESCRIPTION:
XS GIS Cut Line= 3
      3683365.78     10157534.62      3683196.52     10157248.18
      3682567.84     10157161.07
#Sta/Elev= 30
  4712.2  348.48    4720  347.91  4735.7   348.1  4741.5  346.97  4757.1  346.52
  4762.9  344.98  4772.8  344.81  4778.6  343.07  4852.7  340.53  4858.5   341.1
    4871  340.68  4948.3  337.66  4969.8  338.17  4991.2  337.09  4995.3  334.96
  4998.8  334.96    4999  335.46 5009.77337.1437  5012.7  337.93  5018.5  337.94
  5104.1  336.47  5156.8  336.88  5274.8  337.97  5306.1  339.27  5326.2  339.17
  5437.3  341.42  5447.4  342.37  5538.2  343.92  5588.7  344.06  5679.6  346.33
#Mann= 5 ,-1 , 0
  4712.2     .11       0    4871     .15       0  4991.2     .09       0
 5009.77     .15       0  5156.8     .11       0
Bank Sta=4991.2,5009.77
XS Rating Curve= 0 ,0
Exp/Cntr=0.3,0.1

Type RM Length L Ch R = 1 ,17203   ,517,517,517
BEGIN DESCRIPTION:
HAYNIE CREEK 31.0
END DESCRIPTION:
XS GIS Cut Line= 3
      3683604.51     10157382.73      3683322.39     10156983.42
      3682567.83     10157111.08
#Sta/Elev= 30
    4611  345.51  4782.8  342.11  4818.4  340.27  4889.8  337.96  4925.5  335.76
  4955.1  335.22  4982.1  335.79  4990.8  335.08  5003.1   332.2  5006.6   332.2
 5010.44335.1216  5011.7  335.96  5017.8  335.42  5026.5  335.94  5050.3     335
    5077  335.24  5097.9  334.61  5112.7  335.65  5130.2  335.65  5233.5  335.51
  5292.1  337.23  5331.7  338.34  5368.2  338.51  5398.6  339.71  5550.8  342.14
  5651.2  342.57  5814.5  345.63  5832.4  346.81  5844.9  346.22  5865.2  346.75
#Mann= 7 ,-1 , 0
    4611     .11       0  4990.8     .09       0 5010.44     .15       0
  5050.3     .17       0  5130.2     .11       0  5292.1     .15       0
  5331.7     .11       0
Bank Sta=4990.8,5010.44
XS Rating Curve= 0 ,0
Exp/Cntr=0.3,0.1

Type RM Length L Ch R = 1 ,16686   ,394,394,394
BEGIN DESCRIPTION:
HAYNIE CREEK 30.0
END DESCRIPTION:
XS GIS Cut Line= 3
        3683917.      10157057.2      3683630.55     10156831.51
      3682967.89     10156911.07
#Sta/Elev= 30
  4576.1  344.86  4751.3  341.86  4786.5  340.24  4863.1  338.66  4929.4  335.98
  4944.7  335.35  4963.6  333.39  4973.7  333.26    4977  334.15  4983.9  334.51
  4991.9  332.26  4992.1  331.76  5024.1  334.37  5044.2   334.1  5066.2  334.77
  5114.7  333.85    5155  335.02  5195.3  335.06  5230.6     334  5276.6  334.79
    5296  334.77  5326.2  336.14  5416.9  336.81    5437  338.47  5467.2   338.3
  5482.4  339.44  5527.7  340.26  5564.6  340.32    5578  339.67  5608.2  340.67
#Mann= 7 ,-1 , 0
  4576.1     .11       0  4863.1     .17       0  4929.4     .11       0
    4977     .17       0  4983.9     .09       0  5024.1     .17       0
  5276.6     .11       0
Bank Sta=4983.9,5024.1
XS Rating Curve= 0 ,0
Exp/Cntr=0.3,0.1

Type RM Length L Ch R = 1 ,16292   ,436,436,436
BEGIN DESCRIPTION:
HAYNIE CREEK 29.0
END DESCRIPTION:
XS GIS Cut Line= 3
      3684067.84     10157011.06      3683435.24     10156510.33
      3682867.88     10156861.05
#Sta/Elev= 30
  4249.8  345.27  4300.3   344.9    4350  343.09  4385.2  343.52  4420.5  342.41
  4505.4  341.35  4583.9  339.28  4641.7  336.88  4843.8  332.87  4875.6  332.26
  4965.9  333.14  4968.6  333.31  4976.6  331.88  4981.3  328.47  4997.4  330.05
  5003.8  332.12  5040.5  333.74  5063.5  333.13  5069.3  333.53    5077  332.94
  5163.9  333.78  5288.7  336.42  5382.7  339.39    5411  339.28  5520.9  342.06
  5563.5  341.54  5615.5  341.95  5629.6  341.36  5688.4  343.02  5723.6  343.34
#Mann= 5 ,-1 , 0
  4249.8     .11       0  4843.8     .17       0  4965.9     .11       0
  4976.6     .06       0  5003.8     .11       0
Bank Sta=4976.6,5003.8
XS Rating Curve= 0 ,0
Exp/Cntr=0.3,0.1

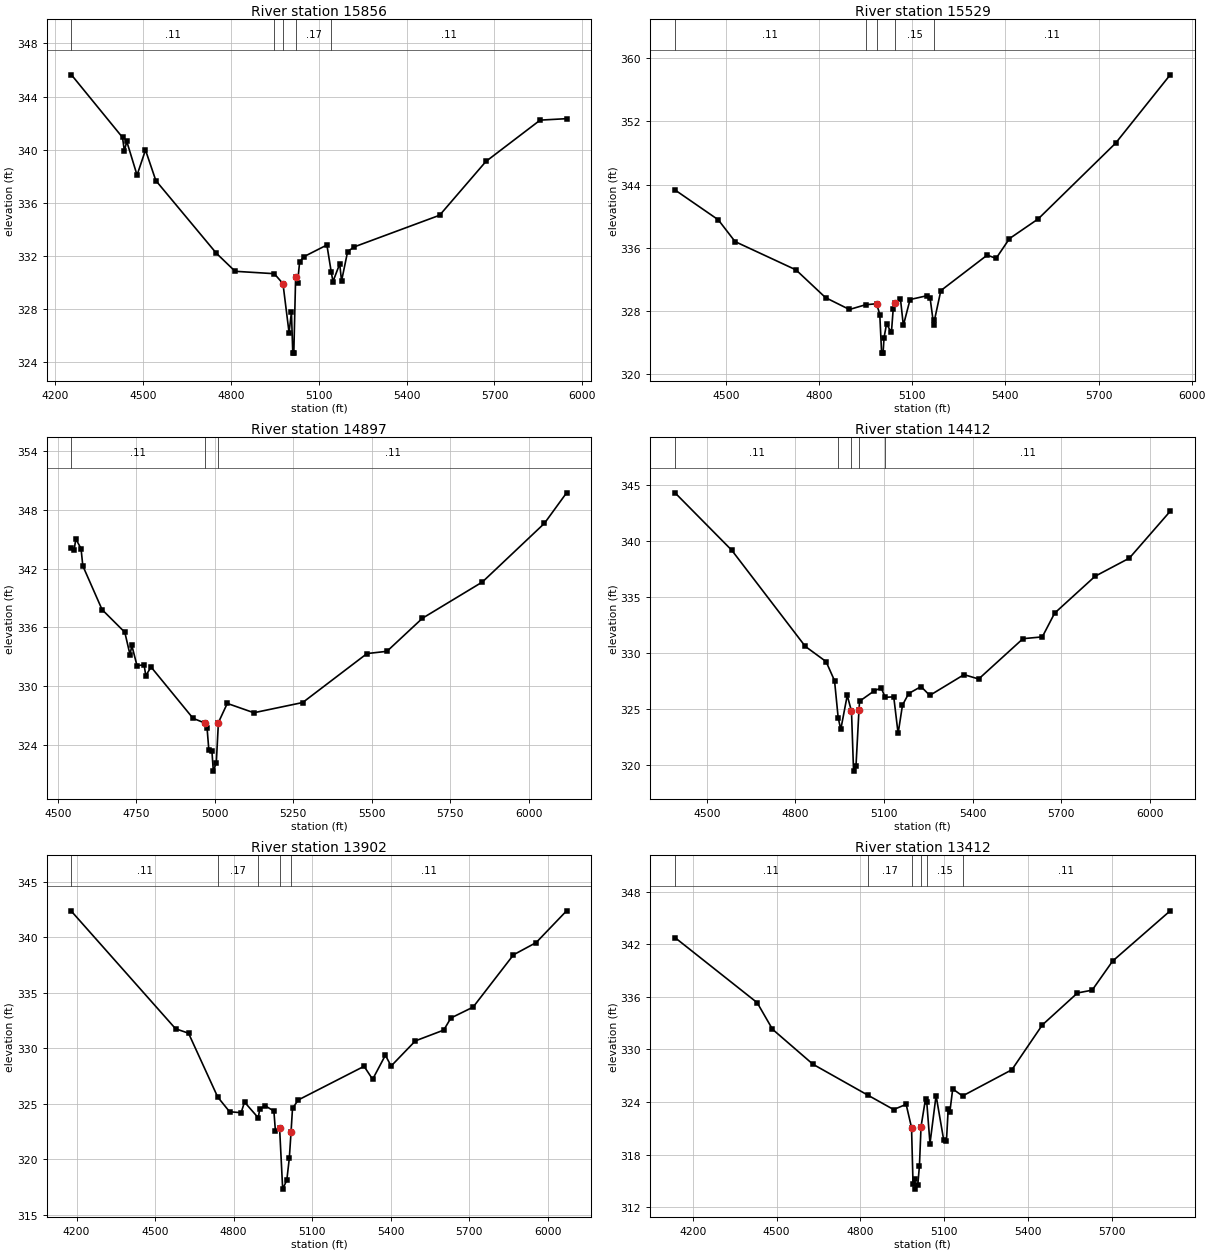
Type RM Length L Ch R = 1 ,15856   ,327,327,327
BEGIN DESCRIPTION:
HAYNIE CREEK 28.0
END DESCRIPTION:
XS GIS Cut Line= 3
      3684142.71     10156900.97      3683621.87     10156245.58
      3682941.64     10156761.16
#Sta/Elev= 30
  4255.6  345.64    4430  340.93  4436.4  339.91  4444.5  340.63  4479.7  338.09
  4508.5  339.98  4543.8  337.68  4750.4  332.21  4814.5  330.85  4948.2  330.67
  4977.9  329.92  4998.7  326.23  5006.8  327.78  5011.4  324.69  5014.9  324.69
  5021.2  330.45  5027.6  329.94  5034.6  331.52  5048.4  331.94  5127.9  332.83
  5142.9  330.77  5148.7  330.08  5171.6  331.41  5177.9  330.12  5198.7  332.34
  5221.5  332.69  5512.8  335.07  5670.9  339.12    5856  342.23  5946.3  342.34
#Mann= 5 ,-1 , 0
  4255.6     .11       0  4948.2     .17       0  4977.9     .09       0
  5021.2     .17       0  5142.9     .11       0
Bank Sta=4977.9,5021.2
XS Rating Curve= 0 ,0
Exp/Cntr=0.3,0.1

Type RM Length L Ch R = 1 ,15529   ,632,632,632
BEGIN DESCRIPTION:
Mapping XS a787d160
END DESCRIPTION:
XS GIS Cut Line= 3
       3684151.4     10156779.47       3683786.8     10155907.03
       3683375.5     10155404.82
#Sta/Elev= 30
  4336.2  343.33  4475.4  339.56  4529.6   336.8  4725.8  333.22    4821  329.71
  4897.8  328.21  4949.8  328.81  4985.5  328.94  4995.6  327.57  5001.5  322.69
  5006.2  322.69  5009.3  324.64  5017.3  326.38  5033.1  325.31  5038.9  328.32
 5043.64328.9724  5062.3  329.51  5071.5  326.19  5093.1  329.47  5147.3  329.95
  5157.5   329.7    5169  326.31  5171.8  326.88  5192.2   330.6  5341.5  335.09
  5370.2  334.68  5413.3  337.18  5505.8  339.67  5754.8  349.24  5930.9   357.9
#Mann= 5 ,-1 , 0
  4336.2     .11       0  4949.8     .15       0  4985.5     .09       0
 5043.64     .15       0  5171.8     .11       0
Bank Sta=4985.5,5043.64
XS Rating Curve= 0 ,0
Exp/Cntr=0.3,0.1

Type RM Length L Ch R = 1 ,14897   ,485,485,485
BEGIN DESCRIPTION:
HAYNIE CREEK 27.0
END DESCRIPTION:
XS GIS Cut Line= 3
      3684567.87      10156611.1      3684362.26     10156202.63
      3683567.88      10155411.1
#Sta/Elev= 30
  4542.7  344.11  4551.1  343.85  4556.7  345.02  4573.4  344.03    4579  342.28
  4640.4  337.82  4712.9  335.51  4729.6  333.21  4735.2  334.17  4751.9   332.1
  4774.3   332.2  4779.8  331.09  4796.6  331.97  4930.5  326.74  4968.2  326.26
  4975.1  325.79  4980.7  323.55  4990.5  323.46  4995.1  321.36  5004.6  322.22
  5011.3  326.31  5039.6  328.26  5124.4  327.31    5280  328.35  5485.1  333.34
  5548.7  333.57  5661.8  336.94  5852.8  340.63  6050.7  346.61  6121.4  349.72
#Mann= 3 , 0 , 0
  4542.7     .11       0  4968.2     .06       0  5011.3     .11       0
Bank Sta=4968.2,5011.3
XS Rating Curve= 0 ,0
Exp/Cntr=0.3,0.1

Type RM Length L Ch R = 1 ,14412   ,510,510,510
BEGIN DESCRIPTION:
HAYNIE CREEK 26.0
END DESCRIPTION:
XS GIS Cut Line= 3
      3685200.83     10156398.33      3684732.17     10156012.27
      3683857.14     10155398.37
#Sta/Elev= 30
  4392.8  344.33  4584.8  339.19  4833.7  330.58    4904  329.22  4932.7  327.51
    4945   324.2  4953.8  323.14  4975.7  326.19  4990.1  324.77  4997.1  319.41
  5005.4  319.91 5015.47324.9057  5017.5  325.67  5067.7  326.61  5090.8  326.86
    5104  326.02  5133.1  326.06  5147.9  322.78  5162.7  325.32  5183.7  326.36
  5225.5  326.98  5255.1  326.19    5371  328.05  5420.6  327.66  5570.6  331.27
    5636  331.43  5677.8  333.56  5814.7  336.86  5930.6  338.48  6068.9  342.68
#Mann= 5 ,-1 , 0
  4392.8     .11       0    4945     .15       0  4990.1     .09       0
 5015.47     .15       0    5104     .11       0
Bank Sta=4990.1,5015.47
XS Rating Curve= 0 ,0
Exp/Cntr=0.3,0.1

Type RM Length L Ch R = 1 ,13902   ,490,490,490
BEGIN DESCRIPTION:
HAYNIE CREEK 25.0
END DESCRIPTION:
XS GIS Cut Line= 3
      3685216.49     10156330.65      3684773.78     10155523.35
      3683846.74     10155236.91
#Sta/Elev= 30
  4180.6  342.35  4578.4  331.77  4627.8  331.37  4739.3  325.62  4784.6   324.3
  4828.7  324.21  4841.6  325.17  4894.1  323.75  4899.8  324.55  4921.6  324.82
  4953.8  324.36  4959.5  322.59  4975.6  322.81  4987.4  317.33  5003.1  318.14
  5012.7  320.11  5019.2  322.43  5024.9   324.6  5046.9  325.36  5298.2  328.39
  5330.9  327.22  5379.6  329.39  5401.4  328.41  5494.1  330.68  5602.4  331.65
  5629.8  332.74  5714.6  333.72  5868.8  338.43  5955.3  339.53  6071.6  342.39
#Mann= 5 ,-1 , 0
  4180.6     .11       0  4739.3     .17       0  4894.1     .15       0
  4975.6     .06       0  5019.2     .11       0
Bank Sta=4975.6,5019.2
XS Rating Curve= 0 ,0
Exp/Cntr=0.3,0.1

Type RM Length L Ch R = 1 ,13412   ,548,548,548
BEGIN DESCRIPTION:
HAYNIE CREEK 24.0
END DESCRIPTION:
XS GIS Cut Line= 3
      3685467.87     10156261.12      3685158.54     10155455.03
      3684717.83     10154661.04
#Sta/Elev= 30
  4136.6  342.76  4430.5  335.34  4485.2  332.31  4629.9  328.32  4825.9   324.8
  4918.6  323.15  4963.4  323.74  4982.7  321.09  4988.1  314.61  4993.5  315.25
  4996.6  314.07  5005.1  314.57    5011  316.75  5016.7   321.2  5032.7  324.37
  5037.2  323.99  5048.7  319.27  5070.5  324.75  5097.9  319.65  5107.5  319.52
    5114  323.24  5119.7  322.85    5130   325.5  5165.2   324.7  5341.7  327.69
  5450.6   332.8  5576.4  336.45  5628.9  336.77  5702.2  340.09  5908.1  345.82
#Mann= 6 ,-1 , 0
  4136.6     .11       0  4825.9     .17       0  4982.7     .09       0
  5016.7     .17       0  5037.2     .15       0  5165.2     .11       0
Bank Sta=4982.7,5016.7
XS Rating Curve= 0 ,0
Exp/Cntr=0.3,0.1

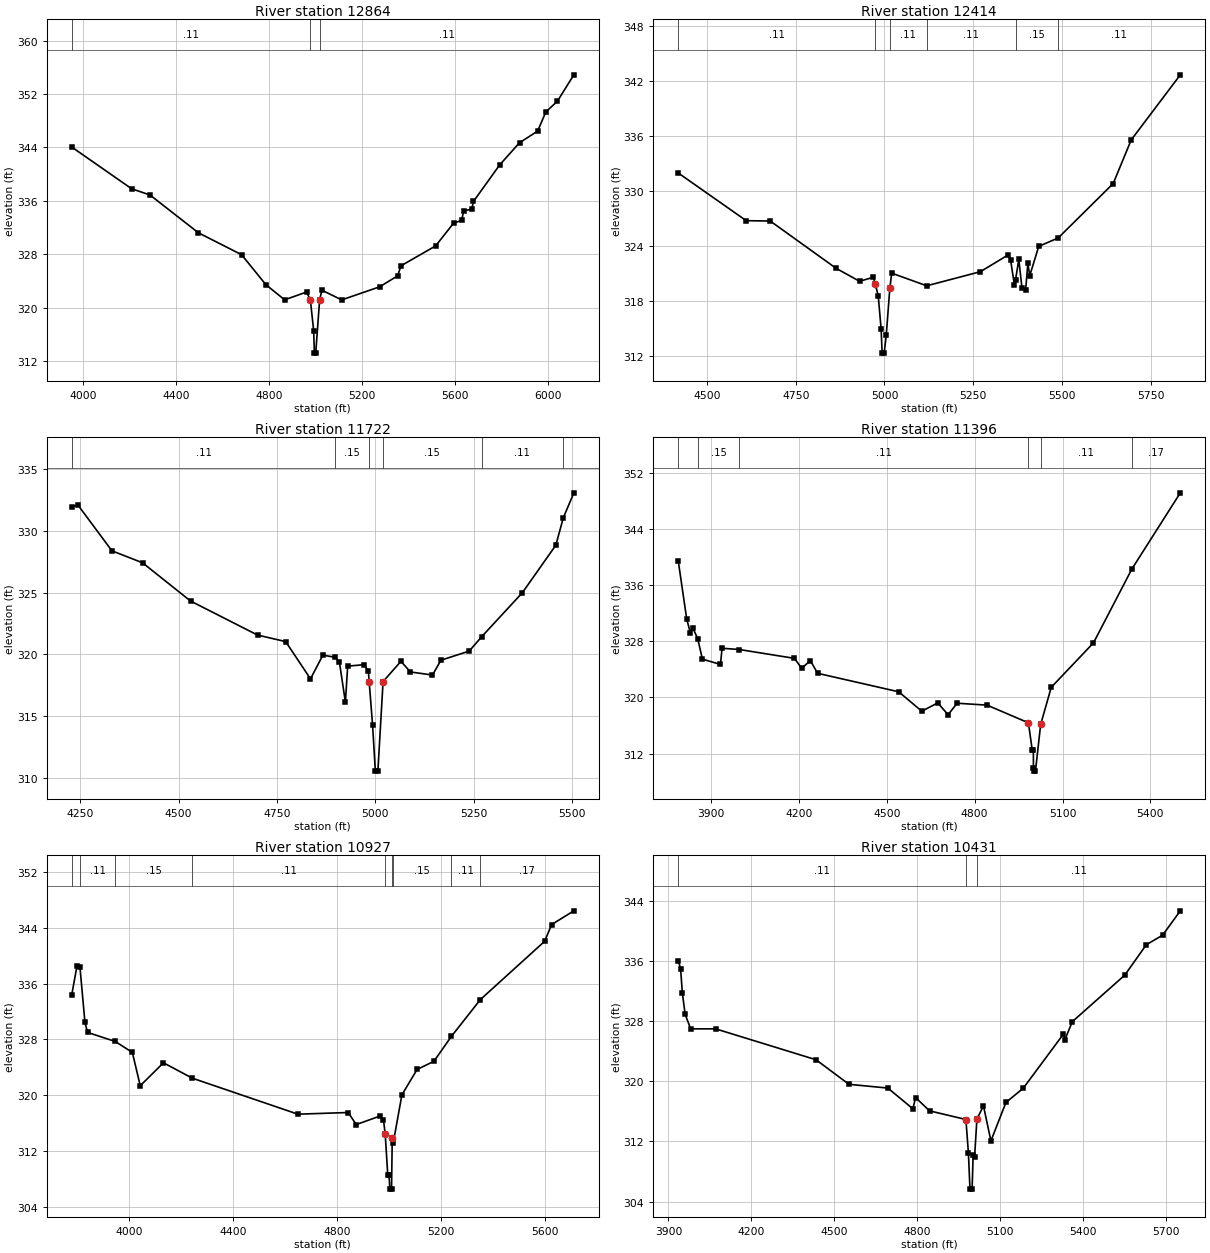
Type RM Length L Ch R = 1 ,12864   ,450,450,450
BEGIN DESCRIPTION:
HAYNIE CREEK 23.0
END DESCRIPTION:
XS GIS Cut Line= 3
      3686039.41     10156127.54      3685544.61     10155205.65
      3684717.86     10154461.08
#Sta/Elev= 30
  3950.5  344.06  4207.5  337.82  4287.1  336.87    4495  331.21  4680.9  327.92
  4784.9  323.44  4865.8  321.16  4960.2  322.33  4976.5  321.13  4990.6  316.55
  4993.7  313.17  4999.4  313.17 5016.29321.1691  5026.1   322.6  5111.3  321.15
  5274.2  323.11  5351.9  324.76  5366.1  326.26  5514.9  329.24  5592.6  332.67
  5627.7  333.07  5635.2  334.52  5670.3  334.73  5677.8  335.91  5790.6  341.39
  5875.8  344.71  5953.6  346.45  5988.7  349.31  6038.8  350.94  6109.4  354.89
#Mann= 3 ,-1 , 0
  3950.5     .11       0  4976.5     .06       0 5016.29     .11       0
Bank Sta=4976.5,5016.29
XS Rating Curve= 0 ,0
Exp/Cntr=0.3,0.1

Type RM Length L Ch R = 1 ,12414   ,692,692,692
BEGIN DESCRIPTION:
HAYNIE CREEK 22.0
END DESCRIPTION:
XS GIS Cut Line= 3
      3686167.86     10155561.08      3685899.66     10155045.57
      3685617.85     10154261.05
#Sta/Elev= 30
  4418.9  331.99  4610.5  326.79  4678.2  326.75  4863.6   321.6  4929.9  320.18
  4968.5  320.62  4974.2  319.87  4982.5  318.59  4990.6  314.96  4993.4  312.35
  4999.2  312.35    5005  314.29  5015.1  319.43  5020.4  321.07  5119.1  319.69
  5270.4  321.23  5347.8  323.04  5355.4  322.49  5366.1  319.81  5369.4  320.35
  5378.5  322.56  5387.3   319.5  5397.9  319.26    5404  322.17  5409.3  320.79
  5434.7  323.99  5489.6  324.91  5644.5  330.84  5695.3   335.6  5833.6  342.69
#Mann= 6 ,-1 , 0
  4418.9     .11       0  4974.2     .09       0  5015.1     .11       0
  5119.1     .11       0  5369.4     .15       0  5489.6     .11       0
Bank Sta=4974.2,5015.1
XS Rating Curve= 0 ,0
Exp/Cntr=0.3,0.1

Type RM Length L Ch R = 1 ,11722   ,326,326,326
BEGIN DESCRIPTION:
Mapping XS b61f173c
END DESCRIPTION:
XS GIS Cut Line= 3
      3686338.19      10155508.2      3686077.78     10154708.72
      3685812.52     10154362.85
#Sta/Elev= 30
  4228.2   331.9  4243.2  332.12  4330.3  328.38  4408.1  327.41  4530.2  324.31
  4700.6  321.55  4772.1  321.02  4835.2     318  4866.7  319.92  4898.2  319.75
  4908.8  319.35    4924  316.11  4929.8  319.03  4971.9  319.15  4982.4  318.61
 4984.46 317.771  4993.1  314.24  5000.2  310.52  5006.6  310.52  5019.8  317.78
  5065.2  319.42  5089.3  318.56  5145.4  318.31  5166.9  319.51  5238.8  320.25
  5270.1   321.4  5373.9  324.98    5459  328.83  5478.2  331.06  5504.9  333.08
#Mann= 6 ,-1 , 0
  4228.2     .11       0  4898.2     .15       0 4984.46     .09       0
  5019.8     .15       0  5270.1     .11       0  5478.2     .17       0
Bank Sta=4984.46,5019.8
XS Rating Curve= 0 ,0
Exp/Cntr=0.3,0.1

Type RM Length L Ch R = 1 ,11396   ,469,469,469
BEGIN DESCRIPTION:
HAYNIE CREEK 21.0
END DESCRIPTION:
XS GIS Cut Line= 3
      3686586.27     10155637.92      3686145.49     10154508.64
      3685867.52     10154091.05
#Sta/Elev= 30
  3788.2  339.48    3817  331.23  3829.1  329.26  3838.5  329.86  3854.6   328.4
  3870.7  325.47  3932.4  324.71  3937.8  327.02  3996.3  326.84    4185  325.58
  4209.5  324.16  4239.3  325.26  4263.8  323.45  4540.9  320.81  4619.7  318.04
  4674.1  319.23  4709.3  317.54  4740.2  319.18  4842.4  318.91  4983.6  316.39
  4996.5  312.52  5000.5  312.52  5000.7     310  5001.2   309.5  5007.6   309.5
  5025.4  316.15  5061.5  321.45  5205.7  327.79  5336.5   338.3  5502.1  349.18
#Mann= 6 ,-1 , 0
  3788.2     .11       0  3854.6     .15       0  3996.3     .11       0
  4983.6     .09       0  5025.4     .11       0  5336.5     .17       0
Bank Sta=4983.6,5025.4
XS Rating Curve= 0 ,0
Exp/Cntr=0.3,0.1

Type RM Length L Ch R = 1 ,10927   ,496,496,496
BEGIN DESCRIPTION:
HAYNIE CREEK 20.0
END DESCRIPTION:
XS GIS Cut Line= 3
      3686667.85     10155611.04      3686479.27     10154406.61
      3686118.08     10153795.12
#Sta/Elev= 30
  3780.9  334.41  3801.1  338.56  3812.4  338.35  3831.5  330.43  3841.6     329
  3947.8   327.7  4013.7  326.13    4044  321.35  4133.2  324.64  4244.4  322.43
  4649.9  317.27  4843.1  317.51    4874  315.78  4965.1     317  4978.6  316.49
  4985.4  314.36  4995.2  308.53    5000  308.53  5003.2  306.52  5009.6  306.52
  5012.4  313.82  5015.9  313.09  5049.5  320.05    5108  323.69  5172.4  324.85
  5239.7  328.43    5351  333.71  5597.7  342.06    5625  344.47  5710.2  346.44
#Mann= 9 ,-1 , 0
  3780.9     .15       0  3812.4     .11       0  3947.8     .15       0
  4244.4     .11       0  4985.4     .06       0  5012.4     .11       0
  5015.9     .15       0  5239.7     .11       0    5351     .17       0
Bank Sta=4985.4,5012.4
XS Rating Curve= 0 ,0
Exp/Cntr=0.3,0.1

Type RM Length L Ch R = 1 ,10431   ,499,499,499
BEGIN DESCRIPTION:
HAYNIE CREEK 19.0
END DESCRIPTION:
XS GIS Cut Line= 3
      3686732.11      10155585.9      3686841.27     10154527.01
      3687070.66      10153809.8
#Sta/Elev= 30
  3935.5  336.08  3944.1  334.98  3950.4  331.76  3960.5  328.92  3980.6  326.99
    4071  326.99  4434.2  322.88  4553.6  319.61  4694.3  319.11  4784.8  316.36
  4794.9  317.84  4845.1  316.08 4976.83314.9261  4985.9  310.49  4991.6  305.66
  4999.3  305.66  5003.1  310.21  5008.3  309.96  5016.7  314.99  5040.5  316.73
  5067.4  312.08  5121.7  317.19  5184.7   319.1    5330   326.3  5335.2  325.56
  5362.1  327.95  5552.2  334.15  5629.9  338.19  5688.7  339.45    5753   342.7
#Mann= 3 , 0 , 0
  3935.5     .11       0 4976.83     .06       0  5016.7     .11       0
Bank Sta=4976.83,5016.7
XS Rating Curve= 0 ,0
Exp/Cntr=0.3,0.1

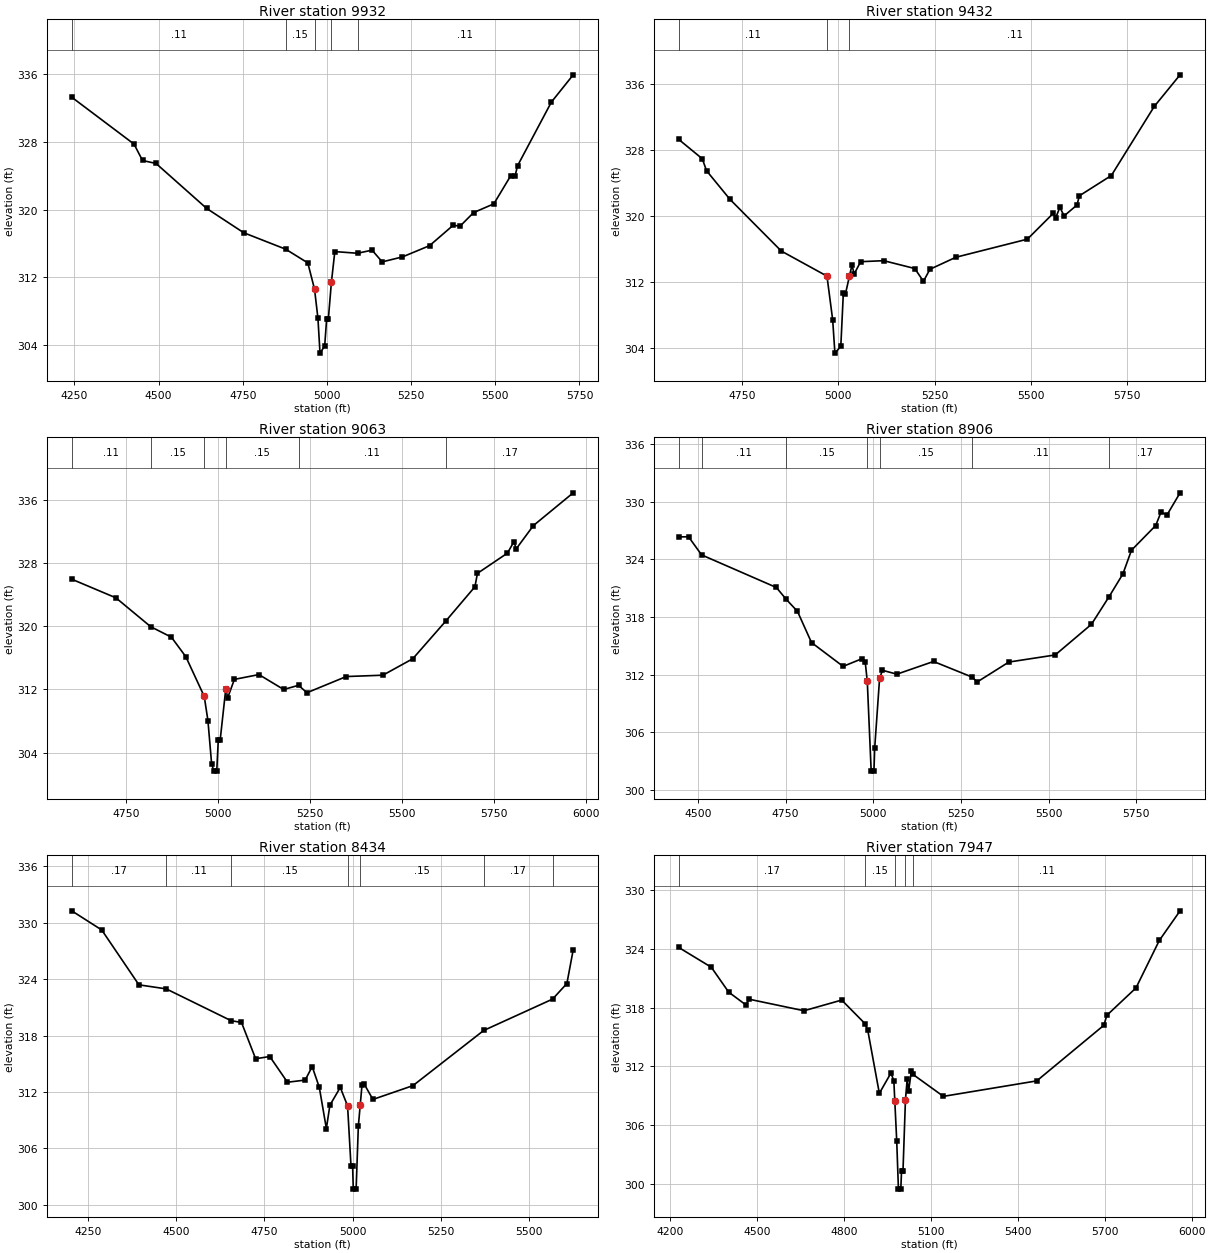
Type RM Length L Ch R = 1 ,9932    ,500,500,500
BEGIN DESCRIPTION:
HAYNIE CREEK 18.0
END DESCRIPTION:
XS GIS Cut Line= 3
      3687221.69     10155460.89      3687267.46     10154704.38
      3687195.66     10153976.51
#Sta/Elev= 30
  4242.1   333.3  4427.1  327.75  4452.3  325.81  4492.4  325.46  4642.7  320.14
  4752.9  317.26  4877.6  315.31  4943.2  313.69  4963.2  310.57  4973.3  307.12
  4979.4  303.01  4993.3  303.85  4999.2  307.07  5004.2  307.07  5013.4  311.45
  5023.4  315.03  5090.8  314.83    5134   315.2  5164.1  313.81  5224.4   314.4
  5304.8  315.73  5375.1  318.15  5395.2  318.03  5435.4  319.64  5495.7  320.68
  5545.9  324.01  5558.6  323.95    5566  325.18  5666.5  332.72  5731.4  335.95
#Mann= 5 ,-1 , 0
  4242.1     .11       0  4877.6     .15       0  4963.2     .09       0
  5013.4     .15       0  5090.8     .11       0
Bank Sta=4963.2,5013.4
XS Rating Curve= 0 ,0
Exp/Cntr=0.3,0.1

Type RM Length L Ch R = 1 ,9432    ,369,369,369
BEGIN DESCRIPTION:
HAYNIE CREEK 17.0
END DESCRIPTION:
XS GIS Cut Line= 3
      3687517.85     10155161.06      3687609.16     10154757.05
      3687217.84     10153961.04
#Sta/Elev= 30
  4585.8  329.25  4647.3  326.89  4658.3  325.44  4719.1  321.97  4852.3   315.7
  4970.8  312.66  4985.6  307.36  4991.4  303.32  5006.7  304.14  5013.3  310.62
  5018.8   310.5    5029  312.64  5035.7     314  5041.3  312.91  5058.2  314.41
  5118.1  314.53  5198.6  313.58  5221.1  312.03    5238  313.49  5305.5  314.95
  5490.8  317.14  5558.3  320.29  5563.8  319.67    5575  320.99  5586.3  319.97
  5619.5  321.28  5625.7   322.4  5708.7  324.86  5820.1  333.24    5887  337.07
#Mann= 3 , 0 , 0
  4585.8     .11       0  4970.8     .06       0    5029     .11       0
Bank Sta=4970.8,5029
XS Rating Curve= 0 ,0
Exp/Cntr=0.3,0.1

Type RM Length L Ch R = 1 ,9063    ,157,157,157
BEGIN DESCRIPTION:
HAYNIE CREEK 16.0
END DESCRIPTION:
XS GIS Cut Line= 3
      3687917.85      10155211.1      3687940.45     10154809.81
       3687560.6     10153925.24
#Sta/Elev= 30
  4601.9  325.97  4722.1  323.61  4816.9  319.95    4873  318.63  4912.4  316.15
  4962.5  311.12  4972.5  308.06  4982.5   302.6  4988.6  301.66  4996.5  301.66
  5000.7  305.63  5005.9  305.63  5020.9  312.01  5026.4  310.97  5044.5  313.28
  5111.3  313.89  5178.6     312  5219.1  312.53  5241.9  311.59  5348.9  313.64
  5448.6  313.81  5530.1   315.9  5619.6  320.66    5699  325.01  5705.9  326.71
  5787.4  329.27  5805.5  330.74    5811  329.79  5858.1  332.76  5966.5  336.91
#Mann= 6 ,-1 , 0
  4601.9     .11       0  4816.9     .15       0  4962.5     .09       0
  5020.9     .15       0  5219.1     .11       0  5619.6     .17       0
Bank Sta=4962.5,5020.9
XS Rating Curve= 0 ,0
Exp/Cntr=0.3,0.1

Type RM Length L Ch R = 1 ,8906    ,472,472,472
BEGIN DESCRIPTION:
Mapping XS ca78a045
END DESCRIPTION:
XS GIS Cut Line= 5
      3688138.76     10155269.28      3688108.38     10154761.46
      3688043.27     10154718.05      3687910.89     10154718.05
      3687652.73     10154056.39
#Sta/Elev= 30
  4444.9  326.33  4473.2  326.35  4510.5  324.46  4723.6  321.07  4751.9  319.83
  4783.7  318.59  4823.8  315.34  4913.9  312.86  4967.8  313.66  4976.8  313.35
  4982.8  311.31  4993.9  301.96  5001.8  301.96  5003.9  304.34 5017.94311.6376
  5026.1  312.45  5067.3  312.05  5171.7  313.37  5282.7  311.73  5295.8  311.23
  5386.4  313.31  5518.6  314.05  5621.9  317.24  5671.9   320.1  5711.5  322.48
    5736  324.95  5805.1  327.52  5820.2  328.91  5837.3  328.62  5874.5  330.92
#Mann= 7 ,-1 , 0
  4444.9     .17       0  4510.5     .11       0  4751.9     .15       0
  4982.8     .09       0 5017.94     .15       0  5282.7     .11       0
  5671.9     .17       0
Bank Sta=4982.8,5017.94
XS Rating Curve= 0 ,0
Exp/Cntr=0.3,0.1

Type RM Length L Ch R = 1 ,8434    ,487,487,487
BEGIN DESCRIPTION:
HAYNIE CREEK 15.0
END DESCRIPTION:
XS GIS Cut Line= 3
      3688167.85     10155411.02      3688121.05      10154616.9
      3687967.85     10154011.07
#Sta/Elev= 30
  4204.5  331.28  4289.5  329.24  4394.8   323.4  4472.1  322.97  4656.1  319.58
  4685.3   319.4  4725.4  315.53  4765.4  315.77  4815.5  313.03  4865.6  313.26
  4885.6  314.69  4905.7  312.49  4925.7   308.1  4935.7  310.58  4965.1  312.48
  4985.8  310.51  4995.4  304.16    5000  304.16    5002  301.65    5010  301.65
  5016.3  308.35 5021.54310.5681  5026.6  312.71  5032.6  312.85  5057.6   311.2
    5171  312.67  5371.3  318.54  5566.4  321.88    5607  323.54  5624.9  327.13
#Mann= 7 ,-1 , 0
  4204.5     .17       0  4472.1     .11       0  4656.1     .15       0
  4985.8     .09       0 5021.54     .15       0  5371.3     .17       0
  5566.4     .11       0
Bank Sta=4985.8,5021.54
XS Rating Curve= 0 ,0
Exp/Cntr=0.3,0.1

Type RM Length L Ch R = 1 ,7947    ,328,328,328
BEGIN DESCRIPTION:
HAYNIE CREEK 14.0
END DESCRIPTION:
XS GIS Cut Line= 3
      3688617.53     10155413.99       3688595.2     10154642.91
       3688476.9     10153690.03
#Sta/Elev= 30
  4228.6  324.16  4341.6  322.13  4401.6  319.59  4461.6  318.27  4471.6  318.87
  4661.7  317.69  4791.8  318.78  4872.4  316.37  4881.8   315.7  4921.8  309.26
  4961.8  311.33  4971.8  310.55  4975.2308.4587  4981.8   304.4  4987.7  299.48
  4995.9  299.48  4998.4  301.31  5003.4  301.31  5011.9  308.58    5018  310.73
    5023  309.49  5032.1  311.51  5037.9  311.19  5142.9  308.95  5465.4  310.53
  5697.2  316.21  5707.2  317.22    5808  320.02  5888.6  324.87  5960.2  327.89
#Mann= 5 ,-1 , 0
  4228.6     .17       0  4872.4     .15       0  4975.2     .09       0
  5011.9     .15       0  5037.9     .11       0
Bank Sta=4975.2,5011.9
XS Rating Curve= 0 ,0
Exp/Cntr=0.3,0.1