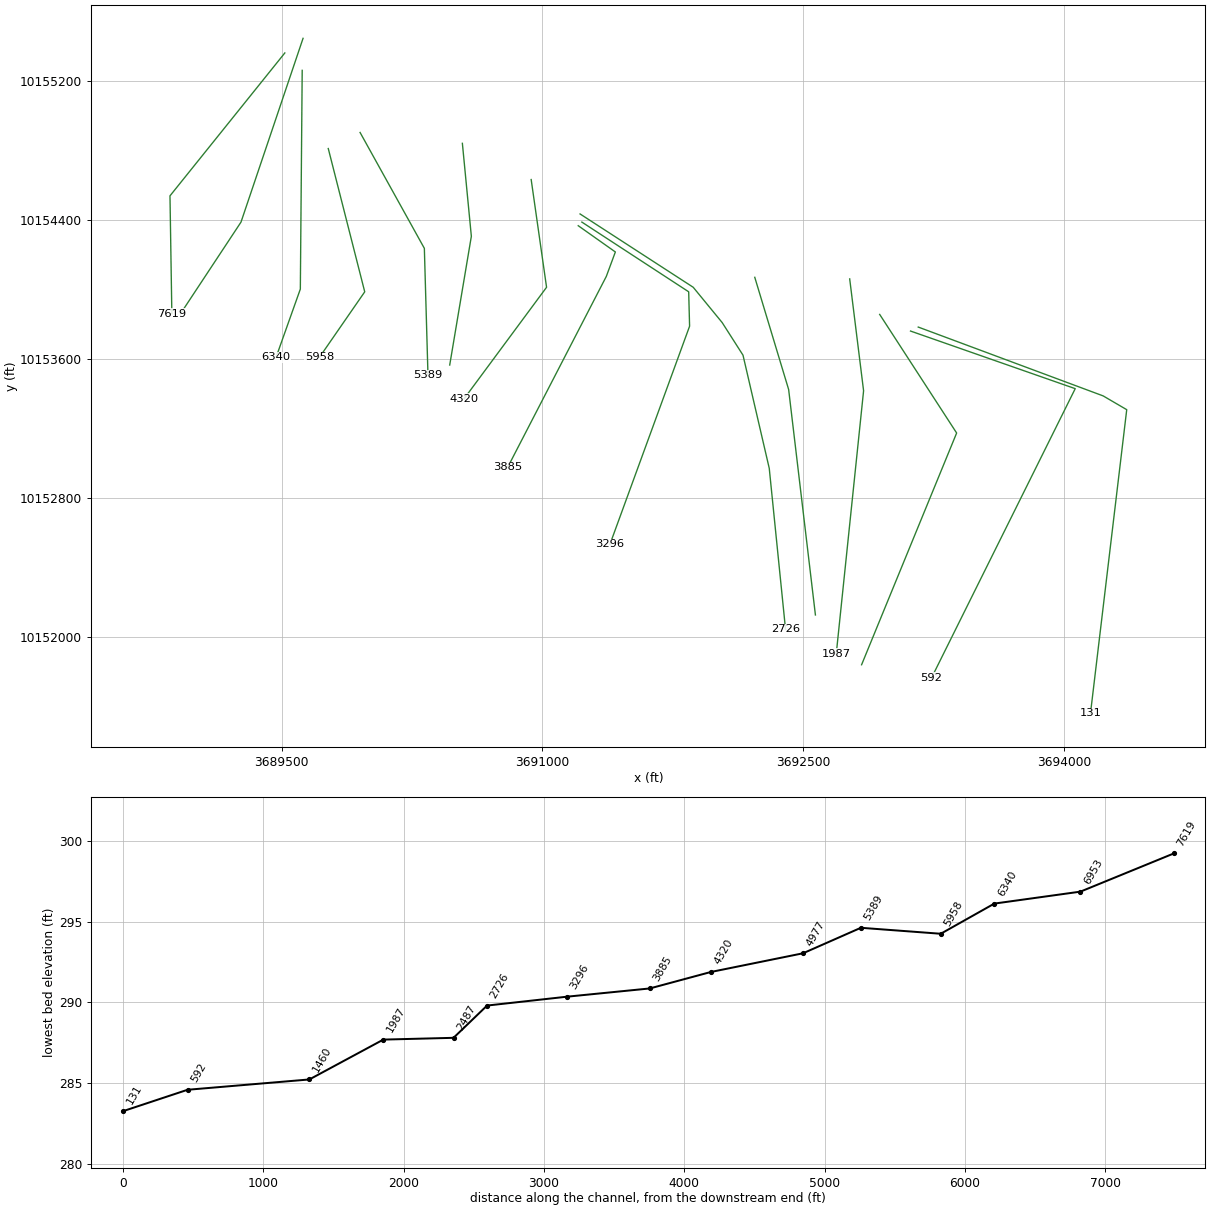
HEC-RAS study HAYNIE CREEK.prj: HAYNIE CREEK Base Level Engineering

--- HAYNIE CREEK.g01 (geometry) --- (continued)

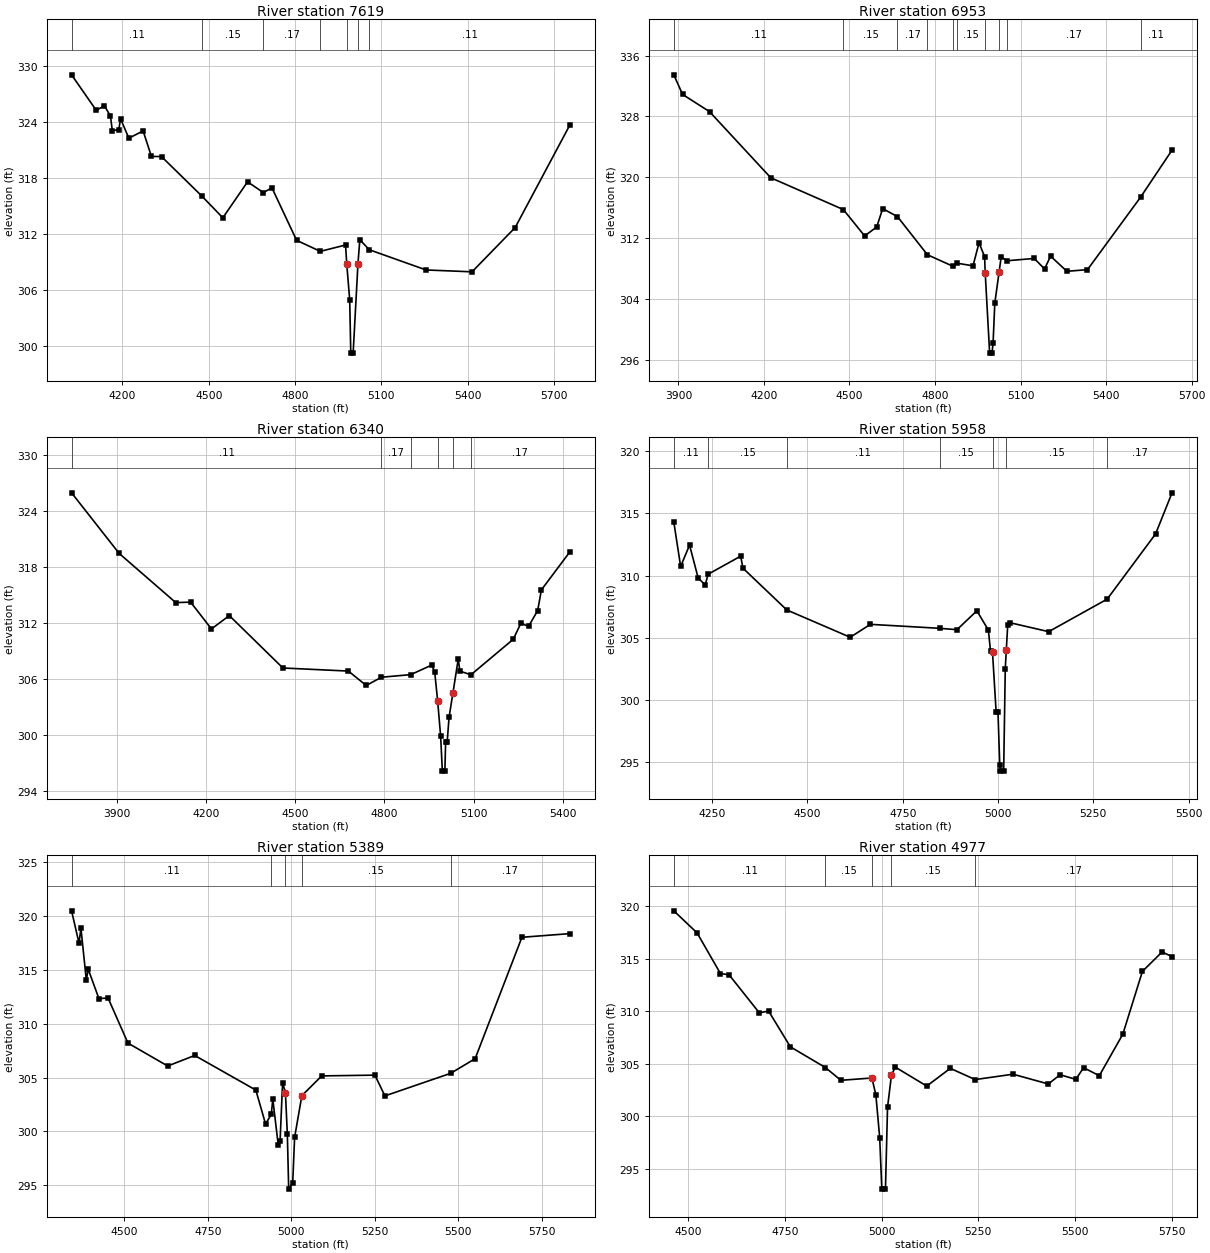
Type RM Length L Ch R = 1 ,7619    ,666,666,666
BEGIN DESCRIPTION:
HAYNIE CREEK 13.0
END DESCRIPTION:
XS GIS Cut Line= 3
      3689517.87     10155361.09      3688857.11     10154538.98
      3688867.85      10153861.1
#Sta/Elev= 30
    4023  329.01  4108.6  325.22  4137.4  325.69  4158.2   324.6  4164.6  323.05
    4187  323.14  4193.4   324.3  4222.2  322.23  4271.8  323.01  4300.6  320.28
  4335.8  320.26  4476.3  316.03    4549  313.71    4635  317.56  4690.1  316.41
  4719.8  316.92  4805.6   311.3  4888.1  310.12  4975.8   310.8 4979.97308.7669
  4990.2  304.93    4994  299.23  5002.2  299.23    5019  308.82  5025.4  311.36
  5058.6  310.29  5255.7  308.13  5415.7  307.93  5565.7  312.67  5755.7  323.63
#Mann= 7 ,-1 , 0
    4023     .11       0  4476.3     .15       0  4690.1     .17       0
  4888.1     .15       0 4979.97     .09       0    5019     .15       0
  5058.6     .11       0
Bank Sta=4979.97,5019
XS Rating Curve= 0 ,0
Exp/Cntr=0.3,0.1

Type RM Length L Ch R = 1 ,6953    ,613,613,613
BEGIN DESCRIPTION:
HAYNIE CREEK 12.0
END DESCRIPTION:
XS GIS Cut Line= 3
      3689622.73      10155445.2      3689265.66     10154387.76
      3688917.83     10153861.04
#Sta/Elev= 30
  3883.9  333.46  3914.7  330.88  4009.1  328.62    4224  319.92  4478.4  315.74
  4553.2  312.27  4595.4  313.45  4616.5  315.86  4668.1  314.82  4773.2   309.8
  4861.9   308.3  4878.4  308.68  4933.2  308.34  4954.3  311.37  4973.8  309.55
 4975.97 307.437  4991.5  296.86  4999.8  296.86  5003.6  298.21  5009.6  303.43
  5024.6  307.51    5032  309.53  5052.7  309.01    5148  309.31  5184.2  307.93
  5205.2  309.62  5262.4  307.62  5334.7  307.84  5521.1  317.38  5631.2  323.56
#Mann= 10 ,-1 , 0
  3883.9     .11       0  4478.4     .15       0  4668.1     .17       0
  4773.2     .11       0  4861.9     .17       0  4878.4     .15       0
 4975.97     .09       0  5024.6     .15       0  5052.7     .17       0
  5521.1     .11       0
Bank Sta=4975.97,5024.6
XS Rating Curve= 0 ,0
Exp/Cntr=0.3,0.1

Type RM Length L Ch R = 1 ,6340    ,382,382,382
BEGIN DESCRIPTION:
HAYNIE CREEK 11.0
END DESCRIPTION:
XS GIS Cut Line= 3
      3689617.85     10155261.03      3689607.11     10154002.52
      3689467.86      10153611.1
#Sta/Elev= 30
  3748.7  325.91  3908.7  319.42  4098.7  314.16  4148.7  314.21  4218.7  311.34
  4278.7  312.77  4458.7  307.16  4678.7  306.83  4738.7  305.29  4789.8  306.17
  4888.2  306.45  4958.7  307.47  4968.7  306.77  4978.7  303.62  4988.7  299.86
  4994.5  296.12  5002.9  296.12  5005.5  299.25  5010.7  299.25    5017  301.89
    5030  304.48  5047.9  308.13  5053.2  306.83  5090.4  306.43  5232.9  310.24
  5258.4  311.96    5284  311.61  5314.8  313.31  5327.2  315.52  5422.7  319.58
#Mann= 6 ,-1 , 0
  3748.7     .11       0  4789.8     .17       0  4888.2     .15       0
  4978.7     .09       0    5030     .15       0  5090.4     .17       0
Bank Sta=4978.7,5030
XS Rating Curve= 0 ,0
Exp/Cntr=0.3,0.1

Type RM Length L Ch R = 1 ,5958    ,569,569,569
BEGIN DESCRIPTION:
HAYNIE CREEK 10.0
END DESCRIPTION:
XS GIS Cut Line= 3
      3689767.85     10154811.08       3689977.6     10153986.75
      3689717.87      10153611.1
#Sta/Elev= 30
  4149.4  314.31  4167.3  310.73  4190.7  312.45  4213.4  309.79    4232  309.24
  4239.1   310.1  4324.8  311.56  4330.9  310.59  4445.8  307.23  4612.2  305.03
  4665.3  306.07  4846.9  305.75  4892.4  305.64  4944.6  307.16  4974.9   305.6
  4980.4  303.89  4985.6  303.83  4995.2  298.98    5000  298.98  5004.6  294.77
  5006.5  294.25  5014.9  294.25  5019.1  302.51 5021.85304.0139  5025.5  306.01
  5031.6   306.2    5133  305.48  5286.5   308.1  5413.5  313.35  5456.7  316.66
#Mann= 7 ,-1 , 0
  4149.4     .11       0  4239.1     .15       0  4445.8     .11       0
  4846.9     .15       0  4985.6     .09       0 5021.85     .15       0
  5286.5     .17       0
Bank Sta=4985.6,5021.85
XS Rating Curve= 0 ,0
Exp/Cntr=0.3,0.1

Type RM Length L Ch R = 1 ,5389    ,412,412,412
BEGIN DESCRIPTION:
HAYNIE CREEK 9.0
END DESCRIPTION:
XS GIS Cut Line= 3
      3689950.88     10154903.53      3690320.65      10154236.9
      3690341.49     10153507.71
#Sta/Elev= 30
  4342.4   320.5  4364.7  317.49  4370.4  318.89  4386.5  314.07  4392.2  315.07
  4424.2  312.34  4451.7  312.39  4511.2   308.2  4630.2  306.07  4711.1  307.05
  4894.1  303.83  4923.2  300.68  4940.4  301.57  4944.9     303    4961  298.77
  4966.7  299.11  4974.2  304.52  4982.7   303.6  4988.4  299.76  4992.5  294.62
  5004.5  295.21  5010.2  299.43  5031.9  303.31  5091.4  305.15  5250.6  305.22
  5280.6  303.29  5477.5  305.39  5550.7  306.75  5690.8  318.04  5834.2  318.38
#Mann= 5 ,-1 , 0
  4342.4     .11       0  4940.4     .15       0  4982.7     .09       0
  5031.9     .15       0  5477.5     .17       0
Bank Sta=4982.7,5031.9
XS Rating Curve= 0 ,0
Exp/Cntr=0.3,0.1

Type RM Length L Ch R = 1 ,4977    ,657,657,657
BEGIN DESCRIPTION:
HAYNIE CREEK 8.0
END DESCRIPTION:
XS GIS Cut Line= 3
       3690539.4     10154841.11      3690591.04     10154306.19
      3690466.58     10153565.58
#Sta/Elev= 30
  4462.6  319.56  4522.9  317.45  4583.2  313.58  4605.4  313.47  4683.7  309.84
  4707.7  310.01    4764   306.6  4854.5  304.63  4894.6  303.41    4975  303.63
  4985.1  302.01    4995  297.95  5000.5  293.04  5009.9  293.04  5015.3  300.84
  5025.5  303.93  5035.6  304.66  5116.7  302.86  5177.6  304.55  5241.8  303.48
  5339.8  303.99  5431.1  303.06  5461.5  303.94  5502.1   303.5  5522.3  304.61
  5562.9  303.85  5623.7   307.8  5674.4  313.79  5725.2  315.64    5751   315.2
#Mann= 5 ,-1 , 0
  4462.6     .11       0  4854.5     .15       0    4975     .09       0
  5025.5     .15       0  5241.8     .17       0
Bank Sta=4975,5025.5
XS Rating Curve= 0 ,0
Exp/Cntr=0.3,0.1

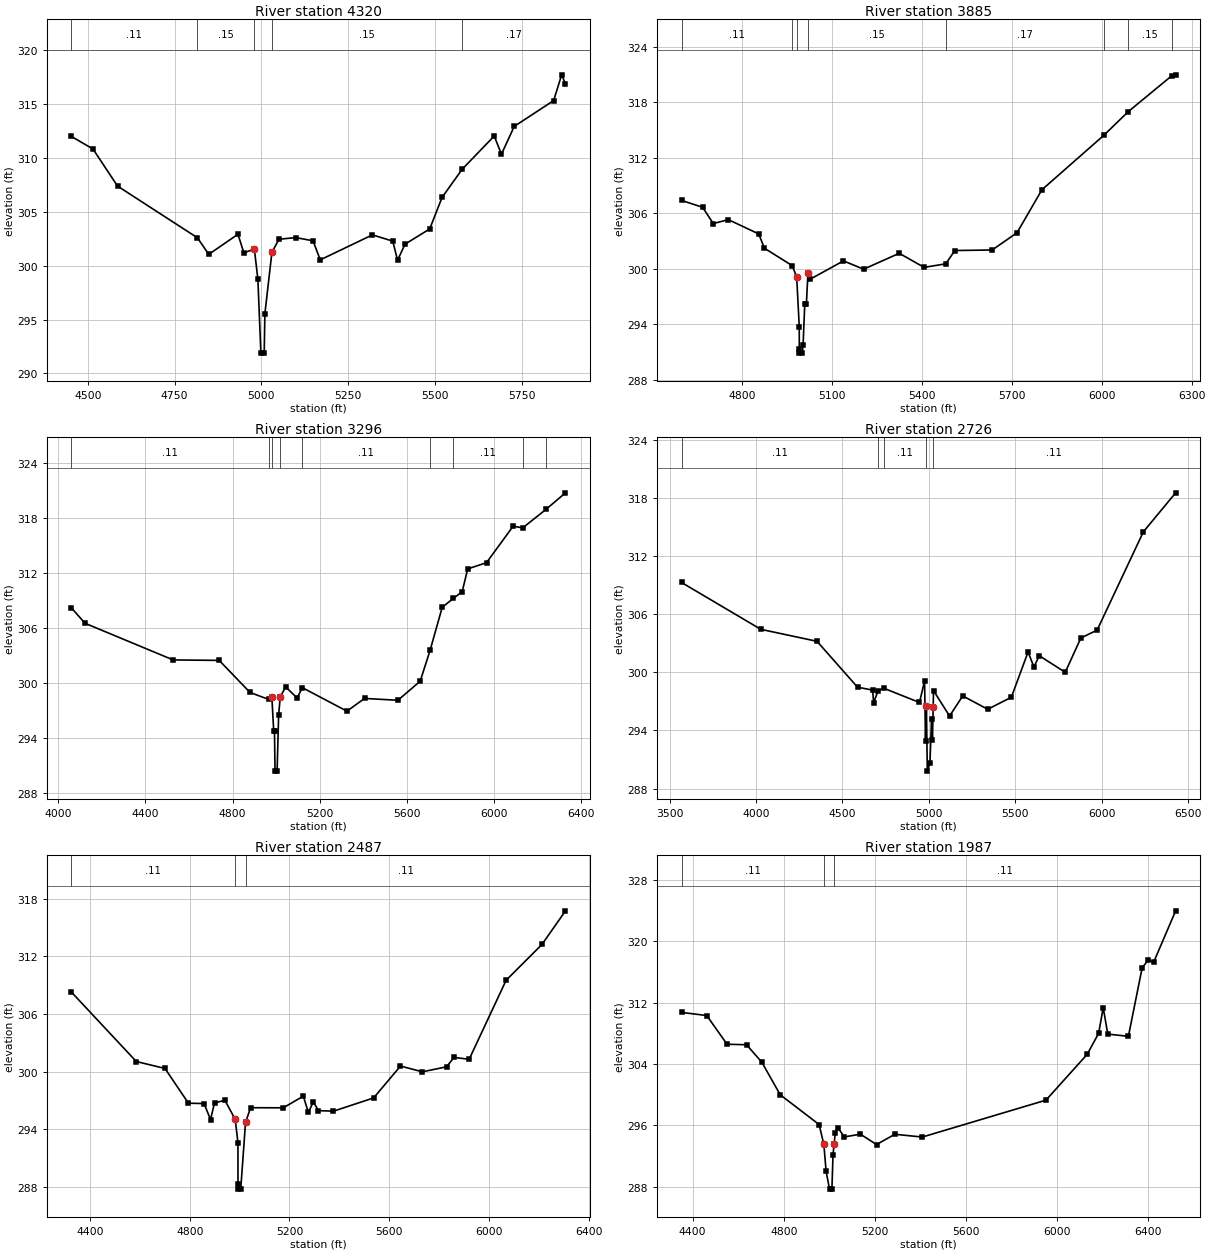
Type RM Length L Ch R = 1 ,4320    ,435,435,435
BEGIN DESCRIPTION:
HAYNIE CREEK 7.0
END DESCRIPTION:
XS GIS Cut Line= 3
      3690935.23     10154632.76      3691023.78     10154012.94
      3690549.83     10153372.32
#Sta/Elev= 30
  4452.8     312  4515.1  310.83  4585.8  307.39  4815.8  302.59  4848.5  301.05
  4932.6  302.92  4949.5  301.19  4979.8  301.54  4989.9  298.73  4998.6  291.88
  5008.1  291.88  5010.1  295.55  5030.3  301.23  5050.5  302.45  5098.6  302.61
  5148.7  302.31  5169.5  300.54  5319.8  302.86  5378.3  302.28  5392.2  300.51
  5413.8     302  5484.8  303.41  5520.2  306.33  5577.9  308.94  5670.5  312.04
  5691.4  310.35  5728.1  312.93  5841.7  315.33  5864.7  317.72  5875.8  316.87
#Mann= 5 ,-1 , 0
  4452.8     .11       0  4815.8     .15       0  4979.8     .09       0
  5030.3     .15       0  5577.9     .17       0
Bank Sta=4979.8,5030.3
XS Rating Curve= 0 ,0
Exp/Cntr=0.3,0.1

Type RM Length L Ch R = 1 ,3885    ,589,589,589
BEGIN DESCRIPTION:
HAYNIE CREEK 6.0
END DESCRIPTION:
XS GIS Cut Line= 4
       3691206.1     10154367.09      3691419.61     10154216.06
      3691367.53     10154075.44      3690799.83      10152976.5
#Sta/Elev= 30
  4598.2  307.38  4668.5  306.64  4704.2  304.88  4754.6   305.3  4855.6  303.76
  4874.8  302.21  4967.3  300.33  4982.4  299.12    4991  293.72  4991.1  291.36
  4991.6  290.86  5001.1  290.86  5003.7  291.71  5009.4   296.2  5014.8   296.2
  5020.1  299.58  5025.9  298.83  5138.4  300.84  5205.9  299.94  5324.5  301.66
  5407.5  300.14  5479.8  300.52  5509.8  301.96  5634.6  302.02  5717.6  303.89
  5800.6  308.54  6007.2  314.43  6088.6  316.99    6233  320.85  6246.6  320.97
#Mann= 8 ,-1 , 0
  4598.2     .11       0  4967.3     .15       0  4982.4     .09       0
  5020.1     .15       0  5479.8     .17       0  6007.2     .11       0
  6088.6     .15       0    6233     .17       0
Bank Sta=4982.4,5020.1
XS Rating Curve= 0 ,0
Exp/Cntr=0.3,0.1

Type RM Length L Ch R = 1 ,3296    ,570,570,570
BEGIN DESCRIPTION:
HAYNIE CREEK 5.0
END DESCRIPTION:
XS GIS Cut Line= 4
      3691226.88     10154387.96      3691841.49      10153986.9
       3691846.7     10153788.98      3691388.79     10152534.94
#Sta/Elev= 30
    4060  308.16  4122.6  306.48  4526.9  302.48  4738.2  302.43  4879.7  298.93
  4965.5  298.17  4979.8  298.45  4988.3  294.69  4991.9  294.69  4994.2  290.35
  5003.8  290.35  5010.9  296.51 5018.41298.4402  5042.9  299.54  5096.1  298.32
  5119.2  299.46  5324.4  296.89  5404.8  298.28  5558.1  298.08  5660.3  300.16
  5706.4  303.59  5761.3  308.22  5812.6   309.2  5852.9  309.92  5878.2  312.41
  5964.5  313.09  6086.7  317.07    6131  316.89  6237.2   318.9  6326.9  320.71
#Mann= 9 ,-1 , 0
    4060     .11       0  4965.5     .15       0  4979.8     .09       0
 5018.41     .15       0  5119.2     .11       0  5706.4     .17       0
  5812.6     .11       0    6131     .17       0  6237.2     .11       0
Bank Sta=4979.8,5018.41
XS Rating Curve= 0 ,0
Exp/Cntr=0.3,0.1

Type RM Length L Ch R = 1 ,2726    ,239,239,239
BEGIN DESCRIPTION:
Mapping XS b0fcb6ca
END DESCRIPTION:
XS GIS Cut Line= 6
      3691216.51      10154434.8      3691867.53     10154012.94
       3692034.2     10153809.81      3692153.99     10153622.31
      3692305.03     10152971.27      3692398.68     10152045.15
#Sta/Elev= 30
  3568.4  309.29  4027.3  304.45  4352.8  303.21  4587.4  298.47  4674.7  298.17
  4680.6  296.87  4705.9  298.09  4738.3  298.37  4945.8  296.89  4975.5  299.12
  4980.8  292.87    4986  296.52  4991.3   289.8  5006.6  290.68  5015.9  295.19
    5021  293.04 5025.19296.4187  5027.3  298.12    5120  295.49  5196.4  297.57
  5340.8  296.19  5477.7  297.43  5574.6  302.11  5608.7  300.55  5638.9  301.73
  5789.6  300.01  5880.1  303.55  5974.4  304.37  6241.9  314.52  6428.8  318.55
#Mann= 5 ,-1 , 0
  3568.4     .11       0  4705.9     .15       0  4738.3     .11       0
    4986     .06       0 5025.19     .11       0
Bank Sta=4986,5025.19
XS Rating Curve= 0 ,0
Exp/Cntr=0.3,0.1

Type RM Length L Ch R = 1 ,2487    ,500,500,500
BEGIN DESCRIPTION:
HAYNIE CREEK 3.0
END DESCRIPTION:
XS GIS Cut Line= 3
      3692221.69     10154070.25      3692416.57     10153424.72
      3692570.65     10152127.54
#Sta/Elev= 30
  4325.7  308.28    4586  301.06  4700.9  300.34  4794.9  296.73  4857.6  296.69
  4883.5  295.03  4899.4  296.76  4941.1  297.03  4982.4  295.05  4993.4  292.63
  4993.5   288.3    4994   287.8  5004.5   287.8  5023.8  294.73    5044  296.26
  5174.9  296.25  5255.4  297.46  5275.6  295.78  5295.7  296.87  5315.9  295.96
  5376.3   295.9  5537.4  297.28  5644.9  300.59  5732.6  299.99  5829.4  300.51
  5859.7  301.49  5920.1  301.29  6068.4  309.51  6212.1  313.23  6306.3  316.72
#Mann= 3 ,-1 , 0
  4325.7     .11       0  4982.4     .07       0  5023.8     .11       0
Bank Sta=4982.4,5023.8
XS Rating Curve= 0 ,0
Exp/Cntr=0.3,0.1

Type RM Length L Ch R = 1 ,1987    ,527,527,527
BEGIN DESCRIPTION:
HAYNIE CREEK 2.0
END DESCRIPTION:
XS GIS Cut Line= 3
      3692767.85      10154061.1       3692847.8     10153417.34
      3692690.57     10151904.79
#Sta/Elev= 30
  4351.3  310.73  4462.2  310.32    4551  306.58  4636.9  306.51    4704  304.23
  4784.6  299.99  4955.4  296.11  4976.1  293.53  4986.2     290  5001.1  287.69
  5011.6  287.69  5016.4  292.14 5021.34293.5874  5026.4  295.07  5036.5  295.72
  5066.6   294.5    5137  294.85  5207.4   293.5  5287.8  294.84  5408.5  294.48
  5951.4  299.29  6132.3  305.26  6182.6     308  6202.7  311.35  6222.8   307.9
  6313.3  307.61  6373.6  316.53  6400.4  317.58  6423.9  317.25  6520.7  323.97
#Mann= 3 , 0 , 0
  4351.3     .11       0  4976.1     .06       0 5021.34     .11       0
Bank Sta=4976.1,5021.34
XS Rating Curve= 0 ,0
Exp/Cntr=0.3,0.1

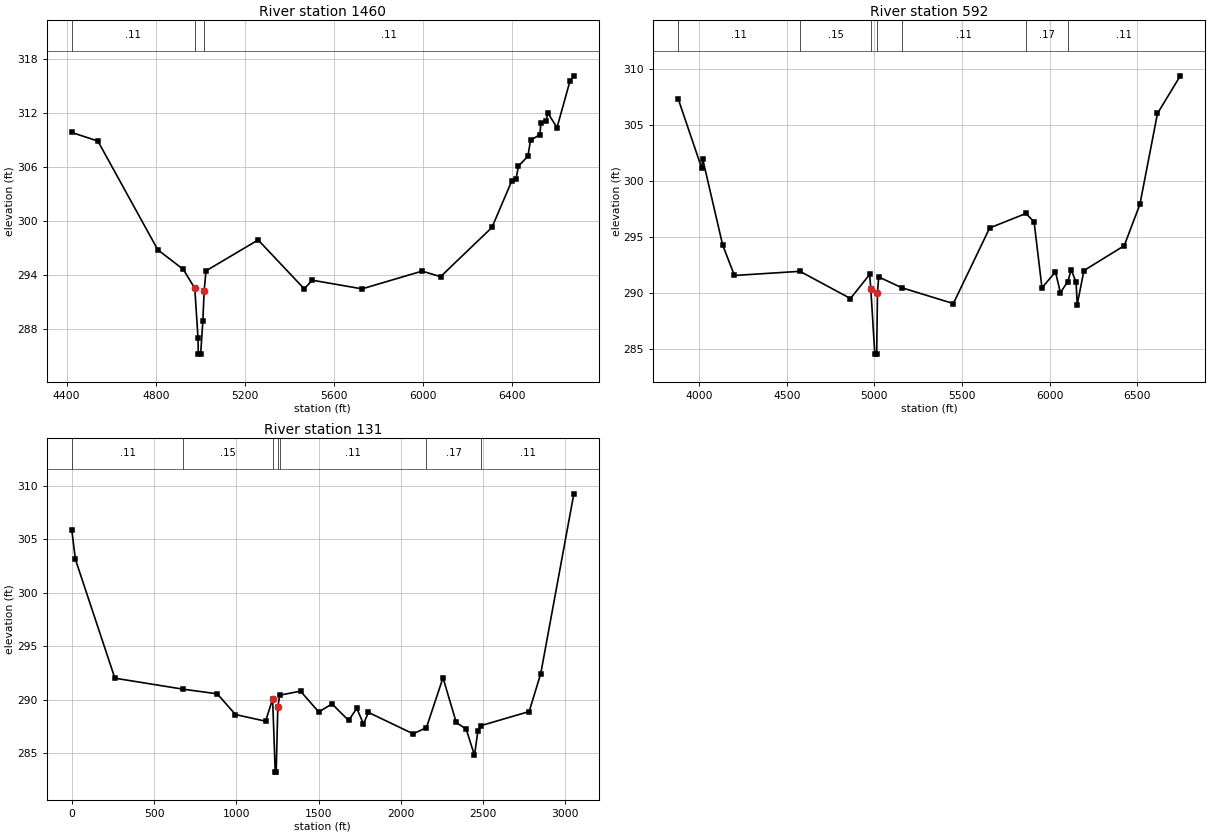
Type RM Length L Ch R = 1 ,1460    ,868,868,868
BEGIN DESCRIPTION:
Mapping XS 26179622
END DESCRIPTION:
XS GIS Cut Line= 3
      3692940.47     10153856.65      3693383.15      10153174.4
      3692836.29     10151841.08
#Sta/Elev= 30
  4423.2  309.84  4540.5  308.88  4809.4  296.81  4924.1  294.63  4975.5  292.53
  4990.1  287.02  4991.3  285.22  5001.9  285.22  5011.7  288.87  5017.7  292.27
  5025.9  294.47    5260   297.9  5467.1  292.47  5502.9  293.43  5726.5  292.47
  5996.4  294.44  6079.2  293.82  6310.1   299.3  6399.4  304.49    6418  304.69
    6429   306.1  6471.3   307.2  6483.1  308.97  6524.7  309.59  6530.1  310.91
  6554.1  311.06  6559.5  312.05    6602  310.38  6660.9  315.61  6677.6  316.13
#Mann= 3 , 0 , 0
  4423.2     .11       0  4975.5     .06       0  5017.7     .11       0
Bank Sta=4975.5,5017.7
XS Rating Curve= 0 ,0
Exp/Cntr=0.3,0.1

Type RM Length L Ch R = 1 ,592     ,461,461,461
BEGIN DESCRIPTION:
HAYNIE CREEK 1.0
END DESCRIPTION:
XS GIS Cut Line= 3
      3693117.89     10153761.06      3694065.45      10153429.6
      3693238.09     10151764.48
#Sta/Elev= 30
  3881.3  307.29  4015.6  301.11  4020.9  301.94  4134.5   294.3  4201.8  291.58
  4575.5  291.95  4863.4  289.53  4972.9  291.67  4979.7  290.34  5002.3  284.58
  5012.9  284.58  5017.5  290.02  5024.5  291.45  5155.9  290.49  5450.1  289.08
  5657.3  295.81  5864.4   297.1  5910.8  296.34  5955.5  290.48  6032.6   291.9
  6060.6  290.05  6102.8  291.04  6122.2  292.08  6150.2  290.98  6156.5  288.99
    6195  292.02  6424.6  294.23  6514.2  297.92  6614.3     306  6744.5  309.35
#Mann= 7 ,-1 , 0
  3881.3     .11       0  4575.5     .15       0  4979.7     .06       0
  5017.5     .15       0  5155.9     .11       0  5864.4     .17       0
  6102.8     .11       0
Bank Sta=4979.7,5017.5
XS Rating Curve= 0 ,0
Exp/Cntr=0.3,0.1

Type RM Length L Ch R = 1 ,131     ,0,0,0
BEGIN DESCRIPTION:
HAYNIE CREEK 1.0
END DESCRIPTION:
XS GIS Cut Line= 4
      3693162.34     10153783.92      3694226.14     10153387.94
      3694361.77     10153308.73      3694153.22     10151561.34
#Sta/Elev= 30
       0  305.88    22.2  303.13     262  292.03   677.3     291   884.3  290.57
     995  288.63  1178.1  288.01    1221  290.08  1236.7  283.28  1242.5  283.25
  1252.5  289.36  1264.5  290.44  1390.5  290.82  1501.3  288.87  1581.9  289.63
  1682.6  288.08  1732.9  289.21  1773.2  287.75  1803.4  288.83  2075.4  286.83
  2155.9  287.41  2256.6  292.07  2337.2  287.89  2397.6  287.27    2448  284.82
  2468.8  287.11  2488.3   287.6  2780.3  288.91  2850.8  292.46    3052  309.26
#Mann= 7 ,-1 , 0
       0     .11       0   677.3     .15       0    1221     .06       0
  1252.5     .15       0  1264.5     .11       0  2155.9     .17       0
  2488.3     .11       0
Bank Sta=1221,1252.5
XS Rating Curve= 0 ,0
Exp/Cntr=0.3,0.1

Chan Stop Cuts=-1
Use User Specified Reach Order=0
Composite Channel Slope=5