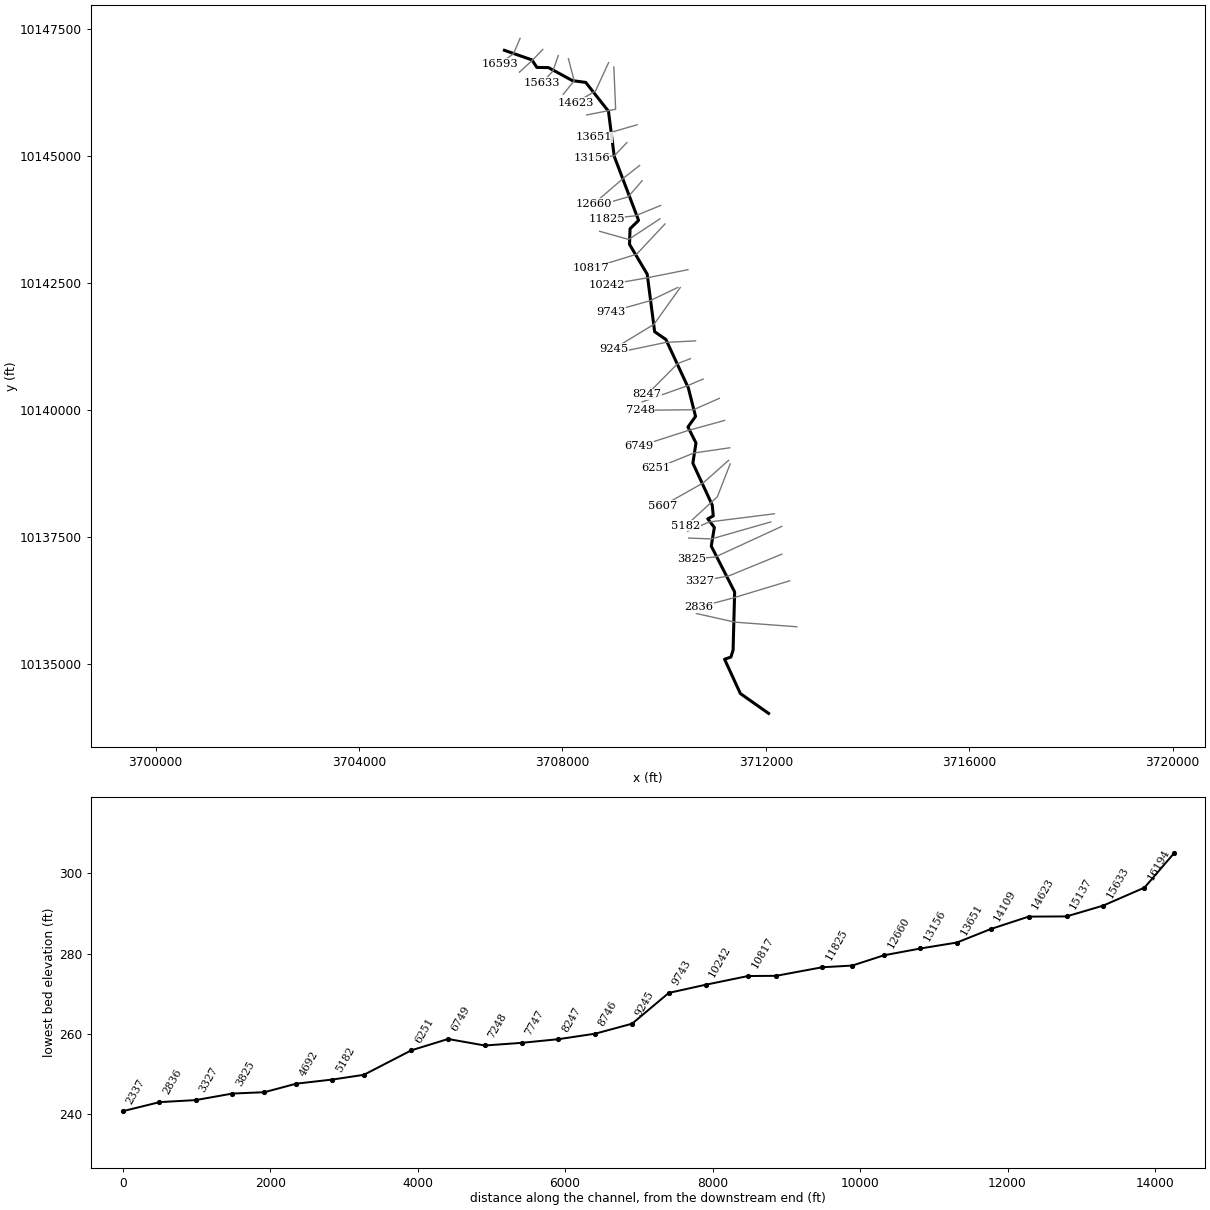
--- JOHNS CREEK.prj (project) ---

Proj Title=JOHNS CREEK Base Level Engineering
Current Plan=p01
Default Exp/Contr=0.3,0.1
English Units
Geom File=g01
Flow File=f01
Flow File=f02
Plan File=p01
Y Axis Title=Elevation
X Axis Title(PF)=Main Channel Distance
X Axis Title(XS)=Station
BEGIN DESCRIPTION:
JOHNS CREEK
END DESCRIPTION:
DSS Export Rating Curves= 0
DSS Export Rating Curve Sorted= 0
DSS Export Volume Flow Curves= 0
DXF OffsetX= 0
DXF OffsetY= 0
DXF ScaleX= 1
DXF ScaleY= 10

--- JOHNS CREEK.p01 (plan) ---

Plan Title=Multiple Run
Short Identifier=Multiple
Geom File=g01
Flow File=f01
Subcritical Flow
K Sum by GR= 0
Std Step Tol= 0.01
Critical Tol= 0.01
Num of Std Step Trials= 20
Max Error Tol= 0.3
Flow Tol Ratio= 0.001
Split Flow NTrial= 30
Split Flow Tol= 0.02
Split Flow Ratio= 0.02
Log Output Level= 0
Friction Slope Method= 1
Unsteady Friction Slope Method= 2
Unsteady Bridges Friction Slope Method= 1
Parabolic Critical Depth
Global Vel Dist=  1 , 1 , 1
Global Log Level= 0
CheckData=True
Encroach Param= -1, 0, 0, 0
BEGIN DESCRIPTION:
Multiple Run
END DESCRIPTION:

--- JOHNS CREEK.f01 (steady flow) ---

Flow Title=Multiple
Program Version=4.10
Number of Profiles= 7
Profile Names=10-year,25-year,50-year,1pct_min,100-year,1pct_plu,500-year
River Rch & RM=JOHNS CREEK,Reach-1         ,16593
     878    1218    1672     755    2279    6882    4379
River Rch & RM=JOHNS CREEK,Reach-1         ,10242
    1084    1514    2087     945    2854    8619    5521
River Rch & RM=JOHNS CREEK,Reach-1         ,4692
    1051    1447    1977     885    2673    8072    5059
Boundary for River Rch & Prof#=JOHNS CREEK,Reach-1         , 1
Up Type= 0
Dn Type= 3
Dn Slope=0.005
Boundary for River Rch & Prof#=JOHNS CREEK,Reach-1         , 2
Up Type= 0
Dn Type= 3
Dn Slope=0.005
Boundary for River Rch & Prof#=JOHNS CREEK,Reach-1         , 3
Up Type= 0
Dn Type= 3
Dn Slope=0.005
Boundary for River Rch & Prof#=JOHNS CREEK,Reach-1         , 4
Up Type= 0
Dn Type= 3
Dn Slope=0.005
Boundary for River Rch & Prof#=JOHNS CREEK,Reach-1         , 5
Up Type= 0
Dn Type= 3
Dn Slope=0.005
Boundary for River Rch & Prof#=JOHNS CREEK,Reach-1         , 6
Up Type= 0
Dn Type= 3
Dn Slope=0.005
Boundary for River Rch & Prof#=JOHNS CREEK,Reach-1         , 7
Up Type= 0
Dn Type= 3
Dn Slope=0.005
DSS Import GetInterval= 0
DSS Import GetPeak= 0
DSS Import FillOption= 0

--- JOHNS CREEK.f02 (steady flow) ---

Flow Title=Orig_BLE_Flows
Program Version=4.10
Number of Profiles= 7
Profile Names=10-year,25-year,50-year,1pct_min,100-year,1pct_plu,500-year
River Rch & RM=JOHNS CREEK,Reach-1         ,16593
     878    1194    1454     580    1753    5293    2546
River Rch & RM=JOHNS CREEK,Reach-1         ,10242
    1084    1484    1815     727    2195    6630    3210
River Rch & RM=JOHNS CREEK,Reach-1         ,4692
    1051    1419    1719     681    2056    6209    2941
Boundary for River Rch & Prof#=JOHNS CREEK,Reach-1         , 1
Up Type= 0
Dn Type= 3
Dn Slope=0.005
Boundary for River Rch & Prof#=JOHNS CREEK,Reach-1         , 2
Up Type= 0
Dn Type= 3
Dn Slope=0.005
Boundary for River Rch & Prof#=JOHNS CREEK,Reach-1         , 3
Up Type= 0
Dn Type= 3
Dn Slope=0.005
Boundary for River Rch & Prof#=JOHNS CREEK,Reach-1         , 4
Up Type= 0
Dn Type= 3
Dn Slope=0.005
Boundary for River Rch & Prof#=JOHNS CREEK,Reach-1         , 5
Up Type= 0
Dn Type= 3
Dn Slope=0.005
Boundary for River Rch & Prof#=JOHNS CREEK,Reach-1         , 6
Up Type= 0
Dn Type= 3
Dn Slope=0.005
Boundary for River Rch & Prof#=JOHNS CREEK,Reach-1         , 7
Up Type= 0
Dn Type= 3
Dn Slope=0.005
DSS Import GetInterval= 0
DSS Import GetPeak= 0
DSS Import FillOption= 0

--- JOHNS CREEK.g01 (geometry) ---

Geom Title=Existing Conditions
Program Version=4.10

River Reach=JOHNS CREEK     ,Reach-1
Reach XY= 30
      3706859.88     10147075.37      3707400.97     10146886.96
      3707497.08     10146739.18      3707725.91     10146735.54
      3708198.09     10146478.89      3708458.26     10146444.73
      3708905.57     10145877.59      3709019.01     10144991.02
      3709498.01     10143730.62      3709330.03     10143566.07
      3709319.54     10143259.39      3709667.33     10142673.59
      3709813.63     10141541.67      3710035.34     10141388.46
      3710476.61     10140435.24      3710618.27     10139875.77
      3710468.78     10139667.55      3710626.61     10139353.48
      3710565.42     10138955.71      3710947.99     10138128.72
      3710966.39     10137918.14      3710858.64     10137861.29
      3710987.74     10137692.02       3710927.2     10137324.83
      3711387.12      10136423.4      3711356.64     10135279.18
      3711313.73     10135143.23      3711189.07     10135100.42
      3711499.45     10134425.65      3712054.25      10134035.6

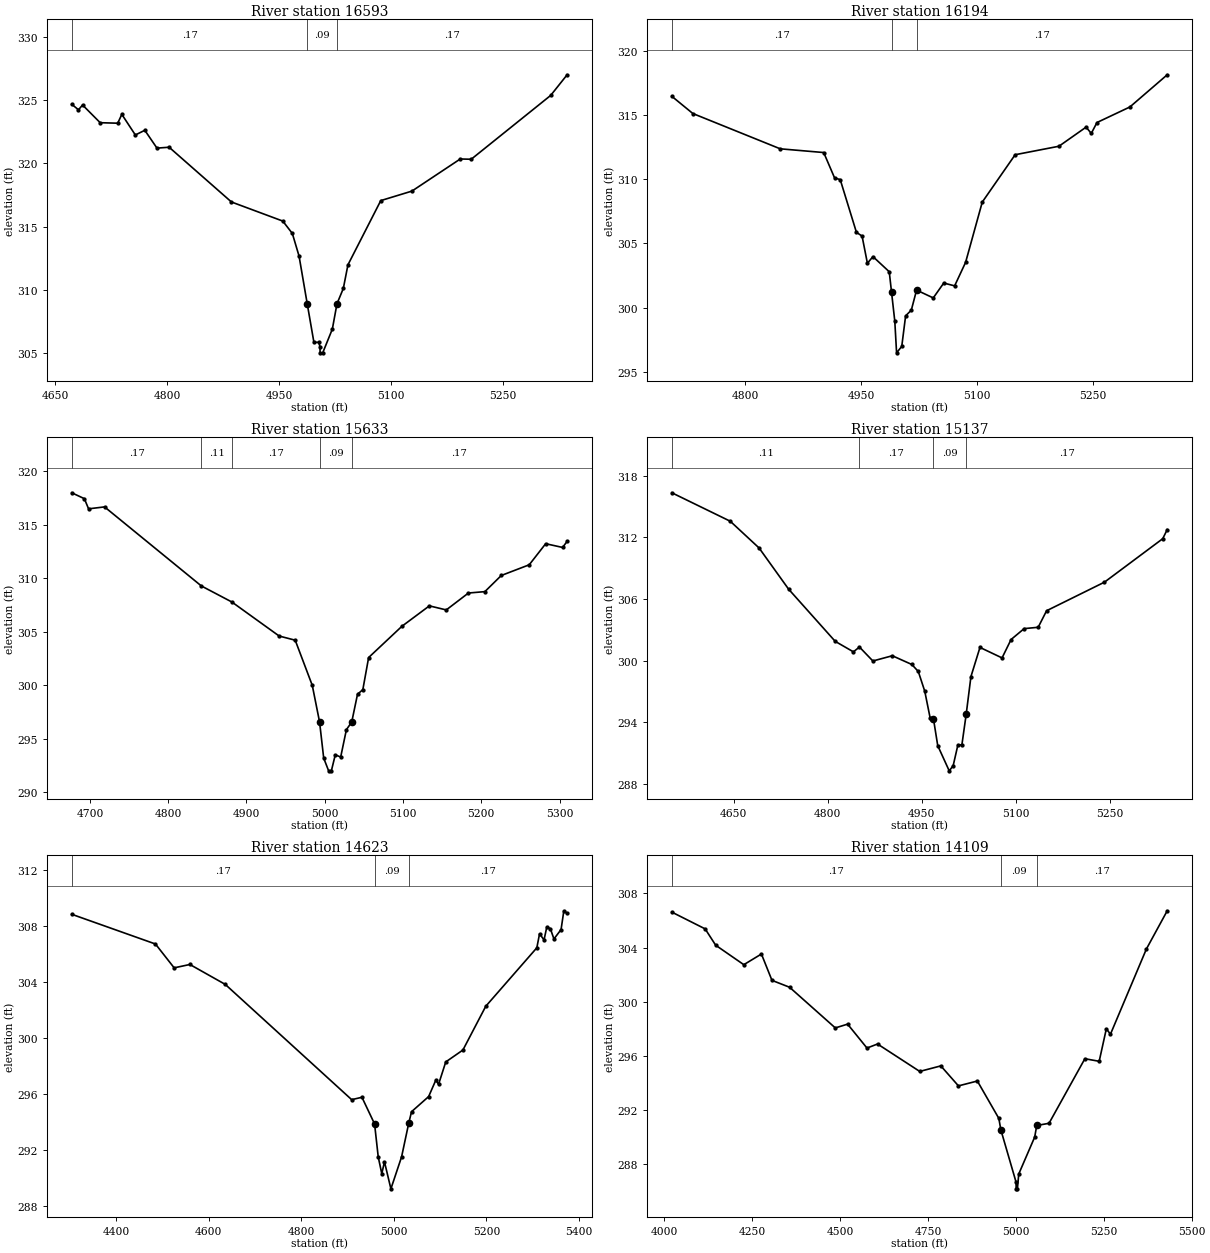
Type RM Length L Ch R = 1 ,16593   ,399,399,399
BEGIN DESCRIPTION:
JOHNS CREEK 32.0
END DESCRIPTION:
XS GIS Cut Line= 3
      3707167.84     10147311.04      3707038.63     10147009.35
      3706767.86     10146811.08
#Sta/Elev= 30
  4671.8  324.67  4680.8  324.23  4686.3  324.61  4709.9  323.21  4733.4  323.17
  4738.9  323.87    4757  322.24  4769.7  322.61    4786   321.2  4802.3  321.27
  4885.8  316.94  4954.6  315.43  4967.4  314.45  4976.4  312.66 4987.44308.8557
  4996.3  305.84  5002.8  305.84  5004.4  305.51  5004.6  305.01  5008.1  305.01
    5021  306.89  5027.2  308.89  5035.7   310.1  5041.9  311.97  5085.9  317.05
  5127.6   317.8  5192.4  320.34  5207.1  320.32  5313.6  325.37  5335.6     327
#Mann= 3 , 0 , 0
  4671.8     .17       0 4987.44     .09       0  5027.2     .17       0
Bank Sta=4987.44,5027.2
XS Rating Curve= 0 ,0
Exp/Cntr=0.3,0.1

Type RM Length L Ch R = 1 ,16194   ,561,561,561
BEGIN DESCRIPTION:
JOHNS CREEK 31.0
END DESCRIPTION:
XS GIS Cut Line= 3
      3707614.29     10147092.92      3707410.29     10146880.24
      3707154.32     10146645.96
#Sta/Elev= 30
    4705  316.46  4732.2  315.12  4845.4  312.37  4901.7  312.08  4915.8   310.1
  4923.1  309.97  4944.1  305.86  4951.4  305.57  4958.3  303.45  4965.5  303.97
  4986.6  302.79 4989.54301.2138  4993.8  298.93  4996.1  296.47  5002.8  296.97
  5007.8  299.35  5015.2   299.8    5022  301.36  5043.6  300.75  5057.2  301.91
  5071.3  301.69  5085.5  303.52  5107.1  308.22  5149.7  311.91  5206.4  312.57
  5241.6  314.06  5248.3  313.57  5255.7  314.42  5298.3  315.63  5346.7  318.14
#Mann= 3 , 0 , 0
    4705     .17       0 4989.54     .09       0    5022     .17       0
Bank Sta=4989.54,5022
XS Rating Curve= 0 ,0
Exp/Cntr=0.3,0.1

Type RM Length L Ch R = 1 ,15633   ,496,496,496
BEGIN DESCRIPTION:
JOHNS CREEK 30.0
END DESCRIPTION:
XS GIS Cut Line= 3
      3707918.09     10146971.35      3707811.98     10146666.06
      3707602.04     10146438.38
#Sta/Elev= 30
  4676.8  317.97  4692.9  317.42  4698.3  316.47  4718.7  316.65  4842.4  309.26
  4881.4  307.76  4941.8  304.58  4962.3  304.19  4984.1  299.97  4993.4  296.56
  4998.7  293.17    5005  291.98  5008.5  291.98  5013.5  293.48  5020.4  293.27
  5027.7  295.83  5034.5  296.54  5041.9  299.14  5048.7  299.57  5056.1  302.57
  5098.6  305.49  5133.7   307.4  5155.3  307.02  5183.6   308.6  5204.6  308.73
  5225.6  310.24  5261.3  311.24  5282.3  313.21  5303.9  312.86  5309.7  313.43
#Mann= 5 ,-1 , 0
  4676.8     .17       0  4842.4     .11       0  4881.4     .17       0
  4993.4     .09       0  5034.5     .17       0
Bank Sta=4993.4,5034.5
XS Rating Curve= 0 ,0
Exp/Cntr=0.3,0.1

Type RM Length L Ch R = 1 ,15137   ,514,514,514
BEGIN DESCRIPTION:
JOHNS CREEK 29.0
END DESCRIPTION:
XS GIS Cut Line= 3
      3708117.84      10146911.1      3708231.22     10146477.27
      3708017.82     10146211.04
#Sta/Elev= 30
  4551.6  316.35  4644.7  313.58  4690.6  310.98  4737.7  306.97    4812  301.89
    4841  300.87  4850.6  301.34    4872  299.98    4903  300.49  4934.1  299.64
  4944.4  298.96  4954.7  297.04  4963.4   294.4  4968.6  294.34  4975.4  291.74
  4993.7  289.29    5000  289.79  5007.5  291.81  5013.9  291.82  5020.8  294.82
  5028.3  298.46  5042.7   301.3  5077.9  300.28  5092.3  302.07  5113.1  303.13
  5135.5  303.26  5148.9  304.87  5241.1  307.65    5334  311.88  5341.2  312.77
#Mann= 4 ,-1 , 0
  4551.6     .11       0  4850.6     .17       0  4968.6     .09       0
  5020.8     .17       0
Bank Sta=4968.6,5020.8
XS Rating Curve= 0 ,0
Exp/Cntr=0.3,0.1

Type RM Length L Ch R = 1 ,14623   ,514,514,514
BEGIN DESCRIPTION:
JOHNS CREEK 28.0
END DESCRIPTION:
XS GIS Cut Line= 3
      3708907.67     10146832.47      3708651.61     10146276.94
      3708256.62     10146042.55
#Sta/Elev= 30
  4303.6  308.82  4484.6   306.7    4525     305    4559  305.24  4635.5  303.82
  4908.8   295.6    4931  295.77  4958.3  293.87  4966.2  291.52  4973.9  290.32
  4979.7  291.17  4993.6  289.24  5016.7  291.52  5032.4  293.96  5038.2  294.74
  5075.2  295.82  5090.8     297  5096.6  296.69  5112.2  298.29  5149.3  299.14
  5198.7  302.26  5309.1  306.43    5315  307.43  5324.7  306.99  5330.5  307.89
  5338.3   307.8  5346.1  307.06  5361.5  307.73  5367.5  309.07  5374.6  308.88
#Mann= 3 , 0 , 0
  4303.6     .17       0  4958.3     .09       0  5032.4     .17       0
Bank Sta=4958.3,5032.4
XS Rating Curve= 0 ,0
Exp/Cntr=0.3,0.1

Type RM Length L Ch R = 1 ,14109   ,458,458,458
BEGIN DESCRIPTION:
JOHNS CREEK 27.0
END DESCRIPTION:
XS GIS Cut Line= 3
      3709011.85     10146745.64      3709046.69     10145916.89
        3708478.     10145803.85
#Sta/Elev= 30
  4021.2  306.62  4115.9  305.38  4145.9  304.17  4225.9  302.73    4276  303.52
    4306  301.57  4356.1  301.06  4486.2  298.05  4521.2  298.33  4576.3  296.56
  4606.3  296.86  4726.4  294.83  4786.4  295.24  4836.5  293.76  4890.3  294.12
  4951.5  291.35    4957  290.52  5000.4  286.64  5000.7  286.14  5004.2  286.14
  5008.1  287.24  5053.4  289.97  5059.3  290.83  5094.2  290.99  5196.2  295.77
  5236.9  295.58  5257.3  297.99  5268.9  297.58  5371.2  303.89  5430.5  306.72
#Mann= 3 , 0 , 0
  4021.2     .17       0    4957     .09       0  5059.3     .17       0
Bank Sta=4957,5059.3
XS Rating Curve= 0 ,0
Exp/Cntr=0.3,0.1

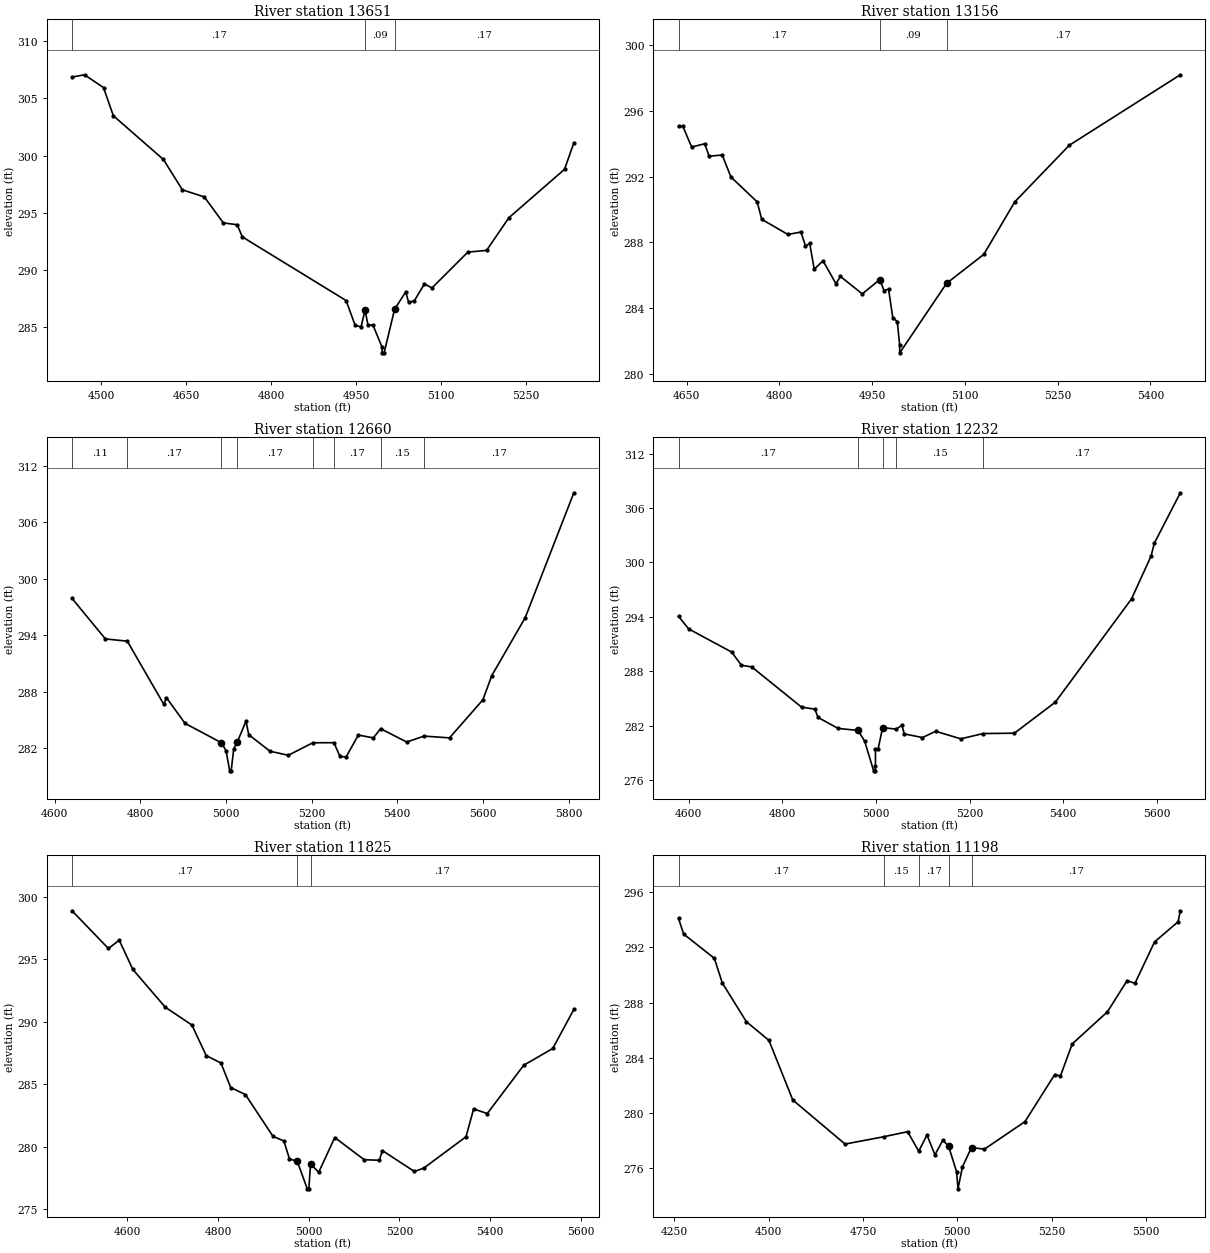
Type RM Length L Ch R = 1 ,13651   ,495,495,495
BEGIN DESCRIPTION:
JOHNS CREEK 26.0
END DESCRIPTION:
XS GIS Cut Line= 3
      3709467.87     10145611.08      3708938.03     10145456.95
      3708617.87     10145361.08
#Sta/Elev= 30
  4448.2  306.87  4470.2  307.07  4503.7  305.95  4521.1  303.49  4609.5  299.67
    4643  297.02  4681.7   296.4  4715.3  294.13  4739.8  293.97  4748.8  292.91
    4932  287.35  4948.1  285.18  4958.5  285.05  4965.5  286.52  4970.7  285.19
  4979.4  285.21  4995.5  283.28  4995.7  282.78  4999.2  282.78 5017.67286.5905
  5037.3   288.1  5042.5  287.19  5052.4  287.32  5070.4   288.8  5083.7  288.45
    5147  291.58  5180.1  291.73  5219.4  294.58  5317.7  298.81  5334.2  301.13
#Mann= 3 , 0 , 0
  4448.2     .17       0  4965.5     .09       0 5017.67     .17       0
Bank Sta=4965.5,5017.67
XS Rating Curve= 0 ,0
Exp/Cntr=0.3,0.1

Type RM Length L Ch R = 1 ,13156   ,496,496,496
BEGIN DESCRIPTION:
JOHNS CREEK 25.0
END DESCRIPTION:
XS GIS Cut Line= 3
      3709267.84     10145261.06      3709018.11     10144997.75
      3708571.04     10144961.99
#Sta/Elev= 30
  4637.1  295.06  4644.2  295.04  4658.3  293.79  4679.4  293.99  4686.6  293.23
  4707.7  293.31  4721.8  291.97  4764.3  290.46  4771.6   289.4    4814  288.48
  4835.1  288.63  4842.4  287.77  4849.2  287.94  4856.5  286.37  4870.7  286.88
  4891.7  285.49  4898.9  285.93  4934.2  284.87  4962.5  285.74  4969.4  285.07
  4976.7  285.16  4983.6  283.42  4990.8  283.19  4994.6  281.79  4994.8  281.29
  5070.5  285.51  5130.7  287.27  5180.8  290.46    5269   293.9  5448.5  298.18
#Mann= 3 , 0 , 0
  4637.1     .17       0  4962.5     .09       0  5070.5     .17       0
Bank Sta=4962.5,5070.5
XS Rating Curve= 0 ,0
Exp/Cntr=0.3,0.1

Type RM Length L Ch R = 1 ,12660   ,428,428,428
BEGIN DESCRIPTION:
JOHNS CREEK 24.0
END DESCRIPTION:
XS GIS Cut Line= 3
      3709517.86     10144811.08      3709235.22     10144588.91
      3708617.82     10144061.04
#Sta/Elev= 30
  4640.5   297.9  4718.3   293.6  4769.5  293.36  4854.7  286.65    4861  287.35
  4904.4  284.63  4989.4  282.57    5000  281.74  5008.6  279.59  5012.1  279.59
    5018  281.92 5026.53282.6661  5046.6  284.87  5053.1  283.43  5102.5  281.68
  5145.4  281.24  5202.5  282.57  5252.1  282.58  5266.1  281.12  5280.4  281.06
  5308.9  283.39  5344.1  283.09  5360.9  284.07    5422  282.65  5462.6  283.28
  5521.9  283.09  5599.8  287.13  5620.7  289.71  5698.6  295.85  5812.3  309.12
#Mann= 8 ,-1 , 0
  4640.5     .11       0  4769.5     .17       0  4989.4     .09       0
 5026.53     .17       0  5202.5     .15       0  5252.1     .17       0
  5360.9     .15       0  5462.6     .17       0
Bank Sta=4989.4,5026.53
XS Rating Curve= 0 ,0
Exp/Cntr=0.3,0.1

Type RM Length L Ch R = 1 ,12232   ,407,407,407
BEGIN DESCRIPTION:
JOHNS CREEK 23.0
END DESCRIPTION:
XS GIS Cut Line= 3
      3709567.84     10144511.06      3709291.65     10144192.93
      3708667.82     10144011.06
#Sta/Elev= 30
  4578.7  294.07  4600.1  292.68  4692.2  290.12    4713  288.66  4734.9  288.49
  4841.3  284.05  4869.8  283.83  4876.4  282.92  4919.1  281.71  4961.9  281.48
    4976   280.3  4995.2  277.03  4998.7  277.03    4999  277.53  4999.1  279.42
  5004.6  279.42  5014.4   281.8  5042.9  281.63  5055.5  282.04  5060.7   281.1
  5099.4   280.7  5127.7  281.39    5181  280.56  5229.1  281.14  5295.6  281.18
    5383   284.6  5545.6  295.98  5587.3   300.7  5594.3  302.12  5649.8  307.68
#Mann= 5 ,-1 , 0
  4578.7     .17       0  4961.9     .09       0  5014.4     .17       0
  5042.9     .15       0  5229.1     .17       0
Bank Sta=4961.9,5014.4
XS Rating Curve= 0 ,0
Exp/Cntr=0.3,0.1

Type RM Length L Ch R = 1 ,11825   ,627,627,627
BEGIN DESCRIPTION:
JOHNS CREEK 22.0
END DESCRIPTION:
XS GIS Cut Line= 3
      3709931.95     10144024.32      3709432.86     10143820.34
      3708867.82     10143761.07
#Sta/Elev= 30
  4477.7  298.88  4557.8  295.86  4581.8  296.52  4611.8  294.18  4683.3  291.16
  4742.1  289.73  4773.8  287.28  4806.2  286.69  4827.8  284.72  4860.2  284.16
    4921  280.82  4945.1  280.44  4957.5     279  4974.5  278.83  4996.7  276.61
  5000.2  276.61  5003.9  278.62  5021.9  277.93  5057.4  280.72  5122.4  278.94
  5155.6   278.9  5162.7  279.67    5233     278  5253.8  278.27    5347  280.78
  5363.8  283.01  5393.9  282.64  5474.4  286.51  5538.4  287.85    5585  290.98
#Mann= 3 , 0 , 0
  4477.7     .17       0  4974.5     .09       0  5003.9     .17       0
Bank Sta=4974.5,5003.9
XS Rating Curve= 0 ,0
Exp/Cntr=0.3,0.1

Type RM Length L Ch R = 1 ,11198   ,381,381,381
BEGIN DESCRIPTION:
JOHNS CREEK 21.0
END DESCRIPTION:
XS GIS Cut Line= 3
      3709917.82     10143761.05      3709302.65     10143355.93
      3708732.12     10143515.85
#Sta/Elev= 30
  4261.5   294.1    4275  292.97  4356.4  291.21  4377.4  289.42  4441.1  286.61
  4500.9  285.25  4564.1  280.92  4702.7  277.72  4804.5  278.25  4868.3  278.62
  4897.7   277.2  4919.6  278.38  4940.6  276.94  4961.7     278  4976.8  277.56
    4998  275.71  5001.7  274.47  5013.5  276.07  5037.5  277.47  5071.6  277.35
  5179.1  279.35  5257.7  282.76  5273.1  282.67  5304.2  284.99  5397.7  287.33
  5449.6  289.59  5470.4  289.39  5522.4   292.4  5584.6  293.86  5590.6  294.66
#Mann= 5 ,-1 , 0
  4261.5     .17       0  4804.5     .15       0  4897.7     .17       0
  4976.8     .09       0  5037.5     .17       0
Bank Sta=4976.8,5037.5
XS Rating Curve= 0 ,0
Exp/Cntr=0.3,0.1

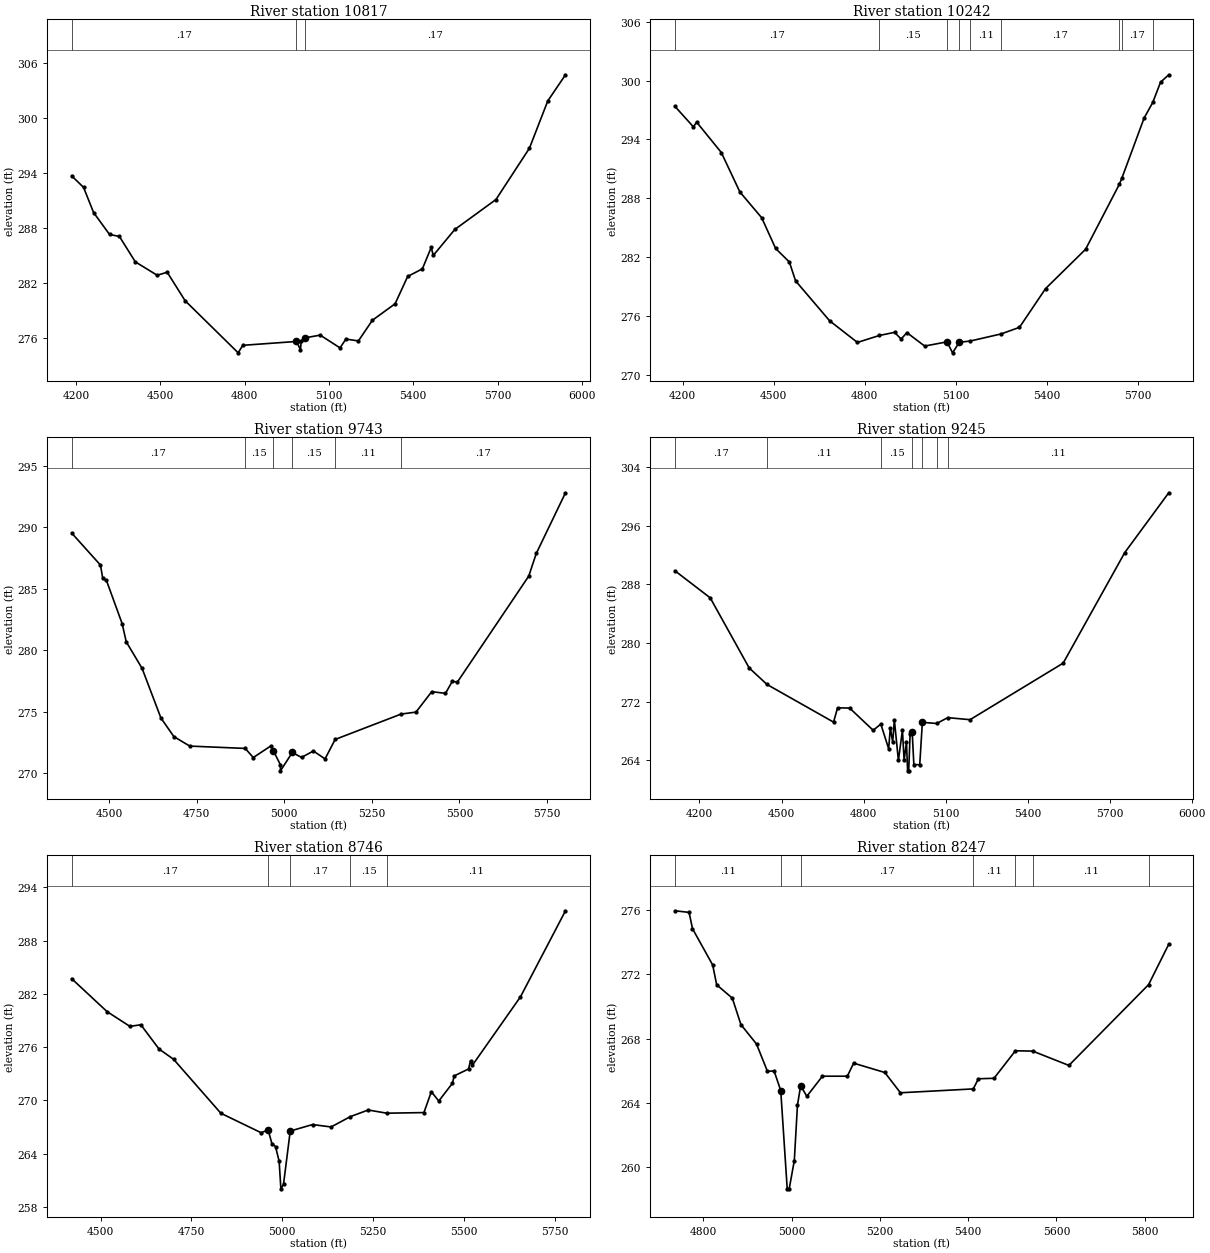
Type RM Length L Ch R = 1 ,10817   ,575,575,575
BEGIN DESCRIPTION:
JOHNS CREEK 20.0
END DESCRIPTION:
XS GIS Cut Line= 3
      3710017.88      10143661.1       3709458.9     10143065.13
      3708561.69     10142787.74
#Sta/Elev= 30
  4185.2  293.72  4227.5  292.46  4263.1  289.72  4319.8  287.33    4355  287.11
  4411.6  284.34  4489.3  282.88  4524.9  283.21  4588.5  280.11  4777.4  274.42
  4793.6  275.24  4984.6  275.66  4998.8  274.77  5001.6  275.73  5013.8  276.05
  5069.1  276.35  5139.6  274.96  5160.4  275.92  5204.9  275.72  5254.6  277.97
  5335.4  279.77  5380.2  282.75  5432.5  283.58  5463.9  285.92  5471.1  285.04
  5547.7  287.87  5694.2  291.14  5813.1  296.73  5878.4  301.89  5941.4  304.74
#Mann= 3 , 0 , 0
  4185.2     .17       0  4984.6     .09       0  5013.8     .17       0
Bank Sta=4984.6,5013.8
XS Rating Curve= 0 ,0
Exp/Cntr=0.3,0.1

Type RM Length L Ch R = 1 ,10242   ,499,499,499
BEGIN DESCRIPTION:
JOHNS CREEK 19.0
END DESCRIPTION:
XS GIS Cut Line= 3
      3710467.89     10142761.08      3709658.01     10142599.69
      3708867.88     10142461.08
#Sta/Elev= 30
  4174.2  297.37  4235.4  295.27  4245.6  295.77  4327.2  292.66  4388.4  288.64
  4460.3  286.01  4506.2  282.88  4551.5   281.5  4571.9  279.58  4684.1  275.51
  4775.8   273.3  4848.2  274.01  4898.2  274.33  4919.9  273.65    4939   274.3
  4997.5  272.93  5071.2  273.36  5089.5  272.24  5111.8  273.32  5147.3  273.44
  5249.7  274.17  5310.1  274.84  5396.1  278.79  5528.1   282.8  5639.4  289.43
  5647.8  290.06    5721  296.18  5749.5  297.77  5775.1  299.83  5802.2  300.59
#Mann= 9 ,-1 , 0
  4174.2     .17       0  4848.2     .15       0  5071.2     .09       0
  5111.8     .15       0  5147.3     .11       0  5249.7     .17       0
  5639.4     .11       0  5647.8     .17       0  5749.5     .11       0
Bank Sta=5071.2,5111.8
XS Rating Curve= 0 ,0
Exp/Cntr=0.3,0.1

Type RM Length L Ch R = 1 ,9743    ,498,498,498
BEGIN DESCRIPTION:
JOHNS CREEK 18.0
END DESCRIPTION:
XS GIS Cut Line= 3
      3710267.85     10142411.07      3709719.81     10142149.41
      3708946.72     10141932.31
#Sta/Elev= 30
  4392.7  289.52  4474.9  286.92  4481.4  285.85    4492  285.67  4536.8  282.17
  4548.5  280.69  4593.8  278.53  4647.6   274.5  4684.6  272.99    4730  272.22
  4888.2  272.03  4911.4  271.29  4962.4  272.25  4968.9  271.83  4988.7  270.71
    4989  270.21  5022.8   271.7  5049.1   271.3  5083.1  271.82  5116.3  271.18
  5145.2  272.76  5333.5  274.82    5376  274.98    5421  276.64  5460.2   276.5
  5479.8  277.48  5494.3  277.42    5698  286.02  5719.5  287.86    5803  292.79
#Mann= 6 ,-1 , 0
  4392.7     .17       0  4888.2     .15       0  4968.9     .09       0
  5022.8     .15       0  5145.2     .11       0  5333.5     .17       0
Bank Sta=4968.9,5022.8
XS Rating Curve= 0 ,0
Exp/Cntr=0.3,0.1

Type RM Length L Ch R = 1 ,9245    ,499,499,499
BEGIN DESCRIPTION:
JOHNS CREEK 17.0
END DESCRIPTION:
XS GIS Cut Line= 3
      3710317.85     10142411.08      3709800.82     10141686.91
      3709017.87     10141211.08
#Sta/Elev= 30
  4110.2  289.87  4239.3  286.17  4381.8  276.59  4447.1  274.33  4690.3  269.19
    4705  271.14  4749.1  271.11  4835.2  268.07  4863.2  268.92  4891.8  265.55
    4898  268.39  4906.6  266.47  4912.7  269.48  4927.5  263.95  4942.2  268.07
  4948.4  263.99    4957  266.45  4961.1  262.53  4965.2  262.53  4970.3  267.55
  4977.9  267.86    4984  263.39  5005.5  263.36  5015.1  269.16  5067.5     269
    5108   269.8  5189.5  269.52  5530.1  277.25  5755.4  292.36  5916.2  300.53
#Mann= 7 ,-1 , 0
  4110.2     .17       0  4447.1     .11       0  4863.2     .15       0
  4977.9     .09       0  5015.1     .15       0  5067.5     .17       0
    5108     .11       0
Bank Sta=4977.9,5015.1
XS Rating Curve= 0 ,0
Exp/Cntr=0.3,0.1

Type RM Length L Ch R = 1 ,8746    ,499,499,499
BEGIN DESCRIPTION:
JOHNS CREEK 16.0
END DESCRIPTION:
XS GIS Cut Line= 3
      3710617.87     10141361.07        3710039.     10141331.97
      3709276.64     10141172.78
#Sta/Elev= 30
  4420.4  283.71  4517.8     280  4580.6  278.34  4610.7  278.52  4660.7  275.79
  4700.8  274.63  4830.9  268.55  4941.1  266.37  4961.1  266.66  4971.1  265.14
  4981.1   264.8  4991.1  263.15  4995.9  260.04  5003.1  260.54  5021.6  266.55
  5082.9  267.28    5134  267.01  5187.3  268.18  5236.1  268.92  5287.3  268.56
  5389.4  268.63  5409.8  270.98  5430.2  269.93  5467.6  271.92  5472.7  272.76
    5512  273.54  5517.6  274.45  5522.7  273.96    5655  281.67  5778.8  291.36
#Mann= 5 ,-1 , 0
  4420.4     .17       0  4961.1     .09       0  5021.6     .17       0
  5187.3     .15       0  5287.3     .11       0
Bank Sta=4961.1,5021.6
XS Rating Curve= 0 ,0
Exp/Cntr=0.3,0.1

Type RM Length L Ch R = 1 ,8247    ,500,500,500
BEGIN DESCRIPTION:
JOHNS CREEK 15.0
END DESCRIPTION:
XS GIS Cut Line= 3
      3710517.81     10141011.06      3710270.43     10140916.89
      3709667.83     10140311.05
#Sta/Elev= 30
  4735.3  275.95  4767.4  275.85  4775.1  274.84  4820.9  272.58  4829.9  271.35
  4865.4  270.52  4884.8  268.88  4920.2  267.67    4945  265.97    4960     266
  4975.1  264.78  4989.8  258.67  4994.3  258.67  5005.9  260.43    5013  263.87
  5020.3  265.08  5034.2  264.42  5069.6  265.67  5126.1  265.67  5140.3  266.48
    5211   265.9  5246.4  264.64  5411.4  264.88  5423.1  265.51  5458.5  265.54
    5507  267.25  5546.1  267.23  5628.2  266.34  5808.8  271.36  5854.5  273.87
#Mann= 7 ,-1 , 0
  4735.3     .11       0  4975.1     .07       0  5020.3     .17       0
  5411.4     .11       0    5507     .17       0  5546.1     .11       0
  5808.8     .17       0
Bank Sta=4975.1,5020.3
XS Rating Curve= 0 ,0
Exp/Cntr=0.3,0.1

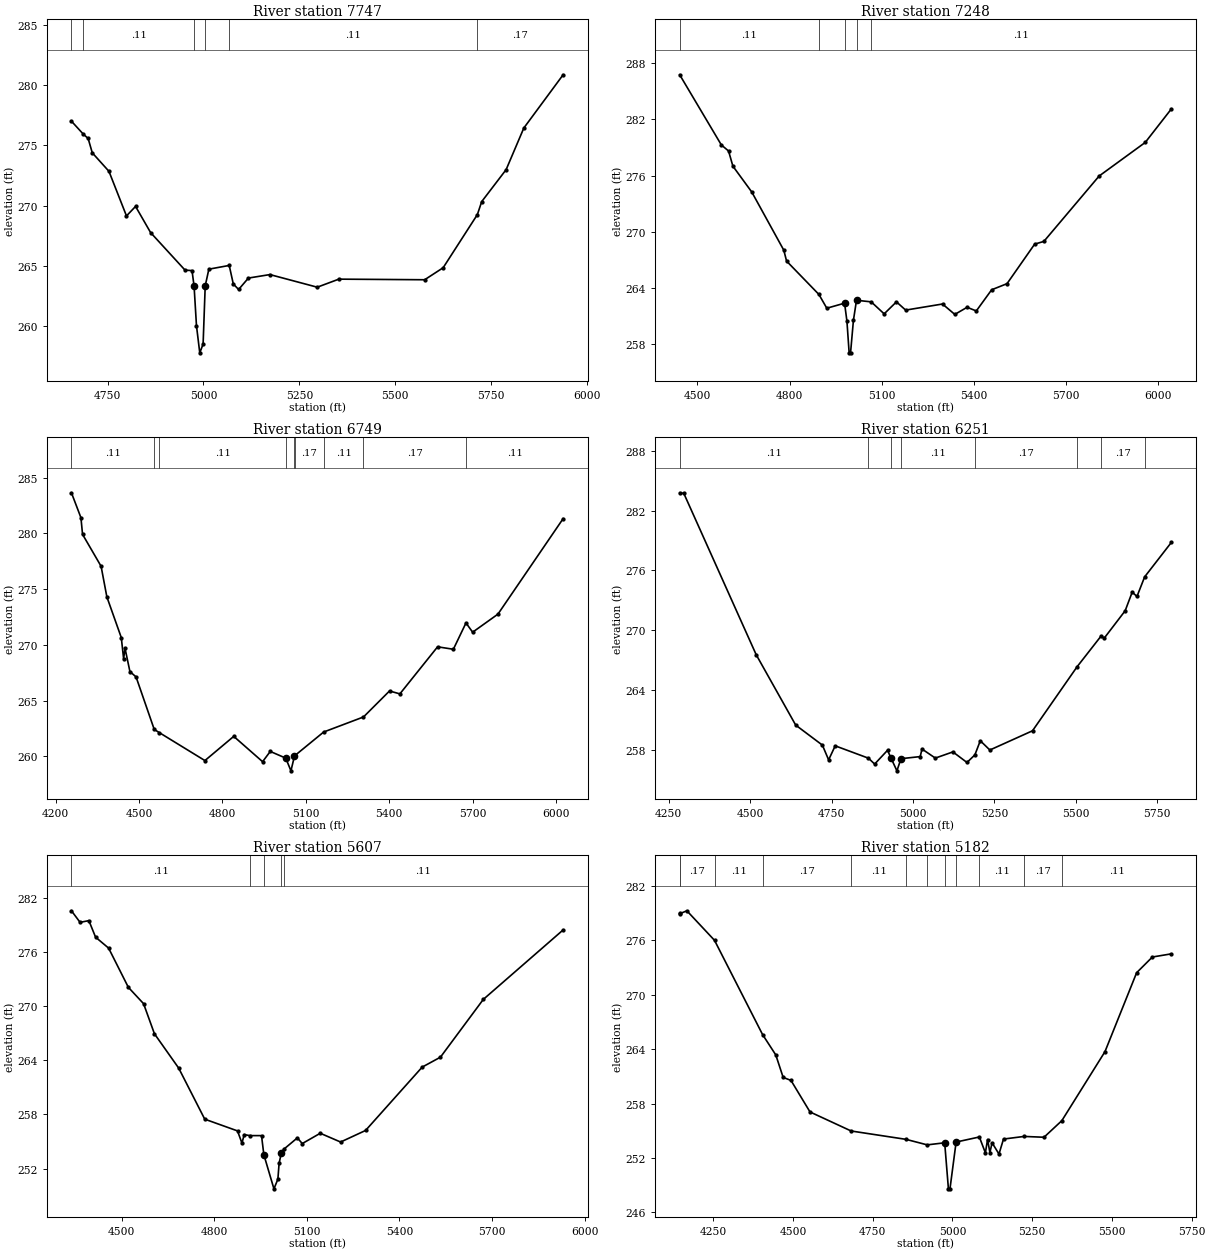
Type RM Length L Ch R = 1 ,7747    ,499,499,499
BEGIN DESCRIPTION:
JOHNS CREEK 14.0
END DESCRIPTION:
XS GIS Cut Line= 3
      3710767.81     10140611.05      3710451.12     10140476.23
      3709567.86     10140161.07
#Sta/Elev= 30
  4655.8  277.02  4686.5  275.95  4699.4  275.58  4710.1  274.39  4753.6  272.85
  4799.3  269.14    4823  269.93  4862.3  267.75    4952  264.63  4970.2  264.59
  4975.6  263.29  4981.8  260.01  4990.4  257.75  4999.1  258.48  5004.6  263.32
  5014.1  264.71  5067.2  265.02  5077.8  263.48  5091.7  263.02  5117.2  263.97
  5173.3  264.26  5296.7  263.21    5353  263.88  5576.8  263.83    5625  264.83
  5714.2  269.25  5725.5  270.33  5789.2  272.99  5835.3  276.45  5937.8  280.88
#Mann= 6 ,-1 , 0
  4655.8     .17       0  4686.5     .11       0  4975.6     .09       0
  5004.6     .17       0  5067.2     .11       0  5714.2     .17       0
Bank Sta=4975.6,5004.6
XS Rating Curve= 0 ,0
Exp/Cntr=0.3,0.1

Type RM Length L Ch R = 1 ,7248    ,499,499,499
BEGIN DESCRIPTION:
JOHNS CREEK 13.0
END DESCRIPTION:
XS GIS Cut Line= 3
      3711086.48     10140230.92      3710575.63      10140006.7
      3709532.78     10139996.56
#Sta/Elev= 30
  4442.1  286.76  4577.8  279.27  4601.2  278.63  4615.3  277.01  4676.8  274.25
  4781.1  268.04  4790.1  266.88  4895.4  263.32  4921.1  261.85  4978.9  262.39
  4986.6  260.47  4993.8  257.09  4998.4  257.09  5007.8  260.58  5017.8   262.7
  5065.6  262.53  5107.8  261.25  5147.8  262.53  5177.8  261.65  5297.8   262.3
  5337.8  261.19  5377.8  261.95  5407.8  261.56  5457.8  263.82  5507.8  264.47
  5597.8  268.69  5627.8  268.98  5807.8  275.96  5957.8  279.54  6042.9  283.12
#Mann= 5 ,-1 , 0
  4442.1     .11       0  4895.4     .17       0  4978.9     .09       0
  5017.8     .17       0  5065.6     .11       0
Bank Sta=4978.9,5017.8
XS Rating Curve= 0 ,0
Exp/Cntr=0.3,0.1

Type RM Length L Ch R = 1 ,6749    ,498,498,498
BEGIN DESCRIPTION:
JOHNS CREEK 12.0
END DESCRIPTION:
XS GIS Cut Line= 3
      3711190.69     10139796.91       3710474.5     10139599.14
      3709497.96     10139284.75
#Sta/Elev= 30
    4257  283.64  4291.1  281.41    4297  279.91  4363.7  277.05  4384.4  274.31
  4436.3  270.66  4444.7  268.77  4449.9  269.68  4467.4  267.61  4489.5  267.13
  4554.9  262.42  4573.6  262.13  4737.2  259.63  4840.9   261.8  4944.7  259.53
  4972.3  260.45    5028  259.85  5046.7  258.71  5059.4  260.04  5059.5  260.05
  5164.4  262.19  5307.7  263.54  5401.3  265.87  5438.6  265.61  5574.3  269.83
    5631  269.61  5676.4  271.97  5700.4  271.14  5791.4  272.76  6025.9  281.32
#Mann= 9 ,-1 , 0
    4257     .11       0  4554.9     .17       0  4573.6     .11       0
    5028     .06       0  5059.4     .09       0  5059.5     .17       0
  5164.4     .11       0  5307.7     .17       0  5676.4     .11       0
Bank Sta=5028,5059.4
XS Rating Curve= 0 ,0
Exp/Cntr=0.3,0.1

Type RM Length L Ch R = 1 ,6251    ,644,644,644
BEGIN DESCRIPTION:
JOHNS CREEK 11.0
END DESCRIPTION:
XS GIS Cut Line= 3
      3711290.54     10139258.72      3710581.52      10139155.4
      3709846.42     10138855.57
#Sta/Elev= 30
  4283.5  283.79  4296.3  283.72  4518.6  267.53  4639.9  260.47  4721.9  258.46
    4741  256.98  4761.2  258.39  4863.4  257.15  4882.4  256.56  4921.9  257.94
    4933  257.14  4950.8  255.88  4963.3   257.1  5022.4  257.31  5027.8  258.07
  5068.8  257.16  5122.8  257.78    5166  256.72  5190.3  257.48  5206.9   258.9
  5236.3  257.97  5367.3   259.9  5504.1  266.32  5578.7  269.44  5587.2  269.18
    5652  271.95  5673.6  273.82  5688.2  273.38  5711.8  275.35  5793.9  278.81
#Mann= 8 ,-1 , 0
  4283.5     .11       0  4863.4     .17       0    4933     .06       0
  4963.3     .11       0  5190.3     .17       0  5504.1     .11       0
  5578.7     .17       0  5711.8     .11       0
Bank Sta=4933,4963.3
XS Rating Curve= 0 ,0
Exp/Cntr=0.3,0.1

Type RM Length L Ch R = 1 ,5607    ,425,425,425
BEGIN DESCRIPTION:
JOHNS CREEK 10.0
END DESCRIPTION:
XS GIS Cut Line= 3
      3711267.86     10139011.08      3710769.66     10138568.61
       3709962.6     10138113.01
#Sta/Elev= 30
  4337.6  280.54  4365.6  279.26  4394.1  279.45  4415.8  277.62    4458  276.41
    4522  272.07  4571.3  270.26  4606.5  266.93  4685.1  263.13  4769.5  257.48
  4875.7  256.18    4890  254.83  4897.5  255.77  4915.9  255.66  4953.5  255.66
    4961  253.55  4993.7  249.77  5006.5  250.84  5010.4  252.58  5017.5  253.72
  5025.2  254.14  5069.6  255.41  5085.5  254.78  5143.8  255.92  5209.7  254.95
  5290.6  256.23    5474  263.24  5533.2  264.34    5672  270.73  5930.7  278.42
#Mann= 5 ,-1 , 0
  4337.6     .11       0  4915.9     .15       0    4961     .09       0
  5017.5     .15       0  5025.2     .11       0
Bank Sta=4961,5017.5
XS Rating Curve= 0 ,0
Exp/Cntr=0.3,0.1

Type RM Length L Ch R = 1 ,5182    ,490,490,490
BEGIN DESCRIPTION:
JOHNS CREEK 9.0
END DESCRIPTION:
XS GIS Cut Line= 3
      3711299.16     10138941.83      3711047.44     10138295.17
      3710422.64     10137722.44
#Sta/Elev= 30
  4144.9  278.96    4147  278.97  4167.4  279.27  4254.1  276.01  4404.7  265.62
  4446.2  263.37  4469.3  260.89  4493.8  260.56  4553.5  257.08  4682.5  254.98
  4854.3  254.06  4920.9  253.45  4975.7  253.68  4987.4   248.6  4992.3   248.6
  5011.5  253.76  5084.4  254.32  5103.3  252.57  5110.1  254.04  5117.5   252.6
  5124.3  253.68  5145.9  252.44  5160.1  254.09  5224.7  254.38  5287.1  254.29
    5343  256.12  5478.2  263.73  5577.5  272.44  5626.8  274.17  5686.4  274.52
#Mann= 12 ,-1 , 0
  4144.9     .11       0    4147     .17       0  4254.1     .11       0
  4404.7     .17       0  4682.5     .11       0  4854.3     .15       0
  4920.9     .17       0  4975.7     .09       0  5011.5     .17       0
  5084.4     .11       0  5224.7     .17       0    5343     .11       0
Bank Sta=4975.7,5011.5
XS Rating Curve= 0 ,0
Exp/Cntr=0.3,0.1

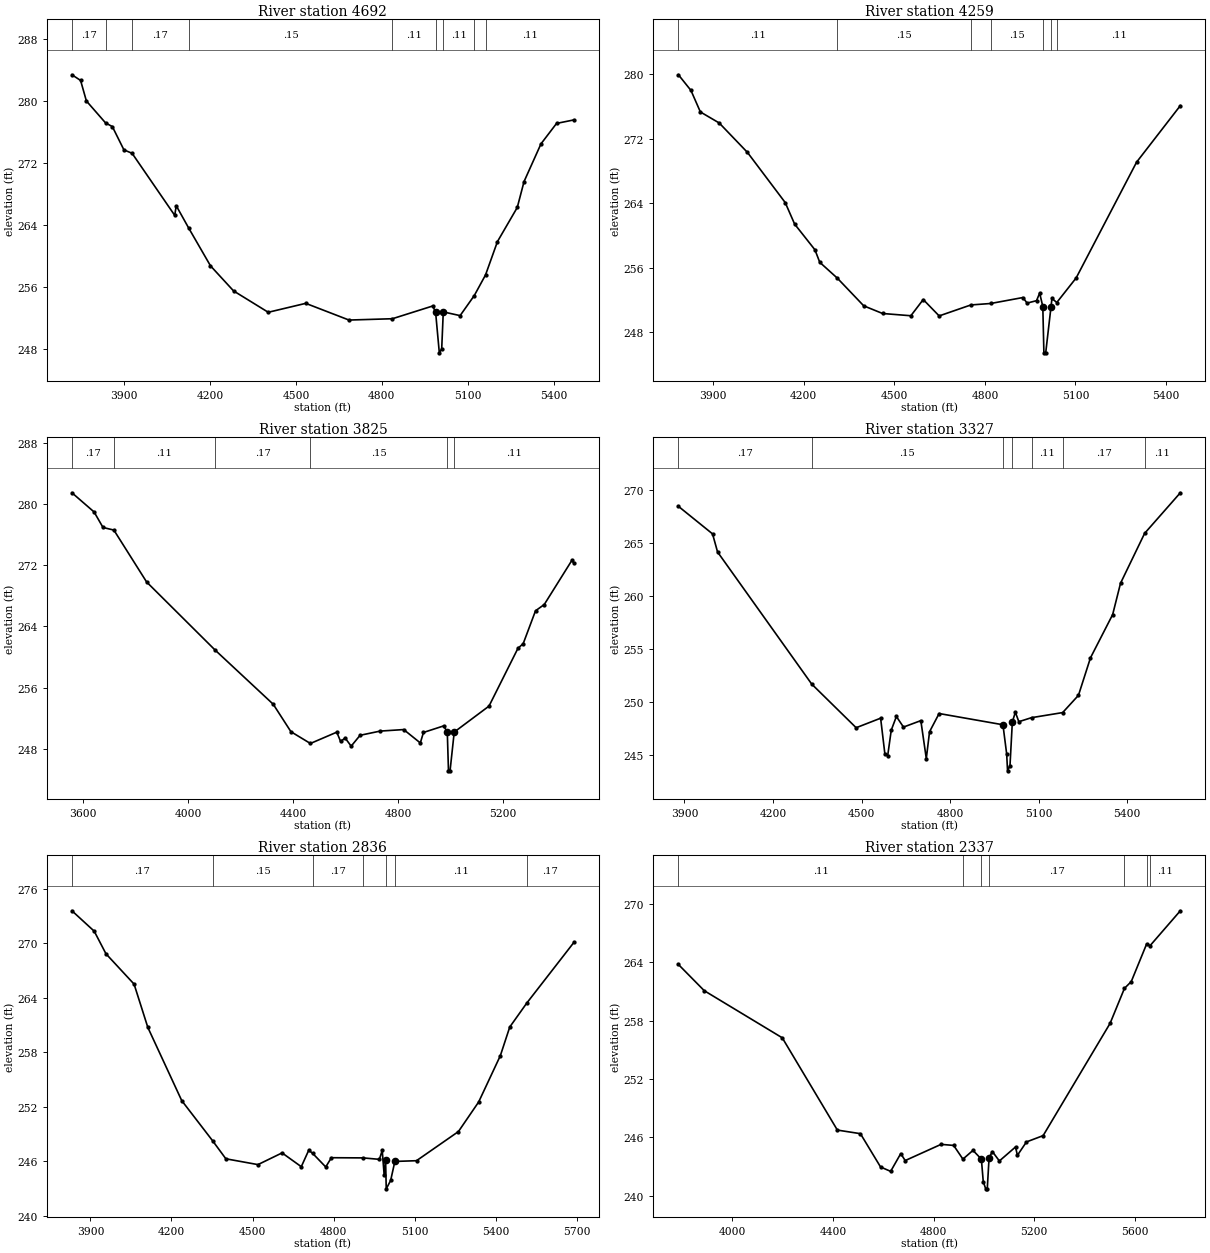
Type RM Length L Ch R = 1 ,4692    ,433,433,433
BEGIN DESCRIPTION:
JOHNS CREEK 8.0
END DESCRIPTION:
XS GIS Cut Line= 3
      3712167.82     10137961.07      3710891.19     10137800.38
       3710462.2     10137618.38
#Sta/Elev= 30
    3718  283.36  3748.2  282.63  3768.4  279.99  3835.5  277.16  3859.1  276.69
  3899.4   273.7  3928.1  273.25    4077  265.26  4082.1  266.51    4126  263.61
  4201.8  258.77  4282.4  255.54  4403.5  252.79  4534.4  253.94  4685.5  251.79
    4837  251.96  4977.8   253.6  4987.9   252.8  5000.9  247.57  5009.2  248.07
  5014.7  252.84  5073.5  252.36  5123.1  254.95  5162.3   257.6  5203.9  261.89
  5273.1  266.28  5296.8  269.62  5355.9  274.47  5410.3   277.1  5470.7  277.55
#Mann= 9 ,-1 , 0
    3718     .17       0  3835.5     .11       0  3928.1     .17       0
    4126     .15       0    4837     .11       0  4987.9     .07       0
  5014.7     .11       0  5123.1     .17       0  5162.3     .11       0
Bank Sta=4987.9,5014.7
XS Rating Curve= 0 ,0
Exp/Cntr=0.3,0.1

Type RM Length L Ch R = 1 ,4259    ,434,434,434
BEGIN DESCRIPTION:
JOHNS CREEK 7.0
END DESCRIPTION:
XS GIS Cut Line= 3
      3712097.78     10137800.38      3710930.25     10137466.18
      3710483.21     10137483.54
#Sta/Elev= 30
  3785.3  279.93  3826.8  277.99    3858  275.32  3920.4  273.95  4013.9   270.3
  4138.9  264.08  4170.1  261.41  4237.3  258.22  4253.3  256.67  4311.6   254.7
  4398.9  251.27  4461.3  250.32  4554.9  250.04  4595.9  252.05  4648.6  250.02
  4753.6  251.38  4819.1  251.56  4925.8   252.3  4939.8  251.61    4971  251.91
  4981.4  252.85  4991.8  251.18  4995.4  245.44  5001.4  245.44 5019.05251.1773
  5022.1  252.19    5038  251.68  5102.2  254.73  5302.3  269.09  5447.1   276.1
#Mann= 7 ,-1 , 0
  3785.3     .11       0  4311.6     .15       0  4753.6     .17       0
  4819.1     .15       0  4991.8     .09       0 5019.05     .15       0
    5038     .11       0
Bank Sta=4991.8,5019.05
XS Rating Curve= 0 ,0
Exp/Cntr=0.3,0.1

Type RM Length L Ch R = 1 ,3825    ,498,498,498
BEGIN DESCRIPTION:
JOHNS CREEK 6.0
END DESCRIPTION:
XS GIS Cut Line= 3
      3712314.79     10137713.57      3711004.25     10137109.86
       3710535.3     10137075.55
#Sta/Elev= 30
  3557.1  281.48  3641.5  278.97  3675.5  276.94  3716.9   276.6  3841.7  269.81
  4102.2  260.92  4324.4  253.81  4391.8  250.22    4466  248.68  4566.6  250.16
    4581  248.95  4598.5  249.39  4621.4  248.33  4655.4  249.75  4731.8   250.3
  4821.6   250.5    4885  248.75  4896.9  250.12    4974  250.98  4987.8  250.17
  4992.3   245.1  4998.3   245.1 5014.24250.1728  5146.8  253.57  5257.1  261.13
  5277.1  261.74  5324.1  266.04  5357.4  266.86  5462.9  272.65  5470.2  272.27
#Mann= 6 ,-1 , 0
  3557.1     .17       0  3716.9     .11       0  4102.2     .17       0
    4466     .15       0  4987.8     .06       0 5014.24     .11       0
Bank Sta=4987.8,5014.24
XS Rating Curve= 0 ,0
Exp/Cntr=0.3,0.1

Type RM Length L Ch R = 1 ,3327    ,491,491,491
BEGIN DESCRIPTION:
JOHNS CREEK 5.0
END DESCRIPTION:
XS GIS Cut Line= 3
      3712314.84     10137166.71      3711278.35     10136741.55
      3710708.93     10136632.85
#Sta/Elev= 30
  3879.7  268.44  3995.3  265.84  4012.3  264.13  4331.2  251.66  4481.7  247.54
  4564.6  248.44    4579  245.07  4588.6  244.91  4600.6  247.31    4618   248.6
    4642   247.6  4700.8  248.21  4719.3  244.63  4730.3  247.16  4762.7  248.88
  4978.9  247.82  4991.6  245.05  4994.5  243.47  5002.8  243.97  5010.7  248.07
  5020.9  249.01  5032.7  248.11  5075.8  248.49  5181.2  248.97  5234.7   250.6
  5275.4  254.14  5350.5  258.22  5377.2  261.18  5458.8  265.89  5579.7  269.72
#Mann= 7 ,-1 , 0
  3879.7     .17       0  4331.2     .15       0  4978.9     .09       0
  5010.7     .15       0  5075.8     .11       0  5181.2     .17       0
  5458.8     .11       0
Bank Sta=4978.9,5010.7
XS Rating Curve= 0 ,0
Exp/Cntr=0.3,0.1

Type RM Length L Ch R = 1 ,2836    ,499,499,499
BEGIN DESCRIPTION:
JOHNS CREEK 4.0
END DESCRIPTION:
XS GIS Cut Line= 3
      3712466.74     10136641.53      3711348.47     10136302.95
      3710682.84     10136125.03
#Sta/Elev= 30
  3831.6   273.6    3914  271.35  3957.5  268.86  4061.5  265.52  4112.5  260.74
  4237.9  252.68  4351.8  248.27  4401.2  246.27    4520  245.63  4609.2  246.92
  4680.3   245.4    4708  247.22  4722.6  246.86  4770.8  245.37  4791.7  246.39
  4908.8  246.37  4969.3  246.21  4979.8  247.19  4987.1  244.46  4992.3   246.1
  4994.7  242.96    5011  243.88  5026.6  245.98  5106.7  246.06  5261.8  249.27
  5336.7  252.53  5416.9  257.63  5451.8  260.79    5515  263.44    5689  270.11
#Mann= 7 ,-1 , 0
  3831.6     .17       0  4351.8     .15       0  4722.6     .17       0
  4908.8     .11       0  4992.3     .06       0  5026.6     .11       0
    5515     .17       0
Bank Sta=4992.3,5026.6
XS Rating Curve= 0 ,0
Exp/Cntr=0.3,0.1

Type RM Length L Ch R = 1 ,2337    ,533,533,533
BEGIN DESCRIPTION:
JOHNS CREEK 3.0
END DESCRIPTION:
XS GIS Cut Line= 3
      3712609.95     10135738.74      3711398.22     10135829.16
      3710635.13     10135999.16
#Sta/Elev= 30
  3784.9  263.79  3887.8  261.09  4198.1  256.24  4417.3  246.74    4509  246.37
  4589.2  242.94  4629.3  242.49  4669.5  244.32  4687.1   243.6  4829.9  245.27
    4880  245.16  4916.8  243.75  4956.9  244.65  4990.3  243.75  4997.7  241.44
  5007.5  240.69  5013.7  240.69  5020.9  243.88    5034  244.53  5061.9  243.56
  5126.1     245  5133.6  244.14  5169.6  245.52    5236  246.17  5502.4  257.73
  5559.5  261.33  5586.6  262.03  5647.9  265.91  5661.5  265.73  5781.8  269.32
#Mann= 7 ,-1 , 0
  3784.9     .11       0  4916.8     .17       0  4990.3     .09       0
  5020.9     .17       0  5559.5     .11       0  5647.9     .17       0
  5661.5     .11       0
Bank Sta=4990.3,5020.9
XS Rating Curve= 0 ,0
Exp/Cntr=0.3,0.1