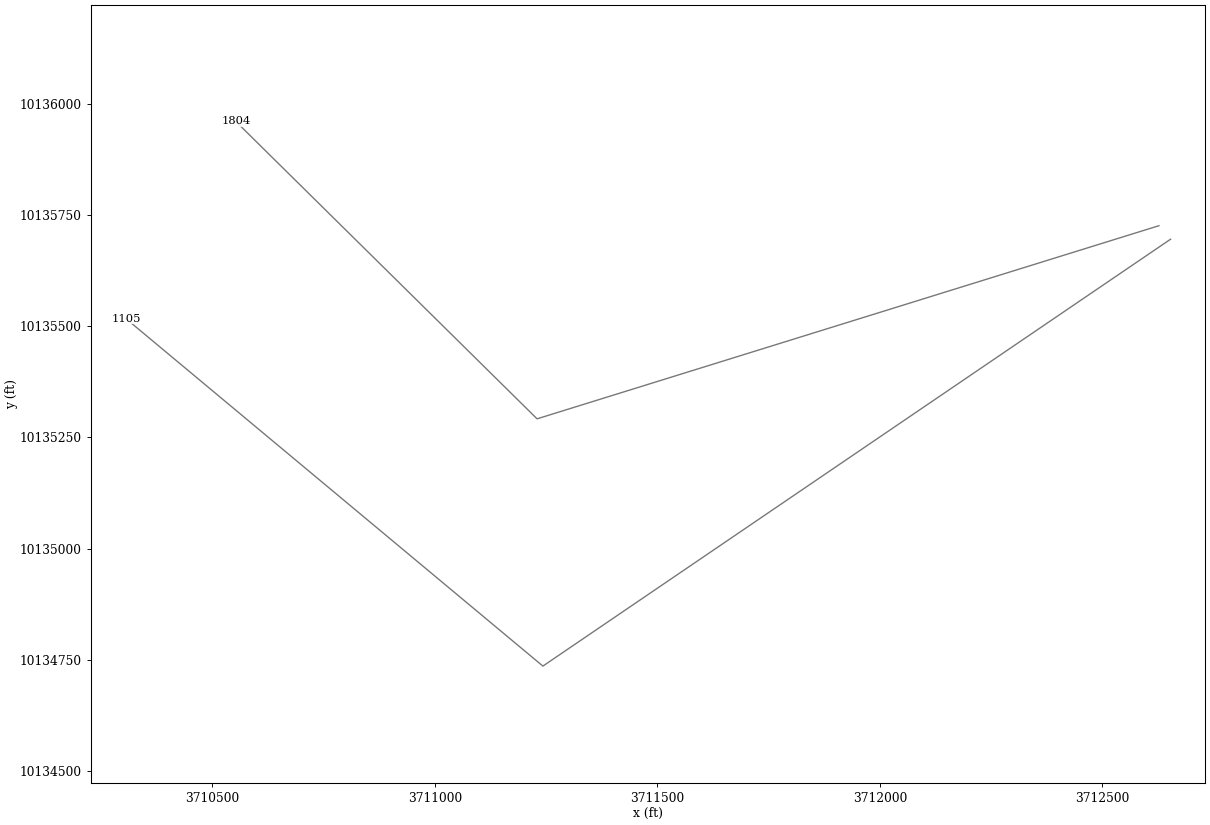
HEC-RAS study JOHNS CREEK.prj: JOHNS CREEK Base Level Engineering

--- JOHNS CREEK.g01 (geometry) --- (continued)

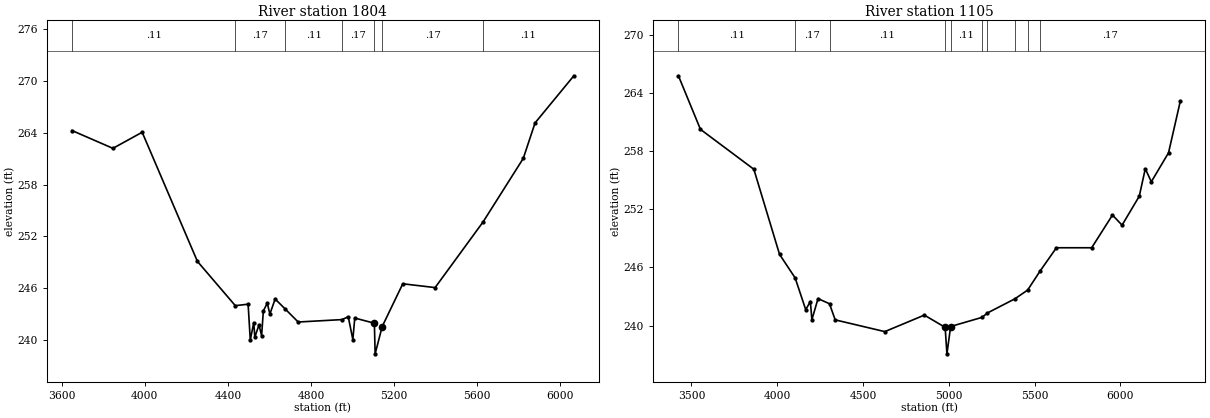
Type RM Length L Ch R = 1 ,1804    ,699,699,699
BEGIN DESCRIPTION:
JOHNS CREEK 2.0
END DESCRIPTION:
XS GIS Cut Line= 3
      3712627.25     10135725.71      3711229.73      10135291.7
      3710552.78     10135959.97
#Sta/Elev= 30
  3649.9  264.25    3847  262.19  3987.7  264.05  4253.5  249.12  4435.8     244
  4497.4  244.17  4507.9  240.02  4524.5  242.04  4529.7  240.36  4549.8  241.78
  4562.3  240.53  4570.7  243.39  4589.6  244.29  4602.1  243.03  4627.4  244.77
    4676  243.61  4738.3  242.11  4949.2  242.39  4979.1  242.72  5001.3  240.08
  5010.5  242.57  5104.8  241.97  5108.5  238.43  5142.5  241.59  5241.5  246.53
    5397  246.09  5627.7  253.68  5821.2  261.03  5877.8  265.13  6064.5  270.58
#Mann= 7 ,-1 , 0
  3649.9     .11       0  4435.8     .17       0    4676     .11       0
  4949.2     .17       0  5104.8     .09       0  5142.5     .17       0
  5627.7     .11       0
Bank Sta=5104.8,5142.5
XS Rating Curve= 0 ,0
Exp/Cntr=0.3,0.1

Type RM Length L Ch R = 1 ,1105    ,0,0,0
BEGIN DESCRIPTION:
JOHNS CREEK 1.0
END DESCRIPTION:
XS GIS Cut Line= 3
      3712653.37     10135695.36      3711242.85     10134736.07
      3710306.01     10135516.76
#Sta/Elev= 30
  3423.8  265.75  3552.2  260.23  3863.4  256.12  4013.2  247.35  4104.2  244.92
  4165.8  241.65  4192.8  242.49  4201.7  240.62  4237.6  242.79  4304.4  242.26
  4337.5   240.6  4626.7  239.39  4857.2  241.09  4978.4  239.83  4988.8   237.1
 5010.36239.9168  5193.8  240.86  5224.8  241.31    5385  242.77  5459.2  243.67
  5531.7  245.63  5626.9  248.03  5832.5  248.03  5953.6   251.4  6009.6  250.36
  6109.8  253.34  6144.9  256.17  6180.1  254.83  6280.3  257.81  6349.1  263.14
#Mann= 10 ,-1 , 0
  3423.8     .11       0  4104.2     .17       0  4304.4     .11       0
  4978.4     .06       0 5010.36     .11       0  5193.8     .17       0
  5224.8     .15       0    5385     .17       0  5459.2     .11       0
  5531.7     .17       0
Bank Sta=4978.4,5010.36
XS Rating Curve= 0 ,0
Exp/Cntr=0.3,0.1

Chan Stop Cuts=-1
Use User Specified Reach Order=0
Composite Channel Slope=5