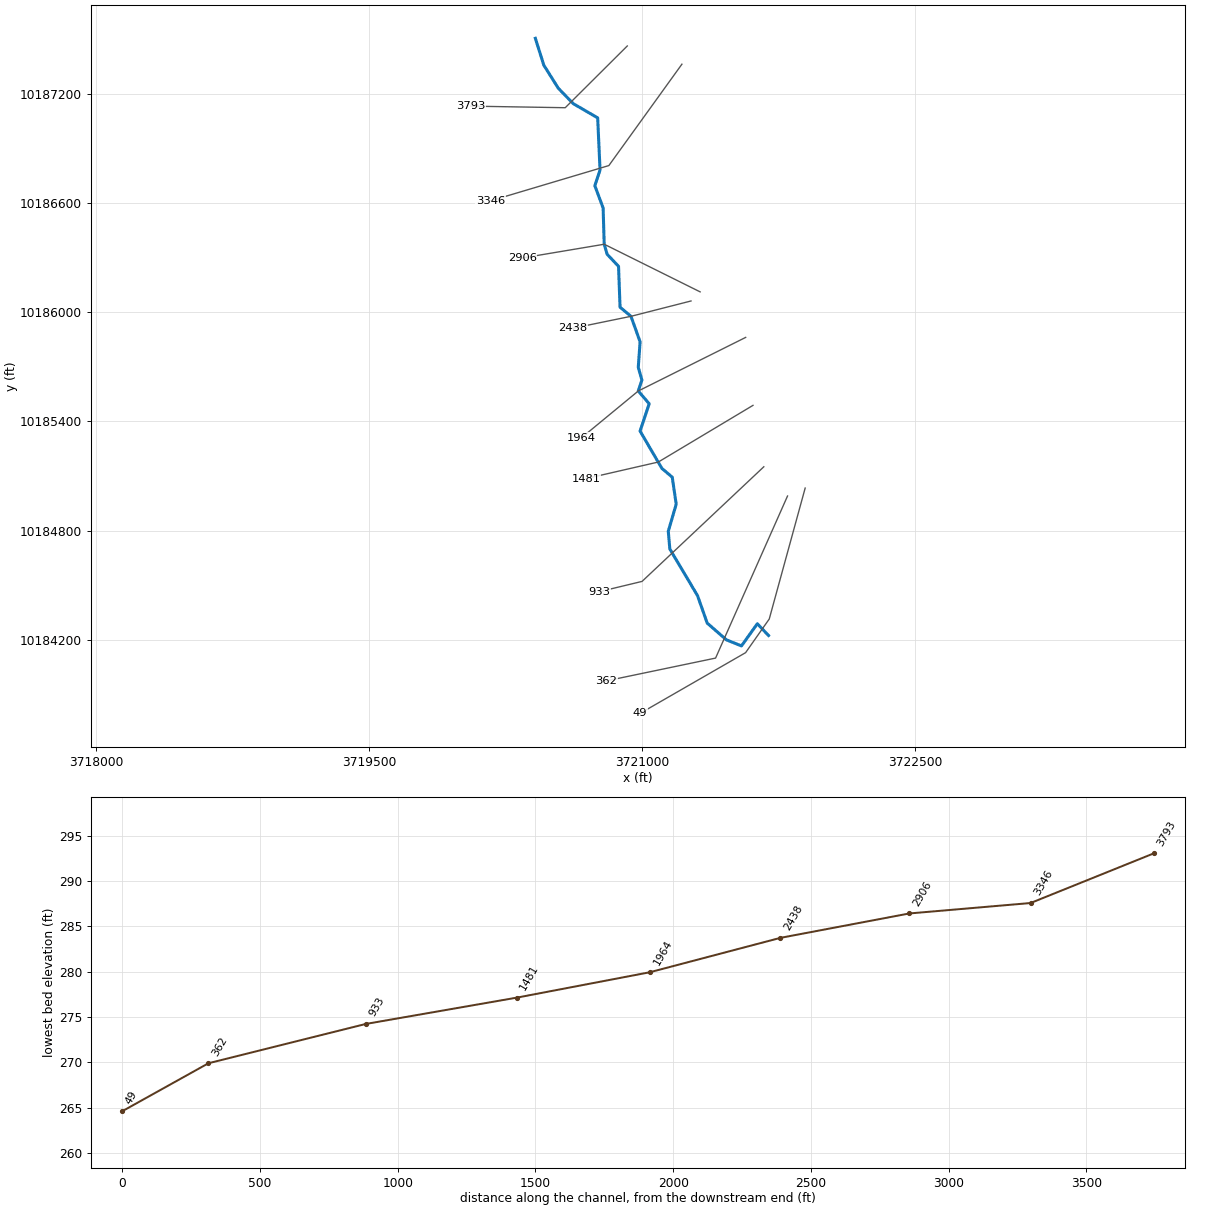
--- KIDHAW BRANCH TRIBUTARY NO 1.prj (project) ---

Proj Title=KIDHAW BRANCH TRIBUTARY NO 1 Base Level Engineering
Current Plan=p01
Default Exp/Contr=0.3,0.1
English Units
Geom File=g01
Flow File=f01
Flow File=f02
Plan File=p01
Y Axis Title=Elevation
X Axis Title(PF)=Main Channel Distance
X Axis Title(XS)=Station
BEGIN DESCRIPTION:
KIDHAW BRANCH TRIBUTARY NO 1
END DESCRIPTION:
DSS Export Rating Curves= 0
DSS Export Rating Curve Sorted= 0
DSS Export Volume Flow Curves= 0
DXF OffsetX= 0
DXF OffsetY= 0
DXF ScaleX= 1
DXF ScaleY= 10

--- KIDHAW BRANCH TRIBUTARY NO 1.p01 (plan) ---

Plan Title=Multiple Run
Short Identifier=Multiple
Geom File=g01
Flow File=f01
Subcritical Flow
K Sum by GR= 0
Std Step Tol= 0.01
Critical Tol= 0.01
Num of Std Step Trials= 20
Max Error Tol= 0.3
Flow Tol Ratio= 0.001
Split Flow NTrial= 30
Split Flow Tol= 0.02
Split Flow Ratio= 0.02
Log Output Level= 0
Friction Slope Method= 1
Unsteady Friction Slope Method= 2
Unsteady Bridges Friction Slope Method= 1
Parabolic Critical Depth
Global Vel Dist=  1 , 1 , 1
Global Log Level= 0
CheckData=True
Encroach Param= -1, 0, 0, 0
BEGIN DESCRIPTION:
Multiple Run
END DESCRIPTION:

--- KIDHAW BRANCH TRIBUTARY NO 1.f01 (steady flow) ---

Flow Title=Multiple
Program Version=4.10
Number of Profiles= 7
Profile Names=10-year,25-year,50-year,1pct_min,100-year,1pct_plu,500-year
River Rch & RM=KIDHAW BRANCH TR,Reach-1         ,3793
     629     857    1162     519    1567    4732    2946
Boundary for River Rch & Prof#=KIDHAW BRANCH TR,Reach-1         , 1
Up Type= 0
Dn Type= 3
Dn Slope=0.005
Boundary for River Rch & Prof#=KIDHAW BRANCH TR,Reach-1         , 2
Up Type= 0
Dn Type= 3
Dn Slope=0.005
Boundary for River Rch & Prof#=KIDHAW BRANCH TR,Reach-1         , 3
Up Type= 0
Dn Type= 3
Dn Slope=0.005
Boundary for River Rch & Prof#=KIDHAW BRANCH TR,Reach-1         , 4
Up Type= 0
Dn Type= 3
Dn Slope=0.005
Boundary for River Rch & Prof#=KIDHAW BRANCH TR,Reach-1         , 5
Up Type= 0
Dn Type= 3
Dn Slope=0.005
Boundary for River Rch & Prof#=KIDHAW BRANCH TR,Reach-1         , 6
Up Type= 0
Dn Type= 3
Dn Slope=0.005
Boundary for River Rch & Prof#=KIDHAW BRANCH TR,Reach-1         , 7
Up Type= 0
Dn Type= 3
Dn Slope=0.005
DSS Import GetInterval= 0
DSS Import GetPeak= 0
DSS Import FillOption= 0

--- KIDHAW BRANCH TRIBUTARY NO 1.f02 (steady flow) ---

Flow Title=Orig_BLE_Flows
Program Version=4.10
Number of Profiles= 7
Profile Names=10-year,25-year,50-year,1pct_min,100-year,1pct_plu,500-year
River Rch & RM=KIDHAW BRANCH TR,Reach-1         ,3793
     629     840    1010     399    1205    3640    1713
Boundary for River Rch & Prof#=KIDHAW BRANCH TR,Reach-1         , 1
Up Type= 0
Dn Type= 3
Dn Slope=0.005
Boundary for River Rch & Prof#=KIDHAW BRANCH TR,Reach-1         , 2
Up Type= 0
Dn Type= 3
Dn Slope=0.005
Boundary for River Rch & Prof#=KIDHAW BRANCH TR,Reach-1         , 3
Up Type= 0
Dn Type= 3
Dn Slope=0.005
Boundary for River Rch & Prof#=KIDHAW BRANCH TR,Reach-1         , 4
Up Type= 0
Dn Type= 3
Dn Slope=0.005
Boundary for River Rch & Prof#=KIDHAW BRANCH TR,Reach-1         , 5
Up Type= 0
Dn Type= 3
Dn Slope=0.005
Boundary for River Rch & Prof#=KIDHAW BRANCH TR,Reach-1         , 6
Up Type= 0
Dn Type= 3
Dn Slope=0.005
Boundary for River Rch & Prof#=KIDHAW BRANCH TR,Reach-1         , 7
Up Type= 0
Dn Type= 3
Dn Slope=0.005
DSS Import GetInterval= 0
DSS Import GetPeak= 0
DSS Import FillOption= 0

--- KIDHAW BRANCH TRIBUTARY NO 1.g01 (geometry) ---

Geom Title=Existing Conditions
Program Version=4.10

River Reach=KIDHAW BRANCH TR,Reach-1
Reach XY= 30
      3720413.19     10187502.97      3720459.73     10187355.37
      3720539.15     10187229.07      3720621.18     10187144.44
       3720755.3     10187066.31      3720768.32     10186779.85
      3720739.67     10186693.92      3720785.25     10186571.52
      3720791.24     10186372.56      3720807.38     10186317.35
      3720869.88     10186251.21      3720878.23     10186026.84
      3720938.23     10185976.84      3720988.23     10185836.84
      3720978.23     10185696.84      3720998.23     10185626.84
      3720978.23     10185566.84      3721038.23     10185496.84
      3720988.23     10185346.84      3721108.23     10185141.39
      3721164.76     10185093.81      3721186.47     10184945.41
      3721143.04       10184797.      3721151.48     10184699.28
       3721303.5      10184443.5      3721356.59     10184292.69
      3721461.56     10184200.99      3721544.81     10184167.21
      3721631.67     10184289.07      3721693.33     10184224.45

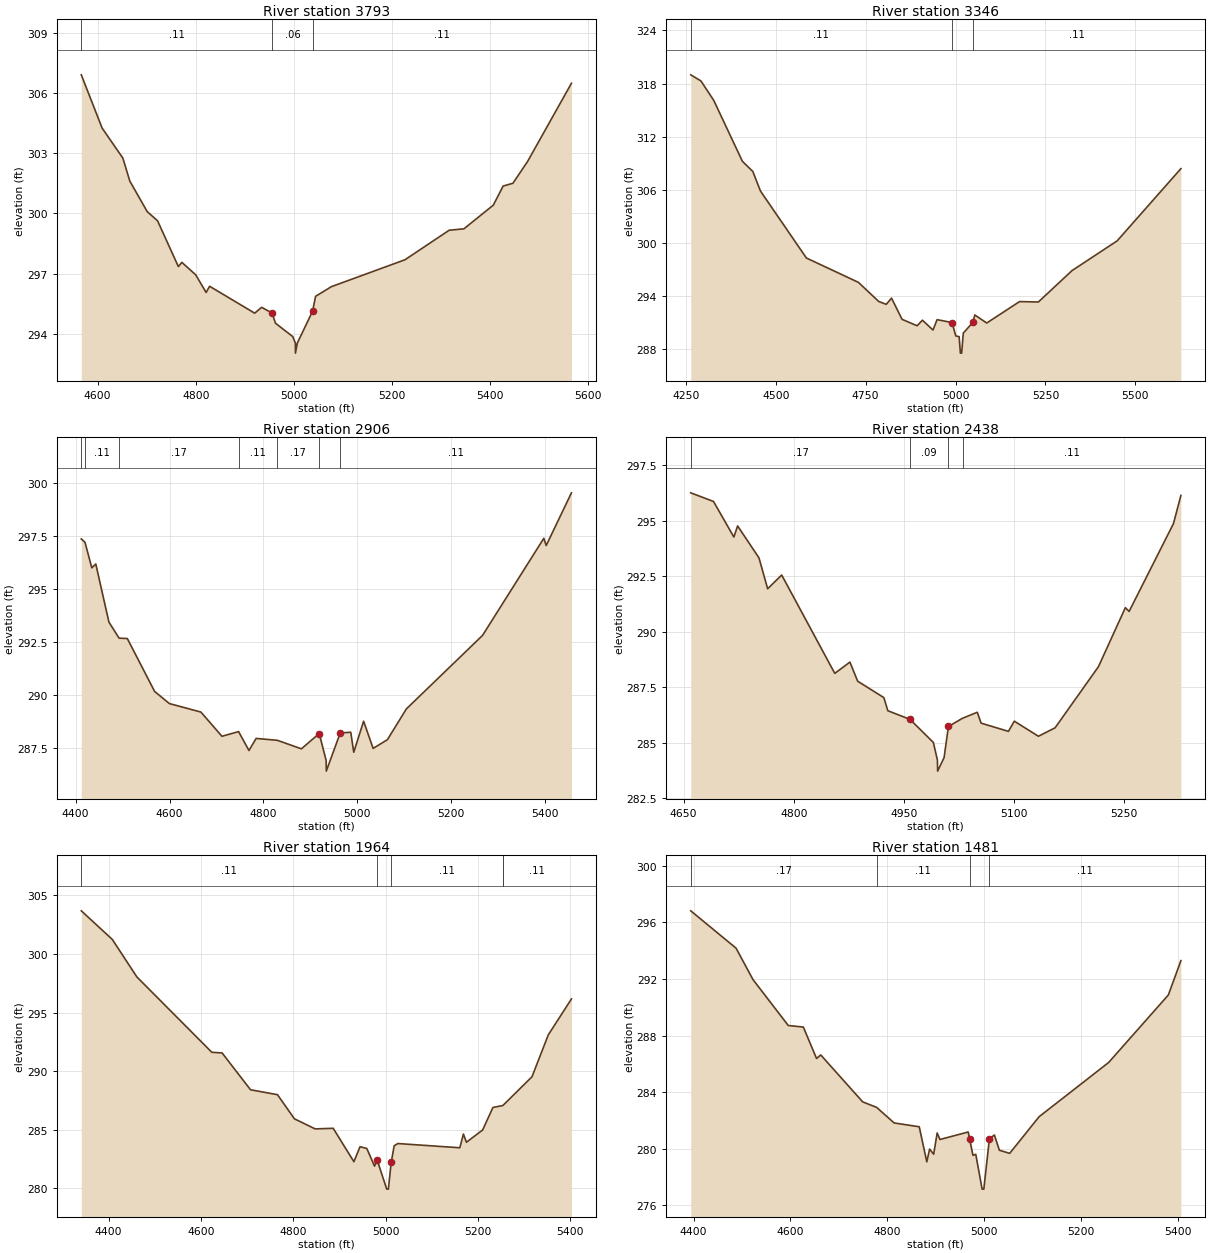
Type RM Length L Ch R = 1 ,3793    ,447,447,447
BEGIN DESCRIPTION:
KIDHAW BRANCH TRIBUTARY NO. 1 7.0
END DESCRIPTION:
XS GIS Cut Line= 3
      3720917.83     10187461.05      3720577.25     10187122.06
      3720058.55     10187130.74
#Sta/Elev= 30
  4566.6   306.9    4609  304.25  4651.4  302.75  4665.5  301.61  4700.9  300.09
  4722.1  299.63  4764.5  297.35  4771.6  297.56  4799.9  296.94  4821.1  296.06
  4828.2  296.37  4920.1  295.03  4934.2  295.32  4955.5  295.04  4962.5  294.53
  4997.9  293.86    5003  293.54  5003.2  293.04    5007  293.54 5038.15295.1286
  5044.3  295.87  5076.5  296.35  5226.5  297.69  5316.6  299.16  5346.6  299.23
  5406.6  300.41  5426.6  301.36  5446.6   301.5  5476.6  302.59  5565.9  306.48
#Mann= 3 , 0 , 0
  4566.6     .11       0  4955.5     .06       0 5038.15     .11       0
Bank Sta=4955.5,5038.15
XS Rating Curve= 0 ,0
Exp/Cntr=0.3,0.1

Type RM Length L Ch R = 1 ,3346    ,440,440,440
BEGIN DESCRIPTION:
KIDHAW BRANCH TRIBUTARY NO. 1 6.0
END DESCRIPTION:
XS GIS Cut Line= 3
      3721217.88     10187361.11      3720816.74     10186804.47
      3720167.87     10186611.08
#Sta/Elev= 30
  4263.5  318.99  4291.8   318.3  4327.4  316.11  4407.1  309.23  4436.1  308.08
  4457.4  305.87  4585.1  298.31  4729.8  295.56  4786.3   293.4  4807.2  293.08
  4821.9  293.78  4851.3  291.38  4893.1  290.66  4907.8  291.29  4937.2  290.18
  4948.6  291.35  4990.2  291.02  5000.6  289.51  5009.9  289.43  5013.4  287.57
  5016.9  287.57  5021.5  289.83  5048.3  291.05  5053.5  291.88  5086.7  290.97
    5178  293.39  5230.2  293.34    5324  296.89  5449.3  300.24  5626.7   308.4
#Mann= 3 , 0 , 0
  4263.5     .11       0  4990.2     .06       0  5048.3     .11       0
Bank Sta=4990.2,5048.3
XS Rating Curve= 0 ,0
Exp/Cntr=0.3,0.1

Type RM Length L Ch R = 1 ,2906    ,468,468,468
BEGIN DESCRIPTION:
KIDHAW BRANCH TRIBUTARY NO. 1 5.0
END DESCRIPTION:
XS GIS Cut Line= 3
      3721317.88     10186111.06      3720791.24     10186372.56
      3720341.04     10186296.95
#Sta/Elev= 30
    4412  297.35  4419.9  297.19  4434.4  295.99  4442.9  296.17  4470.8  293.44
  4492.5  292.68  4510.1  292.66  4568.3  290.17  4599.7   289.6  4666.9   289.2
  4711.7  288.06  4747.2  288.28  4769.3  287.39  4784.6  287.96  4829.9  287.87
    4881  287.47    4919  288.19  4933.8  286.92  4934.1  286.42  4963.8  288.22
  4986.2  288.25  4992.6  287.31  5013.6  288.77  5033.9  287.49  5064.3   287.9
  5104.8  289.35  5267.1  292.81  5397.6  297.38  5402.7  297.04  5456.5  299.52
#Mann= 7 ,-1 , 0
    4412     .17       0  4419.9     .11       0  4492.5     .17       0
  4747.2     .11       0  4829.9     .17       0    4919     .06       0
  4963.8     .11       0
Bank Sta=4919,4963.8
XS Rating Curve= 0 ,0
Exp/Cntr=0.3,0.1

Type RM Length L Ch R = 1 ,2438    ,474,474,474
BEGIN DESCRIPTION:
KIDHAW BRANCH TRIBUTARY NO. 1 4.0
END DESCRIPTION:
XS GIS Cut Line= 3
      3721267.84     10186061.07      3720938.23     10185976.84
      3720617.81     10185911.06
#Sta/Elev= 30
  4659.8  296.26  4690.8  295.87  4718.5  294.27  4723.6  294.77  4752.7  293.33
  4764.5  291.94  4783.6  292.56  4855.9  288.13  4876.5  288.64    4887  287.78
  4922.7  287.04  4928.1  286.45  4958.3  286.06  4990.1  285.02  4995.6  284.23
  4995.9  283.73  5004.7  284.34  5010.6  285.74  5029.8  286.11  5049.9  286.38
  5055.1  285.89  5092.3  285.52  5100.3  285.98  5133.1   285.3  5155.8  285.68
  5214.8  288.43  5251.5  291.09  5256.6  290.92  5316.9  294.87  5327.1  296.14
#Mann= 4 ,-1 , 0
  4659.8     .17       0  4958.3     .09       0  5010.6     .17       0
  5029.8     .11       0
Bank Sta=4958.3,5010.6
XS Rating Curve= 0 ,0
Exp/Cntr=0.3,0.1

Type RM Length L Ch R = 1 ,1964    ,483,483,483
BEGIN DESCRIPTION:
KIDHAW BRANCH TRIBUTARY NO. 1 3.0
END DESCRIPTION:
XS GIS Cut Line= 3
      3721567.89     10185861.09      3720978.23     10185566.84
      3720667.84     10185311.06
#Sta/Elev= 30
    4341  303.69  4408.1  301.25  4461.3  298.05  4623.5  291.62  4645.9  291.56
  4707.4  288.42  4765.7     288  4802.5  285.94  4847.3  285.08  4886.4  285.13
  4931.2  282.28  4944.5  283.56  4959.1  283.41  4975.9   281.9  4981.5  282.43
  5002.3  279.94  5005.8  279.94    5012  282.22  5018.4  283.64  5026.3  283.83
  5160.5  283.47  5168.3  284.64  5174.8  283.94    5210  284.99  5232.2  286.91
  5253.2  287.07  5254.9  287.12  5316.8  289.53    5352   293.1  5402.2  296.17
#Mann= 5 ,-1 , 0
    4341     .11       0  4981.5     .06       0    5012     .11       0
  5253.2     .17       0  5254.9     .11       0
Bank Sta=4981.5,5012
XS Rating Curve= 0 ,0
Exp/Cntr=0.3,0.1

Type RM Length L Ch R = 1 ,1481    ,548,548,548
BEGIN DESCRIPTION:
KIDHAW BRANCH TRIBUTARY NO. 1 2.0
END DESCRIPTION:
XS GIS Cut Line= 3
      3721608.05     10185487.94      3721088.23     10185176.84
       3720692.6     10185086.12
#Sta/Elev= 30
  4394.2  296.82  4487.7  294.18  4522.6  291.96  4595.5  288.71  4626.6   288.6
  4653.8  286.38  4662.5  286.63  4749.1  283.31  4777.9  282.92    4814  281.82
  4865.8  281.55  4881.4  279.07  4887.2  279.97  4895.6  279.61  4902.8  281.11
  4908.6  280.65  4966.9  281.18  4969.9280.6749  4976.7  279.53  4982.5   279.6
  4995.6  277.14  4999.1  277.14  5010.6  280.69  5020.9  280.97  5031.2  279.89
  5052.5  279.67  5113.2  282.26  5256.9   286.1    5380  290.87  5405.9   293.3
#Mann= 4 ,-1 , 0
  4394.2     .17       0  4777.9     .11       0  4969.9     .06       0
  5010.6     .11       0
Bank Sta=4969.9,5010.6
XS Rating Curve= 0 ,0
Exp/Cntr=0.3,0.1

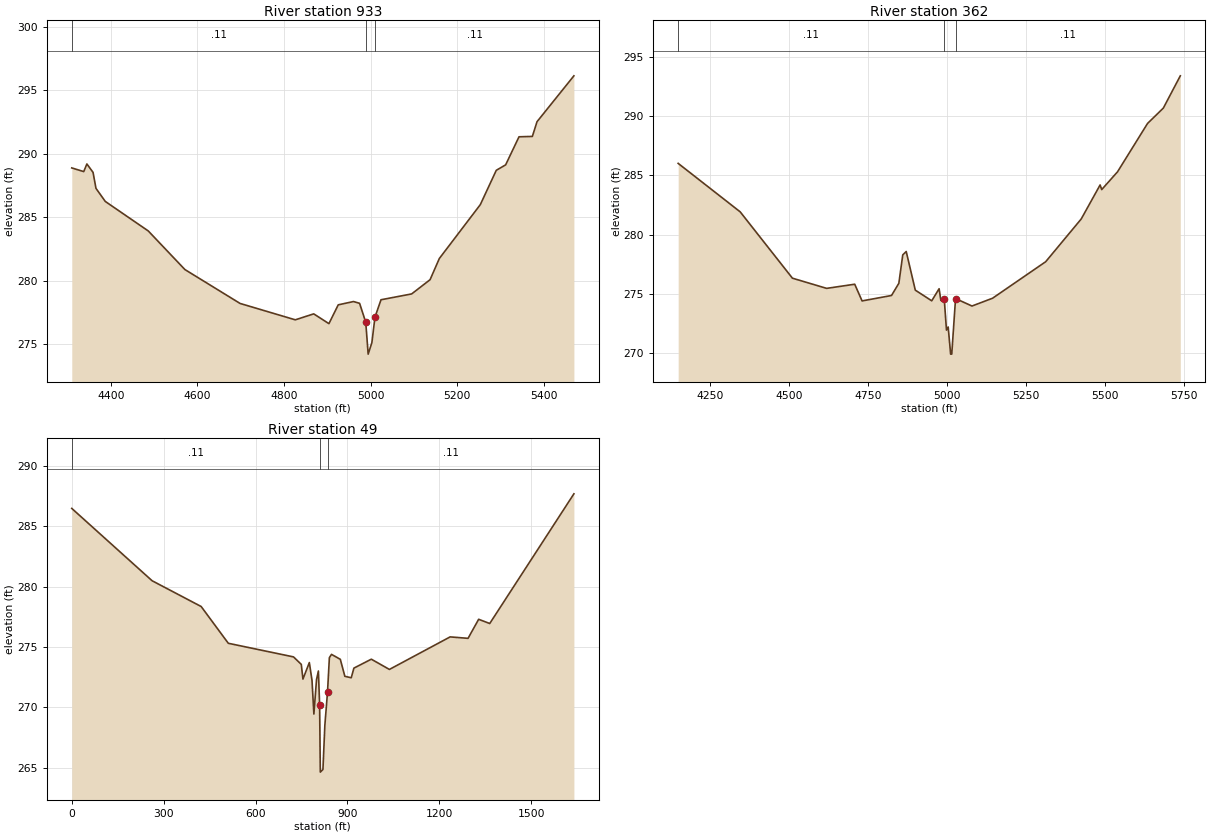
Type RM Length L Ch R = 1 ,933     ,571,571,571
BEGIN DESCRIPTION:
Mapping XS d842dedc
END DESCRIPTION:
XS GIS Cut Line= 3
      3721667.41      10185150.8      3720999.03     10184521.49
      3720764.65     10184465.06
#Sta/Elev= 30
    4310   288.9  4337.6  288.61  4344.9  289.21  4359.1  288.55  4365.9  287.29
  4387.4  286.26  4486.5  283.94  4571.1   280.9  4698.5  278.23    4826  276.94
  4868.5  277.41  4903.6  276.64  4925.1  278.12  4960.3  278.38  4974.4  278.24
  4988.6  276.75  4994.2  274.24  5002.8  275.15  5009.9  277.15  5023.8  278.52
  5094.6  278.98  5137.1   280.1  5158.5  281.77  5253.1  286.01  5289.9  288.71
  5311.5  289.14  5342.4  291.35  5373.2  291.38    5384  292.54  5469.1  296.15
#Mann= 3 , 0 , 0
    4310     .11       0  4988.6     .06       0  5009.9     .11       0
Bank Sta=4988.6,5009.9
XS Rating Curve= 0 ,0
Exp/Cntr=0.3,0.1

Type RM Length L Ch R = 1 ,362     ,313,313,313
BEGIN DESCRIPTION:
KIDHAW BRANCH TRIBUTARY NO. 1 1.0
END DESCRIPTION:
XS GIS Cut Line= 3
      3721797.66     10184990.27      3721402.68     10184100.48
      3720801.15     10183974.98
#Sta/Elev= 30
  4150.5  286.01  4346.6  281.92  4511.8  276.32  4620.1  275.46  4708.8  275.81
  4732.1   274.4  4825.2  274.86  4848.4  275.89  4860.8  278.29  4871.7  278.57
  4900.4  275.31  4952.4  274.41  4975.7  275.43  4981.2  274.44  4992.1  274.53
    4999  271.94  5004.4   272.2  5012.2  269.91  5015.7  269.91  5027.7   274.6
  5079.7  273.97  5144.9  274.63  5312.8  277.71  5425.2  281.32  5484.9  284.19
    5490   283.8    5540   285.3  5634.9  289.38  5684.9  290.68  5738.5   293.4
#Mann= 3 , 0 , 0
  4150.5     .11       0  4992.1     .06       0  5027.7     .11       0
Bank Sta=4992.1,5027.7
XS Rating Curve= 0 ,0
Exp/Cntr=0.3,0.1

Type RM Length L Ch R = 1 ,49      ,0,0,0
BEGIN DESCRIPTION:
KIDHAW BRANCH TRIBUTARY NO. 1 1.0
END DESCRIPTION:
XS GIS Cut Line= 4
      3721894.55     10185033.93      3721697.26     10184314.93
      3721567.39     10184130.21       3720988.3     10183796.95
#Sta/Elev= 30
       0   286.5   262.2   280.5   422.5  278.36   511.1  275.31     724  274.18
   749.4  273.56   754.8  272.34   775.7  273.71   784.4  272.23   790.5  269.44
   799.2  272.31   805.3  273.01  809.22  270.22   811.5  264.62   820.1  264.84
   826.3  268.49     835  271.25   841.1  274.12   848.1  274.39   876.8  273.98
   891.6  272.57   912.5  272.45   921.2  273.25   978.1  273.99  1037.1  273.14
  1235.4  275.84  1293.9  275.72  1328.5   277.3  1364.7  276.95  1639.5  287.71
#Mann= 3 , 0 , 0
       0     .11       0  809.22     .06       0     835     .11       0
Bank Sta=809.22,835
XS Rating Curve= 0 ,0
Exp/Cntr=0.3,0.1

Chan Stop Cuts=-1
Use User Specified Reach Order=0
Composite Channel Slope=5