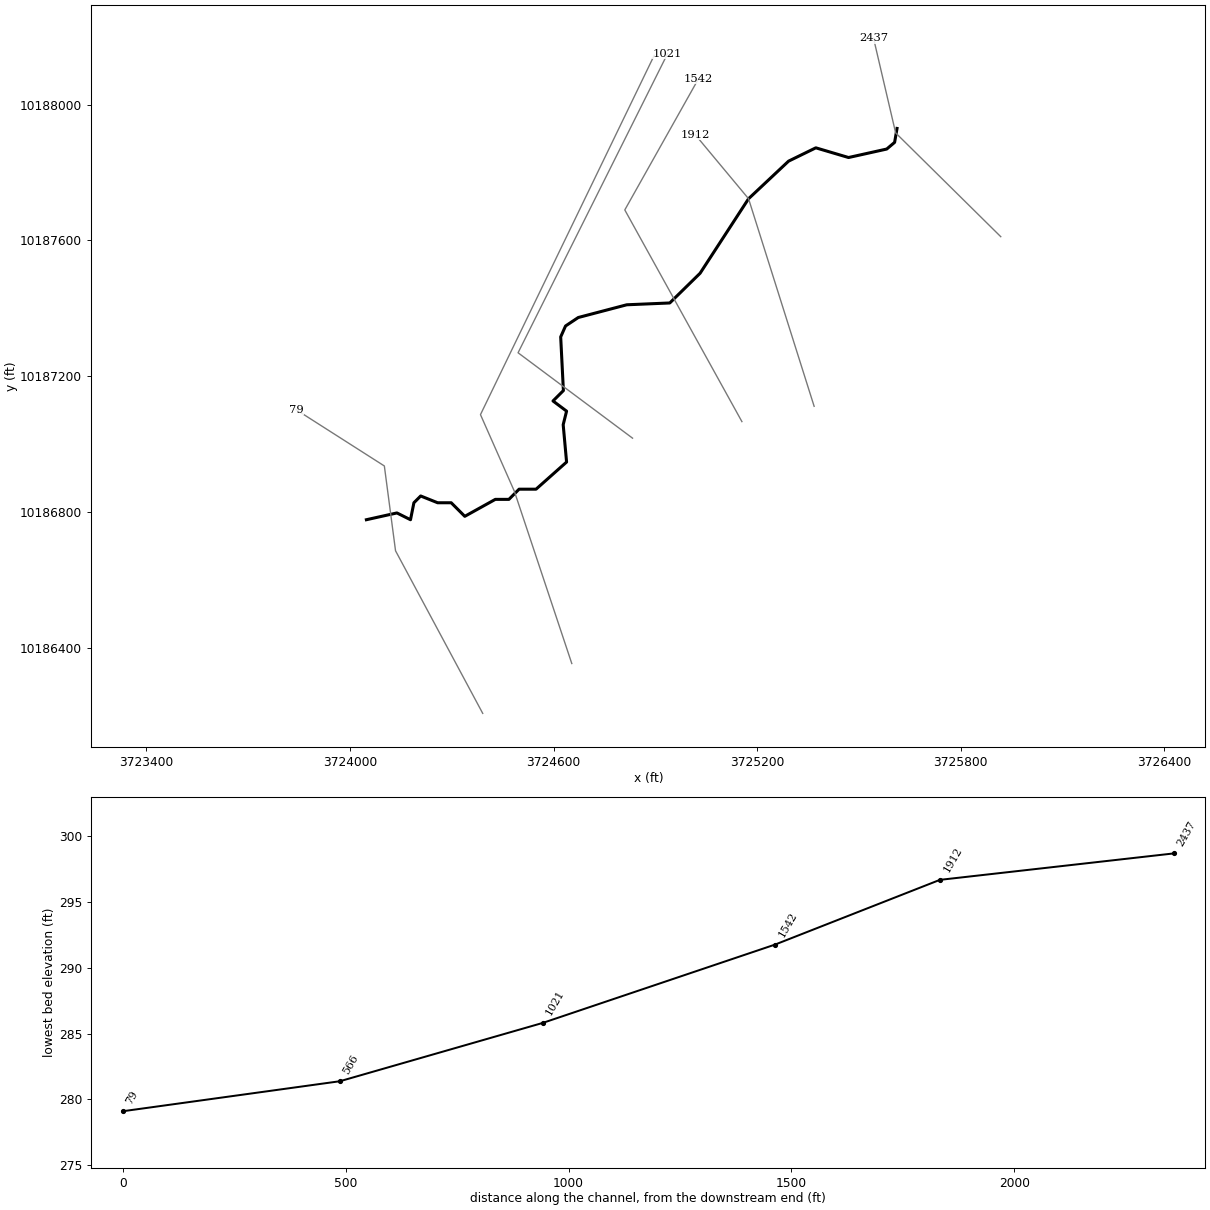
--- KIDHAW BRANCH TRIBUTARY NO 2.prj (project) ---

Proj Title=KIDHAW BRANCH TRIBUTARY NO 2 Base Level Engineering
Current Plan=p01
Default Exp/Contr=0.3,0.1
English Units
Geom File=g01
Flow File=f01
Flow File=f02
Plan File=p01
Y Axis Title=Elevation
X Axis Title(PF)=Main Channel Distance
X Axis Title(XS)=Station
BEGIN DESCRIPTION:
KIDHAW BRANCH TRIBUTARY NO 2
END DESCRIPTION:
DSS Export Rating Curves= 0
DSS Export Rating Curve Sorted= 0
DSS Export Volume Flow Curves= 0
DXF OffsetX= 0
DXF OffsetY= 0
DXF ScaleX= 1
DXF ScaleY= 10

--- KIDHAW BRANCH TRIBUTARY NO 2.p01 (plan) ---

Plan Title=Multiple Run
Short Identifier=Multiple
Geom File=g01
Flow File=f01
Subcritical Flow
K Sum by GR= 0
Std Step Tol= 0.01
Critical Tol= 0.01
Num of Std Step Trials= 20
Max Error Tol= 0.3
Flow Tol Ratio= 0.001
Split Flow NTrial= 30
Split Flow Tol= 0.02
Split Flow Ratio= 0.02
Log Output Level= 0
Friction Slope Method= 1
Unsteady Friction Slope Method= 2
Unsteady Bridges Friction Slope Method= 1
Parabolic Critical Depth
Global Vel Dist=  1 , 1 , 1
Global Log Level= 0
CheckData=True
Encroach Param= -1, 0, 0, 0
BEGIN DESCRIPTION:
Multiple Run
END DESCRIPTION:

--- KIDHAW BRANCH TRIBUTARY NO 2.f01 (steady flow) ---

Flow Title=Multiple
Program Version=4.10
Number of Profiles= 7
Profile Names=10-year,25-year,50-year,1pct_min,100-year,1pct_plu,500-year
River Rch & RM=KIDHAW BRANCH TR,Reach-1         ,2437
     686     940    1281     575    1736    5243    3292
River Rch & RM=KIDHAW BRANCH TR,Reach-1         ,79
    1200    1692    2349    1071    3233    9764    6343
Boundary for River Rch & Prof#=KIDHAW BRANCH TR,Reach-1         , 1
Up Type= 0
Dn Type= 3
Dn Slope=0.005
Boundary for River Rch & Prof#=KIDHAW BRANCH TR,Reach-1         , 2
Up Type= 0
Dn Type= 3
Dn Slope=0.005
Boundary for River Rch & Prof#=KIDHAW BRANCH TR,Reach-1         , 3
Up Type= 0
Dn Type= 3
Dn Slope=0.005
Boundary for River Rch & Prof#=KIDHAW BRANCH TR,Reach-1         , 4
Up Type= 0
Dn Type= 3
Dn Slope=0.005
Boundary for River Rch & Prof#=KIDHAW BRANCH TR,Reach-1         , 5
Up Type= 0
Dn Type= 3
Dn Slope=0.005
Boundary for River Rch & Prof#=KIDHAW BRANCH TR,Reach-1         , 6
Up Type= 0
Dn Type= 3
Dn Slope=0.005
Boundary for River Rch & Prof#=KIDHAW BRANCH TR,Reach-1         , 7
Up Type= 0
Dn Type= 3
Dn Slope=0.005
DSS Import GetInterval= 0
DSS Import GetPeak= 0
DSS Import FillOption= 0

--- KIDHAW BRANCH TRIBUTARY NO 2.f02 (steady flow) ---

Flow Title=Orig_BLE_Flows
Program Version=4.10
Number of Profiles= 7
Profile Names=10-year,25-year,50-year,1pct_min,100-year,1pct_plu,500-year
River Rch & RM=KIDHAW BRANCH TR,Reach-1         ,2437
     686     922    1114     442    1335    4030    1914
River Rch & RM=KIDHAW BRANCH TR,Reach-1         ,79
    1200    1659    2043     824    2487    7512    3688
Boundary for River Rch & Prof#=KIDHAW BRANCH TR,Reach-1         , 1
Up Type= 0
Dn Type= 3
Dn Slope=0.005
Boundary for River Rch & Prof#=KIDHAW BRANCH TR,Reach-1         , 2
Up Type= 0
Dn Type= 3
Dn Slope=0.005
Boundary for River Rch & Prof#=KIDHAW BRANCH TR,Reach-1         , 3
Up Type= 0
Dn Type= 3
Dn Slope=0.005
Boundary for River Rch & Prof#=KIDHAW BRANCH TR,Reach-1         , 4
Up Type= 0
Dn Type= 3
Dn Slope=0.005
Boundary for River Rch & Prof#=KIDHAW BRANCH TR,Reach-1         , 5
Up Type= 0
Dn Type= 3
Dn Slope=0.005
Boundary for River Rch & Prof#=KIDHAW BRANCH TR,Reach-1         , 6
Up Type= 0
Dn Type= 3
Dn Slope=0.005
Boundary for River Rch & Prof#=KIDHAW BRANCH TR,Reach-1         , 7
Up Type= 0
Dn Type= 3
Dn Slope=0.005
DSS Import GetInterval= 0
DSS Import GetPeak= 0
DSS Import FillOption= 0

--- KIDHAW BRANCH TRIBUTARY NO 2.g01 (geometry) ---

Geom Title=Existing Conditions
Program Version=4.10

River Reach=KIDHAW BRANCH TR,Reach-1
Reach XY= 30
      3725612.16     10187930.08      3725605.02       10187889.
       3725581.8     10187869.35      3725469.27     10187844.35
      3725372.82     10187872.92      3725292.45     10187833.63
      3725174.56     10187722.89      3725031.68      10187503.2
      3724942.37     10187415.68      3724815.56     10187410.32
      3724672.67     10187372.81      3724635.16     10187347.81
      3724620.87     10187315.66      3724628.84     10187157.45
      3724598.23     10187126.84      3724638.23     10187096.84
      3724628.23     10187056.84      3724638.23     10186946.84
      3724548.23     10186866.84      3724498.23     10186866.84
      3724468.23     10186836.84      3724428.23     10186836.84
      3724338.23     10186786.84      3724298.23     10186826.84
      3724258.23     10186826.84      3724208.23     10186846.84
      3724188.23     10186826.84      3724178.23     10186776.84
      3724138.23     10186796.84      3724048.23     10186776.84

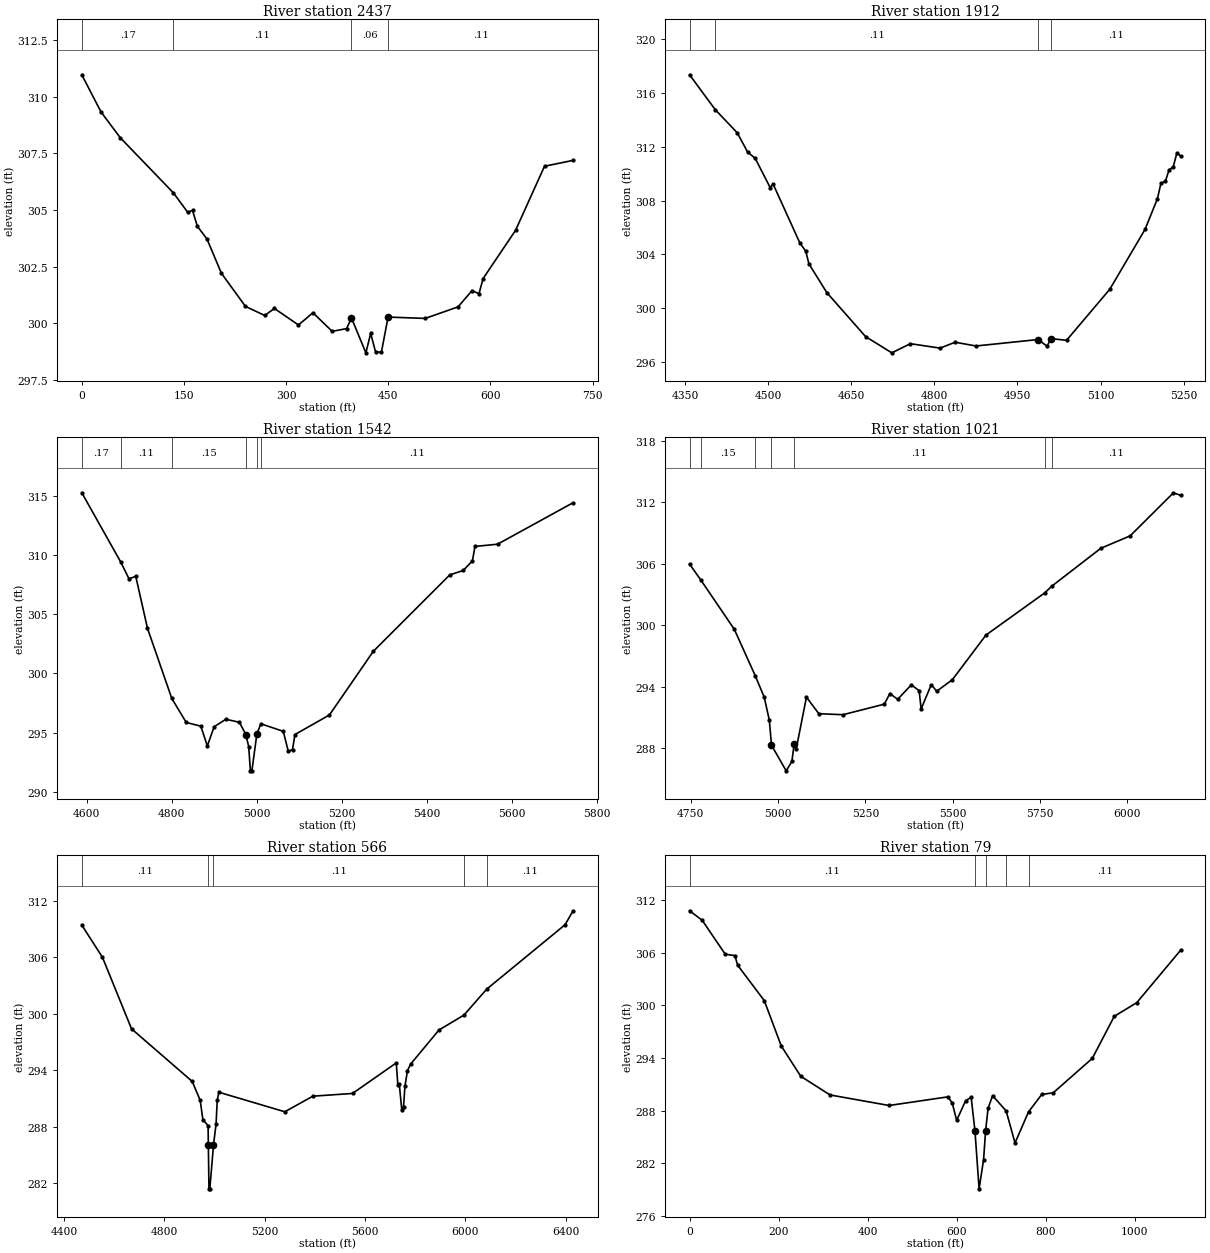
Type RM Length L Ch R = 1 ,2437    ,525,525,525
BEGIN DESCRIPTION:
KIDHAW BRANCH TRIBUTARY NO. 2 3.0
END DESCRIPTION:
XS GIS Cut Line= 3
      3725917.85     10187611.07      3725608.07     10187916.98
      3725542.97     10188195.62
#Sta/Elev= 30
       0  310.97    28.2  309.33    56.5  308.19   134.4  305.76   155.5   304.9
   162.6  304.98   169.7  304.28   183.8  303.72   205.1   302.2   240.4  300.74
   268.7  300.34   282.8  300.65   318.2  299.92   339.4  300.46   367.7  299.64
   388.9  299.76     396  300.23   417.2  298.69   424.2  299.55   431.4  298.73
     440  298.72   449.8  300.27   504.3  300.21   552.5  300.72   573.1  301.44
   583.3   301.3   589.3  301.97     637   304.1   679.5  306.93   721.5  307.19
#Mann= 4 ,-1 , 0
       0     .17       0   134.4     .11       0     396     .06       0
   449.8     .11       0
Bank Sta=396,449.8
XS Rating Curve= 0 ,0
Exp/Cntr=0.3,0.1

Type RM Length L Ch R = 1 ,1912    ,370,370,370
BEGIN DESCRIPTION:
KIDHAW BRANCH TRIBUTARY NO. 2 2.0
END DESCRIPTION:
XS GIS Cut Line= 3
      3725367.84      10187111.1      3725174.56     10187722.89
      3725017.84     10187911.08
#Sta/Elev= 30
  4358.4  317.36  4404.9  314.76  4444.4  313.05  4463.2  311.61  4476.8  311.15
  4503.9  308.97  4509.1  309.24  4557.6  304.84  4568.1  304.24  4573.8   303.3
  4606.1  301.16    4676  297.89  4723.4  296.68  4756.9  297.36  4810.5  297.03
  4837.6  297.47  4875.2  297.19  4987.6  297.67  5003.4  297.17  5010.6  297.74
  5038.6  297.61  5116.7  301.41  5180.4  305.87  5202.6  308.14  5209.1  309.31
  5216.9  309.43  5223.4  310.26  5231.2  310.52  5237.7  311.54  5244.9   311.3
#Mann= 4 ,-1 , 0
  4358.4     .17       0  4404.9     .11       0  4987.6     .06       0
  5010.6     .11       0
Bank Sta=4987.6,5010.6
XS Rating Curve= 0 ,0
Exp/Cntr=0.3,0.1

Type RM Length L Ch R = 1 ,1542    ,521,521,521
BEGIN DESCRIPTION:
Mapping XS 1b87fd03
END DESCRIPTION:
XS GIS Cut Line= 3
      3725154.97     10187066.01       3724809.8     10187689.89
      3725026.77     10188076.11
#Sta/Elev= 30
  4588.4  315.28  4679.9  309.43  4699.4  308.01  4715.4  308.21  4742.9  303.82
  4800.2  297.88  4834.2  295.85  4868.5  295.54  4883.8  293.86  4899.8  295.49
  4927.3  296.12  4959.4  295.87  4974.6294.8049  4981.1  293.81  4985.1  291.76
  4988.6  291.76  5000.4294.8873  5009.8  295.74  5062.5   295.1  5074.2  293.41
  5084.2  293.56  5089.9  294.83  5171.2  296.49  5274.3  301.87  5454.1  308.33
    5486  308.71  5507.6  309.53  5513.4  310.74  5566.6  310.93  5744.4  314.44
#Mann= 6 ,-1 , 0
  4588.4     .17       0  4679.9     .11       0  4800.2     .15       0
  4974.6     .09       0  5000.4     .15       0  5009.8     .11       0
Bank Sta=4974.6,5000.4
XS Rating Curve= 0 ,0
Exp/Cntr=0.3,0.1

Type RM Length L Ch R = 1 ,1021    ,455,455,455
BEGIN DESCRIPTION:
Mapping XS b905e557
END DESCRIPTION:
XS GIS Cut Line= 3
      3724832.67     10187017.21      3724495.25     10187268.92
      3724935.68       10188150.
#Sta/Elev= 30
  4746.7  305.96  4778.2  304.45  4874.9   299.6  4934.4   295.1  4960.4  292.99
    4975  290.75  4981.2  288.31  5023.3  285.81  5039.6  286.73  5045.9  288.39
  5052.1  287.97  5081.3  292.99  5116.7  291.38  5185.8  291.28  5304.2  292.31
  5319.9  293.34  5342.3  292.78  5381.4  294.19  5403.8  293.62  5409.4  291.84
  5438.4  294.21  5454.1  293.57  5498.8  294.69  5594.9  299.04  5763.5  303.16
    5783   303.8  5923.7   307.5  6007.6  308.71  6131.5  312.91  6152.7  312.65
#Mann= 7 ,-1 , 0
  4746.7     .11       0  4778.2     .15       0  4934.4     .11       0
  4981.2     .06       0  5045.9     .11       0  5763.5     .15       0
    5783     .11       0
Bank Sta=4981.2,5045.9
XS Rating Curve= 0 ,0
Exp/Cntr=0.3,0.1

Type RM Length L Ch R = 1 ,566     ,487,487,487
BEGIN DESCRIPTION:
KIDHAW BRANCH TRIBUTARY NO. 2 1.0
END DESCRIPTION:
XS GIS Cut Line= 4
      3724653.56     10186353.04      3724484.28      10186860.9
      3724384.45     10187086.59      3724896.61     10188145.63
#Sta/Elev= 30
    4471  309.45  4553.3  306.02  4669.2  298.41  4911.2  292.81  4942.8  290.81
  4953.8  288.75  4974.4   288.1 4975.47286.0828  4977.9  281.38  4981.4  281.38
    4996  286.05  5006.3  288.27  5010.9   290.8  5017.5  291.66  5280.3  289.58
  5392.1  291.24  5550.2  291.53  5724.6  294.78    5731   292.4  5736.5  292.54
  5746.8  289.73  5753.6  290.13  5759.1  292.28  5769.1  293.95  5781.7  294.65
  5894.7  298.28  5994.5  299.87    6085  302.63  6397.3  309.48  6429.5  310.97
#Mann= 5 ,-1 , 0
    4471     .11       0 4975.47     .06       0    4996     .11       0
  5994.5     .15       0    6085     .11       0
Bank Sta=4975.47,4996
XS Rating Curve= 0 ,0
Exp/Cntr=0.3,0.1

Type RM Length L Ch R = 1 ,79      ,0,0,0
BEGIN DESCRIPTION:
KIDHAW BRANCH TRIBUTARY NO. 2 1.0
END DESCRIPTION:
XS GIS Cut Line= 4
      3724391.08      10186206.1      3724134.13     10186685.27
      3724101.15     10186935.27      3723840.63      10187101.5
#Sta/Elev= 30
       0  310.76    28.3  309.69    80.1  305.82   102.1  305.65   107.8  304.58
   167.9  300.53     206  295.37   249.9  291.91   315.7  289.79   448.2  288.59
   579.8  289.57   589.9  288.91     600   286.9   620.2  289.14   632.6  289.52
   641.1  285.71   650.4   279.1   660.5  282.43  665.01  285.71   670.6  288.27
   680.7  289.71   711.2  287.97   731.1  284.32   761.4  287.86   791.2  289.85
   816.8  290.03   904.8  293.96     954  298.74  1004.6   300.3  1103.6   306.3
#Mann= 5 ,-1 , 0
       0     .11       0   641.1     .06       0  665.01     .11       0
   711.2     .08       0   761.4     .11       0
Bank Sta=641.1,665.01
XS Rating Curve= 0 ,0
Exp/Cntr=0.3,0.1

Chan Stop Cuts=-1
Use User Specified Reach Order=0
Composite Channel Slope=5