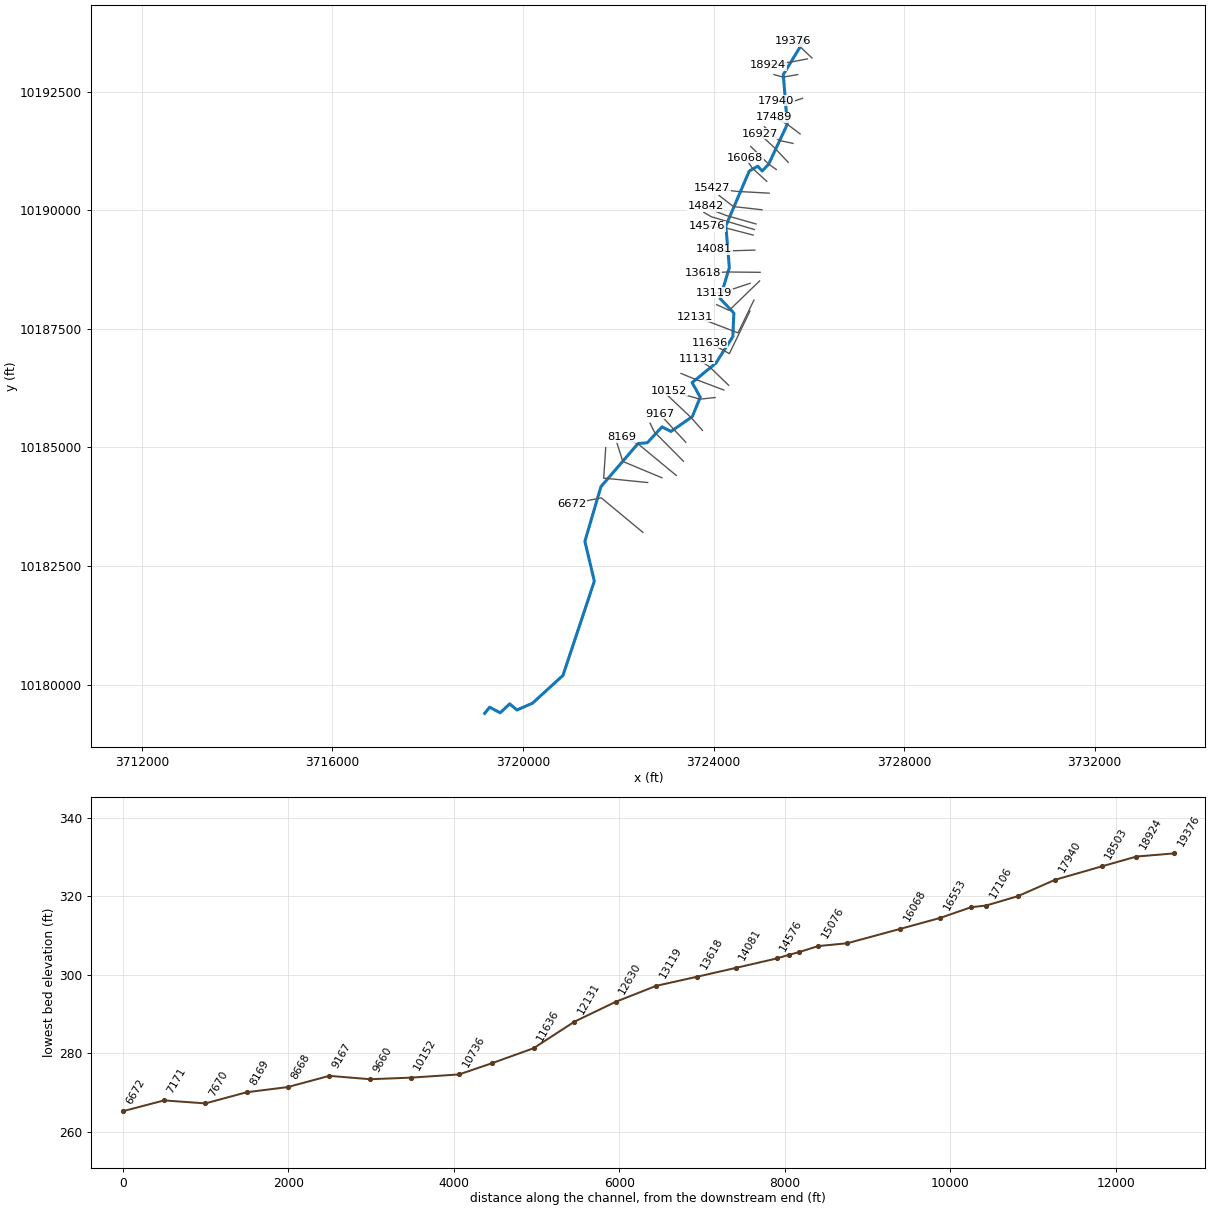
--- KIDHAW BRANCH.prj (project) ---

Proj Title=KIDHAW BRANCH Base Level Engineering
Current Plan=p01
Default Exp/Contr=0.3,0.1
English Units
Geom File=g01
Flow File=f01
Flow File=f02
Plan File=p01
Y Axis Title=Elevation
X Axis Title(PF)=Main Channel Distance
X Axis Title(XS)=Station
BEGIN DESCRIPTION:
KIDHAW BRANCH
END DESCRIPTION:
DSS Export Rating Curves= 0
DSS Export Rating Curve Sorted= 0
DSS Export Volume Flow Curves= 0
DXF OffsetX= 0
DXF OffsetY= 0
DXF ScaleX= 1
DXF ScaleY= 10

--- KIDHAW BRANCH.p01 (plan) ---

Plan Title=Multiple Run
Short Identifier=Multiple
Geom File=g01
Flow File=f01
Subcritical Flow
K Sum by GR= 0
Std Step Tol= 0.01
Critical Tol= 0.01
Num of Std Step Trials= 20
Max Error Tol= 0.3
Flow Tol Ratio= 0.001
Split Flow NTrial= 30
Split Flow Tol= 0.02
Split Flow Ratio= 0.02
Log Output Level= 0
Friction Slope Method= 1
Unsteady Friction Slope Method= 2
Unsteady Bridges Friction Slope Method= 1
Parabolic Critical Depth
Global Vel Dist=  1 , 1 , 1
Global Log Level= 0
CheckData=True
Encroach Param= -1, 0, 0, 0
BEGIN DESCRIPTION:
Multiple Run
END DESCRIPTION:

--- KIDHAW BRANCH.f01 (steady flow) ---

Flow Title=Multiple
Program Version=4.10
Number of Profiles= 7
Profile Names=10-year,25-year,50-year,1pct_min,100-year,1pct_plu,500-year
River Rch & RM=KIDHAW BRANCH,Reach-1         ,19376
     574     775    1047     465    1403    4237    2611
River Rch & RM=KIDHAW BRANCH,Reach-1         ,15427
     690     940    1277     570    1720    5194    3232
River Rch & RM=KIDHAW BRANCH,Reach-1         ,11131
    1200    1692    2349    1071    3233    9764    6343
River Rch & RM=KIDHAW BRANCH,Reach-1         ,9167
    1063    1475    2026     913    2757    8326    5287
River Rch & RM=KIDHAW BRANCH,Reach-1         ,6672
    1733    2471    3456    1583    4781   14438    9481
Boundary for River Rch & Prof#=KIDHAW BRANCH,Reach-1         , 1
Up Type= 0
Dn Type= 3
Dn Slope=0.005
Boundary for River Rch & Prof#=KIDHAW BRANCH,Reach-1         , 2
Up Type= 0
Dn Type= 3
Dn Slope=0.005
Boundary for River Rch & Prof#=KIDHAW BRANCH,Reach-1         , 3
Up Type= 0
Dn Type= 3
Dn Slope=0.005
Boundary for River Rch & Prof#=KIDHAW BRANCH,Reach-1         , 4
Up Type= 0
Dn Type= 3
Dn Slope=0.005
Boundary for River Rch & Prof#=KIDHAW BRANCH,Reach-1         , 5
Up Type= 0
Dn Type= 3
Dn Slope=0.005
Boundary for River Rch & Prof#=KIDHAW BRANCH,Reach-1         , 6
Up Type= 0
Dn Type= 3
Dn Slope=0.005
Boundary for River Rch & Prof#=KIDHAW BRANCH,Reach-1         , 7
Up Type= 0
Dn Type= 3
Dn Slope=0.005
DSS Import GetInterval= 0
DSS Import GetPeak= 0
DSS Import FillOption= 0

--- KIDHAW BRANCH.f02 (steady flow) ---

Flow Title=Orig_BLE_Flows
Program Version=4.10
Number of Profiles= 7
Profile Names=10-year,25-year,50-year,1pct_min,100-year,1pct_plu,500-year
River Rch & RM=KIDHAW BRANCH,Reach-1         ,19376
     574     760     910     357    1079    3260    1518
River Rch & RM=KIDHAW BRANCH,Reach-1         ,15427
     690     922    1110     438    1323    3996    1879
River Rch & RM=KIDHAW BRANCH,Reach-1         ,11131
    1200    1659    2043     824    2487    7512    3688
River Rch & RM=KIDHAW BRANCH,Reach-1         ,9167
    1063    1446    1762     702    2121    6406    3074
River Rch & RM=KIDHAW BRANCH,Reach-1         ,6672
    1733    2423    3005    1218    3678   11107    5512
Boundary for River Rch & Prof#=KIDHAW BRANCH,Reach-1         , 1
Up Type= 0
Dn Type= 3
Dn Slope=0.005
Boundary for River Rch & Prof#=KIDHAW BRANCH,Reach-1         , 2
Up Type= 0
Dn Type= 3
Dn Slope=0.005
Boundary for River Rch & Prof#=KIDHAW BRANCH,Reach-1         , 3
Up Type= 0
Dn Type= 3
Dn Slope=0.005
Boundary for River Rch & Prof#=KIDHAW BRANCH,Reach-1         , 4
Up Type= 0
Dn Type= 3
Dn Slope=0.005
Boundary for River Rch & Prof#=KIDHAW BRANCH,Reach-1         , 5
Up Type= 0
Dn Type= 3
Dn Slope=0.005
Boundary for River Rch & Prof#=KIDHAW BRANCH,Reach-1         , 6
Up Type= 0
Dn Type= 3
Dn Slope=0.005
Boundary for River Rch & Prof#=KIDHAW BRANCH,Reach-1         , 7
Up Type= 0
Dn Type= 3
Dn Slope=0.005
DSS Import GetInterval= 0
DSS Import GetPeak= 0
DSS Import FillOption= 0

--- KIDHAW BRANCH.g01 (geometry) ---

Geom Title=Existing Conditions
Program Version=4.10

River Reach=KIDHAW BRANCH   ,Reach-1
Reach XY= 30
      3725928.02     10193625.16       3725465.2     10192860.93
      3725549.01      10191813.7      3725158.09     10190972.52
      3725022.38     10190829.67       3724928.1     10190929.66
      3724749.55     10190826.81      3724259.33     10189673.52
      3724332.44     10188794.13      3724137.93      10188141.8
      3724426.86     10187834.39      3724405.95     10187336.85
      3724048.23     10186776.84      3723550.82     10186367.73
      3723721.06     10186060.06      3723555.36     10185651.53
      3723106.51     10185338.17      3722918.27     10185434.76
      3722611.42     10185100.91      3722414.29     10185082.18
       3721636.5     10184174.45      3721299.65     10183022.58
      3721497.53     10182181.99        3720839.     10180195.39
      3720199.79     10179609.75      3719872.93     10179466.65
      3719721.56     10179595.86      3719520.41     10179407.17
      3719300.32     10179525.19      3719196.21     10179395.12

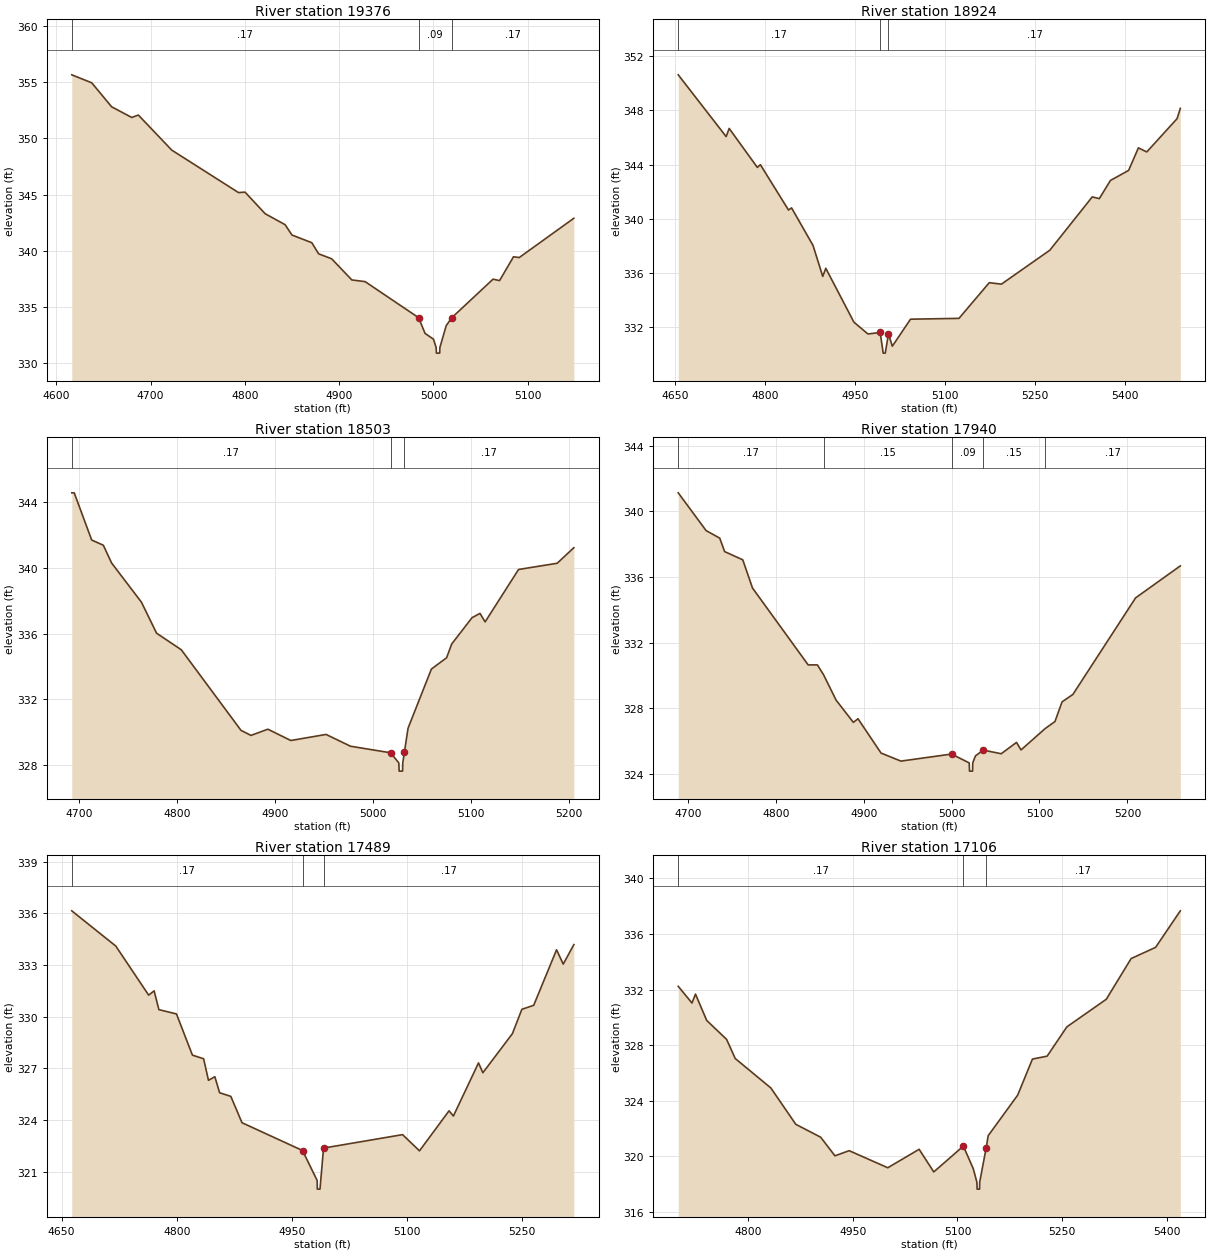
Type RM Length L Ch R = 1 ,19376   ,452,452,452
BEGIN DESCRIPTION:
KIDHAW BRANCH 40.0
END DESCRIPTION:
XS GIS Cut Line= 3
      3726067.83     10193211.09      3725789.46     10193475.17
      3725667.84     10193561.08
#Sta/Elev= 30
  4616.3  355.63  4637.5  354.92  4658.6  352.79    4680  351.84  4686.9  352.06
  4722.4  348.94  4793.2  345.17  4800.1  345.21  4821.5  343.29  4842.6  342.32
  4849.9   341.4  4870.9  340.72  4878.2  339.73    4892  339.29  4913.4  337.41
  4927.5  337.26  4984.2  334.06  4991.1  332.66    5000  332.15  5002.8  331.41
  5003.1  330.91  5006.6  330.91  5006.8  331.41  5013.5  333.35  5019.6  334.07
  5063.2  337.48  5070.1  337.35  5084.9  339.47    5091   339.4  5148.9  342.89
#Mann= 3 , 0 , 0
  4616.3     .17       0  4984.2     .09       0  5019.6     .17       0
Bank Sta=4984.2,5019.6
XS Rating Curve= 0 ,0
Exp/Cntr=0.3,0.1

Type RM Length L Ch R = 1 ,18924   ,421,421,421
BEGIN DESCRIPTION:
KIDHAW BRANCH 39.0
END DESCRIPTION:
XS GIS Cut Line= 3
       3725968.6     10193191.62      3725629.47     10193126.63
      3725142.53     10193056.25
#Sta/Elev= 30
  4654.7  350.61  4734.6  346.06  4739.7  346.66  4786.6  343.79  4791.7  343.99
  4838.6  340.65  4843.7  340.81  4879.5  338.04  4895.7  335.76  4900.8  336.36
  4947.7  332.39  4971.1  331.52  4991.5  331.63  4996.5  330.11    5000  330.11
  5005.3  331.53  5011.7  330.62  5042.1  332.61  5122.9  332.67  5173.4   335.3
  5193.6  335.19  5274.4  337.69  5345.2  341.62  5356.9  341.49  5375.5  342.83
  5405.8  343.57  5422.1  345.23  5436.1  344.93  5486.6  347.38    5492  348.14
#Mann= 3 , 0 , 0
  4654.7     .17       0  4991.5     .09       0  5005.3     .17       0
Bank Sta=4991.5,5005.3
XS Rating Curve= 0 ,0
Exp/Cntr=0.3,0.1

Type RM Length L Ch R = 1 ,18503   ,563,563,563
BEGIN DESCRIPTION:
KIDHAW BRANCH 38.0
END DESCRIPTION:
XS GIS Cut Line= 3
      3725767.86     10192861.07      3725460.84     10192807.08
      3725267.88     10192861.06
#Sta/Elev= 30
  4692.7  344.59  4695.2  344.59    4713  341.71  4724.9  341.39  4733.3  340.31
  4763.8  337.91  4779.2  336.02  4804.4  335.01  4865.3  330.09  4875.5  329.78
  4892.7  330.16  4916.1  329.47  4952.1  329.84    4977  329.12  5017.9  328.72
  5026.3   328.1  5026.6   327.6  5030.1   327.6  5030.3   328.1    5032328.7674
  5035.7  330.22  5059.5  333.83    5075  334.52  5080.2  335.36    5101  336.97
  5109.1  337.23  5114.3  336.71  5148.4  339.91  5187.8  340.29  5204.8  341.24
#Mann= 3 , 0 , 0
  4692.7     .17       0  5017.9     .09       0    5032     .17       0
Bank Sta=5017.9,5032
XS Rating Curve= 0 ,0
Exp/Cntr=0.3,0.1

Type RM Length L Ch R = 1 ,17940   ,451,451,451
BEGIN DESCRIPTION:
KIDHAW BRANCH 37.0
END DESCRIPTION:
XS GIS Cut Line= 3
      3725867.88     10192361.08      3725573.32     10192261.62
      3725317.86     10192311.07
#Sta/Elev= 30
  4689.1  341.13  4720.8  338.83  4736.3  338.37  4741.9  337.55  4762.5  337.05
  4773.6  335.33  4836.9  330.65  4847.4  330.65  4854.5  330.04  4868.6  328.51
  4888.3  327.15  4893.6  327.37  4919.8  325.28  4942.4  324.79    5000  325.22
  5020.1  324.68  5020.4  324.18  5023.9  324.18  5024.1  324.68  5027.2  325.11
  5036.1  325.46  5056.5  325.24  5073.9  325.93    5079  325.47  5106.2  326.76
  5117.6   327.2  5125.7   328.4    5138  328.85  5209.3  334.73  5260.2  336.68
#Mann= 5 ,-1 , 0
  4689.1     .17       0  4854.5     .15       0    5000     .09       0
  5036.1     .15       0  5106.2     .17       0
Bank Sta=5000,5036.1
XS Rating Curve= 0 ,0
Exp/Cntr=0.3,0.1

Type RM Length L Ch R = 1 ,17489   ,383,383,383
BEGIN DESCRIPTION:
KIDHAW BRANCH 36.0
END DESCRIPTION:
XS GIS Cut Line= 3
      3725817.89     10191611.04      3725549.01      10191813.7
      3725267.89     10191961.05
#Sta/Elev= 30
  4663.3  336.14  4720.6   334.1  4763.5  331.25  4770.6   331.5  4776.8  330.41
  4799.7  330.16  4820.5  327.77  4835.1  327.56  4841.4  326.31  4849.7  326.52
  4855.9  325.59  4870.5  325.38  4885.1  323.85  4963.9  322.24    4983   320.5
  4983.2     320  4986.7     320  4991.3  322.38  5094.3  323.16  5116.3  322.22
  5154.8  324.54  5160.5  324.24  5193.2  327.32  5198.9  326.75  5237.4  329.02
  5249.7  330.43  5265.1  330.66  5294.9  333.88  5303.6  333.05  5317.4  334.18
#Mann= 3 , 0 , 0
  4663.3     .17       0  4963.9     .09       0  4991.3     .17       0
Bank Sta=4963.9,4991.3
XS Rating Curve= 0 ,0
Exp/Cntr=0.3,0.1

Type RM Length L Ch R = 1 ,17106   ,179,179,179
BEGIN DESCRIPTION:
KIDHAW BRANCH 35.0
END DESCRIPTION:
XS GIS Cut Line= 3
      3725667.83     10191411.08      3725373.66     10191473.42
      3725067.88     10191761.05
#Sta/Elev= 30
  4699.3  332.23    4719  331.03  4724.1  331.67  4740.2  329.77  4768.7  328.41
  4781.1  327.03  4832.2  324.91    4868  322.29  4903.7  321.36  4924.2  320.02
  4944.6  320.39    5000  319.16    5045  320.49    5066  318.86  5108.5  320.72
  5122.7  319.09  5127.9  318.12  5128.2  317.62  5131.7  317.62  5131.9  318.12
 5141.25320.6033  5144.1  321.47  5186.4  324.39  5207.6  326.99  5228.7   327.2
    5257  329.31  5313.6   331.3  5349.2  334.23  5384.4  335.04  5419.8  337.67
#Mann= 3 , 0 , 0
  4699.3     .17       0  5108.5     .09       0 5141.25     .17       0
Bank Sta=5108.5,5141.25
XS Rating Curve= 0 ,0
Exp/Cntr=0.3,0.1

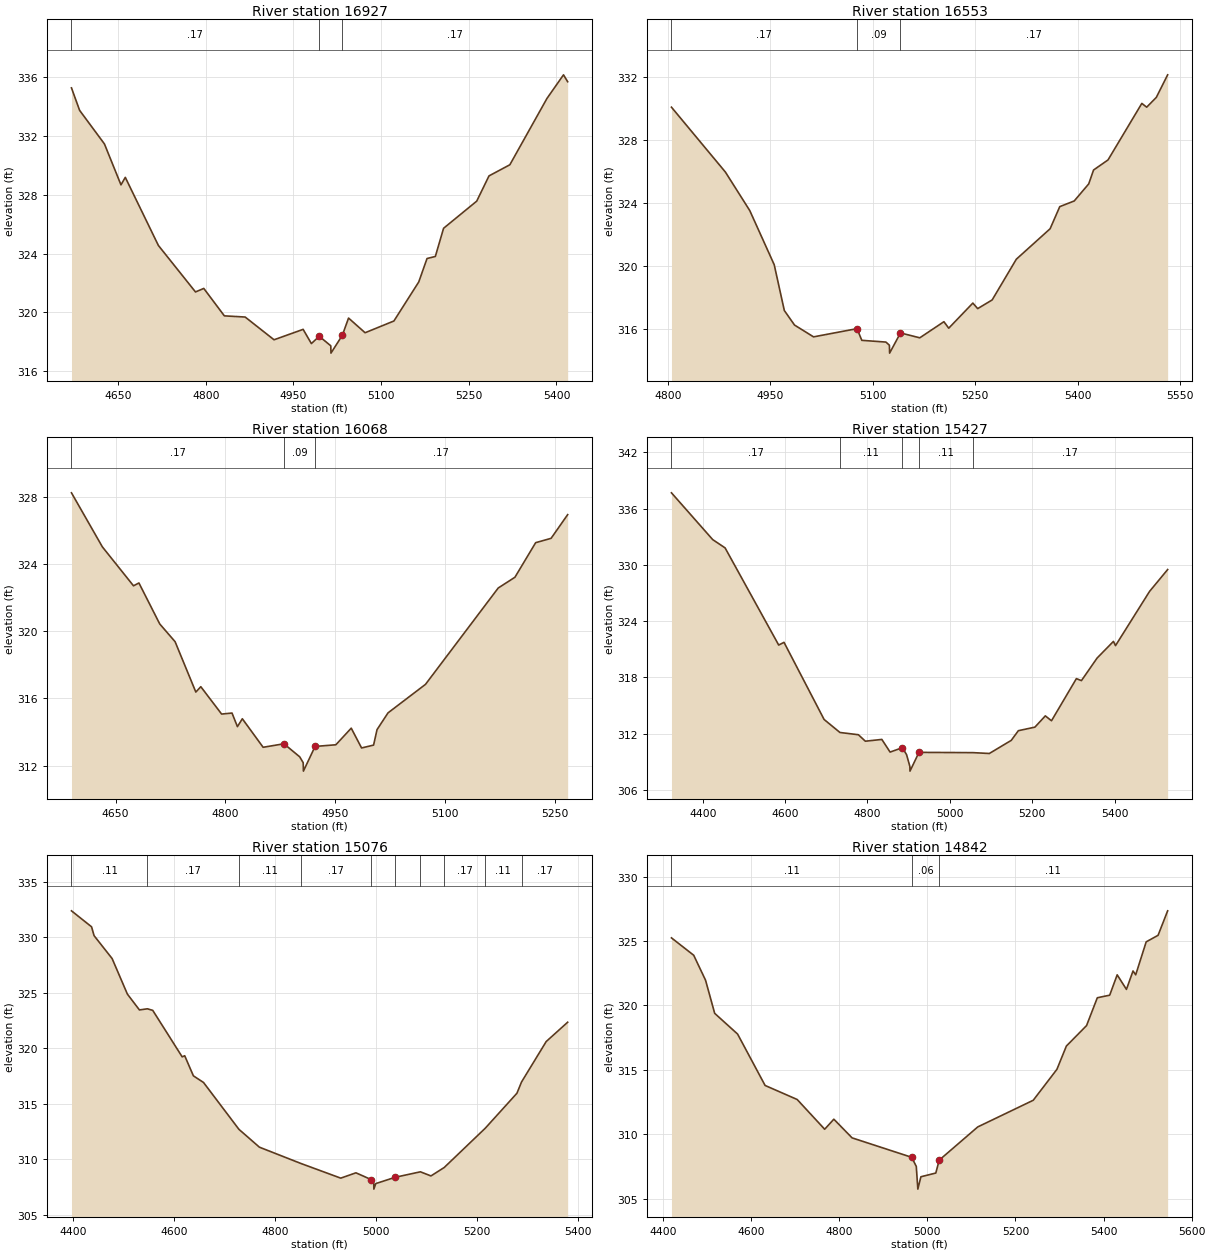
Type RM Length L Ch R = 1 ,16927   ,374,374,374
BEGIN DESCRIPTION:
KIDHAW BRANCH 34.0
END DESCRIPTION:
XS GIS Cut Line= 3
      3725567.84     10191011.08      3725273.95     10191324.69
      3724967.83     10191611.09
#Sta/Elev= 30
  4570.2  335.29  4584.1  333.76  4626.6  331.47  4654.9  328.68  4662.3  329.19
  4718.9  324.55  4782.4  321.38  4796.6  321.62  4831.8  319.75  4867.4  319.67
  4916.8  318.12  4966.6  318.83  4980.7  317.86  4994.1  318.36  5013.9  317.71
  5014.2  317.21 5033.71318.4291  5044.3   319.6  5072.6   318.6  5121.9   319.4
  5164.4  322.06  5178.6  323.66  5192.8   323.8  5206.9  325.72  5263.6  327.57
  5284.6  329.29  5320.3  330.05  5383.8  334.57  5412.1  336.18  5419.2  335.71
#Mann= 3 , 0 , 0
  4570.2     .17       0  4994.1     .09       0 5033.71     .17       0
Bank Sta=4994.1,5033.71
XS Rating Curve= 0 ,0
Exp/Cntr=0.3,0.1

Type RM Length L Ch R = 1 ,16553   ,485,485,485
BEGIN DESCRIPTION:
KIDHAW BRANCH 33.0
END DESCRIPTION:
XS GIS Cut Line= 3
      3725317.86     10190861.07      3725158.09     10190972.52
      3724780.76     10191347.41
#Sta/Elev= 30
  4805.2  330.06  4884.2  325.95  4919.9  323.51  4955.7  320.08  4970.5  317.18
  4985.4  316.26  5013.3  315.51  5076.9  316.03    5084  315.29  5119.3  315.18
  5124.4  314.98  5124.7  314.48  5140.6  315.76  5168.9  315.45  5204.2  316.47
  5211.3  316.06  5246.6  317.65  5253.7   317.3  5274.9  317.85  5310.3  320.43
  5359.8  322.36  5373.9  323.76  5395.1  324.12  5416.3   325.2  5423.4  326.08
  5444.6  326.72  5494.1   330.3  5501.2  330.06  5515.3  330.68  5531.9  332.11
#Mann= 3 , 0 , 0
  4805.2     .17       0  5076.9     .09       0  5140.6     .17       0
Bank Sta=5076.9,5140.6
XS Rating Curve= 0 ,0
Exp/Cntr=0.3,0.1

Type RM Length L Ch R = 1 ,16068   ,641,641,641
BEGIN DESCRIPTION:
KIDHAW BRANCH 32.0
END DESCRIPTION:
XS GIS Cut Line= 3
      3725117.82      10190611.1      3724815.26     10190888.24
      3724667.84     10191111.09
#Sta/Elev= 30
  4589.7  328.25  4631.9  325.03  4674.4  322.71  4681.8  322.88  4710.2  320.44
  4731.2  319.38  4759.5  316.38  4766.3   316.7  4794.7  315.07  4808.9  315.13
  4816.3  314.32    4823  314.79  4851.4  313.09  4879.8   313.3  4901.4  312.52
  4906.1  312.17  4906.4  311.67  4922.3  313.14  4950.7  313.24  4971.7  314.23
  4985.8  313.05  5002.2  313.22  5006.9  314.14  5021.9  315.14  5073.1  316.84
  5172.4  322.58  5195.2  323.22  5223.5  325.28  5244.6  325.54  5267.2  326.95
#Mann= 3 , 0 , 0
  4589.7     .17       0  4879.8     .09       0  4922.3     .17       0
Bank Sta=4879.8,4922.3
XS Rating Curve= 0 ,0
Exp/Cntr=0.3,0.1

Type RM Length L Ch R = 1 ,15427   ,351,351,351
BEGIN DESCRIPTION:
KIDHAW BRANCH 31.0
END DESCRIPTION:
XS GIS Cut Line= 3
       3725167.9     10190361.07       3724497.3     10190398.22
      3723967.85     10190461.07
#Sta/Elev= 30
  4324.1  337.68  4424.3  332.69  4454.3  331.81  4584.5  321.45  4597.4  321.74
  4694.7  313.52  4733.2  312.13    4778  311.89  4794.9   311.2  4834.9  311.39
    4855  310.04    4885  310.51    4895  309.76    4903  308.51  4903.3  308.01
  4925.1  310.01  5056.4  309.98  5095.9  309.89  5149.2  311.29  5166.4  312.32
  5206.6   312.7  5231.9   313.9  5246.9  313.38  5307.3  317.87  5319.6  317.66
  5357.7  320.07  5397.3  321.84  5402.3  321.39    5485  327.17  5528.9   329.5
#Mann= 5 ,-1 , 0
  4324.1     .17       0  4733.2     .11       0    4885     .07       0
  4925.1     .11       0  5056.4     .17       0
Bank Sta=4885,4925.1
XS Rating Curve= 0 ,0
Exp/Cntr=0.3,0.1

Type RM Length L Ch R = 1 ,15076   ,234,234,234
BEGIN DESCRIPTION:
KIDHAW BRANCH 30.0
END DESCRIPTION:
XS GIS Cut Line= 3
      3725017.82     10190011.08      3724418.84     10190078.88
      3724117.89     10190311.05
#Sta/Elev= 30
  4397.2  332.37    4437  330.93    4442  330.13  4477.7  328.07  4507.9  324.87
  4531.8  323.44  4547.6  323.54  4558.2   323.4  4616.5  319.21  4621.5  319.31
  4638.7   317.5  4658.8   316.9  4728.9  312.68  4769.5  311.07  4851.2  309.61
  4930.6  308.28  4960.7  308.76  4990.9  308.15    4996  307.79  4996.2  307.29
    5000  307.79  5038.7  308.36  5088.4  308.85  5109.3  308.48  5135.6  309.24
  5216.9  312.78  5279.6  315.93  5288.8  316.95  5337.6  320.59  5380.1  322.33
#Mann= 10 ,-1 , 0
  4397.2     .11       0  4547.6     .17       0  4728.9     .11       0
  4851.2     .17       0  4990.9     .09       0  5038.7     .17       0
  5088.4     .11       0  5135.6     .17       0  5216.9     .11       0
  5288.8     .17       0
Bank Sta=4990.9,5038.7
XS Rating Curve= 0 ,0
Exp/Cntr=0.3,0.1

Type RM Length L Ch R = 1 ,14842   ,119,119,119
BEGIN DESCRIPTION:
Mapping XS a84d8852
END DESCRIPTION:
XS GIS Cut Line= 4
      3724892.25     10189712.46      3724267.26     10189890.41
      3723946.08     10190016.28      3723837.58     10190090.06
#Sta/Elev= 30
  4419.5  325.24    4470  323.89  4496.9  321.95  4517.6  319.38  4569.6  317.77
    4632  313.78  4704.8  312.69  4767.2  310.38    4788  311.16  4829.4  309.71
  4964.7   308.2  4975.1  307.49  4978.6  305.73  4985.6  306.69  5019.4  306.98
  5027.1  307.98  5114.6  310.56  5240.5  312.63  5294.2  315.03  5315.7  316.84
  5361.5  318.43  5385.9  320.59    5414  320.79    5431  322.37    5452  321.24
  5466.9  322.67    5473  322.37  5496.8  324.93  5523.8  325.44  5545.5  327.34
#Mann= 3 , 0 , 0
  4419.5     .11       0  4964.7     .06       0  5027.1     .11       0
Bank Sta=4964.7,5027.1
XS Rating Curve= 0 ,0
Exp/Cntr=0.3,0.1

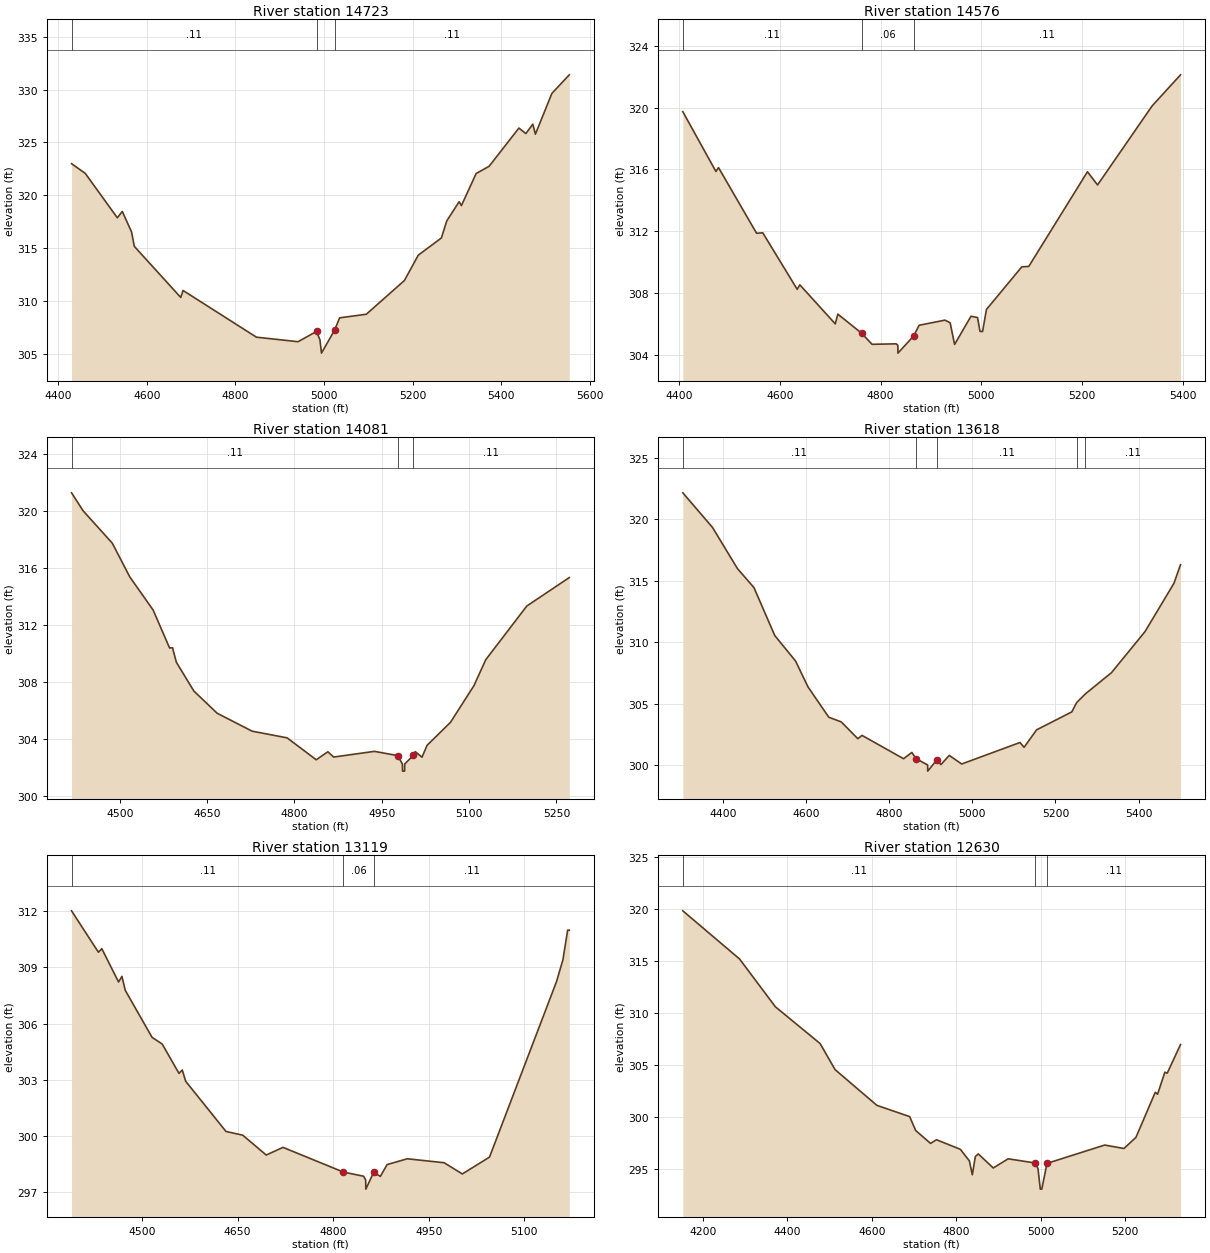
Type RM Length L Ch R = 1 ,14723   ,147,147,147
BEGIN DESCRIPTION:
Mapping XS 94292b1a
END DESCRIPTION:
XS GIS Cut Line= 3
      3724857.57     10189595.26      3723954.76     10189864.37
      3723798.47     10189955.54
#Sta/Elev= 30
  4430.2  322.99  4461.2  322.07  4533.5  317.87  4544.7  318.47  4565.6  316.53
  4571.9  315.16  4676.6  310.33  4681.8  310.99  4847.3  306.57  4941.2  306.14
  4982.9  307.11  4990.7  306.32  4994.1  305.06  5023.8  307.24  5035.1   308.4
  5095.3  308.74  5181.2  311.93  5212.5  314.33  5264.7  315.96  5276.8  317.57
  5304.7  319.39  5309.9  319.02  5343.1  322.06  5372.3  322.74  5439.6  326.36
  5455.3  325.84    5471  326.73  5476.8  325.78    5514  329.64  5553.2   331.4
#Mann= 3 , 0 , 0
  4430.2     .11       0  4982.9     .06       0  5023.8     .11       0
Bank Sta=4982.9,5023.8
XS Rating Curve= 0 ,0
Exp/Cntr=0.3,0.1

Type RM Length L Ch R = 1 ,14576   ,495,495,495
BEGIN DESCRIPTION:
KIDHAW BRANCH 29.0
END DESCRIPTION:
XS GIS Cut Line= 3
      3724831.47     10189478.09      3724258.19     10189628.56
      3723863.57     10189660.38
#Sta/Elev= 30
  4407.3  319.73    4473  315.87  4478.2  316.12  4553.8  311.88  4566.1  311.91
  4634.5  308.26  4639.7  308.55  4710.1  306.03  4715.2  306.66  4762.6  305.42
  4783.2  304.71  4831.2  304.74  4834.4  304.64  4834.6  304.14  4865.9  305.25
  4876.7  305.94    4928  306.27  4938.3   306.1  4947.1   304.7  4979.7  306.52
  4992.7  306.44  4997.6  305.54  5002.7  305.54  5010.4  306.96  5080.6  309.71
  5094.5  309.74    5211  315.85  5231.1     315  5339.4   320.1  5395.9  322.11
#Mann= 3 , 0 , 0
  4407.3     .11       0  4762.6     .06       0  4865.9     .11       0
Bank Sta=4762.6,4865.9
XS Rating Curve= 0 ,0
Exp/Cntr=0.3,0.1

Type RM Length L Ch R = 1 ,14081   ,463,463,463
BEGIN DESCRIPTION:
KIDHAW BRANCH 28.0
END DESCRIPTION:
XS GIS Cut Line= 3
      3724867.85     10189161.07       3724285.3      10189144.1
       3724015.5     10189178.61
#Sta/Elev= 30
  4417.2   321.3  4437.2  320.03  4487.2  317.76  4517.2  315.39  4557.3  313.06
  4585.6  310.39  4590.6  310.41  4597.3  309.38  4627.3  307.36  4667.3   305.8
  4727.3  304.54  4787.4  304.07  4837.4  302.53  4857.4  303.09  4867.4  302.72
  4937.4  303.12  4977.4  302.82  4985.4  302.23  4985.7  301.73  4989.2  301.73
  4989.4  302.23 5004.35302.8438  5007.5   303.1  5019.1  302.71  5027.7  303.54
    5068  305.16  5108.3  307.74  5128.5  309.56  5199.1  313.34    5272  315.34
#Mann= 3 , 0 , 0
  4417.2     .11       0  4977.4     .06       0 5004.35     .11       0
Bank Sta=4977.4,5004.35
XS Rating Curve= 0 ,0
Exp/Cntr=0.3,0.1

Type RM Length L Ch R = 1 ,13618   ,499,499,499
BEGIN DESCRIPTION:
KIDHAW BRANCH 27.0
END DESCRIPTION:
XS GIS Cut Line= 3
       3724979.1     10188692.49      3724282.24     10188699.95
      3723781.99     10188670.84
#Sta/Elev= 30
  4303.1  322.16  4374.4  319.35  4434.4     316  4474.4  314.44  4524.4  310.54
  4574.4  308.47  4604.4  306.36  4654.4  303.89  4684.4  303.51  4724.4  302.14
  4734.4  302.41  4834.4  300.51  4854.4  301.02  4864.4  300.52  4892.4     300
  4892.6   299.5  4914.4  300.41  4924.4  300.03  4944.4  300.78  4974.4  300.08
  5114.6  301.83  5124.6  301.44  5154.6  302.86  5239.3  304.32  5251.3  305.09
  5272.1  305.79    5335  307.52  5415.6  310.86  5485.2  314.79  5501.1  316.31
#Mann= 5 ,-1 , 0
  4303.1     .11       0  4864.4     .06       0  4914.4     .11       0
  5251.3     .17       0  5272.1     .11       0
Bank Sta=4864.4,4914.4
XS Rating Curve= 0 ,0
Exp/Cntr=0.3,0.1

Type RM Length L Ch R = 1 ,13119   ,489,489,489
BEGIN DESCRIPTION:
KIDHAW BRANCH 26.0
END DESCRIPTION:
XS GIS Cut Line= 3
      3724767.87     10188461.08      3724188.44     10188267.88
      3724017.87     10188261.07
#Sta/Elev= 30
  4389.2  312.02  4431.4  309.81  4436.7     310    4463  308.22  4468.3  308.52
  4473.6  307.77  4515.7  305.26  4531.5  304.91  4557.9  303.34  4563.1  303.52
  4568.4  302.92  4631.7  300.24    4658  300.04  4694.9  298.98  4721.2  299.39
  4816.1  298.07  4847.7  297.85    4851  297.66  4851.3  297.16  4863.6  298.06
  4874.1  297.84  4884.7  298.47  4916.3  298.78  4974.2  298.57  5002.8  297.97
  5045.5  298.87  5150.7  308.24  5160.7   309.4  5168.2  310.99  5170.7  310.99
#Mann= 3 , 0 , 0
  4389.2     .11       0  4816.1     .06       0  4863.6     .11       0
Bank Sta=4816.1,4863.6
XS Rating Curve= 0 ,0
Exp/Cntr=0.3,0.1

Type RM Length L Ch R = 1 ,12630   ,499,499,499
BEGIN DESCRIPTION:
KIDHAW BRANCH 25.0
END DESCRIPTION:
XS GIS Cut Line= 3
      3724967.86     10188511.08      3724328.03     10187889.54
      3724067.83     10188011.08
#Sta/Elev= 30
    4152   319.8  4286.4  315.18  4371.3  310.59  4477.3  307.06  4512.7  304.56
  4611.8  301.13  4689.5  300.05  4703.6  298.72  4738.9  297.48    4753  297.83
  4809.6  296.91  4830.9   295.8  4837.9  294.47  4845.1  296.22  4852.1  296.47
  4887.5  295.12  4922.8     296  4986.6   295.6  4993.5  295.07    4999  293.09
  5002.5  293.09  5014.8  295.56  5151.5  297.32  5197.2  296.99  5225.6  298.06
  5271.3  302.38  5276.8   302.2  5294.1  304.31  5299.7  304.22  5331.2  306.97
#Mann= 3 , 0 , 0
    4152     .11       0  4986.6     .06       0  5014.8     .11       0
Bank Sta=4986.6,5014.8
XS Rating Curve= 0 ,0
Exp/Cntr=0.3,0.1

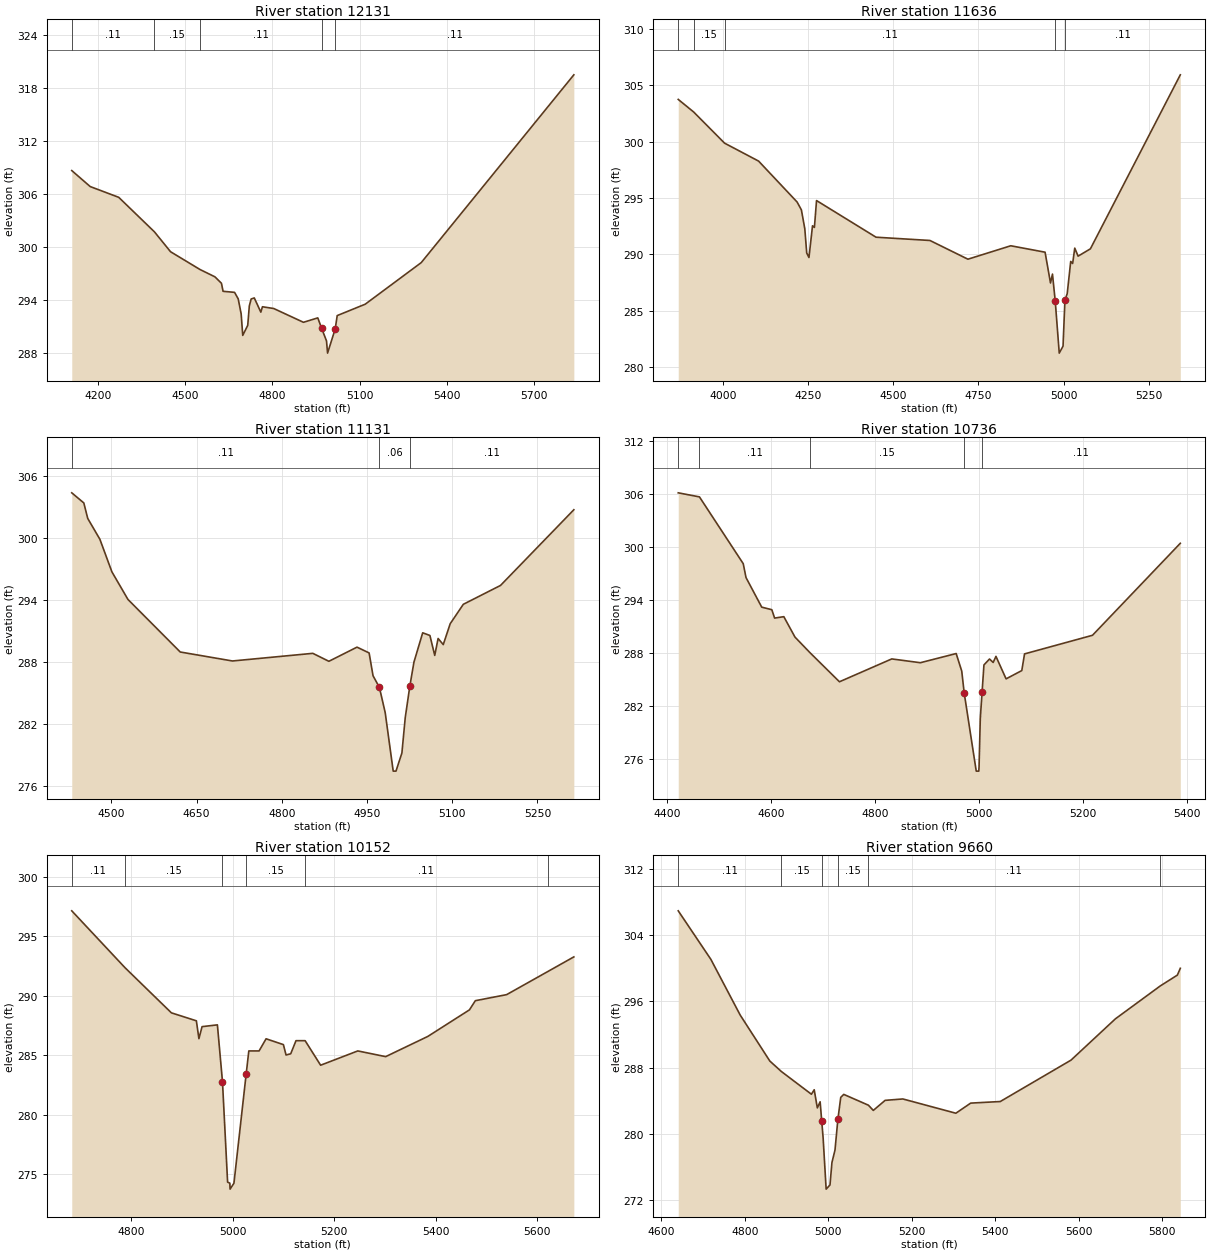
Type RM Length L Ch R = 1 ,12131   ,495,495,495
BEGIN DESCRIPTION:
KIDHAW BRANCH 24.0
END DESCRIPTION:
XS GIS Cut Line= 3
      3724848.84     10188106.52      3724514.66     10187416.45
      3723617.82     10187761.08
#Sta/Elev= 30
  4109.8   308.7  4173.2  306.89  4271.4  305.67  4394.3  301.76  4449.7  299.51
  4550.9   297.5  4602.3  296.67  4624.8  295.94  4630.4  295.03    4670  294.91
  4682.5  294.17  4692.6  292.48  4698.1  290.04  4715.2  291.17  4720.7  293.37
    4727  294.16  4737.8  294.28  4760.3  292.67  4765.9  293.28  4804.7  293.08
    4907  291.52  4956.3  292.02  4969.5  290.84  4986.3  289.41  4989.9  288.03
  5016.3  290.78  5023.1  292.28  5119.5  293.57  5312.3  298.28  5837.3  319.54
#Mann= 5 ,-1 , 0
  4109.8     .11       0  4394.3     .15       0  4550.9     .11       0
  4969.5     .06       0  5016.3     .11       0
Bank Sta=4969.5,5016.3
XS Rating Curve= 0 ,0
Exp/Cntr=0.3,0.1

Type RM Length L Ch R = 1 ,11636   ,505,505,505
BEGIN DESCRIPTION:
KIDHAW BRANCH 23.0
END DESCRIPTION:
XS GIS Cut Line= 3
      3724766.37     10187876.48      3724332.37     10186978.08
      3723917.89     10187211.05
#Sta/Elev= 30
  3869.3  303.75  3914.7  302.63  4005.3  299.87  4105.1  298.28  4218.1  294.65
  4230.7  293.95  4240.7  292.28  4246.3  290.13  4252.9  289.73  4263.3  292.54
  4268.9   292.4  4275.1  294.78  4449.7  291.53  4607.9  291.24  4719.3  289.58
    4845  290.77  4945.7   290.2  4961.6  287.47  4967.4  288.26  4975.5  285.87
  4987.3  281.25  4998.4  281.87 5003.93285.9338  5010.7  286.53  5020.9  289.38
  5026.6   289.2  5032.8  290.56  5042.6  289.85  5078.7   290.5  5342.5  305.93
#Mann= 5 ,-1 , 0
  3869.3     .11       0  3914.7     .15       0  4005.3     .11       0
  4975.5     .06       0 5003.93     .11       0
Bank Sta=4975.5,5003.93
XS Rating Curve= 0 ,0
Exp/Cntr=0.3,0.1

Type RM Length L Ch R = 1 ,11131   ,395,395,395
BEGIN DESCRIPTION:
KIDHAW BRANCH 22.0
END DESCRIPTION:
XS GIS Cut Line= 3
      3724317.82      10186311.1      3723909.39     10186708.13
       3723642.6     10186873.71
#Sta/Elev= 30
  4430.4  304.38  4451.6   303.4  4458.5   301.9  4479.9  299.88    4501  296.73
  4529.3  294.05  4621.3  288.96  4713.2  288.09  4854.6  288.83  4882.9  288.06
  4932.4  289.43  4953.7  288.87  4960.6  286.66 4971.81285.5298    4982  283.09
  4996.1  277.42    5001  277.42  5011.4  279.18  5017.3  282.61  5025.3  285.63
  5032.6  287.98    5048  290.82  5060.7  290.56  5069.2  288.63  5075.1  290.27
  5084.2  289.68  5096.4   291.7  5119.5  293.58    5185  295.41    5314  302.74
#Mann= 3 , 0 , 0
  4430.4     .11       0 4971.81     .06       0  5025.3     .11       0
Bank Sta=4971.81,5025.3
XS Rating Curve= 0 ,0
Exp/Cntr=0.3,0.1

Type RM Length L Ch R = 1 ,10736   ,584,584,584
BEGIN DESCRIPTION:
KIDHAW BRANCH 21.0
END DESCRIPTION:
XS GIS Cut Line= 3
      3724217.84     10186211.08      3723590.18     10186448.57
      3723317.89     10186561.06
#Sta/Elev= 30
  4421.9  306.13  4462.7  305.67  4546.9   298.1  4552.3  296.52  4582.5  293.17
  4601.9  292.88  4607.3  291.93    4625  292.09  4646.4  289.78  4675.1  288.02
    4732  284.71  4832.6   287.3  4887.6  286.87  4956.5  287.91  4967.2  285.92
    4972  283.41  4995.1  274.58    5000  274.58  5000.5  275.08  5002.9  280.56
 5006.36283.5553  5009.9  286.62  5020.6  287.29  5027.7   286.9    5033  287.59
  5052.5  285.04  5082.7  285.98    5088  287.87  5218.7  289.98  5387.6  300.41
#Mann= 5 ,-1 , 0
  4421.9     .17       0  4462.7     .11       0  4675.1     .15       0
    4972     .06       0 5006.36     .11       0
Bank Sta=4972,5006.36
XS Rating Curve= 0 ,0
Exp/Cntr=0.3,0.1

Type RM Length L Ch R = 1 ,10152   ,492,492,492
BEGIN DESCRIPTION:
KIDHAW BRANCH 20.0
END DESCRIPTION:
XS GIS Cut Line= 3
      3724032.87      10186053.6       3723718.2     10186018.64
      3723071.12     10186200.68
#Sta/Elev= 30
  4683.4  297.14  4788.3  292.36  4879.6  288.57  4928.8   287.9  4933.8   286.4
    4940  287.41  4970.2  287.56  4980.2   282.8  4990.3  274.35  4994.7  274.26
  4995.2  273.76  5002.8  274.26  5026.9  283.44  5032.1  285.37  5052.3  285.37
  5066.1  286.39  5100.2   285.9  5105.4  285.03  5114.6  285.13    5125  286.23
    5143  286.23  5173.5  284.17  5246.7  285.37  5301.6  284.89  5384.7  286.59
  5466.6  288.82  5478.2  289.59  5539.9   290.1  5620.5  292.03  5672.2  293.27
#Mann= 6 ,-1 , 0
  4683.4     .11       0  4788.3     .15       0  4980.2     .09       0
  5026.9     .15       0    5143     .11       0  5620.5     .17       0
Bank Sta=4980.2,5026.9
XS Rating Curve= 0 ,0
Exp/Cntr=0.3,0.1

Type RM Length L Ch R = 1 ,9660    ,493,493,493
BEGIN DESCRIPTION:
KIDHAW BRANCH 19.0
END DESCRIPTION:
XS GIS Cut Line= 3
      3723767.83     10185361.09      3723529.65      10185630.1
      3722917.85     10186211.07
#Sta/Elev= 30
  4640.7  306.91  4718.9  301.06  4789.1  294.35  4860.2   288.8  4887.8  287.54
  4959.8   284.8  4966.5  285.34    4974  283.15  4980.7  283.89 4984.52281.5662
  4987.9  279.51  4995.1  273.36  5004.3  273.86    5009  276.57  5016.3  278.07
  5023.2  281.76  5030.1  284.42  5037.3  284.78  5096.3  283.48  5108.1  282.85
  5136.4  284.06  5178.9  284.23  5305.9  282.51  5341.5  283.73  5412.3  283.92
  5581.8  288.91  5688.2  293.89  5795.8  297.86  5836.6  299.16  5843.7  299.98
#Mann= 6 ,-1 , 0
  4640.7     .11       0  4887.8     .15       0 4984.52     .09       0
  5023.2     .15       0  5096.3     .11       0  5795.8     .17       0
Bank Sta=4984.52,5023.2
XS Rating Curve= 0 ,0
Exp/Cntr=0.3,0.1

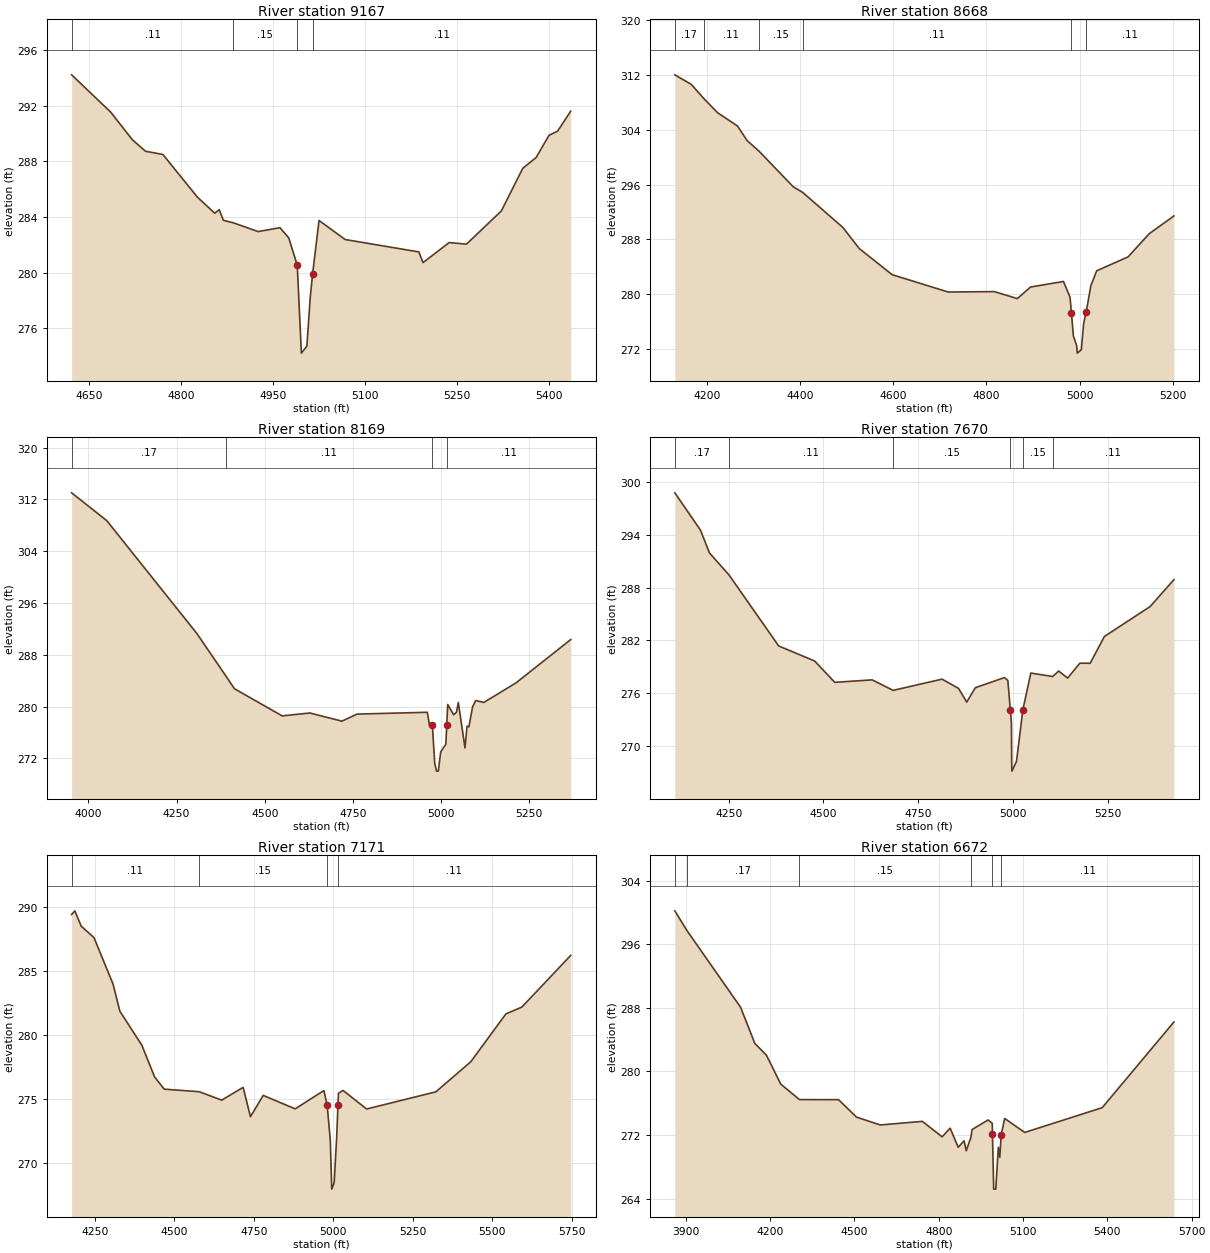
Type RM Length L Ch R = 1 ,9167    ,499,499,499
BEGIN DESCRIPTION:
KIDHAW BRANCH 18.0
END DESCRIPTION:
XS GIS Cut Line= 3
      3723417.88     10185111.04      3723160.31     10185389.19
      3722867.85     10185711.07
#Sta/Elev= 30
  4620.9  294.21  4684.7  291.53  4719.9  289.55  4741.4  288.72  4769.8  288.49
  4825.9  285.43  4854.3  284.27  4861.6  284.52  4868.4  283.76  4884.7  283.58
  4925.1  282.95  4960.8  283.23    4975   282.5  4988.9  280.53  4995.6  274.22
  5004.6  274.72  5010.2  278.29  5013.9  279.89  5024.4  283.75    5067  282.38
  5187.2  281.49    5194  280.72  5236.6  282.16  5264.9  282.05  5321.7  284.43
  5356.8   287.5  5378.5  288.27  5399.4  289.86  5413.6  290.17  5434.9   291.6
#Mann= 4 ,-1 , 0
  4620.9     .11       0  4884.7     .15       0  4988.9     .09       0
  5013.9     .11       0
Bank Sta=4988.9,5013.9
XS Rating Curve= 0 ,0
Exp/Cntr=0.3,0.1

Type RM Length L Ch R = 1 ,8668    ,499,499,499
BEGIN DESCRIPTION:
KIDHAW BRANCH 17.0
END DESCRIPTION:
XS GIS Cut Line= 3
      3723367.86     10184711.07       3722757.3     10185329.16
      3722667.86     10185511.06
#Sta/Elev= 30
  4131.2  312.04  4166.6  310.64  4193.1   308.6  4223.1   306.5  4265.6  304.57
  4286.7  302.41  4312.2  300.87  4385.7  295.66  4405.5  294.87  4491.8  289.75
  4527.2  286.65  4597.9  282.83  4718.1   280.3  4817.1  280.36  4866.6  279.34
  4894.9  281.03  4965.6  281.84  4979.7  279.54 4982.56277.2917  4986.9  273.88
  4993.9  272.46  4995.2  271.37  5003.9  271.87  5008.9  275.71  5014.5  277.44
  5024.4  281.22  5036.9   283.4  5104.4  285.44  5149.3   288.8  5202.7  291.42
#Mann= 6 ,-1 , 0
  4131.2     .17       0  4193.1     .11       0  4312.2     .15       0
  4405.5     .11       0 4982.56     .06       0  5014.5     .11       0
Bank Sta=4982.56,5014.5
XS Rating Curve= 0 ,0
Exp/Cntr=0.3,0.1

Type RM Length L Ch R = 1 ,8169    ,499,499,499
BEGIN DESCRIPTION:
KIDHAW BRANCH 16.0
END DESCRIPTION:
XS GIS Cut Line= 3
      3723217.83     10184411.09      3722411.13      10185079.6
      3722067.85     10185211.07
#Sta/Elev= 30
  3952.3  313.03  4051.9  308.74  4307.2  291.32  4389.4  284.76    4414  282.77
  4549.4  278.57  4627.6  279.02  4718.7  277.76  4761.7  278.85    4961  279.13
  4967.5  277.03  4975.3  277.16  4981.8  271.32    4987  270.04  4992.2  270.04
  4998.9  273.02  5013.5  274.19 5016.01277.0977  5018.8  280.33  5035.6  278.75
  5043.5  279.13  5048.9  280.64  5067.8  273.63  5073.6  276.99  5078.9  276.88
  5089.2  279.96  5098.3  280.94  5121.3  280.65  5213.1   283.7  5367.6  290.36
#Mann= 4 ,-1 , 0
  3952.3     .17       0  4389.4     .11       0  4975.3     .06       0
 5016.01     .11       0
Bank Sta=4975.3,5016.01
XS Rating Curve= 0 ,0
Exp/Cntr=0.3,0.1

Type RM Length L Ch R = 1 ,7670    ,499,499,499
BEGIN DESCRIPTION:
KIDHAW BRANCH 15.0
END DESCRIPTION:
XS GIS Cut Line= 3
      3722917.88     10184361.06      3722095.34     10184706.17
      3721967.85     10185111.07
#Sta/Elev= 30
    4108  298.73  4175.6  294.51  4199.3  291.93  4251.4   289.4    4382  281.38
  4476.7  279.68    4530  277.26  4628.6  277.54    4684  276.35  4812.9  277.62
  4856.3  276.58    4878  275.02  4900.7  276.65  4977.5   277.8  4986.4  277.48
 4993.01274.1328  4995.8  272.72  4996.7   267.7  4997.2   267.2  5009.3  268.31
  5026.1  274.16  5047.1  278.31  5104.5  277.92  5120.5  278.54  5144.1  277.74
  5176.4  279.43  5203.6  279.42  5241.2  282.46  5361.6  285.84  5424.5  288.89
#Mann= 6 ,-1 , 0
    4108     .17       0  4251.4     .11       0    4684     .15       0
 4993.01     .09       0  5026.1     .15       0  5104.5     .11       0
Bank Sta=4993.01,5026.1
XS Rating Curve= 0 ,0
Exp/Cntr=0.3,0.1

Type RM Length L Ch R = 1 ,7171    ,499,499,499
BEGIN DESCRIPTION:
KIDHAW BRANCH 14.0
END DESCRIPTION:
XS GIS Cut Line= 4
      3722617.85     10184261.07       3721798.5     10184344.63
      3721693.96     10184353.53      3721736.88     10184994.57
#Sta/Elev= 30
  4176.4  289.41  4186.5   289.7  4206.6   288.5  4246.8  287.61  4307.1  283.96
  4328.2  281.86  4397.5   279.2  4437.7  276.72  4467.9  275.77    4578  275.57
  4648.8  274.91  4716.3  275.91  4739.3  273.62  4779.5  275.28    4880  274.23
  4970.5  275.66  4980.5  274.57  4990.6  271.79  4995.2  267.96  5002.8  268.46
  5010.7  272.01 5014.84274.5531  5016.3  275.45  5030.8  275.67  5104.9  274.22
    5323  275.56  5433.2  277.92  5543.4  281.65  5593.6  282.18  5747.4  286.22
#Mann= 4 ,-1 , 0
  4176.4     .11       0    4578     .15       0  4980.5     .07       0
 5014.84     .11       0
Bank Sta=4980.5,5014.84
XS Rating Curve= 0 ,0
Exp/Cntr=0.3,0.1

Type RM Length L Ch R = 1 ,6672    ,499,499,499
BEGIN DESCRIPTION:
KIDHAW BRANCH 13.0
END DESCRIPTION:
XS GIS Cut Line= 3
      3722517.88     10183211.05       3721641.7     10183939.12
      3721017.81     10183811.06
#Sta/Elev= 30
  3860.8   300.2  3904.4   297.7  4094.9  288.07  4145.3  283.54    4187  282.03
  4237.8  278.41  4304.3  276.46  4443.5  276.45  4507.3  274.26  4591.9  273.27
  4741.7  273.72    4812  271.78  4840.6  272.87  4869.3  270.46  4890.1  271.28
  4897.9  270.02  4914.5  271.72  4918.7   272.7    4976   273.9  4990.4  273.48
 4991.23272.0761  4995.5   265.2    5003   265.2  5012.1  270.47  5017.2  269.19
 5022.32272.0456  5034.6  274.09    5106  272.33  5381.6  275.44  5636.9  286.22
#Mann= 6 ,-1 , 0
  3860.8     .11       0  3904.4     .17       0  4304.3     .15       0
  4914.5     .11       0 4991.23     .06       0 5022.32     .11       0
Bank Sta=4991.23,5022.32
XS Rating Curve= 0 ,0
Exp/Cntr=0.3,0.1