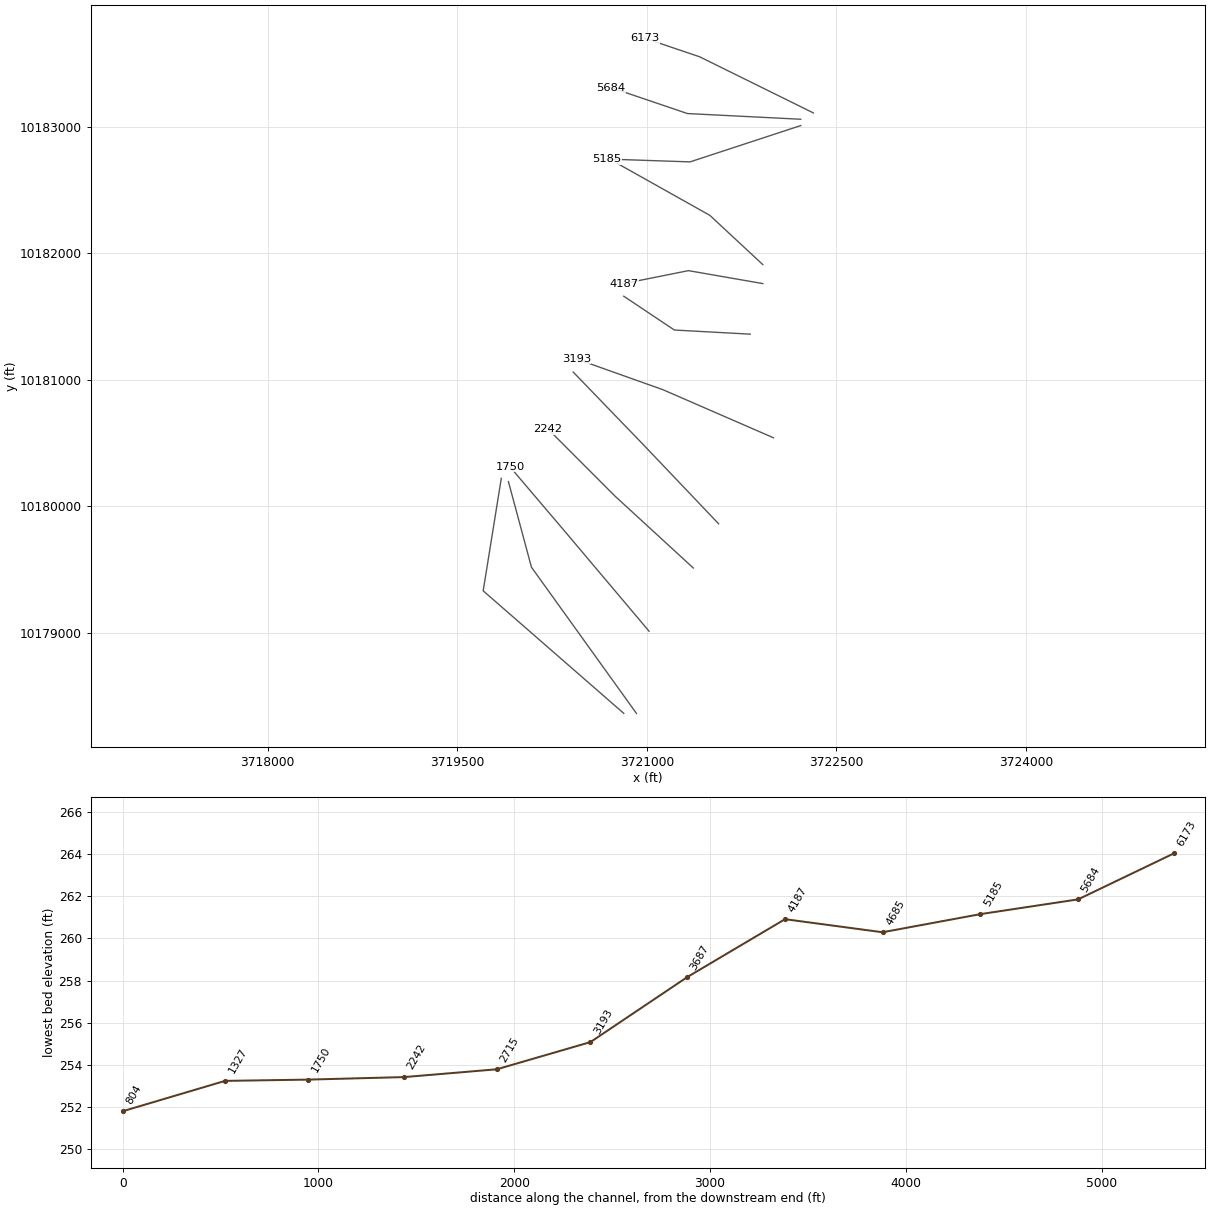
HEC-RAS study KIDHAW BRANCH.prj: KIDHAW BRANCH Base Level Engineering

--- KIDHAW BRANCH.g01 (geometry) --- (continued)

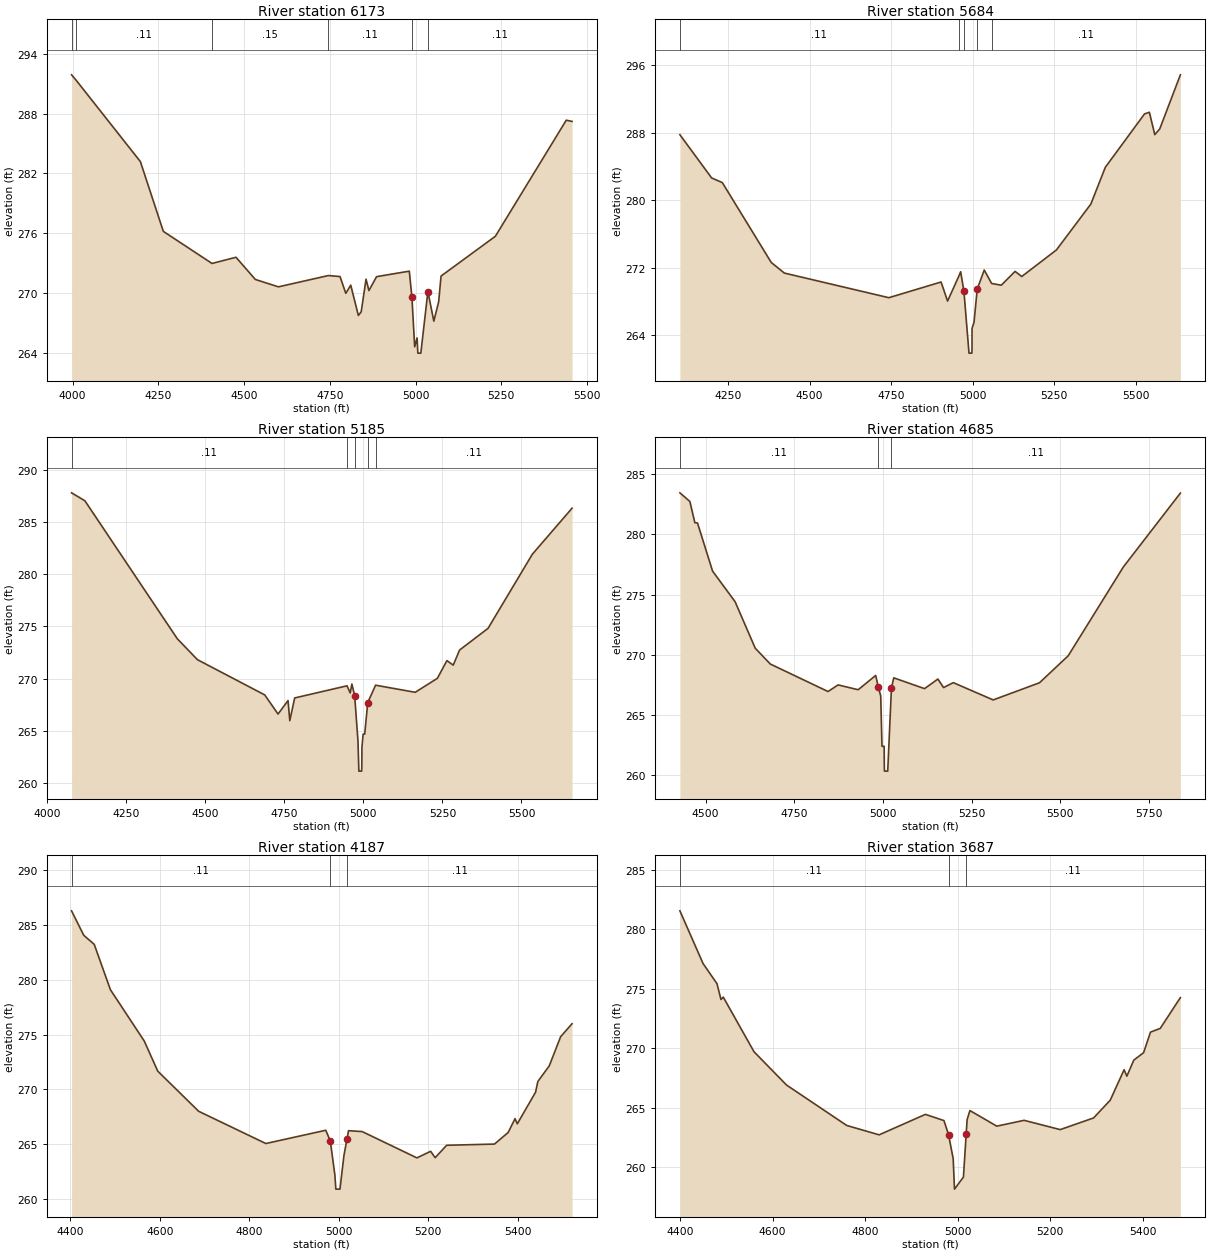
Type RM Length L Ch R = 1 ,6173    ,489,489,489
BEGIN DESCRIPTION:
KIDHAW BRANCH 12.0
END DESCRIPTION:
XS GIS Cut Line= 3
      3722317.86     10183111.07      3721418.27     10183555.08
      3720985.99     10183701.18
#Sta/Elev= 30
  3996.8  291.87  4010.6  291.31  4197.5  283.19  4264.4  276.21  4406.4     273
  4476.3  273.62  4532.7   271.4  4600.1  270.66  4745.6  271.79  4779.7  271.69
  4796.5  270.01  4810.9  270.83  4833.2   267.8  4841.4  268.16  4855.5  271.43
  4863.9  270.29  4886.3  271.68  4981.7  272.23  4989.3  269.63  4997.4  264.66
  5004.4  265.55  5006.6  264.03  5015.3  264.03  5035.9  270.19  5053.2  267.23
  5067.3  269.16  5074.3  271.74  5232.7  275.72  5439.4  287.33  5456.3  287.21
#Mann= 6 ,-1 , 0
  3996.8     .17       0  4010.6     .11       0  4406.4     .15       0
  4745.6     .11       0  4989.3     .07       0  5035.9     .11       0
Bank Sta=4989.3,5035.9
XS Rating Curve= 0 ,0
Exp/Cntr=0.3,0.1

Type RM Length L Ch R = 1 ,5684    ,499,499,499
BEGIN DESCRIPTION:
KIDHAW BRANCH 11.0
END DESCRIPTION:
XS GIS Cut Line= 3
      3722217.84     10183061.07      3721321.27     10183106.16
      3720717.82     10183311.08
#Sta/Elev= 30
  4102.3  287.74  4199.6  282.62  4232.5  282.06  4382.6  272.59  4422.7  271.34
  4743.1  268.42  4903.3  270.28  4923.3  268.02  4957.8  270.98  4963.4   271.5
  4973.4  269.19    4989  261.85  4997.7  261.85  4998.2  262.35  4998.3  264.79
  5004.4  265.51  5014.2  269.44  5035.7   271.7  5058.3  270.11  5087.9   269.9
  5130.3  271.54  5150.7  270.93  5257.1  274.08  5362.7  279.52  5407.1  283.88
  5527.4  290.21  5542.2   290.4  5558.8  287.75  5573.9  288.42  5637.3  294.84
#Mann= 5 ,-1 , 0
  4102.3     .11       0  4957.8     .15       0  4973.4     .09       0
  5014.2     .15       0  5058.3     .11       0
Bank Sta=4973.4,5014.2
XS Rating Curve= 0 ,0
Exp/Cntr=0.3,0.1

Type RM Length L Ch R = 1 ,5185    ,500,500,500
BEGIN DESCRIPTION:
KIDHAW BRANCH 10.0
END DESCRIPTION:
XS GIS Cut Line= 3
      3722217.86     10183011.07      3721341.98     10182723.75
      3720682.57      10182746.3
#Sta/Elev= 30
  4078.2  287.77  4120.3  287.01  4412.4  273.81    4476  271.81  4688.6  268.44
  4730.7  266.61  4762.3   267.9  4767.8  265.98  4783.3  268.15  4948.7  269.31
  4958.7  268.63    4964  269.48  4972.8  268.38  4983.3  264.03  4986.1  261.15
  4994.9  261.15  4995.4  261.65  4995.8  263.41  4999.5  264.69  5004.6  264.69
  5014.1   267.7  5038.9  269.37  5164.2  268.69  5234.3  270.03  5264.3  271.72
  5284.3  271.29  5304.3  272.73  5394.4  274.81  5534.4   281.9  5659.8   286.3
#Mann= 5 ,-1 , 0
  4078.2     .11       0  4948.7     .15       0  4972.8     .09       0
  5014.1     .15       0  5038.9     .11       0
Bank Sta=4972.8,5014.1
XS Rating Curve= 0 ,0
Exp/Cntr=0.3,0.1

Type RM Length L Ch R = 1 ,4685    ,498,498,498
BEGIN DESCRIPTION:
KIDHAW BRANCH 9.0
END DESCRIPTION:
XS GIS Cut Line= 3
      3721917.84     10181911.08      3721498.73     10182300.79
      3720767.81     10182711.09
#Sta/Elev= 30
  4427.7  283.47  4455.8  282.75  4469.9  280.98  4477.3  280.96  4519.8  276.95
  4583.3   274.4    4640  270.53  4682.5  269.21  4845.2  266.92  4873.5  267.47
  4930.2  267.07  4979.5  268.26  4986.9  267.29  4993.7  266.55  4997.2  262.36
  5003.4  262.36  5003.7  260.79  5004.2  260.29  5013.4  260.29  5023.9  267.21
  5030.4  268.06  5117.2  267.16  5154.8  267.96  5170.8  267.25  5198.2  267.66
  5310.6  266.22  5441.2  267.65  5522.1   269.9  5677.6   277.3  5838.2  283.45
#Mann= 3 , 0 , 0
  4427.7     .11       0  4986.9     .06       0  5023.9     .11       0
Bank Sta=4986.9,5023.9
XS Rating Curve= 0 ,0
Exp/Cntr=0.3,0.1

Type RM Length L Ch R = 1 ,4187    ,500,500,500
BEGIN DESCRIPTION:
KIDHAW BRANCH 8.0
END DESCRIPTION:
XS GIS Cut Line= 3
      3721917.82     10181761.08      3721329.46     10181863.44
       3720817.8     10181761.06
#Sta/Elev= 30
  4402.8   286.3    4430  284.07  4453.5  283.24  4489.7   279.1  4565.2  274.43
  4595.6  271.67    4687  268.01  4837.2  265.07  4971.2  266.28  4981.3   265.3
  4991.5  262.21  4993.7  260.91  5002.9  260.91  5011.8  263.98 5018.53265.4711
    5022  266.24  5052.6  266.16    5175  263.76  5205.6  264.36  5215.8  263.78
  5241.4  264.91  5348.4  265.02    5379  266.08  5394.3  267.34  5399.4  266.87
  5440.2  269.75  5445.3  270.73  5470.8  272.15  5496.3  274.82  5521.8     276
#Mann= 3 , 0 , 0
  4402.8     .11       0  4981.3     .06       0 5018.53     .11       0
Bank Sta=4981.3,5018.53
XS Rating Curve= 0 ,0
Exp/Cntr=0.3,0.1

Type RM Length L Ch R = 1 ,3687    ,494,494,494
BEGIN DESCRIPTION:
KIDHAW BRANCH 7.0
END DESCRIPTION:
XS GIS Cut Line= 3
      3721817.89     10181361.07      3721218.17     10181393.59
      3720817.82     10181661.09
#Sta/Elev= 30
  4399.4  281.54  4449.5  277.11  4479.6  275.42  4488.2  274.09  4493.2  274.29
  4559.7   269.7  4629.8  266.91    4760  263.51  4830.1  262.72  4930.2  264.44
  4970.3  263.92  4980.3  262.73  4990.3  260.71  4993.1  258.16  5012.4  259.17
 5018.36262.7683  5020.4     264  5026.5  264.76  5084.6  263.45  5143.6  263.94
  5221.7  263.16  5293.8  264.14  5329.8  265.63  5359.8  268.19  5365.8  267.65
  5380.8     269  5401.9  269.62  5416.9  271.35  5437.9  271.66  5481.5  274.25
#Mann= 3 , 0 , 0
  4399.4     .11       0  4980.3     .06       0 5018.36     .11       0
Bank Sta=4980.3,5018.36
XS Rating Curve= 0 ,0
Exp/Cntr=0.3,0.1

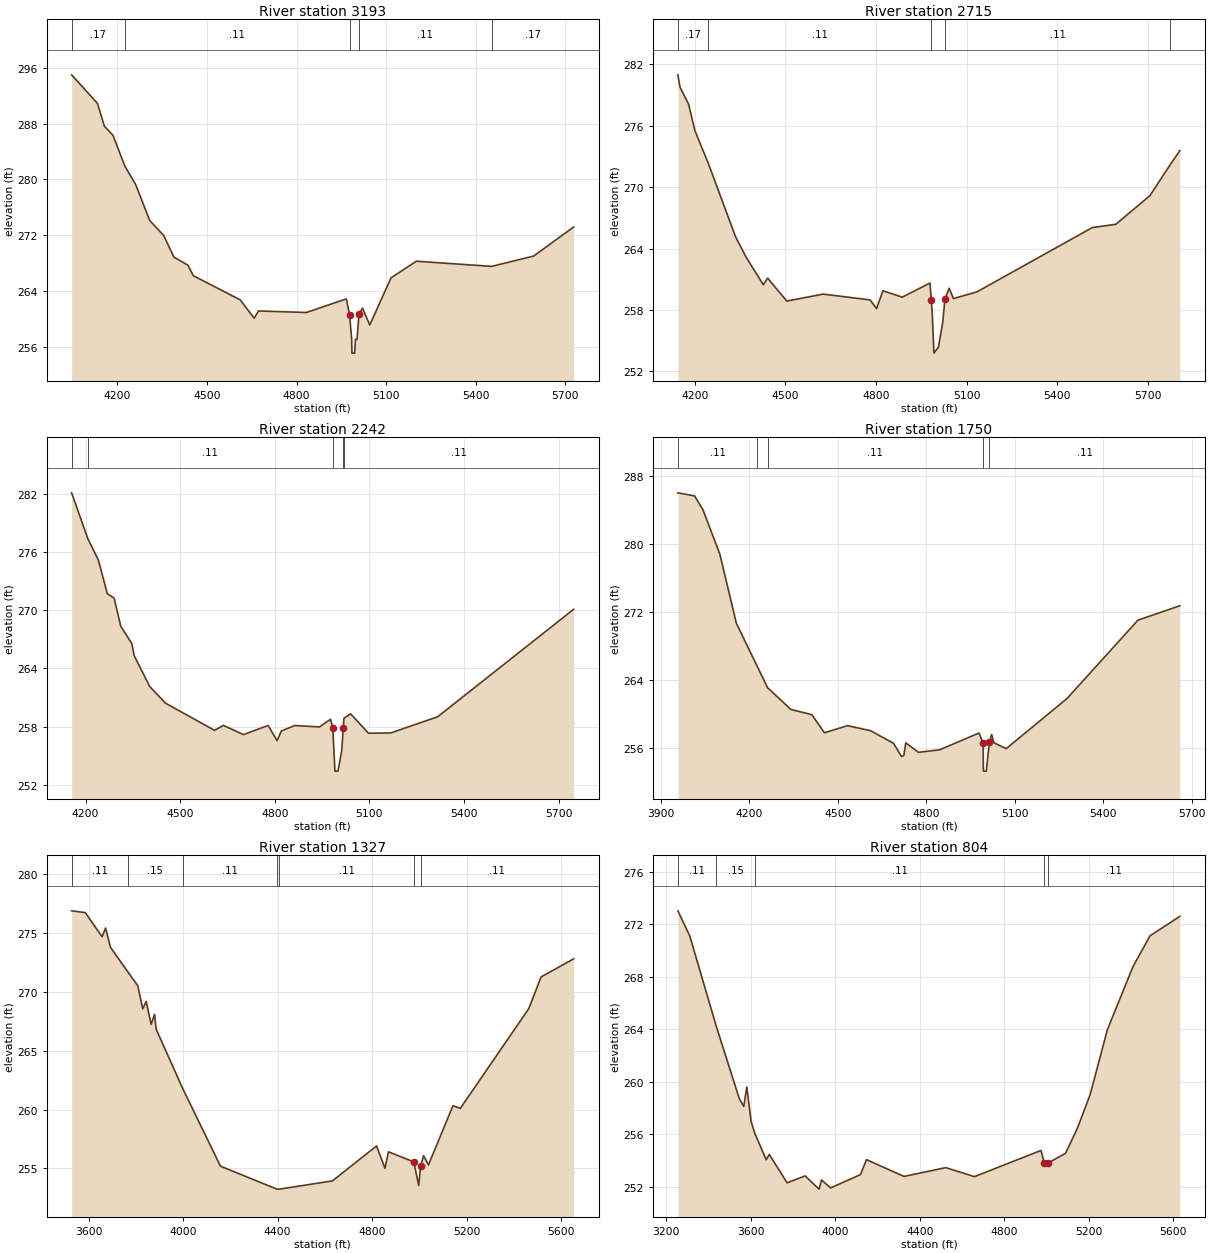
Type RM Length L Ch R = 1 ,3193    ,478,478,478
BEGIN DESCRIPTION:
KIDHAW BRANCH 6.0
END DESCRIPTION:
XS GIS Cut Line= 3
      3722001.64     10180541.45      3721127.35     10180921.71
      3720441.53      10181165.6
#Sta/Elev= 30
  4046.6  295.02    4133  290.92  4156.4  287.64  4185.3  286.33  4224.4  281.96
  4261.1  279.27    4308  274.12  4354.8  271.97  4389.2  268.86  4436.1   267.7
  4454.1  266.19  4611.1  262.73  4657.9  260.09  4672.3  261.13  4832.9  260.91
  4966.7  262.87  4977.6  260.53  4984.5  257.08  4985.3  255.08  4994.6  255.08
    4997  257.05  5002.4  257.05  5008.9  260.64  5020.7  261.54  5045.1  259.12
  5116.2  265.88  5201.1  268.27  5453.5  267.53  5593.8  269.01  5727.9  273.18
#Mann= 5 ,-1 , 0
  4046.6     .17       0  4224.4     .11       0  4977.6     .06       0
  5008.9     .11       0  5453.5     .17       0
Bank Sta=4977.6,5008.9
XS Rating Curve= 0 ,0
Exp/Cntr=0.3,0.1

Type RM Length L Ch R = 1 ,2715    ,473,473,473
BEGIN DESCRIPTION:
KIDHAW BRANCH 5.0
END DESCRIPTION:
XS GIS Cut Line= 3
      3721567.84     10179861.09      3720977.75     10180481.33
      3720417.83      10181061.1
#Sta/Elev= 30
  4143.9  280.99    4151  279.78  4179.3  278.13  4200.3  275.53  4244.7  272.33
    4335  265.15  4370.2  263.15  4426.8  260.47    4441  261.12  4504.5  258.88
    4625  259.56  4780.3  258.99  4801.7  258.14  4822.8  259.89  4886.7  259.26
  4978.5  260.64 4982.86258.9796  4985.8  257.86  4991.6  253.79  5006.8  254.39
    5021  256.85  5027.9  259.05  5042.1  260.13  5056.2  259.12  5134.2  259.78
  5515.9  266.06  5593.9  266.38    5707  269.19  5773.9  272.21    5806  273.59
#Mann= 5 ,-1 , 0
  4143.9     .17       0  4244.7     .11       0 4982.86     .06       0
  5027.9     .11       0  5773.9     .17       0
Bank Sta=4982.86,5027.9
XS Rating Curve= 0 ,0
Exp/Cntr=0.3,0.1

Type RM Length L Ch R = 1 ,2242    ,492,492,492
BEGIN DESCRIPTION:
KIDHAW BRANCH 4.0
END DESCRIPTION:
XS GIS Cut Line= 3
      3721367.85     10179511.07       3720746.1     10180081.98
      3720217.82     10180611.11
#Sta/Elev= 30
  4155.9  282.07    4207  277.37  4240.7  275.15    4269  271.69  4290.6  271.23
  4311.6  268.35  4346.7  266.55  4354.1  265.32  4403.5  262.13  4453.4  260.42
  4608.8  257.62  4637.1  258.13  4700.6  257.18  4778.9  258.12  4807.3  256.56
  4821.1  257.56  4863.4  258.11  4941.7  257.97  4976.9  258.76    4984  257.86
  4990.8  253.42  5000.4  253.42  5012.3  255.51 5017.19257.8503  5019.3  258.86
  5040.5  259.32  5097.1  257.32  5167.8  257.35  5316.3  259.01  5747.7  270.08
#Mann= 5 ,-1 , 0
  4155.9     .17       0    4207     .11       0    4984     .06       0
 5017.19     .09       0  5019.3     .11       0
Bank Sta=4984,5017.19
XS Rating Curve= 0 ,0
Exp/Cntr=0.3,0.1

Type RM Length L Ch R = 1 ,1750    ,423,423,423
BEGIN DESCRIPTION:
KIDHAW BRANCH 3.0
END DESCRIPTION:
XS GIS Cut Line= 3
      3721017.84     10179011.09      3720345.54      10179808.1
      3719917.87     10180311.05
#Sta/Elev= 30
  3957.3  285.98  4013.9  285.62  4042.5  283.97  4099.6  278.78  4155.6  270.67
  4226.5   265.6  4261.3  263.11  4340.2  260.55  4411.7  259.93  4454.4   257.8
  4532.6  258.64  4610.6  258.05  4688.7  256.57  4716.1     255  4723.8  255.15
  4730.3  256.62  4773.2  255.51  4844.7   255.8  4978.7  257.77    4993  256.58
  4993.3   253.8  4993.8   253.3  5003.5   253.3 5013.87256.6748  5021.6  257.59
  5029.3  256.63    5071  255.94  5277.5  261.83    5518  271.03  5660.2  272.72
#Mann= 5 ,-1 , 0
  3957.3     .11       0  4226.5     .17       0  4261.3     .11       0
    4993     .06       0 5013.87     .11       0
Bank Sta=4993,5013.87
XS Rating Curve= 0 ,0
Exp/Cntr=0.3,0.1

Type RM Length L Ch R = 1 ,1327    ,523,523,523
BEGIN DESCRIPTION:
KIDHAW BRANCH 2.0
END DESCRIPTION:
XS GIS Cut Line= 3
      3720917.84     10178361.09      3720087.57     10179517.15
      3719905.28     10180194.23
#Sta/Elev= 30
  3528.3  276.89    3586  276.74  3657.2  274.69  3671.9  275.43  3692.8  273.78
  3765.6  271.72  3808.2  270.53  3829.1  268.56  3843.8  269.19  3864.7  267.24
  3879.4   268.1  3885.6  266.85  3998.1   261.8  4158.2  255.19  4397.1  253.24
  4407.8  253.24  4632.1  253.94  4818.7  256.91  4854.3  255.01    4869  256.41
  4976.4  255.56  4997.1  253.55  5005.3   255.2  5017.8  256.08  5038.5   255.3
  5142.1  260.33  5173.1   260.1  5463.1  268.58  5514.9  271.27  5652.8  272.81
#Mann= 7 ,-1 , 0
  3528.3     .11       0  3765.6     .15       0  3998.1     .11       0
  4397.1     .11       0  4407.8     .11       0  4976.4     .07       0
  5005.3     .11       0
Bank Sta=4976.4,5005.3
XS Rating Curve= 0 ,0
Exp/Cntr=0.3,0.1

Type RM Length L Ch R = 1 ,804     ,0,0,0
BEGIN DESCRIPTION:
KIDHAW BRANCH 1.0
END DESCRIPTION:
XS GIS Cut Line= 3
      3720817.84     10178361.08      3719705.63     10179330.52
      3719848.86     10180220.26
#Sta/Elev= 30
    3255  273.03  3311.5   271.1  3436.5  264.23    3546  258.69  3566.9  258.11
  3581.1  259.59    3602  256.94  3619.5  256.04  3673.2  254.04  3687.4  254.45
  3772.3  252.28  3857.4  252.81  3923.2   251.8  3935.2   252.5  3977.9  251.89
  4119.4  252.91  4147.9  254.05  4325.4  252.77  4523.8  253.44  4658.6  252.75
  4974.1  254.75 4989.87   253.8 5008.87   253.8  5090.5  254.54  5146.2  256.44
    5207  259.02    5288  263.95  5409.9  268.79  5490.6  271.13  5631.6  272.61
#Mann= 5 ,-1 , 0
    3255     .11       0  3436.5     .15       0  3619.5     .11       0
 4989.87     .06       0 5008.87     .11       0
Bank Sta=4989.87,5008.87
XS Rating Curve= 0 ,0
Exp/Cntr=0.3,0.1

Chan Stop Cuts=-1
Use User Specified Reach Order=0
Composite Channel Slope=5