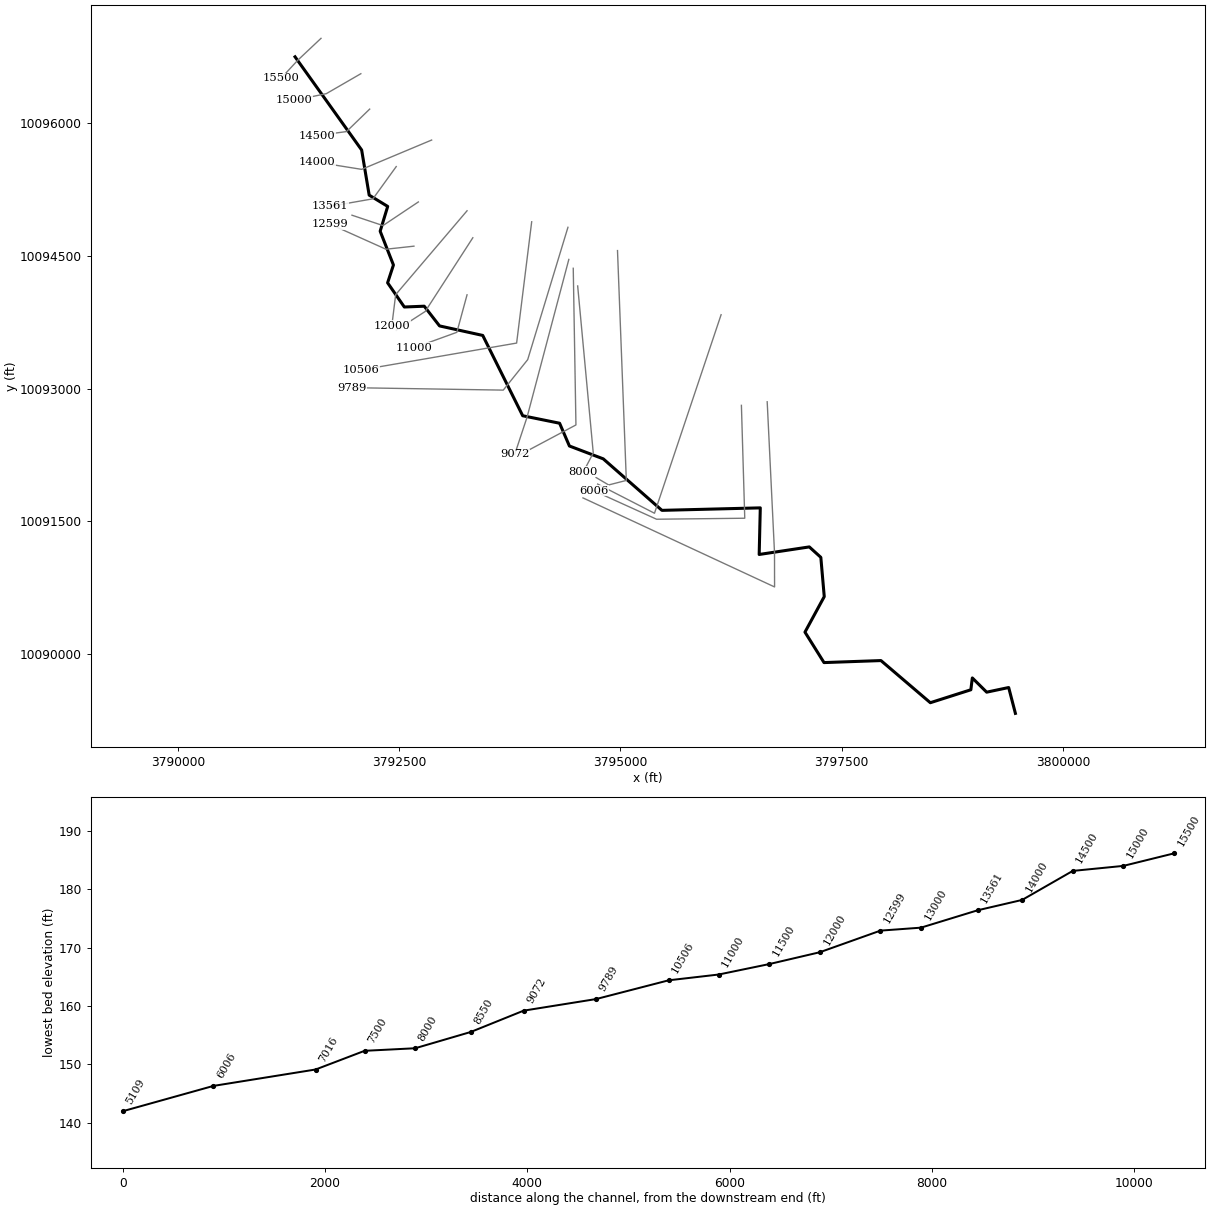
--- LAKE CREEK TRIBUTARY NO 1.prj (project) ---

Proj Title=LAKE CREEK TRIBUTARY NO 1 Base Level Engineering
Current Plan=p01
Default Exp/Contr=0.3,0.1
English Units
Geom File=g01
Flow File=f01
Flow File=f02
Plan File=p01
Y Axis Title=Elevation
X Axis Title(PF)=Main Channel Distance
X Axis Title(XS)=Station
BEGIN DESCRIPTION:
LAKE CREEK TRIBUTARY NO 1
END DESCRIPTION:
DSS Export Rating Curves= 0
DSS Export Rating Curve Sorted= 0
DSS Export Volume Flow Curves= 0
DXF OffsetX= 0
DXF OffsetY= 0
DXF ScaleX= 1
DXF ScaleY= 10

--- LAKE CREEK TRIBUTARY NO 1.p01 (plan) ---

Plan Title=Multiple Run
Short Identifier=Multiple
Geom File=g01
Flow File=f01
Subcritical Flow
K Sum by GR= 0
Std Step Tol= 0.01
Critical Tol= 0.01
Num of Std Step Trials= 20
Max Error Tol= 0.3
Flow Tol Ratio= 0.001
Split Flow NTrial= 30
Split Flow Tol= 0.02
Split Flow Ratio= 0.02
Log Output Level= 0
Friction Slope Method= 1
Unsteady Friction Slope Method= 2
Unsteady Bridges Friction Slope Method= 1
Parabolic Critical Depth
Global Vel Dist=  1 , 1 , 1
Global Log Level= 0
CheckData=True
Encroach Param= -1, 0, 0, 0
BEGIN DESCRIPTION:
Multiple Run
END DESCRIPTION:

--- LAKE CREEK TRIBUTARY NO 1.f01 (steady flow) ---

Flow Title=Multiple
Program Version=4.10
Number of Profiles= 7
Profile Names=10-year,25-year,50-year,1pct_min,100-year,1pct_plu,500-year
River Rch & RM=LAKE CREEK TRIBU,Reach-1         ,15500
     497     656     872     381    1152    3479    2076
River Rch & RM=LAKE CREEK TRIBU,Reach-1         ,5109
     920    1258    1709     763    2304    6958    4326
Boundary for River Rch & Prof#=LAKE CREEK TRIBU,Reach-1         , 1
Up Type= 0
Dn Type= 3
Dn Slope=0.005
Boundary for River Rch & Prof#=LAKE CREEK TRIBU,Reach-1         , 2
Up Type= 0
Dn Type= 3
Dn Slope=0.005
Boundary for River Rch & Prof#=LAKE CREEK TRIBU,Reach-1         , 3
Up Type= 0
Dn Type= 3
Dn Slope=0.005
Boundary for River Rch & Prof#=LAKE CREEK TRIBU,Reach-1         , 4
Up Type= 0
Dn Type= 3
Dn Slope=0.005
Boundary for River Rch & Prof#=LAKE CREEK TRIBU,Reach-1         , 5
Up Type= 0
Dn Type= 3
Dn Slope=0.005
Boundary for River Rch & Prof#=LAKE CREEK TRIBU,Reach-1         , 6
Up Type= 0
Dn Type= 3
Dn Slope=0.005
Boundary for River Rch & Prof#=LAKE CREEK TRIBU,Reach-1         , 7
Up Type= 0
Dn Type= 3
Dn Slope=0.005
DSS Import GetInterval= 0
DSS Import GetPeak= 0
DSS Import FillOption= 0

--- LAKE CREEK TRIBUTARY NO 1.f02 (steady flow) ---

Flow Title=Orig_BLE_Flows
Program Version=4.10
Number of Profiles= 7
Profile Names=10-year,25-year,50-year,1pct_min,100-year,1pct_plu,500-year
River Rch & RM=LAKE CREEK TRIBU,Reach-1         ,15500
     497     643     758     293     886    2675    1207
River Rch & RM=LAKE CREEK TRIBU,Reach-1         ,5109
     920    1233    1486     587    1772    5350    2515
Boundary for River Rch & Prof#=LAKE CREEK TRIBU,Reach-1         , 1
Up Type= 0
Dn Type= 3
Dn Slope=0.005
Boundary for River Rch & Prof#=LAKE CREEK TRIBU,Reach-1         , 2
Up Type= 0
Dn Type= 3
Dn Slope=0.005
Boundary for River Rch & Prof#=LAKE CREEK TRIBU,Reach-1         , 3
Up Type= 0
Dn Type= 3
Dn Slope=0.005
Boundary for River Rch & Prof#=LAKE CREEK TRIBU,Reach-1         , 4
Up Type= 0
Dn Type= 3
Dn Slope=0.005
Boundary for River Rch & Prof#=LAKE CREEK TRIBU,Reach-1         , 5
Up Type= 0
Dn Type= 3
Dn Slope=0.005
Boundary for River Rch & Prof#=LAKE CREEK TRIBU,Reach-1         , 6
Up Type= 0
Dn Type= 3
Dn Slope=0.005
Boundary for River Rch & Prof#=LAKE CREEK TRIBU,Reach-1         , 7
Up Type= 0
Dn Type= 3
Dn Slope=0.005
DSS Import GetInterval= 0
DSS Import GetPeak= 0
DSS Import FillOption= 0

--- LAKE CREEK TRIBUTARY NO 1.g01 (geometry) ---

Geom Title=Existing Conditions
Program Version=4.10

River Reach=LAKE CREEK TRIBU,Reach-1
Reach XY= 30
      3791324.44     10096752.01      3792077.02     10095698.52
      3792162.09     10095188.11      3792371.29      10095060.5
      3792286.22     10094780.12      3792436.22     10094398.17
      3792370.25     10094196.79      3792559.14     10093923.17
      3792784.14      10093932.2      3792957.06     10093709.29
      3793445.25     10093601.65      3793896.64     10092693.57
      3794313.65     10092608.85      3794424.42     10092351.56
      3794807.06     10092206.07       3795469.9     10091623.78
      3796581.25     10091651.88      3796568.65     10091124.88
      3797135.05     10091210.38      3797265.26     10091092.33
      3797303.89     10090648.31      3797086.01     10090246.84
      3797301.22     10089902.48       3797944.7     10089925.22
      3798502.51     10089448.66      3798960.32     10089595.01
      3798976.99     10089728.87      3799138.97     10089567.93
      3799387.76     10089620.45      3799463.67     10089328.12

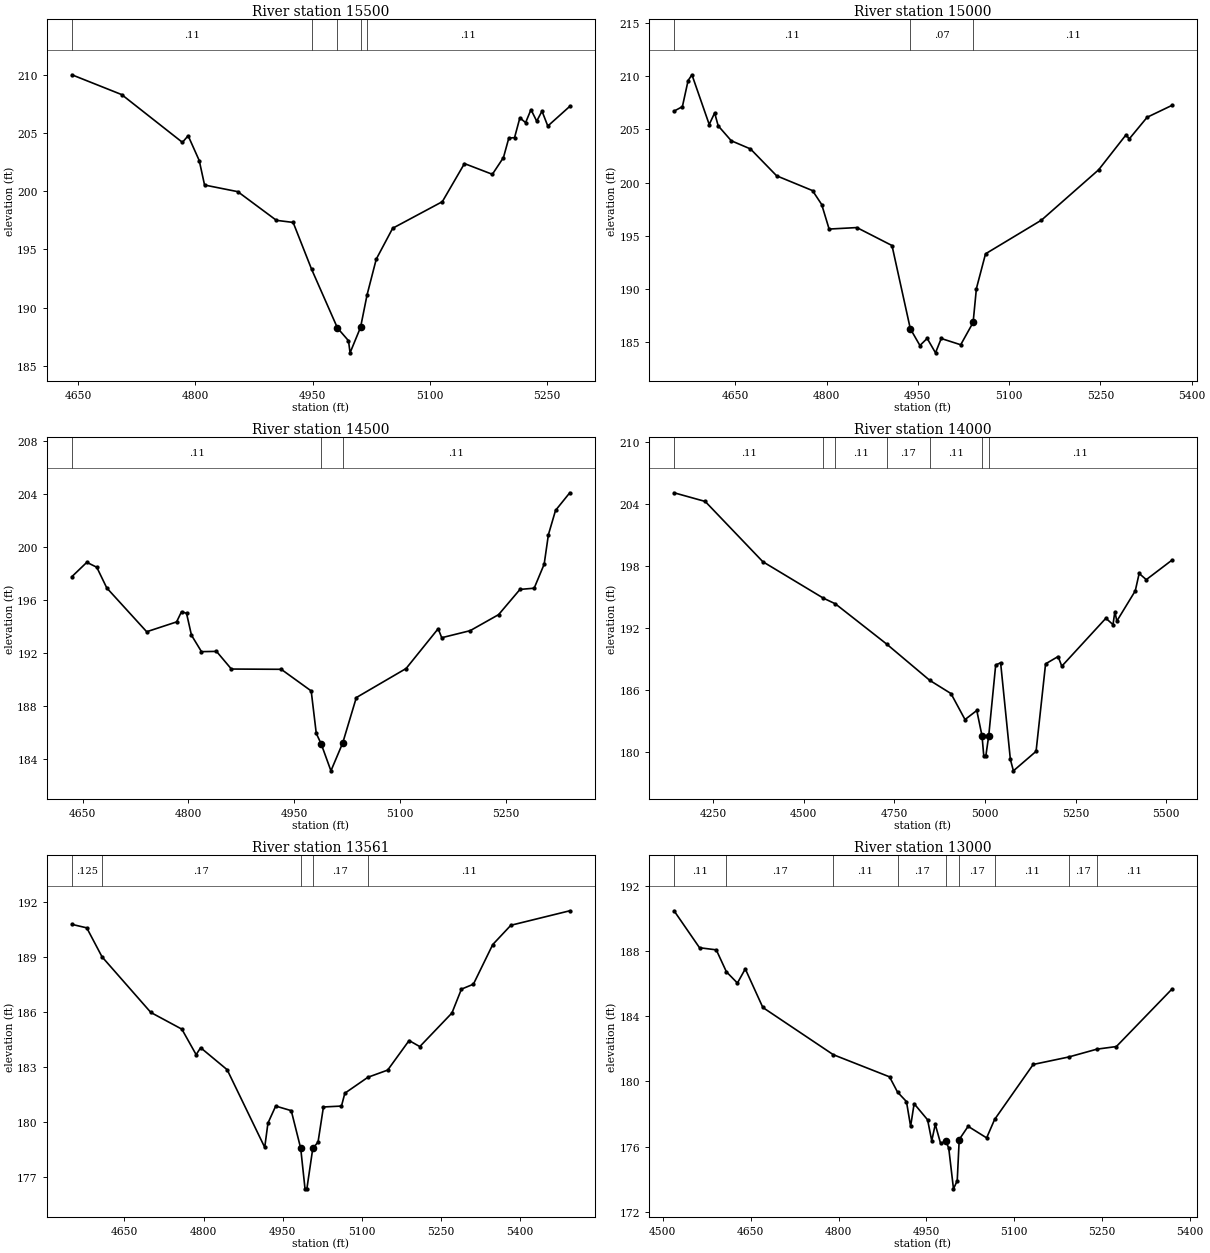
Type RM Length L Ch R = 1 ,15500   ,500,500,500
BEGIN DESCRIPTION:
LAKE CREEK TRIBUTARY NO. 1 31.0
END DESCRIPTION:
XS GIS Cut Line= 3
      3791617.86     10096961.08       3791357.4     10096715.61
      3791167.83     10096511.05
#Sta/Elev= 30
  4642.1  209.98  4705.8  208.28  4783.5  204.18  4790.8  204.75    4805  202.62
  4811.8  200.52  4854.3  199.95  4903.7  197.49  4925.1  197.31  4948.6  193.31
  4981.8  188.25  4995.9  187.16  4997.9  186.12 5011.34188.3149  5019.7  191.11
  5031.4  194.16  5052.4  196.81  5115.9  199.09  5144.2  202.36  5179.9  201.44
  5194.1  202.88  5200.9  204.54  5208.3  204.59  5215.1  206.29  5222.4  205.87
  5229.3  206.99  5236.6     206  5243.4  206.86  5250.8  205.58  5278.9  207.27
#Mann= 5 ,-1 , 0
  4642.1     .11       0  4948.6    .125       0  4981.8     .09       0
 5011.34    .125       0  5019.7     .11       0
Bank Sta=4981.8,5011.34
XS Rating Curve= 0 ,0
Exp/Cntr=0.3,0.1

Type RM Length L Ch R = 1 ,15000   ,500,500,500
BEGIN DESCRIPTION:
LAKE CREEK TRIBUTARY NO. 1 30.0
END DESCRIPTION:
XS GIS Cut Line= 3
      3792067.85     10096561.07      3791677.79     10096335.48
       3791317.9     10096261.08
#Sta/Elev= 30
  4549.4  206.73  4563.1  207.15  4572.5  209.61  4578.8  210.15  4607.2  205.47
  4616.1  206.56  4621.9  205.35  4643.4  203.94    4675  203.17    4718  200.64
  4776.9  199.25    4792  197.94  4804.2  195.63  4849.8  195.77  4907.5  194.08
  4937.6  186.25  4953.4  184.67  4965.3  185.34    4979  183.98  4988.4  185.33
  5020.4  184.74  5040.8  186.84  5046.2  190.03  5061.2   193.3  5153.1  196.47
  5247.1  201.21  5292.2  204.51  5297.3  204.11  5326.7  206.15  5367.5  207.27
#Mann= 3 ,-1 , 0
  4549.4     .11       0  4937.6     .07       0  5040.8     .11       0
Bank Sta=4937.6,5040.8
XS Rating Curve= 0 ,0
Exp/Cntr=0.3,0.1

Type RM Length L Ch R = 1 ,14500   ,500,500,500
BEGIN DESCRIPTION:
LAKE CREEK TRIBUTARY NO. 1 29.0
END DESCRIPTION:
XS GIS Cut Line= 3
      3792167.82     10096161.04      3791905.57     10095906.74
      3791567.84     10095861.07
#Sta/Elev= 30
  4634.7  197.75  4655.9  198.83    4670  198.46  4684.2   196.9  4740.8   193.6
  4783.2  194.34  4790.2  195.11  4797.3  194.99  4804.3  193.34  4818.5   192.1
  4839.8  192.12  4860.9  190.79  4931.6  190.77  4974.1  189.14  4981.3  185.94
  4988.2  185.16  5002.1  183.12 5018.75185.2127  5038.1  188.64  5108.7  190.83
  5154.2  193.83  5159.2  193.15  5199.5  193.68  5239.9  194.89  5270.2  196.79
  5290.3  196.88  5304.5  198.69  5310.5  200.91  5320.6  202.74  5340.8  204.07
#Mann= 3 , 0 , 0
  4634.7     .11       0  4988.2     .06       0 5018.75     .11       0
Bank Sta=4988.2,5018.75
XS Rating Curve= 0 ,0
Exp/Cntr=0.3,0.1

Type RM Length L Ch R = 1 ,14000   ,439,439,439
BEGIN DESCRIPTION:
LAKE CREEK TRIBUTARY NO. 1 28.0
END DESCRIPTION:
XS GIS Cut Line= 3
      3792867.82     10095811.06      3792077.01     10095479.51
       3791567.9     10095561.06
#Sta/Elev= 30
  4142.5   205.1  4228.4  204.26  4387.3  198.42  4554.1  194.89  4587.2  194.34
  4728.4  190.45  4847.7  186.92  4906.2  185.64  4944.9  183.12  4977.4     184
 4991.83  181.54  4996.8  179.54  5002.1  179.54 5010.41  181.57  5029.5   188.4
  5043.1  188.63    5070  179.26  5078.4  178.15  5140.9  180.04  5167.1  188.52
  5201.7  189.23  5211.8  188.29  5333.4  192.94  5353.1  192.32  5358.1  193.57
  5363.7  192.67  5414.4  195.59  5425.2  197.28  5444.8  196.68  5515.6  198.57
#Mann= 7 ,-1 , 0
  4142.5     .11       0  4554.1    .125       0  4587.2     .11       0
  4728.4     .17       0  4847.7     .11       0 4991.83     .06       0
 5010.41     .11       0
#Block Obstruct= 2 , 0
                         5043.23          188.55
Bank Sta=4991.83,5010.41
XS Rating Curve= 0 ,0
Exp/Cntr=0.3,0.1

Type RM Length L Ch R = 1 ,13561   ,561,561,561
BEGIN DESCRIPTION:
LAKE CREEK TRIBUTARY NO. 1 27.0
END DESCRIPTION:
XS GIS Cut Line= 3
      3792467.84     10095511.06      3792204.62     10095146.44
      3791717.85     10095061.07
#Sta/Elev= 30
  4550.3  190.79  4578.5   190.6  4607.5  189.02    4700  185.99  4758.8  185.08
  4785.9  183.69  4794.4  184.07  4844.7  182.87  4915.9  178.64    4922  179.96
  4936.7  180.89  4966.2  180.64 4984.12178.5859  4992.3  176.38  4995.8  176.38
    5007  178.58    5017  178.93  5027.2  180.84  5061.4  180.89  5067.8  181.59
  5111.6  182.46    5149  182.85  5189.6  184.46  5209.9  184.13  5270.8  185.96
  5288.8  187.26  5311.5  187.53  5348.2  189.69  5382.5  190.74  5494.2  191.53
#Mann= 5 ,-1 , 0
  4550.3    .125       0  4607.5     .17       0 4984.12     .09       0
    5007     .17       0  5111.6     .11       0
Bank Sta=4984.12,5007
XS Rating Curve= 0 ,0
Exp/Cntr=0.3,0.1

Type RM Length L Ch R = 1 ,13000   ,401,401,401
BEGIN DESCRIPTION:
LAKE CREEK TRIBUTARY NO. 1 26.0
END DESCRIPTION:
XS GIS Cut Line= 3
      3792717.82     10095111.05      3792318.04     10094843.94
      3791967.81     10094961.08
#Sta/Elev= 30
  4519.2  190.48  4562.7  188.21  4591.3  188.08  4608.6  186.73  4627.4  186.04
  4640.8  186.91  4670.8  184.54  4791.1  181.64  4887.1  180.28  4900.8  179.34
    4916  178.76  4923.1  177.24  4929.1  178.63  4952.1  177.64  4959.2  176.35
  4965.2  177.36  4974.2   176.2 4983.36176.3235  4988.2   175.9  4996.3   173.4
  5002.7   173.9  5006.1  176.43  5021.3  177.24  5052.9  176.53  5066.5  177.66
  5132.4  181.04  5193.2   181.5  5241.2  181.98  5274.4  182.14  5369.3  185.67
#Mann= 9 ,-1 , 0
  4519.2     .11       0  4608.6     .17       0  4791.1     .11       0
  4900.8     .17       0 4983.36     .09       0  5006.1     .17       0
  5066.5     .11       0  5193.2     .17       0  5241.2     .11       0
Bank Sta=4983.36,5006.1
XS Rating Curve= 0 ,0
Exp/Cntr=0.3,0.1

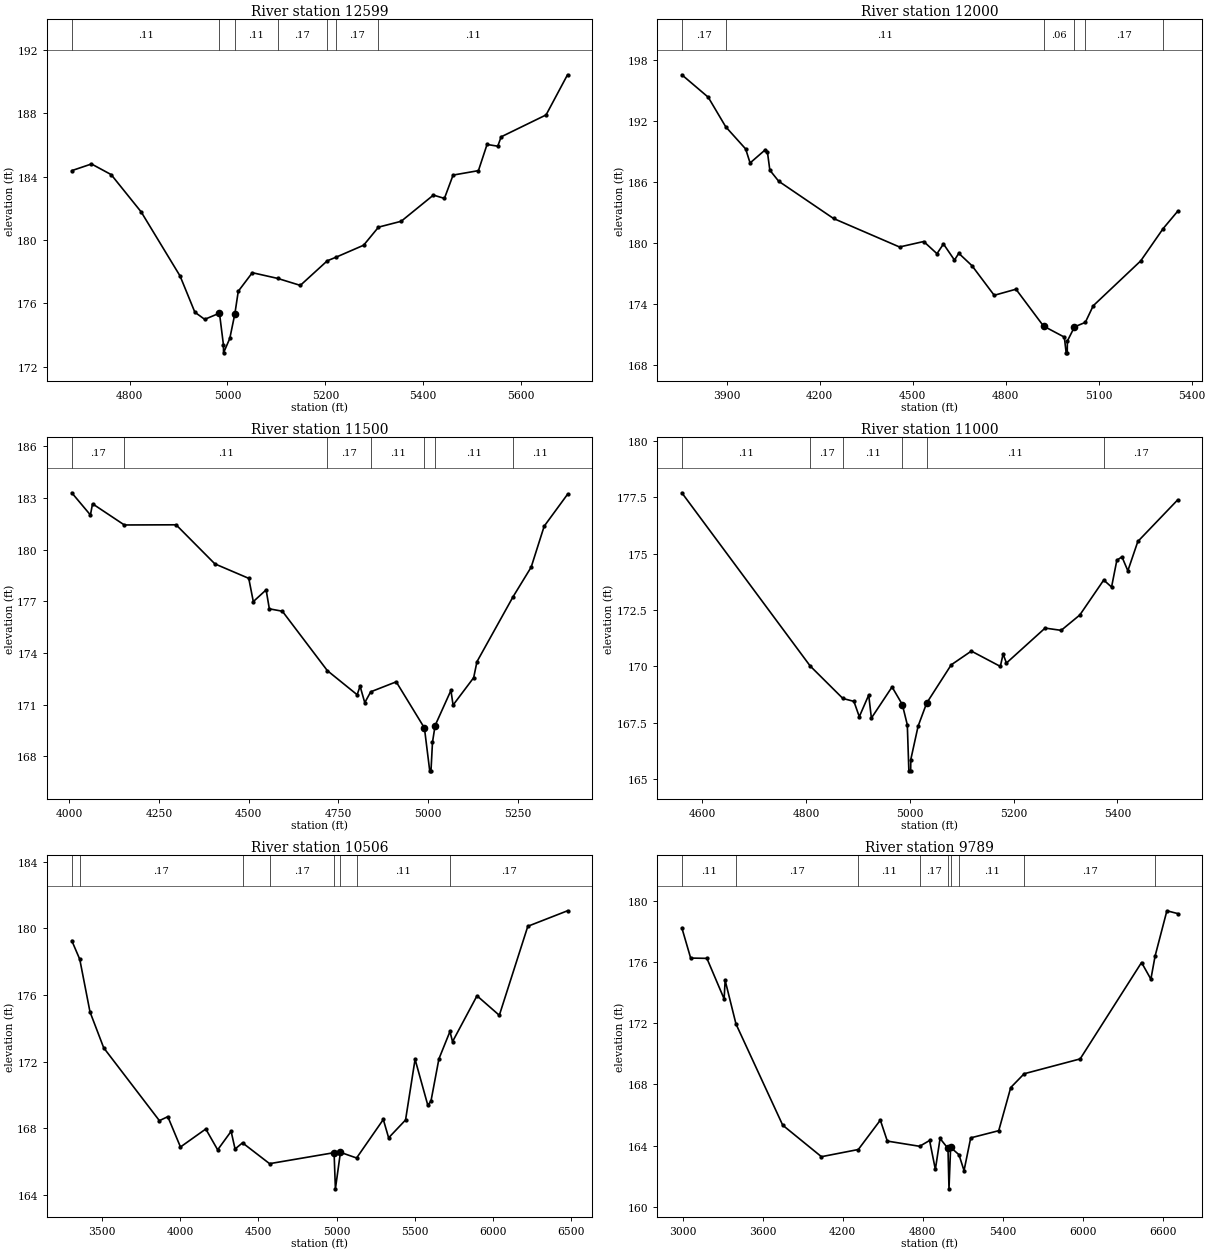
Type RM Length L Ch R = 1 ,12599   ,599,599,599
BEGIN DESCRIPTION:
LAKE CREEK TRIBUTARY NO. 1 25.0
END DESCRIPTION:
XS GIS Cut Line= 3
      3792667.88     10094611.07      3792351.67     10094576.41
      3791717.86     10094861.07
#Sta/Elev= 30
  4681.9  184.37  4722.2  184.79  4762.4  184.12  4823.7  181.77  4903.2  177.73
  4933.4  175.45  4953.5     175  4983.7  175.39  4991.8  173.39    4992  172.89
  5004.8   173.8  5015.2  175.36  5022.1  176.77  5050.8  177.94  5102.5  177.58
  5148.9  177.14    5204  178.69  5221.4  178.91  5278.2  179.67  5308.6  180.81
    5355  181.18  5420.8  182.83  5443.3  182.62    5461  184.09  5512.8  184.37
  5530.4  186.02  5552.3  185.91  5559.2   186.5    5651  187.88  5694.8  190.41
#Mann= 7 ,-1 , 0
  4681.9     .11       0  4983.7     .07       0  5015.2     .11       0
  5102.5     .17       0    5204     .11       0  5221.4     .17       0
  5308.6     .11       0
Bank Sta=4983.7,5015.2
XS Rating Curve= 0 ,0
Exp/Cntr=0.3,0.1

Type RM Length L Ch R = 1 ,12000   ,500,500,500
BEGIN DESCRIPTION:
LAKE CREEK TRIBUTARY NO. 1 24.0
END DESCRIPTION:
XS GIS Cut Line= 3
      3793267.86     10095011.08      3792461.46     10094062.78
      3792417.85     10093711.08
#Sta/Elev= 30
  3755.2  196.59  3840.3  194.38  3896.9  191.46  3961.1  189.28  3975.4   187.9
  4024.8  189.21  4031.4  188.97  4039.1  187.19  4067.7   186.1  4244.5  182.43
  4457.5  179.62  4535.5  180.16  4578.3  178.96  4599.2  179.92  4634.7  178.33
  4648.6     179  4691.4  177.77  4762.9  174.86  4833.1  175.46 4921.91 171.829
  4989.1  170.74    4995  169.19  4998.5  169.19  4998.9  170.35  5021.9  171.75
  5056.8  172.19  5082.3  173.83  5235.5  178.25    5308  181.44  5354.4  183.13
#Mann= 6 ,-1 , 0
  3755.2     .17       0  3896.9     .11       0 4921.91     .06       0
  5021.9     .11       0  5056.8     .17       0    5308     .11       0
Bank Sta=4921.91,5021.9
XS Rating Curve= 0 ,0
Exp/Cntr=0.3,0.1

Type RM Length L Ch R = 1 ,11500   ,500,500,500
BEGIN DESCRIPTION:
LAKE CREEK TRIBUTARY NO. 1 23.0
END DESCRIPTION:
XS GIS Cut Line= 3
      3793333.26     10094706.29      3792794.82      10093872.3
      3792467.82     10093661.05
#Sta/Elev= 30
  4007.3  183.31  4059.3  182.02  4065.2  182.67  4153.9  181.44  4298.1  181.45
  4406.3  179.18  4500.7  178.34  4513.4  176.99  4549.1  177.67  4558.1  176.57
  4594.4  176.43  4719.8  172.98  4802.9  171.58    4811  172.08  4824.1  171.12
  4840.7  171.75  4911.8  172.33  4990.4  169.65  5005.2  167.16  5008.7  167.16
  5012.9  168.82  5020.2  169.79  5064.3  171.83  5070.3  170.98  5127.7  172.57
  5136.9   173.5  5237.5  177.27    5288  178.99  5324.3  181.37  5389.3  183.22
#Mann= 7 ,-1 , 0
  4007.3     .17       0  4153.9     .11       0  4719.8     .17       0
  4840.7     .11       0  4990.4     .06       0  5020.2     .11       0
  5237.5     .11       0
Bank Sta=4990.4,5020.2
XS Rating Curve= 0 ,0
Exp/Cntr=0.3,0.1

Type RM Length L Ch R = 1 ,11000   ,494,494,494
BEGIN DESCRIPTION:
LAKE CREEK TRIBUTARY NO. 1 22.0
END DESCRIPTION:
XS GIS Cut Line= 3
      3793267.86     10094061.12      3793152.71     10093636.97
      3792667.83     10093461.07
#Sta/Elev= 30
  4560.5   177.7  4807.8  170.02  4870.8  168.58  4892.1  168.45  4902.5  167.77
  4920.6  168.73  4925.8  167.71  4965.6  169.09  4985.4  168.31    4995  167.41
    4998  165.37  5001.5  165.37  5001.7  165.87  5015.8  167.35 5032.28168.3735
  5079.6  170.07  5118.4  170.68  5174.3     170  5179.6  170.55    5186  170.15
  5260.5   171.7  5291.5   171.6  5327.4  172.28  5373.5  173.83  5388.6  173.52
  5398.8  174.71  5408.6  174.86    5420  174.24  5439.2  175.54  5515.8  177.38
#Mann= 6 ,-1 , 0
  4560.5     .11       0  4807.8     .17       0  4870.8     .11       0
  4985.4     .06       0 5032.28     .11       0  5373.5     .17       0
Bank Sta=4985.4,5032.28
XS Rating Curve= 0 ,0
Exp/Cntr=0.3,0.1

Type RM Length L Ch R = 1 ,10506   ,717,717,717
BEGIN DESCRIPTION:
LAKE CREEK TRIBUTARY NO. 1 21.0
END DESCRIPTION:
XS GIS Cut Line= 3
       3793998.2     10094886.83      3793828.07     10093515.34
      3792067.88     10093211.08
#Sta/Elev= 30
  3307.6  179.27  3358.7  178.15  3424.2  174.99  3511.7  172.84  3867.6  168.47
  3921.4  168.71  4002.3  166.89  4164.1  167.97    4240  166.72    4326  167.83
  4351.3  166.77  4398.8  167.14  4571.8  165.89  4984.1  166.55  4992.5  164.38
  5024.7  166.57  5127.9  166.23  5298.7  168.54  5332.7  167.44  5440.8  168.51
  5501.7  172.15  5582.9   169.4  5603.2  169.64  5653.9  172.17  5724.6  173.82
  5741.1  173.21  5897.5  175.96  6040.1  174.79  6222.2  180.13  6475.9  181.06
#Mann= 8 ,-1 , 0
  3307.6     .11       0  3358.7     .17       0  4398.8     .11       0
  4571.8     .17       0  4984.1     .09       0  5024.7     .17       0
  5127.9     .11       0  5724.6     .17       0
Bank Sta=4984.1,5024.7
XS Rating Curve= 0 ,0
Exp/Cntr=0.3,0.1

Type RM Length L Ch R = 1 ,9789    ,717,717,717
BEGIN DESCRIPTION:
LAKE CREEK TRIBUTARY NO. 1 19.0
END DESCRIPTION:
XS GIS Cut Line= 4
      3794407.93     10094824.38      3793953.07     10093327.84
      3793677.02     10092983.33      3791967.85     10093011.07
#Sta/Elev= 30
  2994.4  178.23  3060.6  176.25  3182.3  176.23  3311.4  173.58    3319  174.79
  3400.3  171.94  3750.4  165.33  4040.6  163.27    4317  163.74    4482  165.66
  4534.3  164.29  4776.5  163.95  4851.1  164.33  4894.3  162.44  4929.6  164.46
 4988.88163.8102  4996.5  161.17 5008.69 163.879  5071.2   163.4  5109.2  162.36
  5159.2   164.5  5369.2  164.97  5459.2  167.79  5559.7  168.69  5979.3  169.66
  6439.4  175.96  6509.4  174.87  6540.9  176.38  6629.4  179.34  6709.4  179.16
#Mann= 9 ,-1 , 0
  2994.4     .11       0  3400.3     .17       0    4317     .11       0
  4776.5     .17       0 4988.88     .09       0 5008.69     .17       0
  5071.2     .11       0  5559.7     .17       0  6540.9     .11       0
Bank Sta=4988.88,5008.69
XS Rating Curve= 0 ,0
Exp/Cntr=0.3,0.1

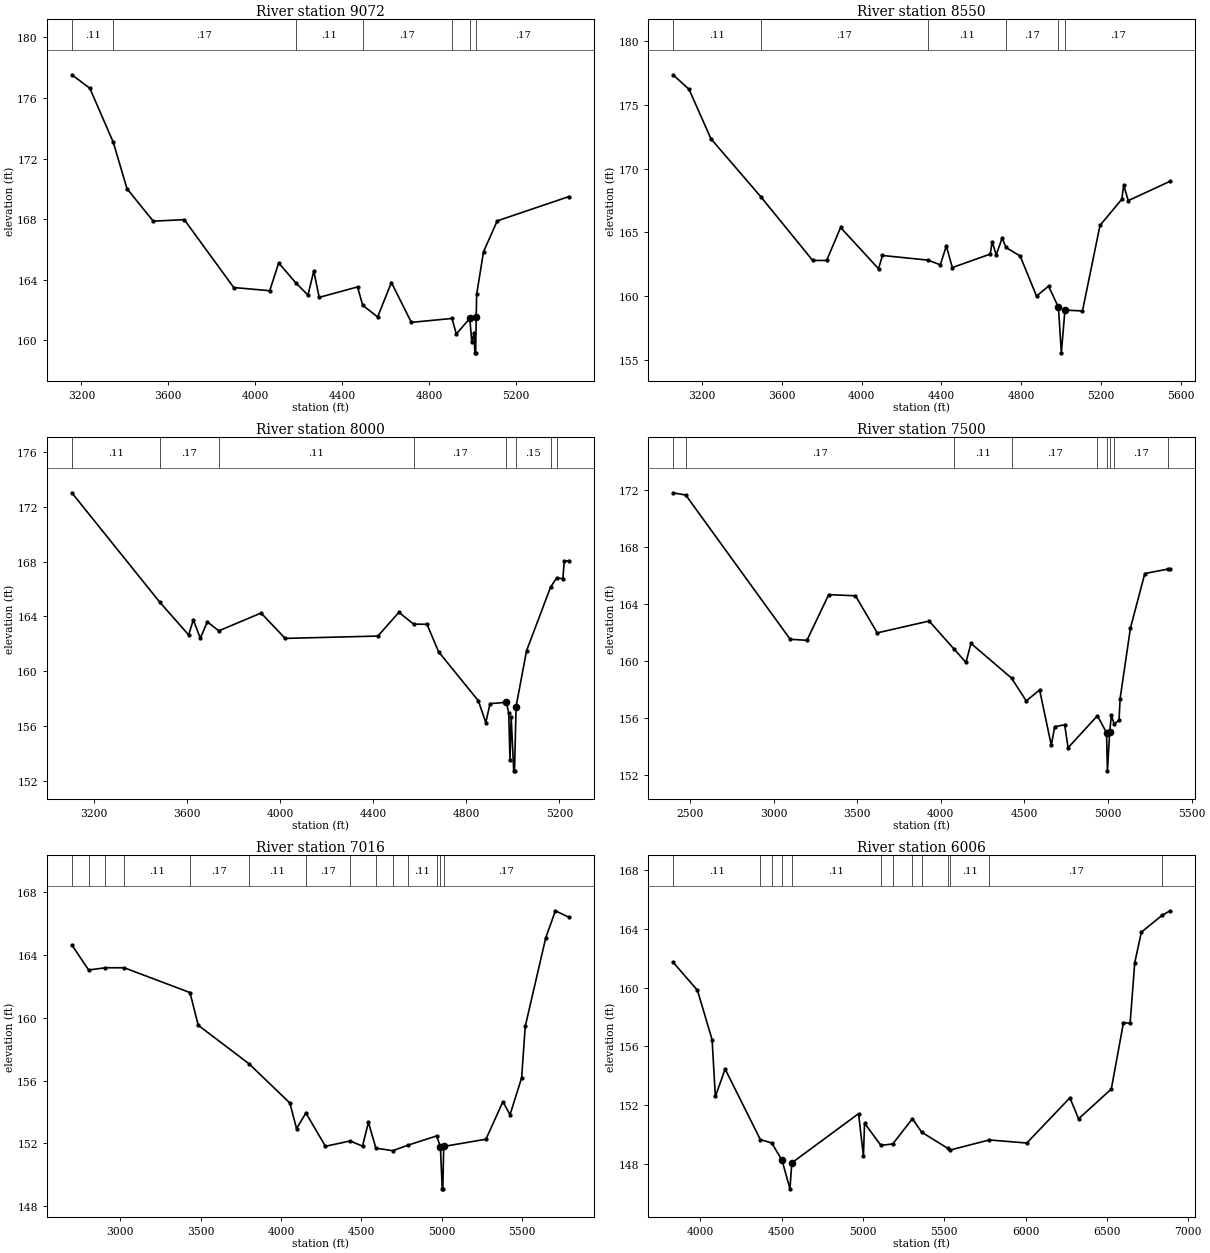
Type RM Length L Ch R = 1 ,9072    ,522,522,522
BEGIN DESCRIPTION:
LAKE CREEK TRIBUTARY NO. 1 18.0
END DESCRIPTION:
XS GIS Cut Line= 3
      3794417.86     10094461.12      3793946.29     10092678.64
      3793807.22     10092258.35
#Sta/Elev= 30
  3156.2  177.53    3239  176.64  3346.7  173.08    3410  170.01  3530.7  167.87
  3673.5  167.97    3901  163.49  4066.5  163.28  4107.9  165.11  4185.9  163.81
  4242.4  162.99  4269.4  164.58  4294.1  162.84  4470.6  163.53  4494.2  162.32
    4563  161.55  4626.4  163.82  4718.2  161.19  4905.2  161.45  4925.1  160.42
  4987.1  161.46  4996.2  159.88  5006.8  160.51  5010.3  159.18  5013.8  159.18
 5016.53161.5299  5018.5  163.03  5050.1  165.85  5113.3  167.89  5442.7  169.49
#Mann= 7 ,-1 , 0
  3156.2     .11       0  3346.7     .17       0  4185.9     .11       0
  4494.2     .17       0  4905.2     .11       0  4987.1     .06       0
 5016.53     .17       0
Bank Sta=4987.1,5016.53
XS Rating Curve= 0 ,0
Exp/Cntr=0.3,0.1

Type RM Length L Ch R = 1 ,8550    ,550,550,550
BEGIN DESCRIPTION:
LAKE CREEK TRIBUTARY NO. 1 17.0
END DESCRIPTION:
XS GIS Cut Line= 3
      3794467.85     10094361.04      3794498.27      10092589.5
       3793862.6     10092250.96
#Sta/Elev= 30
    3055  177.38    3135  176.24    3245  172.35  3494.8   167.8  3755.1  162.79
  3825.1  162.79  3895.1  165.38  4085.1  162.14  4105.1  163.18    4331  162.82
  4395.2  162.45  4425.2  163.93  4455.2  162.23  4645.2  163.29  4655.2  164.26
  4675.2  163.23  4705.2  164.56  4724.2  163.81  4795.2  163.14  4877.4  159.99
  4937.7  160.77  4987.3  159.11  5001.8  155.53  5019.9  158.89  5107.8  158.82
  5195.6  165.54  5305.5  167.61  5314.5  168.73  5337.1  167.49    5547  169.01
#Mann= 6 ,-1 , 0
    3055     .11       0  3494.8     .17       0    4331     .11       0
  4724.2     .17       0  4987.3     .09       0  5019.9     .17       0
Bank Sta=4987.3,5019.9
XS Rating Curve= 0 ,0
Exp/Cntr=0.3,0.1

Type RM Length L Ch R = 1 ,8000    ,500,500,500
BEGIN DESCRIPTION:
LAKE CREEK TRIBUTARY NO. 1 16.0
END DESCRIPTION:
XS GIS Cut Line= 3
      3794517.85     10094161.05      3794693.98     10092273.05
      3794582.85     10092059.88
#Sta/Elev= 30
  3103.8  173.02    3481  165.06    3606  162.65    3626  163.75  3656.2  162.41
  3686.3  163.61  3735.4  162.95  3917.3  164.25  4020.8   162.4  4419.5  162.57
  4509.9   164.3    4573  163.44  4630.4  163.43  4680.6  161.42  4851.3  157.85
  4883.3  156.26  4901.6  157.64  4971.9  157.74  4981.9  156.96  4987.4  153.54
  4992.4   156.7  5003.4  152.74  5006.9  152.74  5013.5  157.43  5058.6   161.5
  5162.1  166.15    5188   166.8  5214.8  166.76  5220.5  168.01  5240.4  168.07
#Mann= 8 ,-1 , 0
  3103.8     .11       0    3481     .17       0  3735.4     .11       0
    4573     .17       0  4971.9     .09       0  5013.5     .15       0
  5162.1     .17       0    5188     .11       0
Bank Sta=4971.9,5013.5
XS Rating Curve= 0 ,0
Exp/Cntr=0.3,0.1

Type RM Length L Ch R = 1 ,7500    ,484,484,484
BEGIN DESCRIPTION:
LAKE CREEK TRIBUTARY NO. 1 15.0
END DESCRIPTION:
XS GIS Cut Line= 4
      3794967.85     10094561.08      3795067.65     10091962.19
      3794867.85     10091911.07      3794726.04     10091994.77
#Sta/Elev= 30
  2399.2  171.79  2475.1  171.63  3099.7  161.52  3199.8  161.45  3329.9  164.65
    3490  164.57  3620.1  161.97  3930.3   162.8  4076.8  160.87  4150.5   159.9
  4180.5  161.23  4423.2   158.8  4510.8   157.2  4590.8  157.97  4660.9  154.09
  4680.9  155.39  4740.9  155.53  4760.9  153.92  4936.6  156.16  4991.1  154.97
  4996.3   152.3  5010.1  155.04    5020  156.19  5037.1  155.57    5066  155.86
    5072  157.35    5134  162.31  5219.9  166.13  5361.3  166.45  5370.9  166.43
#Mann= 9 ,-1 , 0
  2399.2     .11       0  2475.1     .17       0  4076.8     .11       0
  4423.2     .17       0  4936.6     .11       0  4991.1     .06       0
  5010.1     .11       0  5037.1     .17       0  5361.3     .11       0
Bank Sta=4991.1,5010.1
XS Rating Curve= 0 ,0
Exp/Cntr=0.3,0.1

Type RM Length L Ch R = 1 ,7016    ,1010,1010,1010
BEGIN DESCRIPTION:
LAKE CREEK TRIBUTARY NO. 1 14.0
END DESCRIPTION:
XS GIS Cut Line= 3
       3796138.4      10093835.9      3795385.79     10091591.11
      3794743.43     10091920.97
#Sta/Elev= 30
  2699.8  164.64    2804  163.04    2909  163.18  3025.8  163.18  3434.3   161.6
  3485.4  159.52  3800.7  157.07  4054.9  154.57  4096.6  152.94  4155.1  153.93
  4276.4  151.81  4429.9  152.15  4506.8  151.82  4543.6  153.34    4590  151.69
  4695.1  151.53  4789.2  151.88  4967.5  152.47 4990.99151.7816  5002.4   149.1
  5005.9   149.1  5011.6   151.8  5274.2  152.26  5379.5  154.65  5423.8  153.82
    5496  156.17  5518.2  159.44  5645.7  165.08  5705.8  166.81  5789.5   166.4
#Mann= 14 ,-1 , 0
  2699.8     .17       0    2804     .11       0    2909     .17       0
  3025.8     .11       0  3434.3     .17       0  3800.7     .11       0
  4155.1     .17       0  4429.9     .15       0    4590     .11       0
  4695.1     .17       0  4789.2     .11       0  4967.5     .17       0
 4990.99     .09       0  5011.6     .17       0
Bank Sta=4990.99,5011.6
XS Rating Curve= 0 ,0
Exp/Cntr=0.3,0.1

Type RM Length L Ch R = 1 ,6006    ,897,897,897
BEGIN DESCRIPTION:
LAKE CREEK TRIBUTARY NO. 1 12.0
END DESCRIPTION:
XS GIS Cut Line= 4
      3796367.85      10092811.1      3796405.76     10091534.69
      3795409.23      10091523.4       3794696.9     10091846.64
#Sta/Elev= 30
  3832.6  161.73  3982.7  159.81  4072.7  156.45  4092.7  152.58  4152.8  154.45
  4369.2  149.65  4439.6  149.41  4502.9  148.23  4551.2  146.29  4562.9  148.06
  4973.1  151.41  5003.1  148.52  5009.9  150.76  5110.7  149.25  5183.5  149.35
  5304.5  151.07    5361  150.15  5522.9  149.04  5535.1  148.93  5776.8  149.62
  6007.5  149.41  6272.4  152.49  6326.1  151.06  6527.2  153.09    6602  157.62
  6642.7  157.56  6671.2  161.69  6711.7  163.77  6840.5  164.93  6888.4  165.23
#Mann= 13 ,-1 , 0
  3832.6     .11       0  4369.2     .17       0  4439.6     .11       0
  4502.9     .06       0  4562.9     .11       0  5110.7     .17       0
  5183.5     .11       0  5304.5     .17       0    5361     .11       0
  5522.9     .17       0  5535.1     .11       0  5776.8     .17       0
  6840.5     .11       0
Bank Sta=4502.9,4562.9
XS Rating Curve= 0 ,0
Exp/Cntr=0.3,0.1

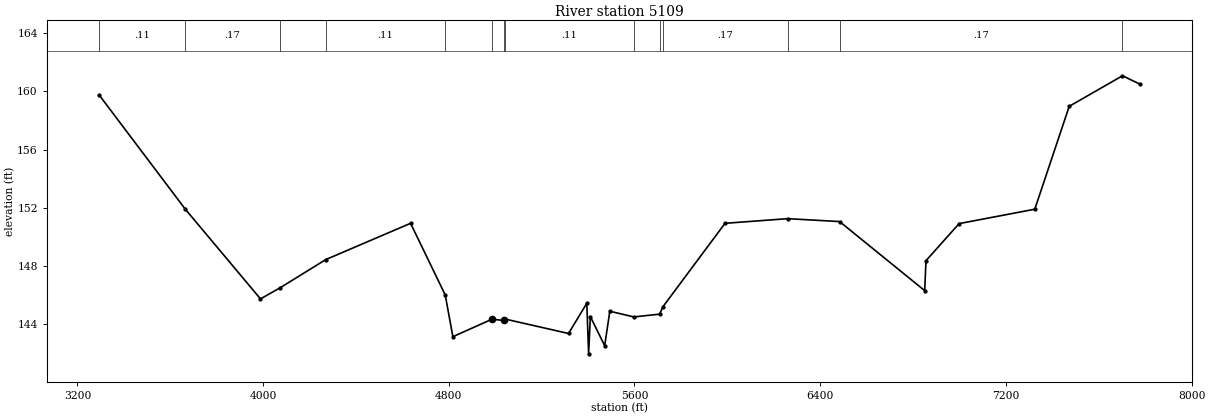
Type RM Length L Ch R = 1 ,5109    ,0,0,0
BEGIN DESCRIPTION:
LAKE CREEK TRIBUTARY NO. 1 10.0
END DESCRIPTION:
XS GIS Cut Line= 4
      3796659.23     10092851.51      3796741.82     10091147.01
      3796742.56     10090757.78      3794577.78     10091764.59
#Sta/Elev= 30
  3293.5  159.77  3664.7  151.91    3989  145.73  4072.1  146.48  4269.6  148.43
  4635.5  150.93  4784.8     146  4817.7  143.13  4985.9  144.33  5035.9  144.25
  5040.5  144.35  5315.9  143.35  5394.6  145.43  5402.4  141.95  5409.9  144.51
  5471.6  142.51  5493.7  144.88  5597.3  144.49  5708.1  144.68  5722.5  145.19
    5990  150.93    6260  151.25  6483.5  151.05    6850   146.3  6855.6  148.36
  6998.4  150.91  7324.3   151.9  7472.6  158.98    7702  161.08  7776.7  160.51
#Mann= 14 ,-1 , 0
  3293.5     .11       0  3664.7     .17       0  4072.1     .15       0
  4269.6     .11       0  4784.8     .17       0  4985.9     .09       0
  5035.9     .17       0  5040.5     .11       0  5597.3     .17       0
  5708.1     .15       0  5722.5     .17       0    6260     .11       0
  6483.5     .17       0    7702     .11       0
Bank Sta=4985.9,5035.9
XS Rating Curve= 0 ,0
Exp/Cntr=0.3,0.1

Chan Stop Cuts=-1
Use User Specified Reach Order=0
Composite Channel Slope=5