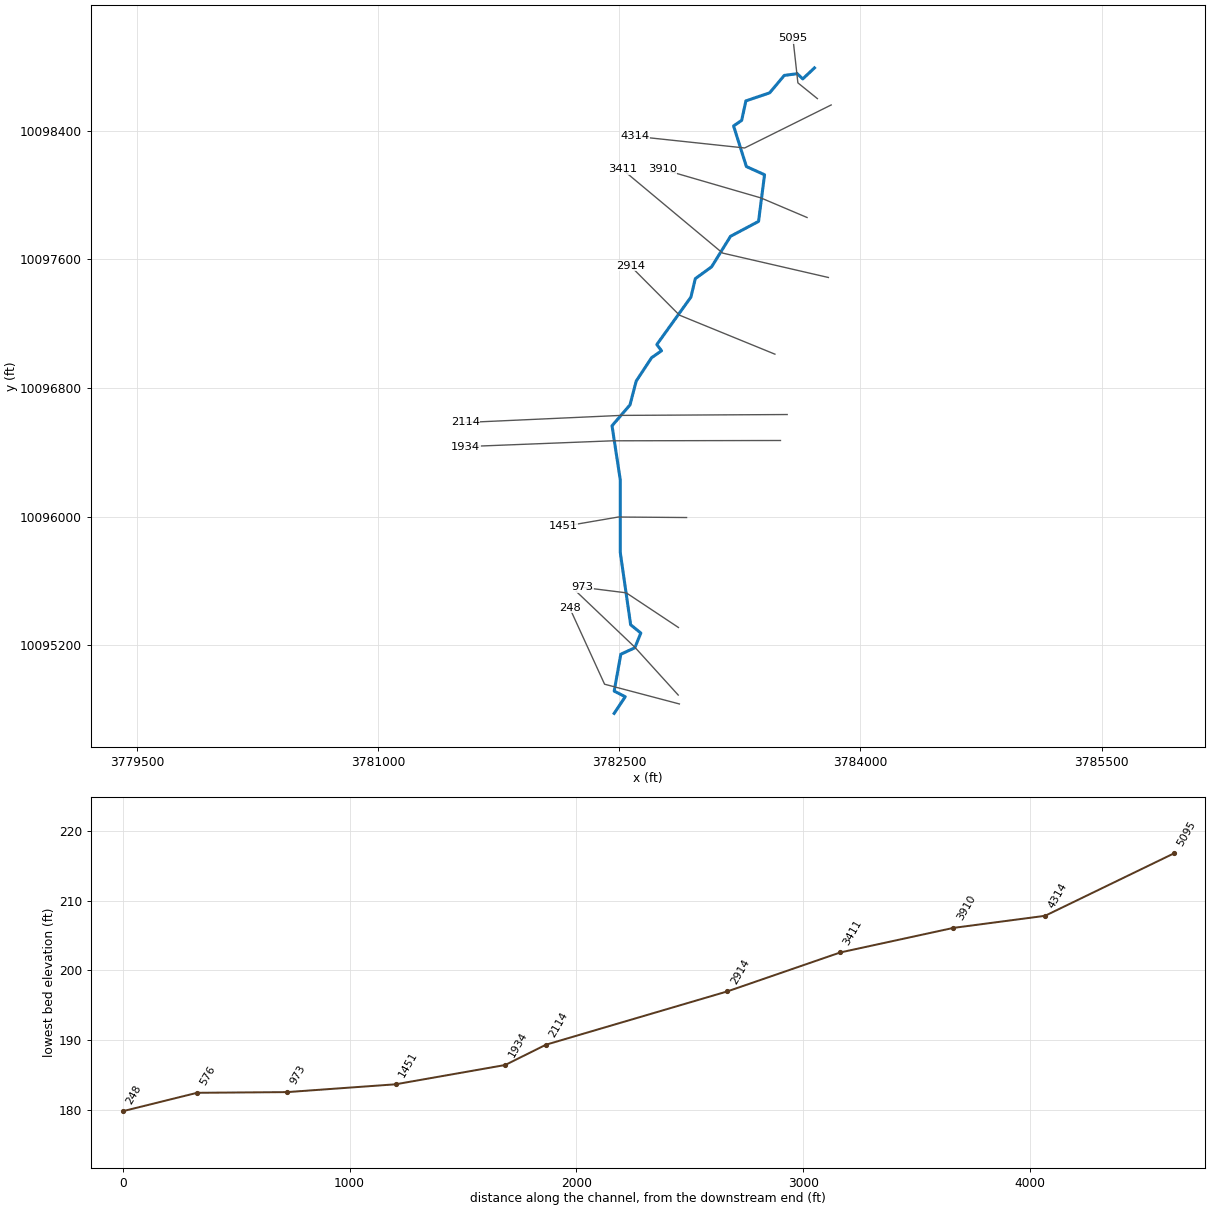
--- LAKE CREEK TRIBUTARY NO 10 1.prj (project) ---

Proj Title=LAKE CREEK TRIBUTARY NO 10 1 Base Level Engineering
Current Plan=p01
Default Exp/Contr=0.3,0.1
English Units
Geom File=g01
Flow File=f01
Flow File=f02
Plan File=p01
Y Axis Title=Elevation
X Axis Title(PF)=Main Channel Distance
X Axis Title(XS)=Station
BEGIN DESCRIPTION:
LAKE CREEK TRIBUTARY NO 10 1
END DESCRIPTION:
DSS Export Rating Curves= 0
DSS Export Rating Curve Sorted= 0
DSS Export Volume Flow Curves= 0
DXF OffsetX= 0
DXF OffsetY= 0
DXF ScaleX= 1
DXF ScaleY= 10

--- LAKE CREEK TRIBUTARY NO 10 1.p01 (plan) ---

Plan Title=Multiple Run
Short Identifier=Multiple
Geom File=g01
Flow File=f01
Subcritical Flow
K Sum by GR= 0
Std Step Tol= 0.01
Critical Tol= 0.01
Num of Std Step Trials= 20
Max Error Tol= 0.3
Flow Tol Ratio= 0.001
Split Flow NTrial= 30
Split Flow Tol= 0.02
Split Flow Ratio= 0.02
Log Output Level= 0
Friction Slope Method= 1
Unsteady Friction Slope Method= 2
Unsteady Bridges Friction Slope Method= 1
Parabolic Critical Depth
Global Vel Dist=  1 , 1 , 1
Global Log Level= 0
CheckData=True
Encroach Param= -1, 0, 0, 0
BEGIN DESCRIPTION:
Multiple Run
END DESCRIPTION:

--- LAKE CREEK TRIBUTARY NO 10 1.f01 (steady flow) ---

Flow Title=Multiple
Program Version=4.10
Number of Profiles= 7
Profile Names=10-year,25-year,50-year,1pct_min,100-year,1pct_plu,500-year
River Rch & RM=LAKE CREEK TRIBU,Reach-1         ,5095
     465     621     833     369    1113    3361    2052
River Rch & RM=LAKE CREEK TRIBU,Reach-1         ,3910
     644     878    1194     534    1613    4871    3044
Boundary for River Rch & Prof#=LAKE CREEK TRIBU,Reach-1         , 1
Up Type= 0
Dn Type= 3
Dn Slope=0.005
Boundary for River Rch & Prof#=LAKE CREEK TRIBU,Reach-1         , 2
Up Type= 0
Dn Type= 3
Dn Slope=0.005
Boundary for River Rch & Prof#=LAKE CREEK TRIBU,Reach-1         , 3
Up Type= 0
Dn Type= 3
Dn Slope=0.005
Boundary for River Rch & Prof#=LAKE CREEK TRIBU,Reach-1         , 4
Up Type= 0
Dn Type= 3
Dn Slope=0.005
Boundary for River Rch & Prof#=LAKE CREEK TRIBU,Reach-1         , 5
Up Type= 0
Dn Type= 3
Dn Slope=0.005
Boundary for River Rch & Prof#=LAKE CREEK TRIBU,Reach-1         , 6
Up Type= 0
Dn Type= 3
Dn Slope=0.005
Boundary for River Rch & Prof#=LAKE CREEK TRIBU,Reach-1         , 7
Up Type= 0
Dn Type= 3
Dn Slope=0.005
DSS Import GetInterval= 0
DSS Import GetPeak= 0
DSS Import FillOption= 0

--- LAKE CREEK TRIBUTARY NO 10 1.f02 (steady flow) ---

Flow Title=Orig_BLE_Flows
Program Version=4.10
Number of Profiles= 7
Profile Names=10-year,25-year,50-year,1pct_min,100-year,1pct_plu,500-year
River Rch & RM=LAKE CREEK TRIBU,Reach-1         ,5095
     465     609     724     284     856    2586    1193
River Rch & RM=LAKE CREEK TRIBU,Reach-1         ,3910
     644     861    1038     411    1241    3747    1770
Boundary for River Rch & Prof#=LAKE CREEK TRIBU,Reach-1         , 1
Up Type= 0
Dn Type= 3
Dn Slope=0.005
Boundary for River Rch & Prof#=LAKE CREEK TRIBU,Reach-1         , 2
Up Type= 0
Dn Type= 3
Dn Slope=0.005
Boundary for River Rch & Prof#=LAKE CREEK TRIBU,Reach-1         , 3
Up Type= 0
Dn Type= 3
Dn Slope=0.005
Boundary for River Rch & Prof#=LAKE CREEK TRIBU,Reach-1         , 4
Up Type= 0
Dn Type= 3
Dn Slope=0.005
Boundary for River Rch & Prof#=LAKE CREEK TRIBU,Reach-1         , 5
Up Type= 0
Dn Type= 3
Dn Slope=0.005
Boundary for River Rch & Prof#=LAKE CREEK TRIBU,Reach-1         , 6
Up Type= 0
Dn Type= 3
Dn Slope=0.005
Boundary for River Rch & Prof#=LAKE CREEK TRIBU,Reach-1         , 7
Up Type= 0
Dn Type= 3
Dn Slope=0.005
DSS Import GetInterval= 0
DSS Import GetPeak= 0
DSS Import FillOption= 0

--- LAKE CREEK TRIBUTARY NO 10 1.g01 (geometry) ---

Geom Title=Existing Conditions
Program Version=4.10

River Reach=LAKE CREEK TRIBU,Reach-1
Reach XY= 30
      3783713.86     10098791.44      3783641.16     10098723.08
      3783606.43     10098755.63      3783526.14     10098744.78
      3783434.99     10098636.28      3783287.42     10098586.36
      3783261.17     10098465.27      3783210.82     10098430.55
      3783290.53     10098178.03      3783403.42      10098126.9
      3783366.16     10097836.85      3783191.82     10097744.08
      3783074.01      10097554.1      3782972.79     10097480.75
      3782945.58     10097366.06      3782733.32      10097070.7
      3782762.71     10097032.25      3782701.02     10096989.11
      3782605.17     10096843.78      3782566.52     10096695.36
      3782454.79      10096565.6      3782506.23     10096228.46
      3782506.23     10095777.02      3782570.52     10095328.06
      3782633.91     10095276.38      3782596.51     10095184.81
      3782509.49     10095144.64      3782468.23     10094915.35
      3782536.93     10094880.35      3782468.23     10094776.84

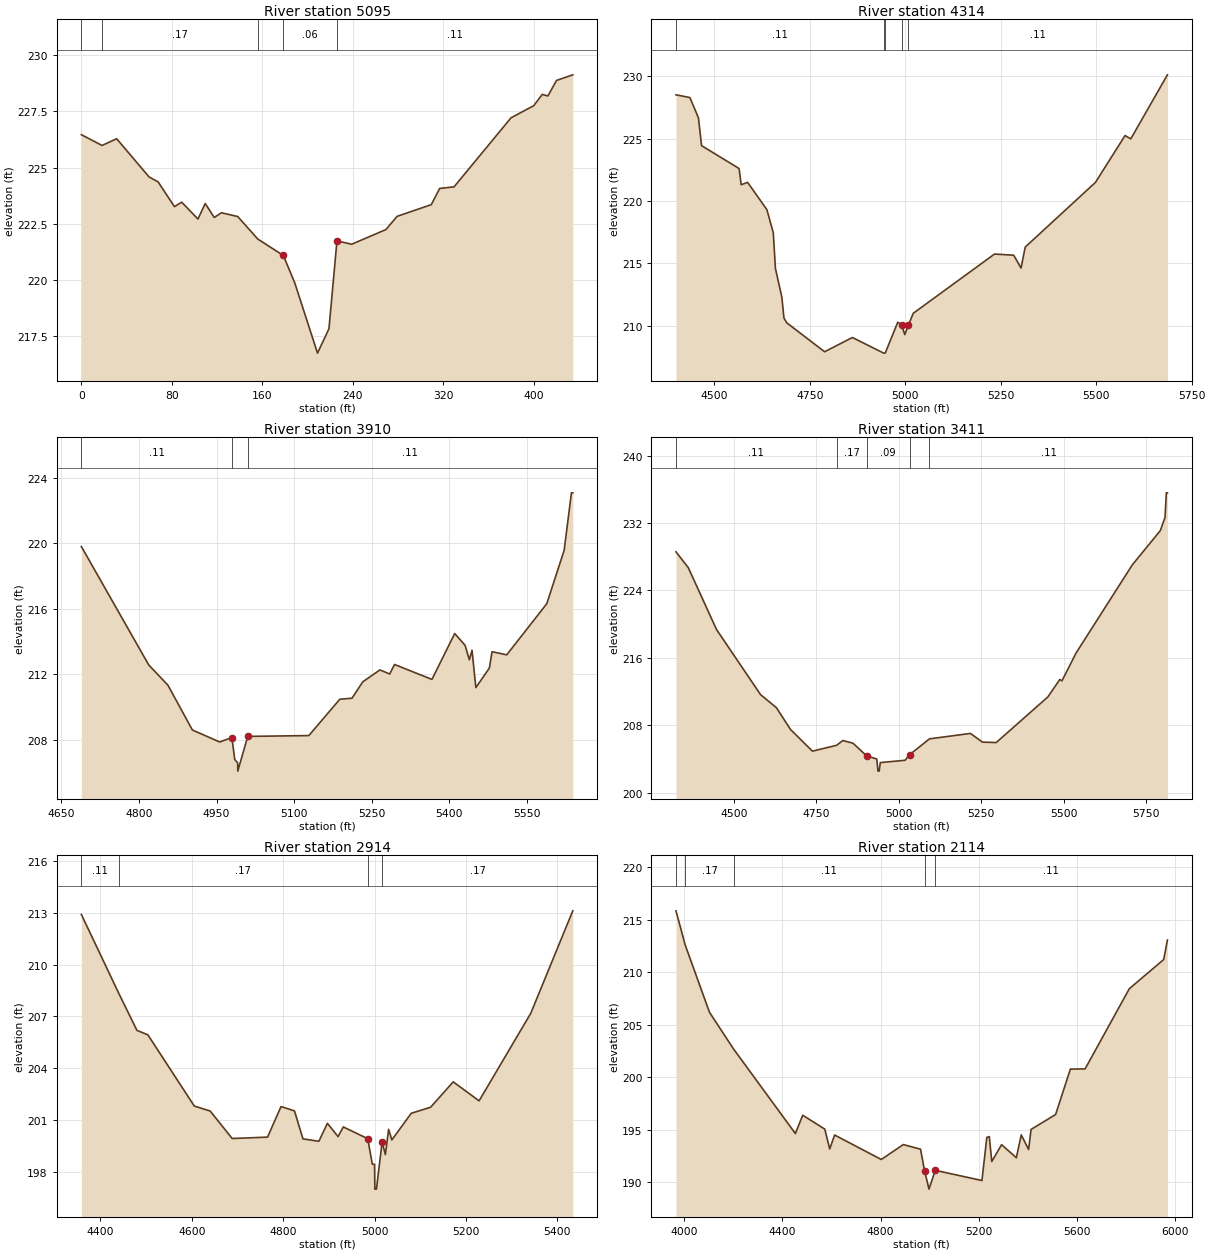
Type RM Length L Ch R = 1 ,5095    ,568,568,568
BEGIN DESCRIPTION:
LAKE CREEK TRIBUTARY NO. 10. 1 10.0
END DESCRIPTION:
XS GIS Cut Line= 3
      3783732.08     10098600.51      3783610.79     10098698.53
      3783580.15     10098975.44
#Sta/Elev= 30
       0  226.47    18.3  225.99    31.2  226.29    59.9  224.59    67.9  224.37
    82.3  223.27    88.7  223.47   103.1  222.72   109.5  223.41   117.5  222.79
   123.9     223   138.3  222.83     156  221.83   178.6   221.1   188.7  219.88
   208.8  216.76   218.9  217.84     226  221.75     239   221.6   269.2  222.25
   279.2  222.84   309.4  223.36   316.8  224.08   329.5  224.15   379.9  227.22
     400  227.76   407.5  228.26   412.5  228.19   420.1  228.88   434.5  229.13
#Mann= 5 ,-1 , 0
       0     .11       0    18.3     .17       0     156     .11       0
   178.6     .06       0     226     .11       0
Bank Sta=178.6,226
XS Rating Curve= 0 ,0
Exp/Cntr=0.3,0.1

Type RM Length L Ch R = 1 ,4314    ,404,404,404
BEGIN DESCRIPTION:
LAKE CREEK TRIBUTARY NO. 10. 1 9.0
END DESCRIPTION:
XS GIS Cut Line= 3
      3783817.85     10098561.07      3783279.67     10098293.55
      3782597.54     10098366.26
#Sta/Elev= 30
  4399.5   228.5  4435.9  228.28  4458.3  226.66  4466.5  224.43  4564.7   222.6
  4570.3   221.3  4587.1  221.49  4637.5  219.31  4654.3  217.46  4659.9   214.6
  4676.7  212.31  4682.3  210.62  4689.9  210.24  4788.7  207.93  4861.5  209.07
  4943.5  207.82  4947.5  207.82  4980.2  210.29  4990.3   210.1  4998.7   209.3
 5008.31  210.07  5020.9  211.01  5233.6  215.75  5283.9  215.66  5303.2  214.63
  5314.1  216.31  5498.1  221.49  5575.6  225.24  5590.5  224.97  5686.5   230.1
#Mann= 5 ,-1 , 0
  4399.5     .11       0  4943.5     .11       0  4947.5     .11       0
  4990.3     .07       0 5008.31     .11       0
#XS Ineff= 2 , 0
         4980.26  210.24
Permanent Ineff=
       F       F
Bank Sta=4990.3,5008.31
XS Rating Curve= 0 ,0
Exp/Cntr=0.3,0.1

Type RM Length L Ch R = 1 ,3910    ,499,499,499
BEGIN DESCRIPTION:
LAKE CREEK TRIBUTARY NO. 10. 1 8.0
END DESCRIPTION:
XS GIS Cut Line= 3
      3783667.83     10097861.08      3783381.19     10097982.76
      3782767.88     10098161.06
#Sta/Elev= 30
  4688.6   219.8  4818.9  212.57  4855.9  211.34  4903.3   208.6    4956  207.87
  4979.7  208.14  4985.1   206.8  4990.8  206.59    4991  206.09  5010.3  208.21
  5128.4  208.26  5188.3  210.48  5211.8  210.54  5232.6  211.54  5265.8  212.27
  5284.7  212.02  5294.1   212.6  5366.4  211.69  5410.4  214.49  5430.5  213.77
  5438.7  212.89  5443.9  213.47  5451.3  211.19  5477.4  212.38  5482.6  213.38
    5511  213.19  5588.4  216.31    5622  219.57  5636.1  223.08  5638.7  223.08
#Mann= 3 , 0 , 0
  4688.6     .11       0  4979.7     .06       0  5010.3     .11       0
Bank Sta=4979.7,5010.3
XS Rating Curve= 0 ,0
Exp/Cntr=0.3,0.1

Type RM Length L Ch R = 1 ,3411    ,497,497,497
BEGIN DESCRIPTION:
LAKE CREEK TRIBUTARY NO. 10. 1 7.0
END DESCRIPTION:
XS GIS Cut Line= 3
      3783800.54     10097487.99      3783142.61     10097639.75
      3782517.85     10098161.07
#Sta/Elev= 30
  4324.8  228.58  4362.1   226.7  4447.7  219.36  4581.1  211.64    4629   210.1
  4671.8  207.51  4738.1  204.94  4811.3  205.63  4830.4   206.2  4861.2  205.88
  4902.3  204.38    4933  204.01  4936.9  202.57  4940.4  202.57  4943.8  203.58
  5019.1  203.86  5032.3  204.51  5092.8   206.4  5216.9  207.04  5253.4  206.01
    5295  205.96  5451.2  211.36  5487.7  213.44  5494.2  213.28  5537.1  216.59
  5707.6  227.05  5792.2   231.1  5806.5  232.67  5810.4  235.58  5813.7  235.58
#Mann= 5 ,-1 , 0
  4324.8     .11       0  4811.3     .17       0  4902.3     .09       0
  5032.3     .17       0  5092.8     .11       0
Bank Sta=4902.3,5032.3
XS Rating Curve= 0 ,0
Exp/Cntr=0.3,0.1

Type RM Length L Ch R = 1 ,2914    ,800,800,800
BEGIN DESCRIPTION:
LAKE CREEK TRIBUTARY NO. 10. 1 6.0
END DESCRIPTION:
XS GIS Cut Line= 3
      3783467.86     10097011.07      3782874.02     10097253.72
      3782567.87     10097561.05
#Sta/Elev= 30
  4358.5   212.9  4439.9  208.36  4480.1  206.19  4504.1  205.93  4605.6  201.81
  4640.4  201.52  4688.5  199.93  4765.9  200.01  4795.4  201.78  4824.8  201.53
  4843.4  199.91  4878.2  199.77  4896.9  200.81  4920.2  200.04  4931.7   200.6
  4985.1  199.92  4995.2  198.44    5000  198.44  5000.7     197  5004.2     197
  5016.6  199.73  5023.7     199  5030.8  200.46  5037.9  199.85  5080.3  201.39
  5122.7  201.74  5172.2  203.21  5228.8  202.11  5341.9  207.18  5433.8  213.11
#Mann= 4 ,-1 , 0
  4358.5     .11       0  4439.9     .17       0  4985.1     .09       0
  5016.6     .17       0
Bank Sta=4985.1,5016.6
XS Rating Curve= 0 ,0
Exp/Cntr=0.3,0.1

Type RM Length L Ch R = 1 ,2114    ,180,180,180
BEGIN DESCRIPTION:
LAKE CREEK TRIBUTARY NO. 10. 1 5.0
END DESCRIPTION:
XS GIS Cut Line= 3
      3783544.23     10096635.56      3782510.34     10096630.19
      3781542.85     10096586.07
#Sta/Elev= 30
  3966.1  215.84  4003.5   212.6  4102.5  206.19  4200.8  202.69  4452.5  194.65
  4482.5  196.39  4572.5  195.07  4592.5  193.18  4612.5  194.51  4802.5  192.18
  4892.5   193.6  4962.5  193.16 4978.89191.1167    4997  189.36  5022.5  191.15
  5212.7  190.18  5232.7  194.28  5242.7  194.36  5252.8  191.99  5292.8  193.59
  5352.9  192.35  5372.9  194.52  5402.9  193.13  5412.9  195.04    5513  196.46
  5573.1  200.78  5633.1   200.8  5813.3  208.43  5953.5  211.21  5968.5  213.06
#Mann= 5 ,-1 , 0
  3966.1     .11       0  4003.5     .17       0  4200.8     .11       0
 4978.89     .07       0  5022.5     .11       0
Bank Sta=4978.89,5022.5
XS Rating Curve= 0 ,0
Exp/Cntr=0.3,0.1

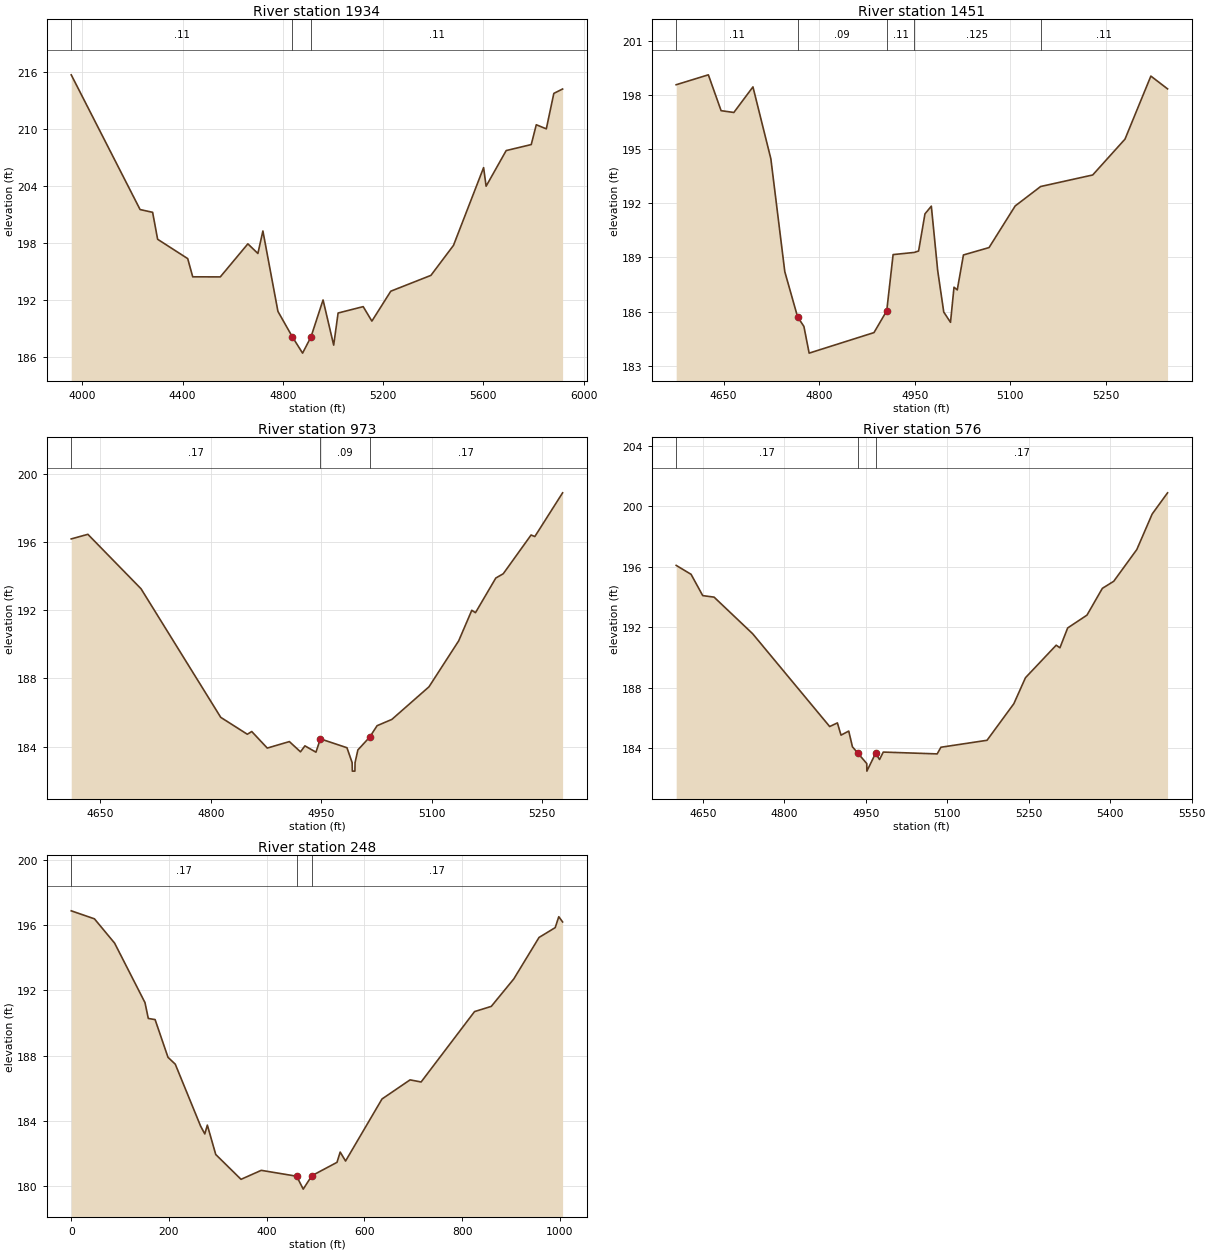
Type RM Length L Ch R = 1 ,1934    ,483,483,483
BEGIN DESCRIPTION:
LAKE CREEK TRIBUTARY NO. 10. 1 4.0
END DESCRIPTION:
XS GIS Cut Line= 3
      3783502.58     10096474.11      3782458.08     10096472.16
      3781542.89     10096436.07
#Sta/Elev= 30
  3955.5  215.66  4230.2  201.52  4280.2  201.23  4300.2   198.4  4420.2  196.37
  4440.2  194.46  4550.2  194.45  4660.2  197.92  4700.2  196.91  4720.2  199.27
  4780.2  190.83 4837.74188.1573  4878.5  186.45 4912.02188.1521  4960.2  192.03
  5002.6  187.29  5020.2  190.66  5120.3  191.33    5155  189.81  5230.4  192.95
  5390.5  194.61  5480.6  197.76  5600.7  205.92  5610.7  203.97  5690.8  207.71
  5790.8  208.34  5810.9  210.42  5850.9  209.99  5880.9  213.71  5915.9  214.17
#Mann= 3 ,-1 , 0
  3955.5     .11       0 4837.74     .07       0 4912.02     .11       0
Bank Sta=4837.74,4912.02
XS Rating Curve= 0 ,0
Exp/Cntr=0.3,0.1

Type RM Length L Ch R = 1 ,1451    ,478,478,478
BEGIN DESCRIPTION:
LAKE CREEK TRIBUTARY NO. 10. 1 3.0
END DESCRIPTION:
XS GIS Cut Line= 3
      3782918.35     10095994.94      3782493.86      10095998.1
      3782152.04     10095939.53
#Sta/Elev= 30
  4575.5  198.59    4626  199.14    4646  197.15    4666  197.05    4696  198.47
  4724.1  194.48    4746  188.21    4766  185.71    4776  185.17  4784.2  183.69
    4886  184.83    4906  186.04    4916  189.16  4949.1  189.28    4956  189.36
    4966  191.42    4976  191.85    4986  188.27  4995.5  185.97  5006.1   185.4
  5011.6  187.35  5016.7   187.2  5026.4  189.14  5066.6  189.55  5107.6  191.86
  5147.6  192.94  5229.3  193.58    5280  195.57  5320.6  199.07  5346.8  198.36
#Mann= 5 ,-1 , 0
  4575.5     .11       0    4766     .09       0    4906     .11       0
  4949.1    .125       0  5147.6     .11       0
Bank Sta=4766,4906
XS Rating Curve= 0 ,0
Exp/Cntr=0.3,0.1

Type RM Length L Ch R = 1 ,973     ,397,397,397
BEGIN DESCRIPTION:
LAKE CREEK TRIBUTARY NO. 10. 1 2.0
END DESCRIPTION:
XS GIS Cut Line= 3
      3782867.89     10095311.05      3782543.33     10095526.57
      3782267.88     10095561.07
#Sta/Elev= 30
  4610.4  196.17    4633  196.44  4705.2  193.25  4813.4  185.72  4849.5  184.73
  4855.5  184.89  4876.6  183.92  4906.6   184.3  4921.7   183.7  4927.7  184.05
  4942.7  183.68  4948.7  184.46  4984.8  183.94  4991.8  183.07  4992.1  182.57
  4995.6  182.57  4995.8  183.07  4999.6  183.81  5015.6  184.56  5025.7  185.23
  5045.8   185.6  5096.2  187.51  5136.5   190.2  5154.3  191.99  5159.3  191.85
  5186.9  193.88    5197  194.13  5234.8   196.4  5239.9  196.31  5277.6  198.87
#Mann= 3 , 0 , 0
  4610.4     .17       0  4948.7     .09       0  5015.6     .17       0
Bank Sta=4948.7,5015.6
XS Rating Curve= 0 ,0
Exp/Cntr=0.3,0.1

Type RM Length L Ch R = 1 ,576     ,328,328,328
BEGIN DESCRIPTION:
LAKE CREEK TRIBUTARY NO. 10. 1 1.0
END DESCRIPTION:
XS GIS Cut Line= 3
      3782866.49     10094890.76      3782595.65     10095189.38
      3782232.24     10095535.48
#Sta/Elev= 30
  4600.6  196.08    4628  195.49  4649.5  194.08  4670.4  193.98  4741.4  191.56
  4883.3  185.42  4897.5  185.66  4904.2  184.85  4918.4  185.12  4925.2  184.08
 4935.35183.6524  4951.6  182.97  4951.8  182.47  4967.8  183.64  4975.2  183.24
    4982  183.73  5081.3  183.61  5088.2  184.05  5173.1  184.51  5222.5  186.93
  5243.9  188.65  5300.5   190.8  5307.4  190.63  5321.6  191.94  5357.2  192.79
  5385.5  194.56  5406.5  195.03    5449  197.13  5477.3  199.48  5505.6  200.88
#Mann= 3 , 0 , 0
  4600.6     .17       0 4935.35     .09       0  4967.8     .17       0
Bank Sta=4935.35,4967.8
XS Rating Curve= 0 ,0
Exp/Cntr=0.3,0.1

Type RM Length L Ch R = 1 ,248     ,0,0,0
BEGIN DESCRIPTION:
LAKE CREEK TRIBUTARY NO. 10. 1 1.0
END DESCRIPTION:
XS GIS Cut Line= 3
      3782873.74     10094835.41      3782408.46     10094958.24
      3782190.38     10095434.93
#Sta/Elev= 30
       0  196.87    47.5  196.38    88.8  194.89   150.9  191.25   157.7  190.28
   171.6  190.21     198   187.9   212.9  187.48   264.7  183.69   273.3  183.21
   278.5  183.75   295.7  181.95   347.4  180.43   388.8  180.98   461.2  180.62
   474.7  179.83   492.3  180.65   543.8  181.47   550.3   182.1   561.3  181.55
   635.9  185.35   693.3  186.52   715.9  186.39   825.2   190.7   859.5  191.02
   905.5   192.7   957.2  195.24   990.2  195.84   997.6  196.51  1005.4  196.19
#Mann= 3 , 0 , 0
       0     .17       0   461.2     .09       0   492.3     .17       0
Bank Sta=461.2,492.3
XS Rating Curve= 0 ,0
Exp/Cntr=0.3,0.1

Chan Stop Cuts=-1
Use User Specified Reach Order=0
Composite Channel Slope=5