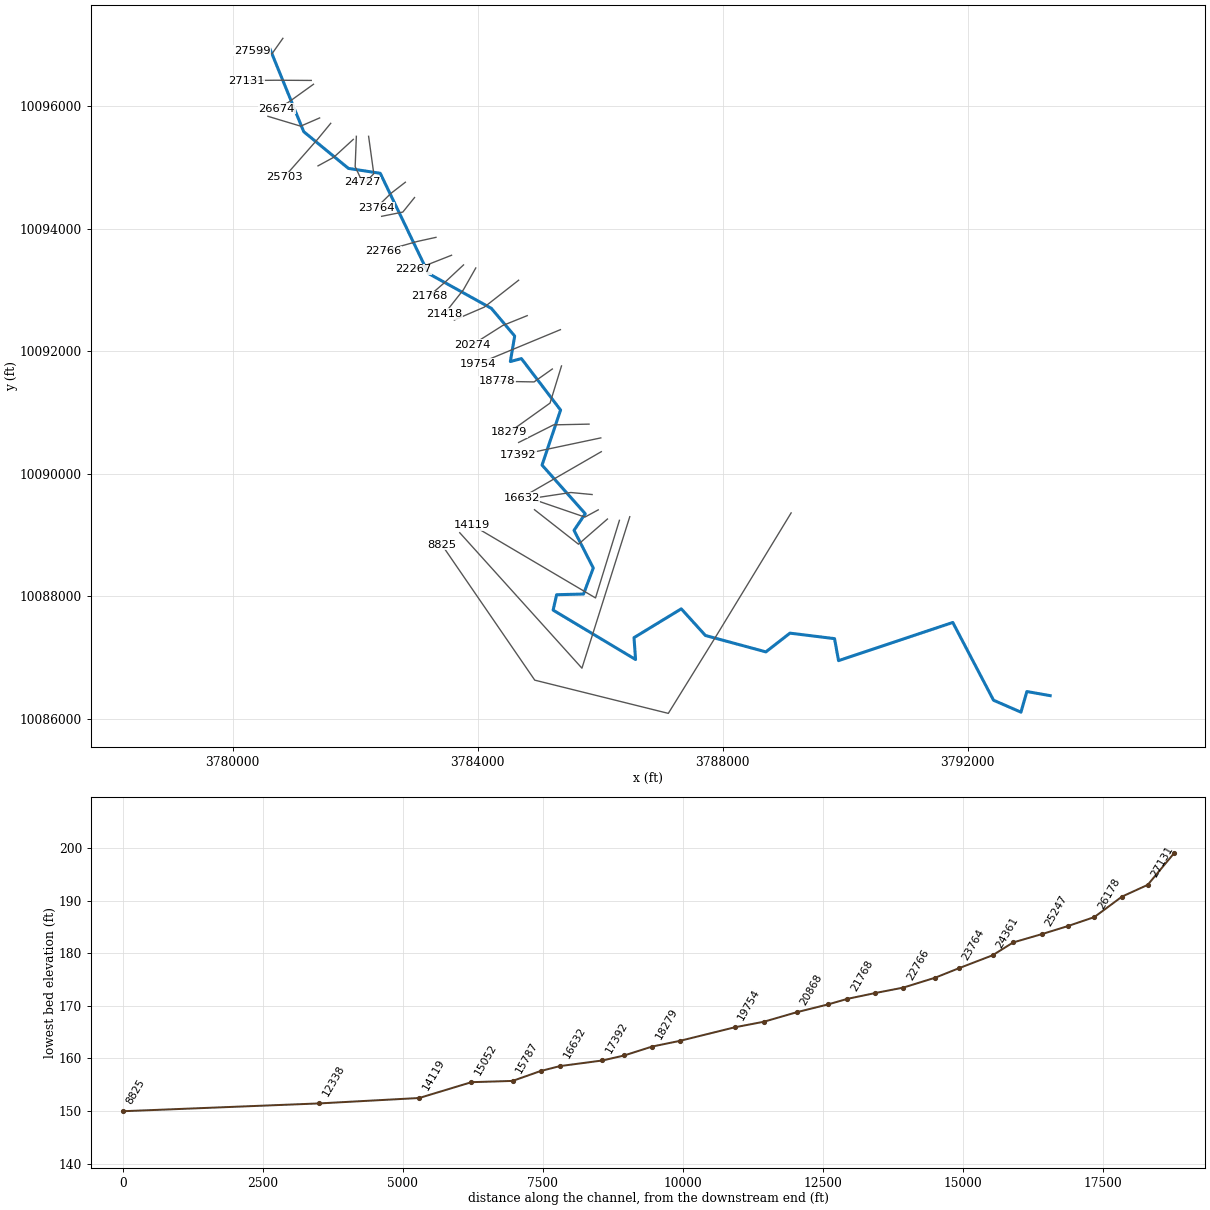
--- LAKE CREEK TRIBUTARY NO 10.prj (project) ---

Proj Title=LAKE CREEK TRIBUTARY NO 10 Base Level Engineering
Current Plan=p01
Default Exp/Contr=0.3,0.1
English Units
Geom File=g01
Flow File=f01
Flow File=f02
Plan File=p01
Y Axis Title=Elevation
X Axis Title(PF)=Main Channel Distance
X Axis Title(XS)=Station
BEGIN DESCRIPTION:
LAKE CREEK TRIBUTARY NO 10
END DESCRIPTION:
DSS Export Rating Curves= 0
DSS Export Rating Curve Sorted= 0
DSS Export Volume Flow Curves= 0
DXF OffsetX= 0
DXF OffsetY= 0
DXF ScaleX= 1
DXF ScaleY= 10

--- LAKE CREEK TRIBUTARY NO 10.p01 (plan) ---

Plan Title=Multiple Run
Short Identifier=Multiple
Geom File=g01
Flow File=f01
Subcritical Flow
K Sum by GR= 0
Std Step Tol= 0.01
Critical Tol= 0.01
Num of Std Step Trials= 20
Max Error Tol= 0.3
Flow Tol Ratio= 0.001
Split Flow NTrial= 30
Split Flow Tol= 0.02
Split Flow Ratio= 0.02
Log Output Level= 0
Friction Slope Method= 1
Unsteady Friction Slope Method= 2
Unsteady Bridges Friction Slope Method= 1
Parabolic Critical Depth
Global Vel Dist=  1 , 1 , 1
Global Log Level= 0
CheckData=True
Encroach Param= -1, 0, 0, 0
BEGIN DESCRIPTION:
Multiple Run
END DESCRIPTION:

--- LAKE CREEK TRIBUTARY NO 10.f01 (steady flow) ---

Flow Title=Multiple
Program Version=4.10
Number of Profiles= 7
Profile Names=10-year,25-year,50-year,1pct_min,100-year,1pct_plu,500-year
River Rch & RM=LAKE CREEK TRIBU,Reach-1         ,27599
     600     817    1109     496    1499    4527    2828
River Rch & RM=LAKE CREEK TRIBU,Reach-1         ,25703
     746    1029    1410     636    1920    5798    3684
River Rch & RM=LAKE CREEK TRIBU,Reach-1         ,24361
    1272    1779    2456    1113    3361   10150    6512
River Rch & RM=LAKE CREEK TRIBU,Reach-1         ,12338
    1833    2601    3626    1656    5001   15103    9849
River Rch & RM=LAKE CREEK TRIBU,Reach-1         ,8825
    1801    2522    3486    1577    4761   14378    9195
Boundary for River Rch & Prof#=LAKE CREEK TRIBU,Reach-1         , 1
Up Type= 0
Dn Type= 3
Dn Slope=0.005
Boundary for River Rch & Prof#=LAKE CREEK TRIBU,Reach-1         , 2
Up Type= 0
Dn Type= 3
Dn Slope=0.005
Boundary for River Rch & Prof#=LAKE CREEK TRIBU,Reach-1         , 3
Up Type= 0
Dn Type= 3
Dn Slope=0.005
Boundary for River Rch & Prof#=LAKE CREEK TRIBU,Reach-1         , 4
Up Type= 0
Dn Type= 3
Dn Slope=0.005
Boundary for River Rch & Prof#=LAKE CREEK TRIBU,Reach-1         , 5
Up Type= 0
Dn Type= 3
Dn Slope=0.005
Boundary for River Rch & Prof#=LAKE CREEK TRIBU,Reach-1         , 6
Up Type= 0
Dn Type= 3
Dn Slope=0.005
Boundary for River Rch & Prof#=LAKE CREEK TRIBU,Reach-1         , 7
Up Type= 0
Dn Type= 3
Dn Slope=0.005
DSS Import GetInterval= 0
DSS Import GetPeak= 0
DSS Import FillOption= 0

--- LAKE CREEK TRIBUTARY NO 10.f02 (steady flow) ---

Flow Title=Orig_BLE_Flows
Program Version=4.10
Number of Profiles= 7
Profile Names=10-year,25-year,50-year,1pct_min,100-year,1pct_plu,500-year
River Rch & RM=LAKE CREEK TRIBU,Reach-1         ,27599
     600     801     964     382    1153    3482    1644
River Rch & RM=LAKE CREEK TRIBU,Reach-1         ,25703
     746    1009    1226     489    1477    4462    2142
River Rch & RM=LAKE CREEK TRIBU,Reach-1         ,24361
    1272    1744    2136     856    2585    7808    3786
River Rch & RM=LAKE CREEK TRIBU,Reach-1         ,12338
    1833    2550    3153    1274    3847   11618    5726
River Rch & RM=LAKE CREEK TRIBU,Reach-1         ,8825
    1801    2473    3031    1213    3662   11060    5346
Boundary for River Rch & Prof#=LAKE CREEK TRIBU,Reach-1         , 1
Up Type= 0
Dn Type= 3
Dn Slope=0.005
Boundary for River Rch & Prof#=LAKE CREEK TRIBU,Reach-1         , 2
Up Type= 0
Dn Type= 3
Dn Slope=0.005
Boundary for River Rch & Prof#=LAKE CREEK TRIBU,Reach-1         , 3
Up Type= 0
Dn Type= 3
Dn Slope=0.005
Boundary for River Rch & Prof#=LAKE CREEK TRIBU,Reach-1         , 4
Up Type= 0
Dn Type= 3
Dn Slope=0.005
Boundary for River Rch & Prof#=LAKE CREEK TRIBU,Reach-1         , 5
Up Type= 0
Dn Type= 3
Dn Slope=0.005
Boundary for River Rch & Prof#=LAKE CREEK TRIBU,Reach-1         , 6
Up Type= 0
Dn Type= 3
Dn Slope=0.005
Boundary for River Rch & Prof#=LAKE CREEK TRIBU,Reach-1         , 7
Up Type= 0
Dn Type= 3
Dn Slope=0.005
DSS Import GetInterval= 0
DSS Import GetPeak= 0
DSS Import FillOption= 0

--- LAKE CREEK TRIBUTARY NO 10.g01 (geometry) ---

Geom Title=Existing Conditions
Program Version=4.10

River Reach=LAKE CREEK TRIBU,Reach-1
Reach XY= 30
      3780611.38     10096927.49      3781158.23     10095586.84
      3781888.23     10094986.84      3782408.23     10094906.84
      3783194.17     10093271.41      3784222.87     10092701.34
      3784603.24     10092249.33      3784532.86     10091832.95
      3784712.86     10091881.23      3785352.87     10091040.86
      3785050.15     10090142.45      3785755.58     10089347.62
      3785572.74     10089076.33      3785886.93     10088461.02
      3785727.87     10088036.17      3785288.26     10088025.08
      3785231.01     10087773.66      3786577.25     10086966.92
      3786551.89     10087324.13       3787323.9     10087794.59
      3787718.26     10087359.17      3788705.78     10087091.46
      3789098.47     10087397.57      3789826.65      10087307.9
      3789891.95     10086948.41      3791757.64     10087572.27
      3792422.76     10086302.32      3792870.74     10086106.93
      3792967.51      10086444.1      3793348.23     10086376.84

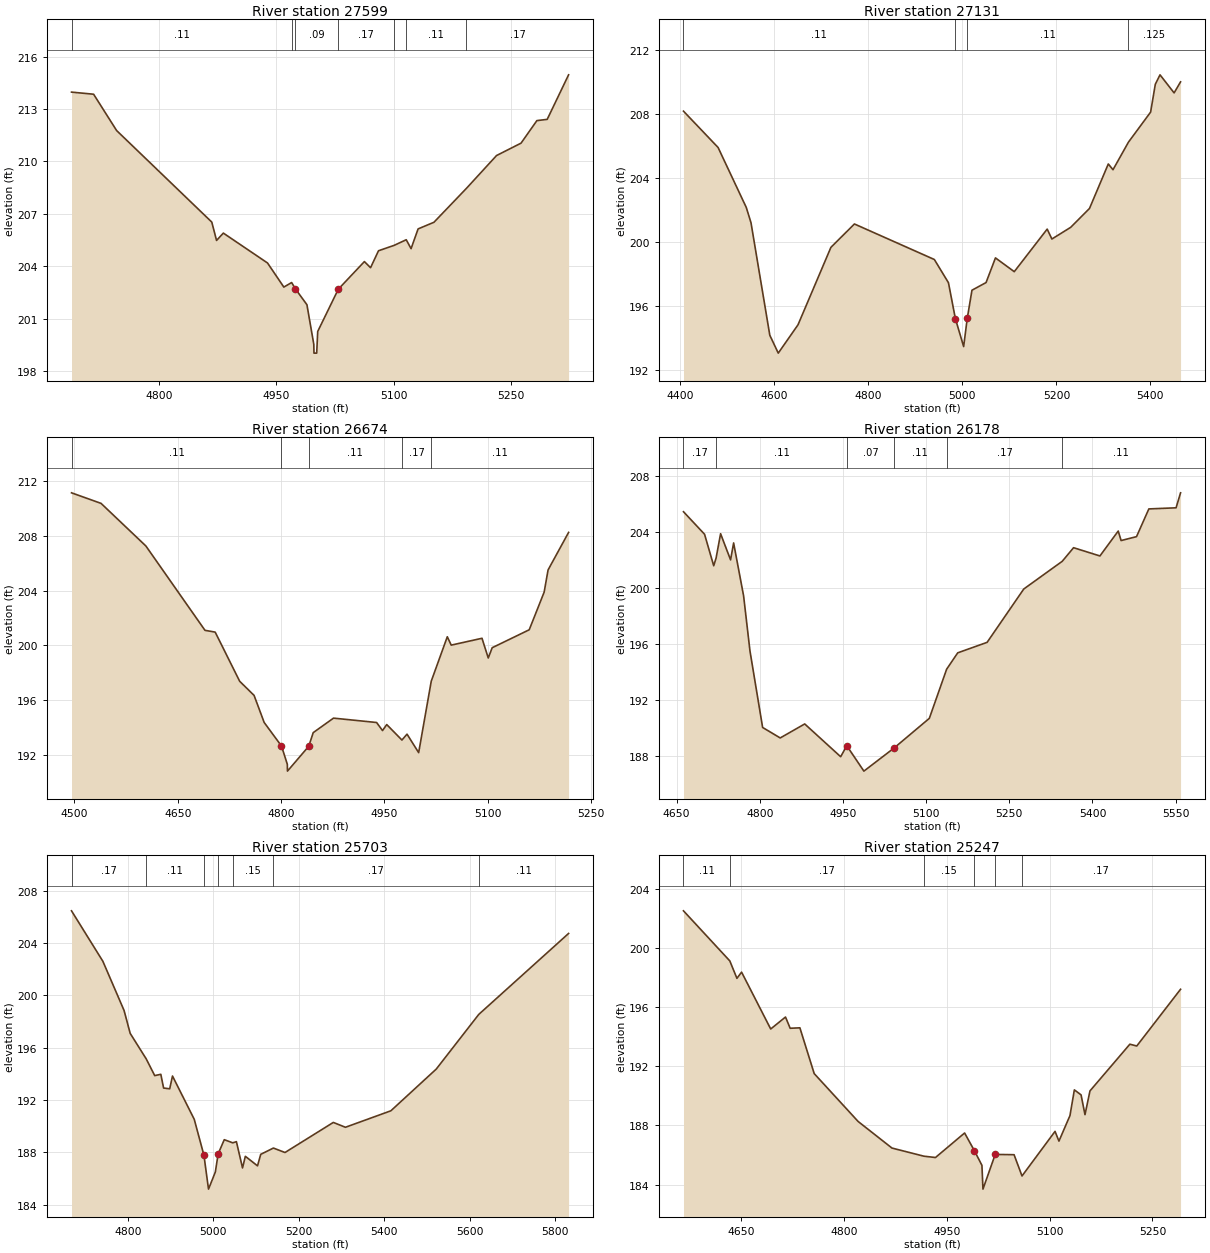
Type RM Length L Ch R = 1 ,27599   ,468,468,468
BEGIN DESCRIPTION:
LAKE CREEK TRIBUTARY NO. 10 38.0
END DESCRIPTION:
XS GIS Cut Line= 3
      3780817.83     10097111.04      3780637.42     10096855.88
      3780317.86     10096911.07
#Sta/Elev= 30
  4687.5  213.97  4715.8  213.85  4745.3  211.77  4867.2  206.53  4873.3  205.48
    4882   205.9  4938.6  204.19  4959.5  202.81  4969.5  203.07  4974.3  202.71
  4989.1   201.8  4997.9  199.53  4998.1  199.03  5001.6  199.03  5002.9  200.27
 5029.28202.6883  5062.7  204.27  5070.6  203.92  5080.8  204.89  5100.9   205.2
  5116.3  205.52  5122.5  205.01  5131.5  206.14  5151.8  206.52  5193.4  208.46
    5232  210.34  5263.4  211.05  5283.7  212.34  5296.9  212.41  5324.3  214.96
#Mann= 7 ,-1 , 0
  4687.5     .11       0  4969.5     .17       0  4974.3     .09       0
 5029.28     .17       0  5100.9     .17       0  5116.3     .11       0
  5193.4     .17       0
Bank Sta=4974.3,5029.28
XS Rating Curve= 0 ,0
Exp/Cntr=0.3,0.1

Type RM Length L Ch R = 1 ,27131   ,457,457,457
BEGIN DESCRIPTION:
LAKE CREEK TRIBUTARY NO. 10 37.0
END DESCRIPTION:
XS GIS Cut Line= 3
      3781281.42     10096423.76      3780688.23     10096426.84
      3780224.16     10096421.15
#Sta/Elev= 30
  4406.8  208.16  4480.4  205.89  4540.4  202.14  4550.4  201.19  4590.4  194.16
  4608.4  193.04  4650.4  194.81  4720.4  199.65  4770.4  201.11  4940.4  198.89
  4970.4  197.44  4985.1195.1993  5002.7  193.45  5010.4  195.21  5020.4  196.97
  5050.4  197.45  5070.4  198.99  5110.4  198.13  5180.4  200.79  5190.4  200.17
  5230.4   200.9  5270.4  202.08  5310.4  204.86  5320.4   204.5  5353.2  206.22
  5400.4   208.1  5410.4  209.84  5420.4  210.43  5450.4   209.3  5464.1  209.99
#Mann= 4 ,-1 , 0
  4406.8     .11       0  4985.1     .06       0  5010.4     .11       0
  5353.2    .125       0
Bank Sta=4985.1,5010.4
XS Rating Curve= 0 ,0
Exp/Cntr=0.3,0.1

Type RM Length L Ch R = 1 ,26674   ,496,496,496
BEGIN DESCRIPTION:
LAKE CREEK TRIBUTARY NO. 10 36.0
END DESCRIPTION:
XS GIS Cut Line= 3
      3781317.82     10096361.05      3780908.23     10096066.84
      3780717.84     10095961.07
#Sta/Elev= 30
  4495.7  211.14  4538.6  210.37  4603.7  207.26  4689.6   201.1  4704.4  200.97
    4740  197.38  4760.9  196.35  4775.6  194.37 4800.73192.6539  4809.2  191.32
  4809.4  190.82  4840.4  192.64  4846.8  193.63  4876.3  194.69  4938.9  194.37
  4947.5  193.78  4953.6  194.22  4975.7  193.09  4983.1  193.52    5000  192.17
  5018.3  197.39  5041.6  200.63  5047.3  200.02    5092  200.52  5101.1  199.08
  5106.8  199.83  5160.6  201.14  5182.3  203.89    5188  205.51  5217.8  208.25
#Mann= 5 ,-1 , 0
  4495.7     .11       0 4800.73     .09       0  4840.4     .11       0
  4975.7     .17       0  5018.3     .11       0
Bank Sta=4800.73,4840.4
XS Rating Curve= 0 ,0
Exp/Cntr=0.3,0.1

Type RM Length L Ch R = 1 ,26178   ,475,475,475
BEGIN DESCRIPTION:
LAKE CREEK TRIBUTARY NO. 10 35.0
END DESCRIPTION:
XS GIS Cut Line= 3
      3781417.88     10095811.09      3781108.23     10095676.84
      3780573.11     10095837.81
#Sta/Elev= 30
  4662.5  205.44  4700.5  203.83    4717  201.58  4721.3  202.13  4729.4  203.87
  4747.4     202  4752.9  203.21  4770.9  199.43  4782.4  195.49  4805.2  190.03
  4836.9  189.28  4881.1  190.28  4945.9  187.94    4957  188.72  4987.8  186.91
  5042.2  188.56  5105.8  190.68    5137  194.19    5157  195.36    5210  196.11
  5276.1  199.92  5345.5   201.9  5365.9  202.87  5413.4  202.28  5446.4  204.06
  5451.6  203.38  5479.4  203.66  5501.6  205.64  5550.7  205.72  5558.8  206.79
#Mann= 6 ,-1 , 0
  4662.5     .17       0  4721.3     .11       0    4957     .07       0
  5042.2     .11       0    5137     .17       0  5345.5     .11       0
Bank Sta=4957,5042.2
XS Rating Curve= 0 ,0
Exp/Cntr=0.3,0.1

Type RM Length L Ch R = 1 ,25703   ,456,456,456
BEGIN DESCRIPTION:
LAKE CREEK TRIBUTARY NO. 10 34.0
END DESCRIPTION:
XS GIS Cut Line= 3
      3781599.13     10095723.25      3781388.23     10095466.84
      3780838.73     10094843.06
#Sta/Elev= 30
    4668  206.47  4741.4  202.61    4791  198.85  4805.3   197.1  4842.8  195.15
  4862.7  193.87    4877  193.97  4883.5  192.92  4897.8  192.86  4904.3  193.84
  4955.2  190.53 4977.93187.7746  4988.6  185.19  5004.6   186.5  5011.2  187.89
  5025.5  188.97  5045.4  188.73  5053.9  188.82  5068.2  186.81  5074.8   187.7
  5103.3  186.97  5110.8  187.85  5140.5  188.33  5167.6  187.99  5280.7  190.29
  5309.1  189.92  5415.4  191.18  5521.6  194.37  5621.1  198.55  5831.3  204.74
#Mann= 7 ,-1 , 0
    4668     .17       0  4842.8     .11       0 4977.93     .06       0
  5011.2     .11       0  5045.4     .15       0  5140.5     .17       0
  5621.1     .11       0
Bank Sta=4977.93,5011.2
XS Rating Curve= 0 ,0
Exp/Cntr=0.3,0.1

Type RM Length L Ch R = 1 ,25247   ,520,520,520
BEGIN DESCRIPTION:
LAKE CREEK TRIBUTARY NO. 10 33.0
END DESCRIPTION:
XS GIS Cut Line= 3
      3781967.83     10095461.05       3781648.6     10095168.55
      3781391.79     10095028.47
#Sta/Elev= 30
  4565.5  202.53  4633.1  199.14  4643.5  197.96  4650.3  198.38  4692.8  194.53
  4714.4  195.34  4721.2  194.58  4735.4  194.61  4756.3  191.51  4820.4  188.27
  4869.8  186.47  4916.4  185.92  4933.3  185.83  4975.8  187.49    4990   186.3
  5001.1   185.3  5002.6  183.69  5020.5  186.04    5048  186.02  5059.6  184.58
  5107.8   187.6  5113.5  186.94  5129.6  188.67    5136  190.41  5145.8  190.07
  5151.5  188.73  5158.8  190.34    5217   193.5  5227.1  193.38    5291  197.22
#Mann= 6 ,-1 , 0
  4565.5     .11       0  4633.1     .17       0  4916.4     .15       0
    4990     .09       0  5020.5     .15       0  5059.6     .17       0
Bank Sta=4990,5020.5
XS Rating Curve= 0 ,0
Exp/Cntr=0.3,0.1

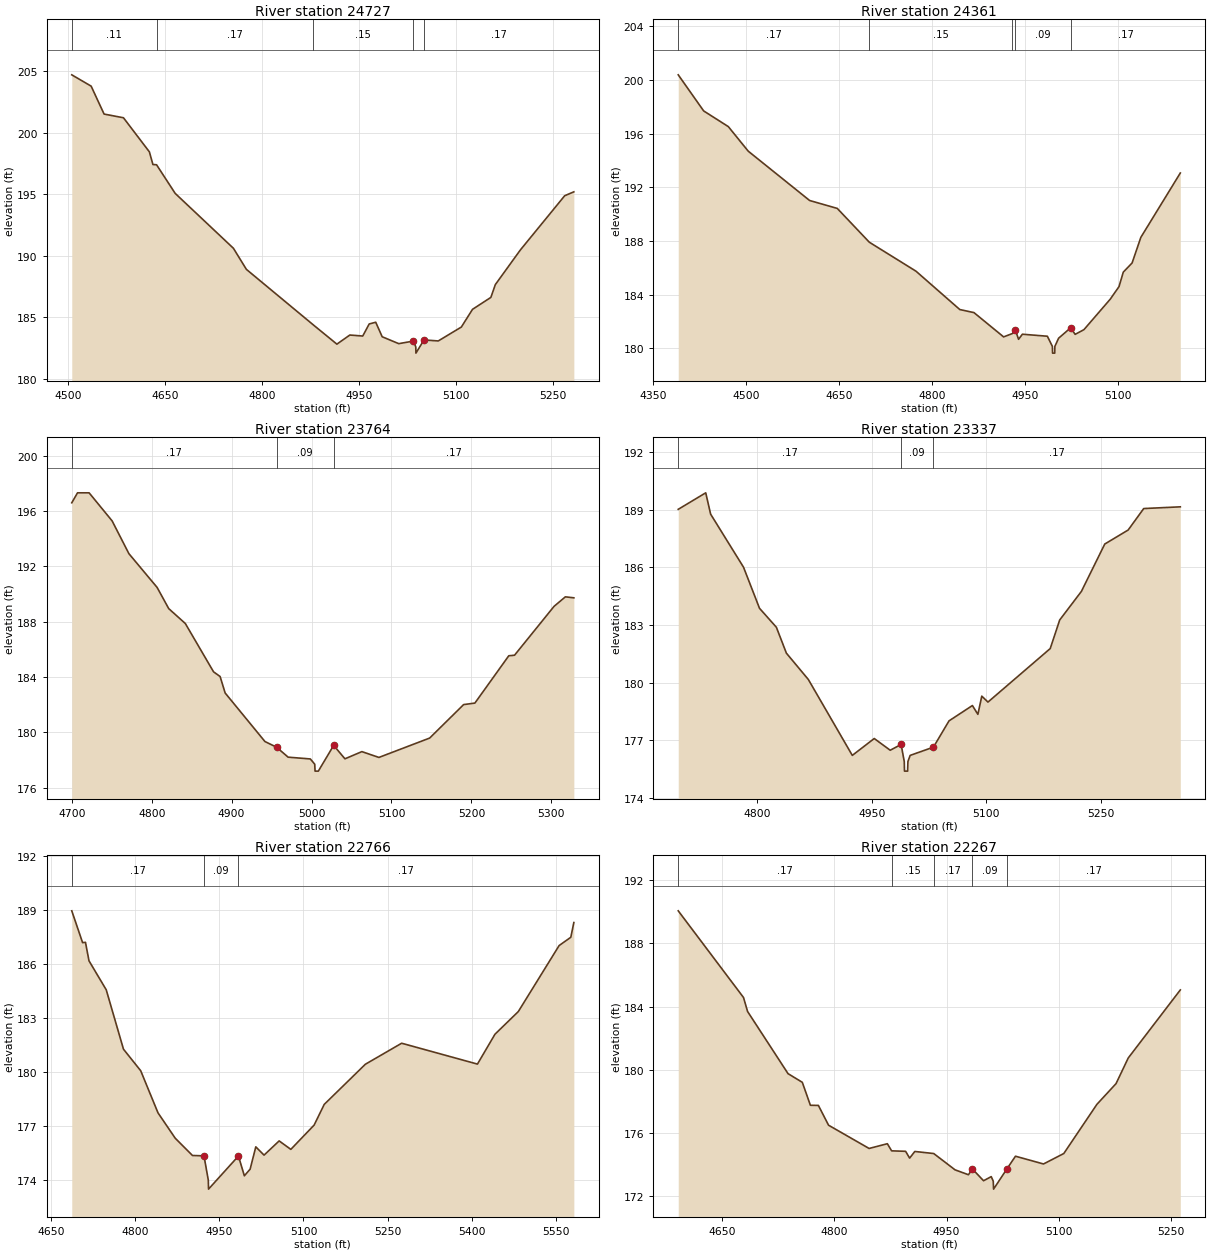
Type RM Length L Ch R = 1 ,24727   ,366,366,366
BEGIN DESCRIPTION:
LAKE CREEK TRIBUTARY NO. 10 32.0
END DESCRIPTION:
XS GIS Cut Line= 3
      3782017.85     10095511.06      3781998.23     10095016.84
      3782117.87     10094761.04
#Sta/Elev= 30
  4505.4   204.7  4535.4  203.78  4555.4  201.51  4585.4  201.21  4625.5  198.44
    4631  197.41  4636.6  197.39  4665.5  195.06  4755.6   190.6  4775.6  188.89
  4879.1  184.38  4915.7  182.81  4935.7  183.55  4955.7  183.47  4965.7  184.45
  4975.8  184.59  4985.8  183.41  5011.4  182.85  5034.2  183.06  5037.8  182.58
    5038  182.08  5050.5  183.15  5072.6  183.07  5108.3   184.2  5125.6  185.64
    5154  186.61  5160.9  187.65  5199.7  190.47  5268.2  194.87  5282.4  195.19
#Mann= 5 ,-1 , 0
  4505.4     .11       0  4636.6     .17       0  4879.1     .15       0
  5034.2     .09       0  5050.5     .17       0
Bank Sta=5034.2,5050.5
XS Rating Curve= 0 ,0
Exp/Cntr=0.3,0.1

Type RM Length L Ch R = 1 ,24361   ,597,597,597
BEGIN DESCRIPTION:
LAKE CREEK TRIBUTARY NO. 10 31.0
END DESCRIPTION:
XS GIS Cut Line= 3
      3782217.85      10095511.1      3782302.24     10094900.32
      3782167.86     10094761.08
#Sta/Elev= 30
    4390  200.39    4431   197.7  4470.8  196.53  4502.9   194.7    4602  191.02
  4646.6  190.43  4698.3  187.91  4773.6  185.75  4844.3  182.89  4867.2  182.66
    4915  180.85  4929.2   181.1    4934  181.36  4939.1  180.67  4945.3  181.05
  4985.6   180.9  4993.7  180.14    4994  179.64  4997.5  179.64  4997.7  180.14
  5003.7  180.75  5023.2  181.53  5030.4  181.04  5044.6  181.39    5087  183.66
  5101.2   184.6  5108.1  185.68  5122.3  186.36  5136.4  188.27  5200.1  193.07
#Mann= 5 ,-1 , 0
    4390     .17       0  4698.3     .15       0  4929.2     .17       0
    4934     .09       0  5023.2     .17       0
Bank Sta=4934,5023.2
XS Rating Curve= 0 ,0
Exp/Cntr=0.3,0.1

Type RM Length L Ch R = 1 ,23764   ,427,427,427
BEGIN DESCRIPTION:
LAKE CREEK TRIBUTARY NO. 10 30.0
END DESCRIPTION:
XS GIS Cut Line= 3
      3782817.82     10094761.05      3782580.48     10094577.55
      3782346.52     10094347.38
#Sta/Elev= 30
    4700   196.6  4707.2  197.32  4721.7  197.32  4750.5  195.29  4771.5  192.92
  4806.8  190.48  4821.3  188.95  4842.1  187.87  4877.4  184.38  4885.6  184.04
  4891.9  182.85  4941.7  179.34  4956.2  178.93  4970.7  178.21  4998.5  178.08
    5004   177.7  5004.4   177.2  5008.5   177.2  5027.7  179.06  5041.8  178.09
    5063  178.61  5084.3  178.19  5147.8  179.59  5190.3  182.01  5204.4  182.12
  5246.8  185.54    5254  185.58  5303.4  189.11  5317.6   189.8  5328.2  189.73
#Mann= 3 , 0 , 0
    4700     .17       0  4956.2     .09       0  5027.7     .17       0
Bank Sta=4956.2,5027.7
XS Rating Curve= 0 ,0
Exp/Cntr=0.3,0.1

Type RM Length L Ch R = 1 ,23337   ,571,571,571
BEGIN DESCRIPTION:
LAKE CREEK TRIBUTARY NO. 10 29.0
END DESCRIPTION:
XS GIS Cut Line= 3
      3782967.85     10094511.06       3782776.2     10094273.58
       3782430.9     10094204.52
#Sta/Elev= 30
  4696.6  189.03  4732.6  189.89    4739  188.78  4782.1  186.01    4803  183.87
  4825.1  182.88  4838.2  181.53  4866.9  180.16  4924.5   176.2  4953.2  177.08
  4974.1  176.47  4988.4  176.77  4992.5  175.88  4992.8  175.38  4996.9  175.38
  4997.3  175.88  5000.2   176.2  5030.7  176.63  5051.1     178  5081.7   178.8
  5088.9  178.34    5094  179.29  5102.1  178.98  5183.6  181.77    5196  183.26
  5224.4  184.75    5255  187.22  5285.6  187.95    5306  189.07  5353.9  189.16
#Mann= 3 , 0 , 0
  4696.6     .17       0  4988.4     .09       0  5030.7     .17       0
Bank Sta=4988.4,5030.7
XS Rating Curve= 0 ,0
Exp/Cntr=0.3,0.1

Type RM Length L Ch R = 1 ,22766   ,499,499,499
BEGIN DESCRIPTION:
LAKE CREEK TRIBUTARY NO. 10 28.0
END DESCRIPTION:
XS GIS Cut Line= 3
      3783317.82     10093861.07      3783012.42     10093793.89
      3782452.64     10093636.11
#Sta/Elev= 30
  4687.3  188.96  4706.6  187.19  4711.7  187.21    4718  186.18  4748.7  184.57
  4779.4  181.27  4810.1  180.07  4840.9  177.73  4871.6  176.32  4902.3  175.36
  4922.8  175.34  4930.5  173.99  4930.9  173.49  4984.2  175.33  4994.7  174.23
    5005   174.6  5015.1  175.84  5029.8  175.38  5056.7  176.17  5077.5   175.7
    5119  177.05    5137   178.2  5210.2  180.43  5274.9   181.6  5409.9  180.44
  5441.1   182.1  5482.7  183.36  5555.4  187.03  5576.2  187.49  5581.6  188.31
#Mann= 3 , 0 , 0
  4687.3     .17       0  4922.8     .09       0  4984.2     .17       0
Bank Sta=4922.8,4984.2
XS Rating Curve= 0 ,0
Exp/Cntr=0.3,0.1

Type RM Length L Ch R = 1 ,22267   ,499,499,499
BEGIN DESCRIPTION:
LAKE CREEK TRIBUTARY NO. 10 27.0
END DESCRIPTION:
XS GIS Cut Line= 3
      3783572.24     10093568.74      3783191.91     10093419.14
      3782941.53     10093339.96
#Sta/Elev= 30
  4591.3  190.05  4678.6  184.57    4684  183.69  4738.1  179.76  4757.2  179.21
    4768  177.76  4778.7  177.75  4792.3   176.5  4846.5  175.03  4870.9  175.33
  4876.6  174.88  4895.3  174.85  4900.7  174.42  4907.6  174.84  4932.9  174.71
  4961.4  173.68  4979.3  173.37  4984.7  173.73  4999.5  172.99  5009.8  173.25
  5012.5  172.96  5012.9  172.46  5031.1 173.763  5042.2  174.54  5079.7  174.05
  5106.8  174.71  5151.1  177.82  5176.7  179.13    5193  180.75  5262.6  185.05
#Mann= 5 ,-1 , 0
  4591.3     .17       0  4876.6     .15       0  4932.9     .17       0
  4984.7     .09       0  5031.1     .17       0
Bank Sta=4984.7,5031.1
XS Rating Curve= 0 ,0
Exp/Cntr=0.3,0.1

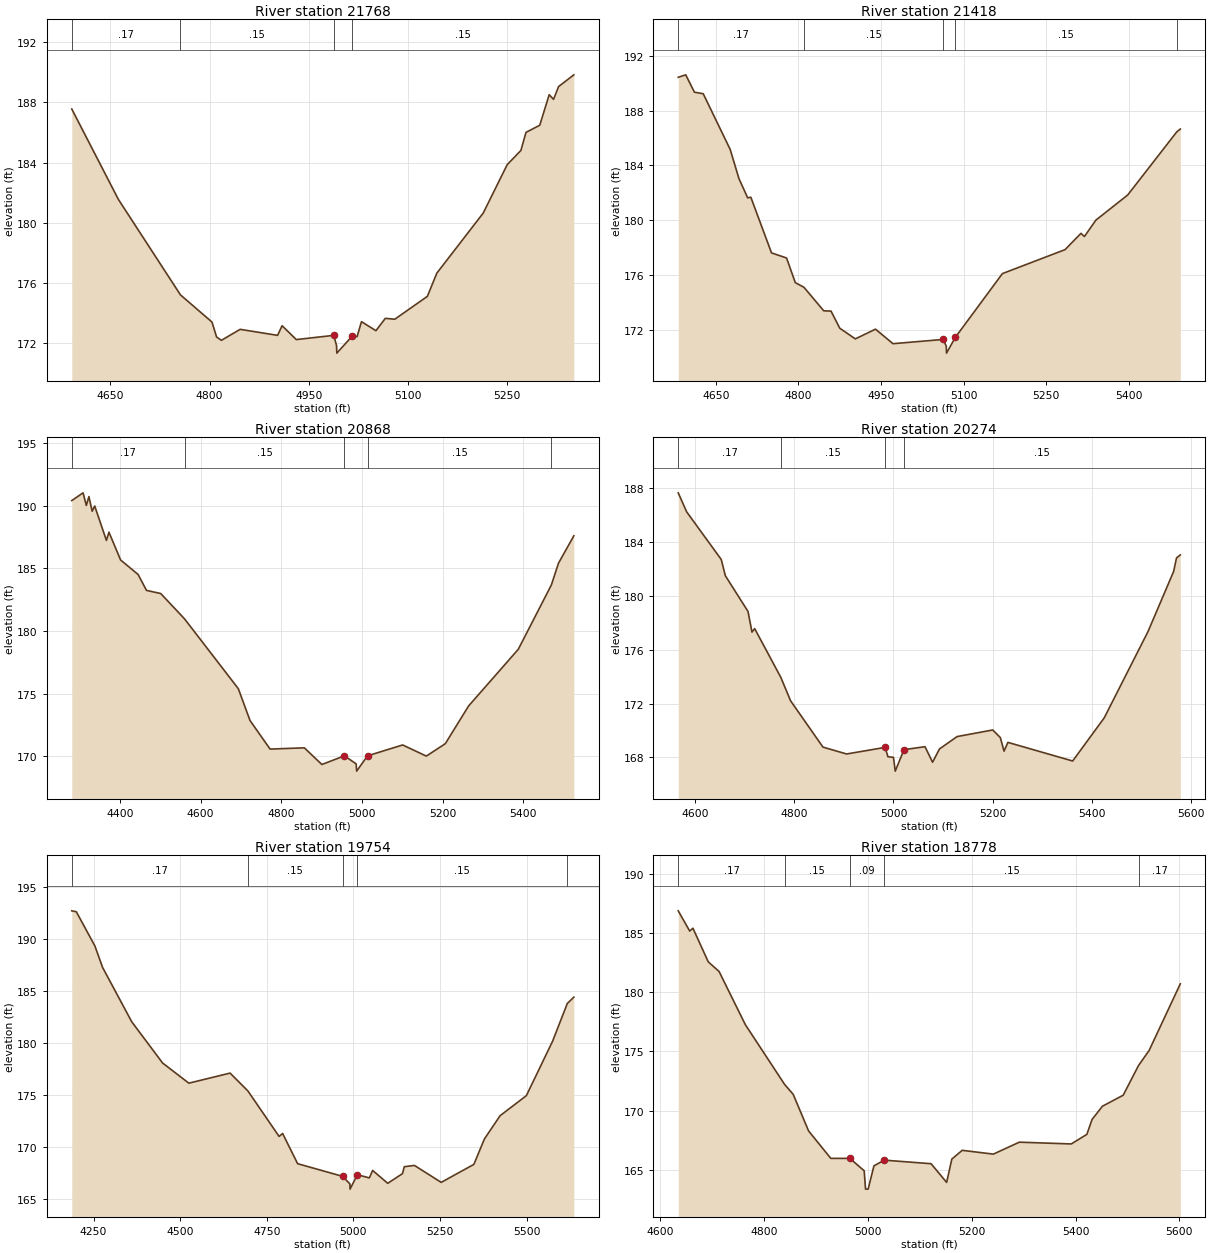
Type RM Length L Ch R = 1 ,21768   ,350,350,350
BEGIN DESCRIPTION:
LAKE CREEK TRIBUTARY NO. 10 26.0
END DESCRIPTION:
XS GIS Cut Line= 3
      3783767.82     10093411.04       3783469.4     10093132.23
      3783204.15     10092902.05
#Sta/Elev= 30
  4591.6  187.56  4662.1  181.56    4756  175.22  4803.8  173.41  4810.7  172.42
    4818   172.2  4846.3  172.93    4903  172.53  4909.8  173.17  4931.3  172.25
    4988  172.53  4992.2  171.85  4992.6  171.35  5015.7  172.47  5023.3  172.45
  5029.9  173.44  5051.8  172.84    5066  173.66  5080.3   173.6  5129.6  175.12
  5143.9  176.66  5214.1  180.65  5250.3  183.86  5271.1  184.81  5278.8  186.01
  5299.6  186.48  5313.9  188.51  5320.5   188.2  5328.1  189.05  5351.2  189.83
#Mann= 4 ,-1 , 0
  4591.6     .17       0    4756     .15       0    4988     .09       0
  5015.7     .15       0
Bank Sta=4988,5015.7
XS Rating Curve= 0 ,0
Exp/Cntr=0.3,0.1

Type RM Length L Ch R = 1 ,21418   ,550,550,550
BEGIN DESCRIPTION:
LAKE CREEK TRIBUTARY NO. 10 25.0
END DESCRIPTION:
XS GIS Cut Line= 3
      3783967.83     10093361.03      3783766.65     10093006.22
      3783454.15     10092610.38
#Sta/Elev= 30
  4581.5  190.43  4595.1  190.61    4611  189.34  4626.9  189.23  4675.9  185.16
  4691.8  183.03  4707.7  181.62  4713.4  181.67    4751   177.6  4778.3  177.23
  4794.2  175.43  4809.9  175.09  4845.9  173.37  4859.1  173.35    4875   172.1
  4903.3  171.32  4939.9  172.03  4971.7  170.97    5063  171.28  5068.5  170.78
  5068.9  170.28  5085.1  171.44  5170.5  176.09  5284.3  177.84  5313.2  179.03
  5319.5   178.8  5340.4     180  5398.1  181.83  5487.4  186.45  5493.7  186.65
#Mann= 5 ,-1 , 0
  4581.5     .17       0  4809.9     .15       0    5063     .09       0
  5085.1     .15       0  5487.4     .11       0
Bank Sta=5063,5085.1
XS Rating Curve= 0 ,0
Exp/Cntr=0.3,0.1

Type RM Length L Ch R = 1 ,20868   ,594,594,594
BEGIN DESCRIPTION:
LAKE CREEK TRIBUTARY NO. 10 24.0
END DESCRIPTION:
XS GIS Cut Line= 3
      3784667.84     10093161.06      3784106.93      10092721.5
      3783617.81     10092511.05
#Sta/Elev= 30
  4280.4  190.42  4308.4  191.04  4316.5  190.03  4322.9  190.74    4331  189.57
  4337.3  189.99  4366.3  187.24  4372.6   187.9  4401.5  185.68  4444.9  184.52
  4465.7  183.25    4501     183    4560  180.98  4693.5   175.4  4722.5  172.86
  4772.2  170.58  4857.2  170.68  4900.6  169.35  4956.6  170.04  4985.6   169.4
  4986.9  168.82  5013.8  170.04  5100.9  170.91  5159.7  170.02  5206.7  171.01
  5264.7  174.03  5387.8  178.55  5469.7  183.68  5487.4  185.42  5525.5  187.61
#Mann= 5 ,-1 , 0
  4280.4     .17       0    4560     .15       0  4956.6     .09       0
  5013.8     .15       0  5469.7     .17       0
Bank Sta=4956.6,5013.8
XS Rating Curve= 0 ,0
Exp/Cntr=0.3,0.1

Type RM Length L Ch R = 1 ,20274   ,520,520,520
BEGIN DESCRIPTION:
LAKE CREEK TRIBUTARY NO. 10 23.0
END DESCRIPTION:
XS GIS Cut Line= 3
      3784808.28     10092582.59      3784406.05     10092420.39
      3783917.89     10092111.09
#Sta/Elev= 30
  4566.3  187.61  4583.3   186.2    4653  182.67  4661.2  181.47  4706.9  178.82
  4714.9  177.29  4720.3  177.55  4773.1  173.93  4792.7   172.2  4857.9  168.77
  4905.5  168.26  4983.3  168.75  4988.7  168.06    5000  168.01  5003.5  166.99
  5021.2  168.58  5063.5   168.8  5078.8  167.65  5092.6  168.63  5128.1  169.55
    5200  170.04  5215.2  169.48  5222.8  168.47  5230.5  169.12    5361  167.74
  5424.5  170.93  5512.7  177.32  5564.4  181.78  5570.3  182.79  5577.9  183.01
#Mann= 4 ,-1 , 0
  4566.3     .17       0  4773.1     .15       0  4983.3     .09       0
  5021.2     .15       0
Bank Sta=4983.3,5021.2
XS Rating Curve= 0 ,0
Exp/Cntr=0.3,0.1

Type RM Length L Ch R = 1 ,19754   ,976,976,976
BEGIN DESCRIPTION:
LAKE CREEK TRIBUTARY NO. 10 22.0
END DESCRIPTION:
XS GIS Cut Line= 2
      3785350.03     10092353.46      3784011.28     10091798.54
#Sta/Elev= 30
    4187  192.72  4200.2  192.63  4253.7  189.34    4276  187.27  4360.1  182.04
  4449.2  178.07    4525  176.13    4644   177.1  4695.4  175.38  4785.5     171
  4795.6  171.29  4838.9  168.38  4968.9  167.16  4989.8  166.43  4990.3  165.93
  5011.3  167.32    5046  167.01  5055.4  167.73  5099.1  166.49  5141.5  167.42
  5146.9  168.09  5176.2  168.21  5253.3  166.58  5347.6  168.31  5378.1  170.76
  5423.4     173  5499.2  174.93    5575  180.18  5617.3   183.8  5636.2  184.41
#Mann= 5 ,-1 , 0
    4187     .17       0  4695.4     .15       0  4968.9     .09       0
  5011.3     .15       0  5617.3     .17       0
Bank Sta=4968.9,5011.3
XS Rating Curve= 0 ,0
Exp/Cntr=0.3,0.1

Type RM Length L Ch R = 1 ,18778   ,499,499,499
BEGIN DESCRIPTION:
LAKE CREEK TRIBUTARY NO. 10 21.0
END DESCRIPTION:
XS GIS Cut Line= 3
      3785217.82     10091711.05      3784919.44     10091500.13
      3784317.84     10091511.07
#Sta/Elev= 30
  4634.6  186.89  4656.7  185.18  4662.9  185.42  4692.4  182.58  4713.3  181.76
  4763.8  177.27  4839.4  172.22  4856.1  171.37  4885.7  168.28  4928.5  165.96
  4965.2  165.96  4992.8  164.91  4995.4  163.36  5000.4  163.36  5011.6  165.33
  5031.6  165.81  5121.6  165.51  5151.6  163.93  5161.6   165.9  5181.6  166.64
  5241.6  166.32  5291.6  167.33  5391.7  167.18  5421.7  167.99  5431.7  169.25
  5451.7  170.37  5491.7   171.3  5521.2  173.81  5541.7  175.09  5601.7  180.72
#Mann= 5 ,-1 , 0
  4634.6     .17       0  4839.4     .15       0  4965.2     .09       0
  5031.6     .15       0  5521.2     .17       0
Bank Sta=4965.2,5031.6
XS Rating Curve= 0 ,0
Exp/Cntr=0.3,0.1

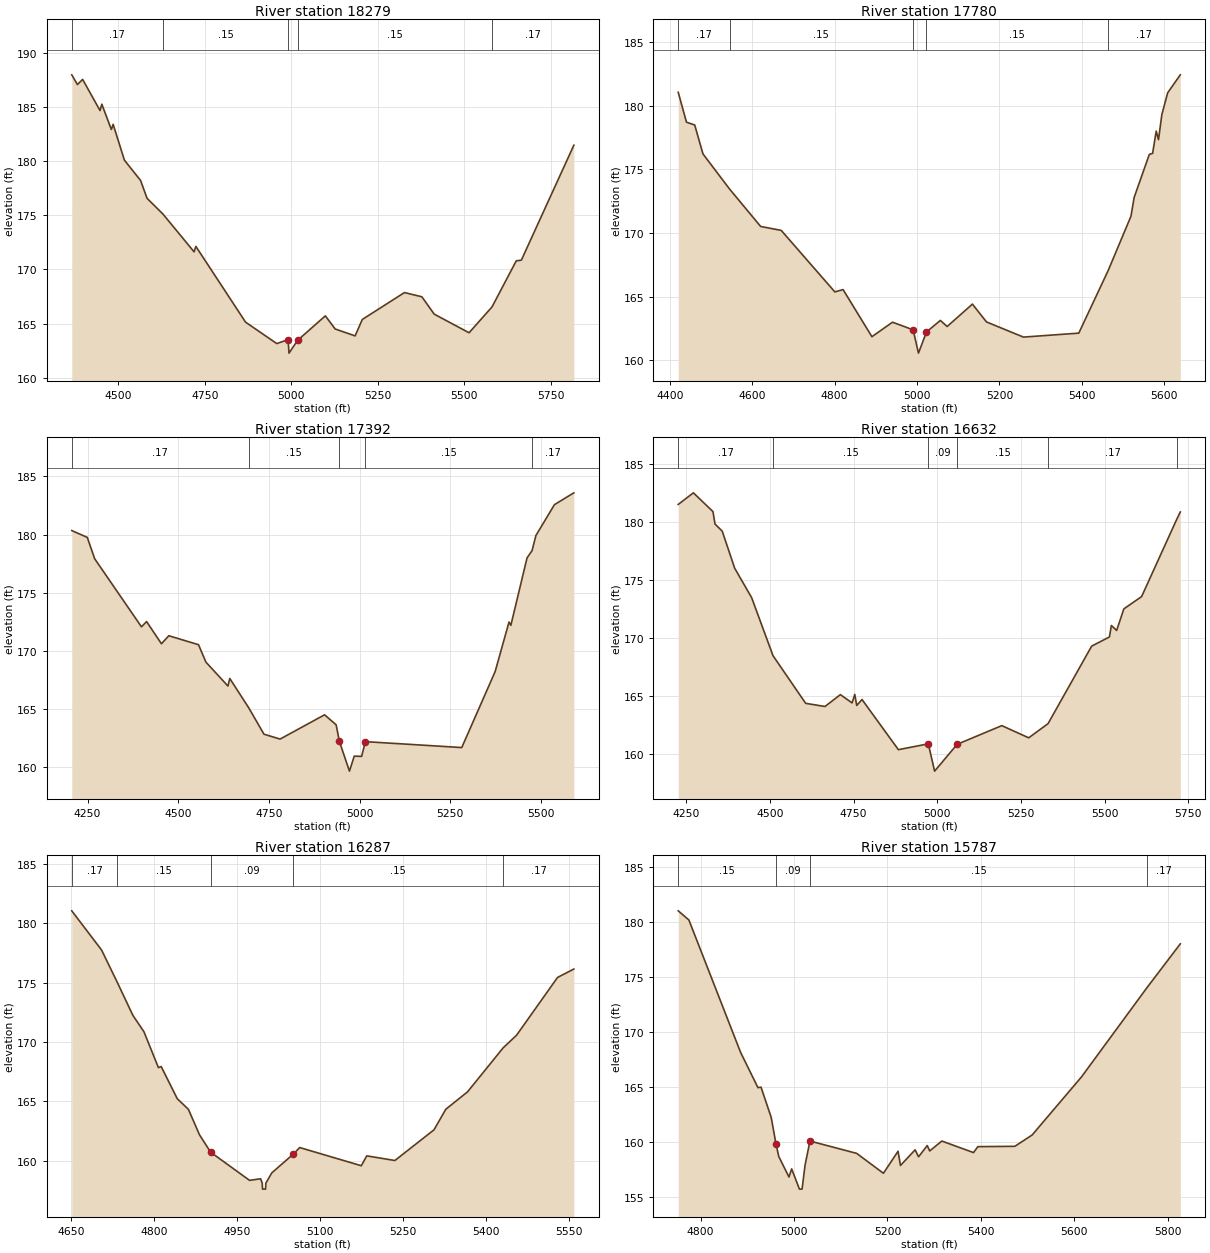
Type RM Length L Ch R = 1 ,18279   ,499,499,499
BEGIN DESCRIPTION:
LAKE CREEK TRIBUTARY NO. 10 20.0
END DESCRIPTION:
XS GIS Cut Line= 3
      3785367.86     10091761.09       3785180.8     10091154.48
      3784516.67     10090679.85
#Sta/Elev= 30
  4365.2  187.96  4381.6  187.06  4396.6  187.54  4446.9  184.66  4452.1  185.25
  4479.6  182.91  4484.8  183.39  4517.4  180.08  4564.1  178.21  4582.8  176.56
  4628.7  175.11  4718.7  171.62  4723.9  172.12  4867.5  165.13  4957.8  163.15
  4990.5  163.52    4993  162.27  5018.3  163.46  5098.1  165.71  5126.5   164.5
  5184.1  163.86    5205  165.38  5326.7  167.86  5377.1  167.47  5412.7  165.87
  5513.5  164.15  5579.9  166.54  5649.9  170.79  5664.6  170.85  5816.3  181.46
#Mann= 5 ,-1 , 0
  4365.2     .17       0  4628.7     .15       0  4990.5     .09       0
  5018.3     .15       0  5579.9     .17       0
Bank Sta=4990.5,5018.3
XS Rating Curve= 0 ,0
Exp/Cntr=0.3,0.1

Type RM Length L Ch R = 1 ,17780   ,388,388,388
BEGIN DESCRIPTION:
LAKE CREEK TRIBUTARY NO. 10 19.0
END DESCRIPTION:
XS GIS Cut Line= 3
      3785817.84     10090811.07      3785238.37     10090798.91
      3784667.87     10090511.08
#Sta/Elev= 30
  4420.4  181.06  4440.4  178.71  4460.4  178.49  4480.4  176.22    4545  173.46
  4620.4  170.52  4670.4  170.21  4800.5  165.38  4820.5  165.56  4890.5  161.86
  4940.5     163  4990.5   162.4  5003.5  160.57  5022.9  162.23  5056.6  163.14
  5073.1  162.66  5134.4  164.42  5168.6  163.02  5258.2  161.83  5392.6  162.14
  5464.1  167.07  5519.2  171.32    5527   172.8  5563.8  176.18  5571.8  176.26
  5580.5  178.01  5586.1  177.34  5594.2  179.31  5608.4  181.02    5639  182.43
#Mann= 5 ,-1 , 0
  4420.4     .17       0    4545     .15       0  4990.5     .09       0
  5022.9     .15       0  5464.1     .17       0
Bank Sta=4990.5,5022.9
XS Rating Curve= 0 ,0
Exp/Cntr=0.3,0.1

Type RM Length L Ch R = 1 ,17392   ,760,760,760
BEGIN DESCRIPTION:
LAKE CREEK TRIBUTARY NO. 10 18.0
END DESCRIPTION:
XS GIS Cut Line= 2
      3786009.68     10090586.08      3784655.55     10090299.63
#Sta/Elev= 30
  4206.3  180.34  4249.1  179.75  4269.5  177.91  4398.4  172.05  4412.6   172.5
  4453.5  170.59  4473.9  171.28  4555.7  170.51  4576.1  169.01  4636.8  166.95
  4641.9   167.6    4694  165.08  4736.2   162.8  4780.6  162.38  4903.2  164.47
  4935.1  163.61  4944.1  162.18  4971.8  159.62    4985  160.91  5005.4  160.89
  5015.7  162.16  5281.4  161.65  5373.4  168.19  5411.7  172.46  5416.8  172.18
  5461.4  177.99  5475.2  178.61  5485.8  179.91  5536.9  182.57  5590.4  183.59
#Mann= 5 ,-1 , 0
  4206.3     .17       0    4694     .15       0  4944.1     .09       0
  5015.7     .15       0  5475.2     .17       0
Bank Sta=4944.1,5015.7
XS Rating Curve= 0 ,0
Exp/Cntr=0.3,0.1

Type RM Length L Ch R = 1 ,16632   ,345,345,345
BEGIN DESCRIPTION:
LAKE CREEK TRIBUTARY NO. 10 17.0
END DESCRIPTION:
XS GIS Cut Line= 2
      3786017.89     10090361.09      3784717.83     10089611.06
#Sta/Elev= 30
  4225.6  181.53  4270.9  182.53  4329.5  180.91  4335.5  179.84  4357.1  179.23
  4394.4  176.03    4445   173.5  4508.9   168.5  4606.6  164.39  4664.3  164.12
  4710.3  165.14  4745.2  164.43  4753.4  165.16  4759.2  164.21    4775  164.72
  4883.7   160.4  4973.2   160.9    4992  158.55  5059.4  160.86  5192.9  162.47
  5273.3  161.42  5331.1  162.64  5461.5  169.32  5514.6  170.11  5520.4   171.1
  5536.2  170.67  5557.7  172.53  5610.8  173.59  5716.7   180.3  5726.5  180.88
#Mann= 6 ,-1 , 0
  4225.6     .17       0  4508.9     .15       0  4973.2     .09       0
  5059.4     .15       0  5331.1     .17       0  5716.7     .11       0
Bank Sta=4973.2,5059.4
XS Rating Curve= 0 ,0
Exp/Cntr=0.3,0.1

Type RM Length L Ch R = 1 ,16287   ,500,500,500
BEGIN DESCRIPTION:
LAKE CREEK TRIBUTARY NO. 10 16.0
END DESCRIPTION:
XS GIS Cut Line= 3
       3785867.8     10089661.08      3785520.59     10089694.25
      3784967.81     10089611.07
#Sta/Elev= 30
  4651.2  181.04  4705.1  177.74  4733.4  175.03  4761.7  172.24  4781.7  170.86
  4807.9  167.84  4812.9  167.93    4842  165.22  4862.1  164.33  4882.2  162.18
  4902.3  160.72  4972.6  158.35  4992.7  158.48  4995.6  158.11  4996.1  157.61
  5001.6  157.61  5002.1  158.11  5012.9  158.98  5051.6  160.55  5063.4  161.11
  5174.7  159.58  5184.6  160.41  5235.4  160.02  5306.1   162.6  5327.6  164.34
  5366.8   165.8  5431.1   169.5  5455.5  170.57  5529.5  175.43    5559  176.14
#Mann= 5 ,-1 , 0
  4651.2     .17       0  4733.4     .15       0  4902.3     .09       0
  5051.6     .15       0  5431.1     .17       0
Bank Sta=4902.3,5051.6
XS Rating Curve= 0 ,0
Exp/Cntr=0.3,0.1

Type RM Length L Ch R = 1 ,15787   ,735,735,735
BEGIN DESCRIPTION:
LAKE CREEK TRIBUTARY NO. 10 15.0
END DESCRIPTION:
XS GIS Cut Line= 3
      3785967.88     10089411.09      3785749.98     10089292.68
      3784967.85     10089561.07
#Sta/Elev= 30
    4752  181.02  4774.8  180.19  4885.5  168.16  4922.7  164.95  4929.2     165
  4951.1  162.24 4961.28159.8361  4967.3  158.69  4989.1  156.83  4994.8  157.57
  5011.5  155.73  5017.1  155.73  5023.4  157.88    5034   160.1    5134  158.98
  5191.3  157.17  5222.6  159.17  5227.8  157.88  5259.1   159.3  5266.6  158.67
  5285.1  159.69  5290.4   159.2  5316.3   160.1  5384.2  159.05  5393.4  159.59
  5472.7  159.62  5509.7  160.65  5615.4  165.93  5755.4  174.03  5826.9  178.02
#Mann= 4 ,-1 , 0
    4752     .15       0 4961.28     .09       0    5034     .15       0
  5755.4     .17       0
Bank Sta=4961.28,5034
XS Rating Curve= 0 ,0
Exp/Cntr=0.3,0.1

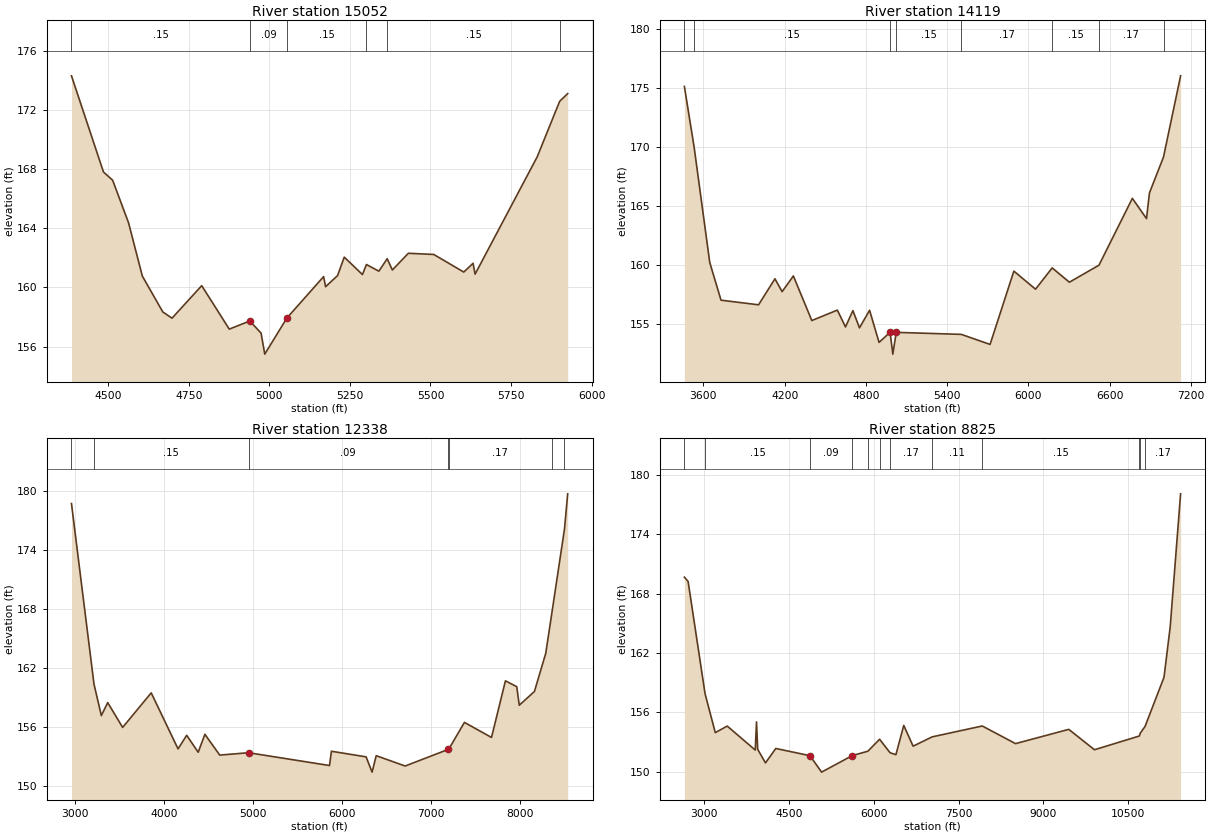
Type RM Length L Ch R = 1 ,15052   ,933,933,933
BEGIN DESCRIPTION:
LAKE CREEK TRIBUTARY NO. 10 14.0
END DESCRIPTION:
XS GIS Cut Line= 3
      3786117.87     10089261.09      3785645.13     10088849.97
      3784926.87     10089413.28
#Sta/Elev= 30
  4386.4  174.31  4485.6  167.81  4514.1  167.25  4563.5  164.37  4606.2  160.77
  4669.8  158.34  4698.3  157.92  4790.4  160.12  4875.9  157.18  4939.5  157.73
  4974.6  156.91    4986  155.49  5054.6  157.93  5168.5  160.73  5174.8  160.05
  5211.8   160.8  5232.6  162.05    5289  160.87  5301.4  161.55  5339.9   161.1
  5365.8  161.94  5381.8  161.18  5431.5  162.31  5510.2  162.23  5603.3  161.04
  5632.2  161.63  5638.5   160.9  5831.1  168.83  5900.9  172.59  5925.7  173.11
#Mann= 6 ,-1 , 0
  4386.4     .15       0  4939.5     .09       0  5054.6     .15       0
  5301.4     .17       0  5365.8     .15       0  5900.9     .17       0
Bank Sta=4939.5,5054.6
XS Rating Curve= 0 ,0
Exp/Cntr=0.3,0.1

Type RM Length L Ch R = 1 ,14119   ,1781,1781,1781
BEGIN DESCRIPTION:
Mapping XS bf28aed9
END DESCRIPTION:
XS GIS Cut Line= 3
      3786313.96     10089239.93      3785923.34     10087972.59
      3783911.16     10089160.81
#Sta/Elev= 30
    3460  175.11  3531.7     170  3647.2  160.23  3730.5  157.04  4007.6  156.65
  4128.5  158.85  4181.4  157.76  4264.5  159.09  4400.6  155.32  4589.1   156.2
  4649.3  154.78    4704  156.16  4752.5   154.7    4827  156.19  4897.1  153.47
  4978.4  154.33  4998.7  152.48    5024  154.32  5504.2  154.15  5716.6   153.3
  5892.2   159.5  6052.1  157.97    6175  159.77  6301.9  158.56  6520.5     160
  6766.8  165.65  6871.3  163.94  6893.1  166.11  6996.9  169.15    7123  176.01
#Mann= 8 ,-1 , 0
    3460     .17       0  3531.7     .15       0  4978.4     .09       0
    5024     .15       0  5504.2     .17       0    6175     .15       0
  6520.5     .17       0  6996.9     .11       0
Bank Sta=4978.4,5024
XS Rating Curve= 0 ,0
Exp/Cntr=0.3,0.1

Type RM Length L Ch R = 1 ,12338   ,3513,3513,3513
BEGIN DESCRIPTION:
LAKE CREEK TRIBUTARY NO. 10 13.0
END DESCRIPTION:
XS GIS Cut Line= 3
       3786482.8      10089299.2      3785701.55     10086825.23
      3783706.23     10089037.43
#Sta/Elev= 30
  2963.2  178.72  3216.1  160.39  3298.6  157.19  3370.2  158.51    3538  155.99
  3858.8   159.5  4160.2  153.81  4257.2  155.19  4386.6  153.47  4461.7  155.29
  4628.7  153.18    4952  153.42  5861.7  152.12    5883  153.57  6272.4     153
  6339.7  151.45    6386  153.12  6711.1  152.07  7193.1  153.75  7202.4   153.8
  7376.9   156.5  7681.1  154.97  7837.3  160.72  7964.4  160.13  7992.8  158.24
  8163.1  159.64  8290.2  163.51  8354.9  167.37  8500.7  176.13  8536.7  179.71
#Mann= 7 ,-1 , 0
  2963.2     .17       0  3216.1     .15       0    4952     .09       0
  7193.1     .15       0  7202.4     .17       0  8354.9     .11       0
  8500.7     .17       0
Bank Sta=4952,7193.1
XS Rating Curve= 0 ,0
Exp/Cntr=0.3,0.1

Type RM Length L Ch R = 1 ,8825    ,0,0,0
BEGIN DESCRIPTION:
LAKE CREEK TRIBUTARY NO. 10 10.0
END DESCRIPTION:
XS GIS Cut Line= 5
      3789117.85     10089361.07      3787897.58     10087356.94
      3787112.14     10086087.39      3784931.15     10086629.92
      3783412.45     10088842.89
#Sta/Elev= 30
  2653.6  169.65  2719.4  169.22  3018.9  157.88  3199.8  153.95  3410.9  154.61
  3906.3  152.19  3928.1  155.03  3949.4  152.26    4087  150.89  4269.3  152.35
  4873.4  151.62    5079  149.96  5620.7  151.63    5896  152.07    6104  153.28
  6288.6  151.92  6392.5  151.72  6531.1  154.68  6696.4  152.58  7032.1  153.52
  7918.6  154.62  8506.7  152.84  9447.7  154.28  9901.9  152.22 10695.9  153.61
 10711.8   153.9 10795.6  154.57   11131  159.54 11240.2  164.62 11424.3  178.07
#Mann= 12 ,-1 , 0
  2653.6     .11       0  3018.9     .15       0  4873.4     .09       0
  5620.7     .15       0    5896     .17       0    6104     .11       0
  6288.6     .17       0  7032.1     .11       0  7918.6     .15       0
 10695.9     .17       0 10711.8     .15       0 10795.6     .17       0
Bank Sta=4873.4,5620.7
XS Rating Curve= 0 ,0
Exp/Cntr=0.3,0.1

Chan Stop Cuts=-1
Use User Specified Reach Order=0
Composite Channel Slope=5