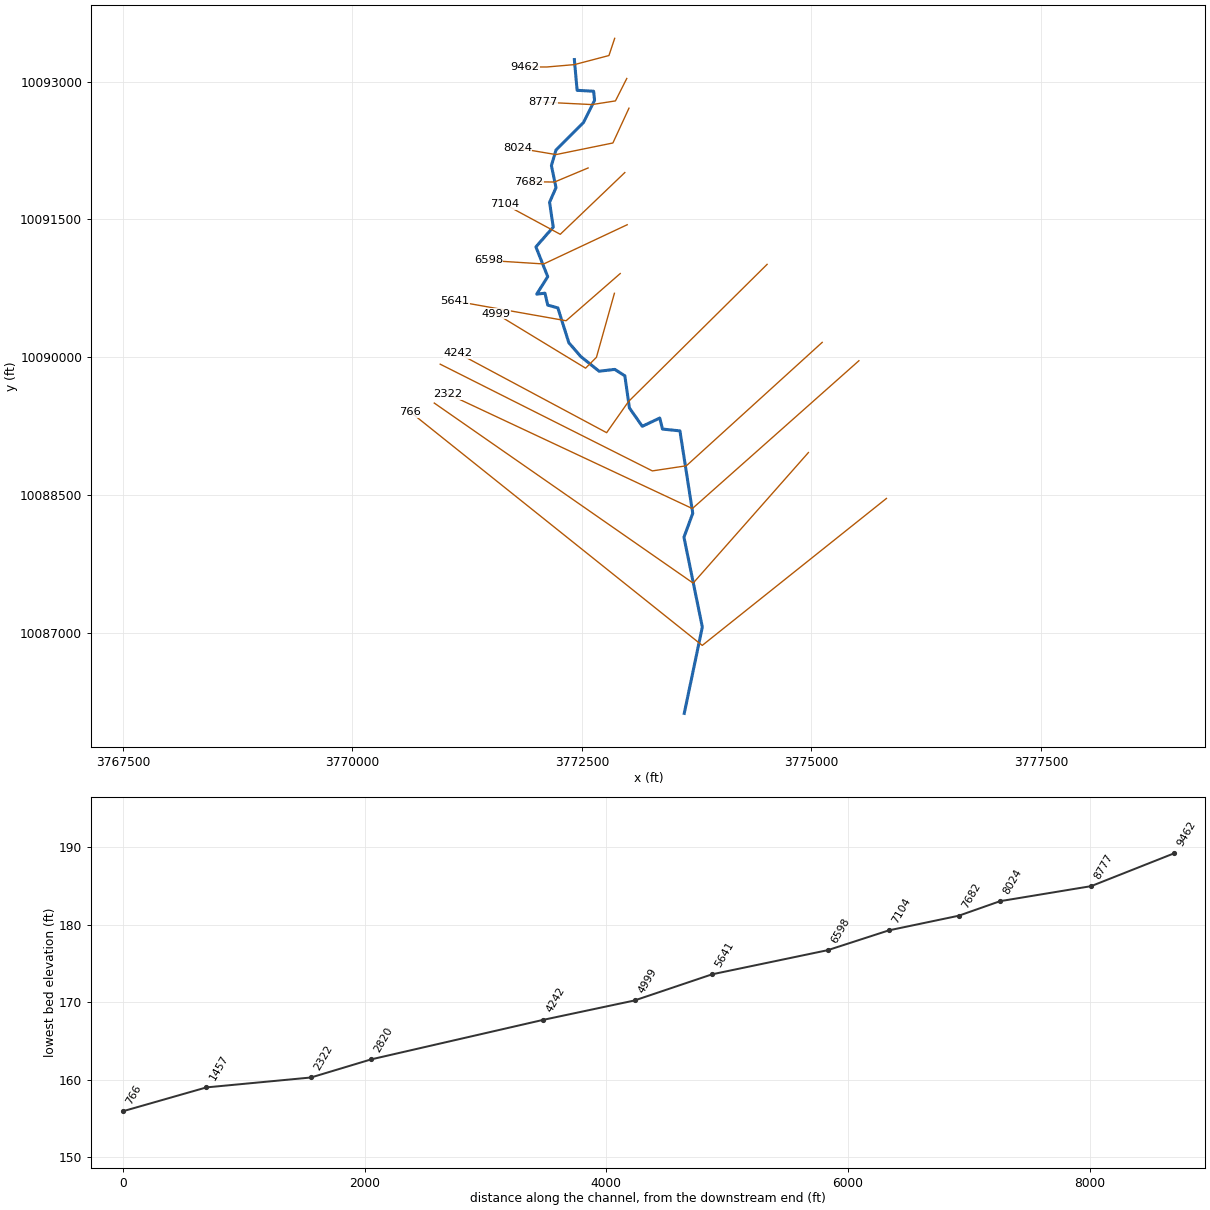
--- LAKE CREEK TRIBUTARY NO 11 2.prj (project) ---

Proj Title=LAKE CREEK TRIBUTARY NO 11 2 Base Level Engineering
Current Plan=p01
Default Exp/Contr=0.3,0.1
English Units
Geom File=g01
Flow File=f01
Flow File=f02
Plan File=p01
Y Axis Title=Elevation
X Axis Title(PF)=Main Channel Distance
X Axis Title(XS)=Station
BEGIN DESCRIPTION:
LAKE CREEK TRIBUTARY NO 11 2
END DESCRIPTION:
DSS Export Rating Curves= 0
DSS Export Rating Curve Sorted= 0
DSS Export Volume Flow Curves= 0
DXF OffsetX= 0
DXF OffsetY= 0
DXF ScaleX= 1
DXF ScaleY= 10

--- LAKE CREEK TRIBUTARY NO 11 2.p01 (plan) ---

Plan Title=Multiple Run
Short Identifier=Multiple
Geom File=g01
Flow File=f01
Subcritical Flow
K Sum by GR= 0
Std Step Tol= 0.01
Critical Tol= 0.01
Num of Std Step Trials= 20
Max Error Tol= 0.3
Flow Tol Ratio= 0.001
Split Flow NTrial= 30
Split Flow Tol= 0.02
Split Flow Ratio= 0.02
Log Output Level= 0
Friction Slope Method= 1
Unsteady Friction Slope Method= 2
Unsteady Bridges Friction Slope Method= 1
Parabolic Critical Depth
Global Vel Dist=  1 , 1 , 1
Global Log Level= 0
CheckData=True
Encroach Param= -1, 0, 0, 0
BEGIN DESCRIPTION:
Multiple Run
END DESCRIPTION:

--- LAKE CREEK TRIBUTARY NO 11 2.f01 (steady flow) ---

Flow Title=Multiple
Program Version=4.10
Number of Profiles= 7
Profile Names=10-year,25-year,50-year,1pct_min,100-year,1pct_plu,500-year
River Rch & RM=LAKE CREEK TRIBU,Reach-1         ,9462
    1141    1597    2207    1002    3025    9135    5879
River Rch & RM=LAKE CREEK TRIBU,Reach-1         ,2820
    1458    2063    2872    1311    3960   11959    7795
Boundary for River Rch & Prof#=LAKE CREEK TRIBU,Reach-1         , 1
Up Type= 0
Dn Type= 3
Dn Slope=0.005
Boundary for River Rch & Prof#=LAKE CREEK TRIBU,Reach-1         , 2
Up Type= 0
Dn Type= 3
Dn Slope=0.005
Boundary for River Rch & Prof#=LAKE CREEK TRIBU,Reach-1         , 3
Up Type= 0
Dn Type= 3
Dn Slope=0.005
Boundary for River Rch & Prof#=LAKE CREEK TRIBU,Reach-1         , 4
Up Type= 0
Dn Type= 3
Dn Slope=0.005
Boundary for River Rch & Prof#=LAKE CREEK TRIBU,Reach-1         , 5
Up Type= 0
Dn Type= 3
Dn Slope=0.005
Boundary for River Rch & Prof#=LAKE CREEK TRIBU,Reach-1         , 6
Up Type= 0
Dn Type= 3
Dn Slope=0.005
Boundary for River Rch & Prof#=LAKE CREEK TRIBU,Reach-1         , 7
Up Type= 0
Dn Type= 3
Dn Slope=0.005
DSS Import GetInterval= 0
DSS Import GetPeak= 0
DSS Import FillOption= 0

--- LAKE CREEK TRIBUTARY NO 11 2.f02 (steady flow) ---

Flow Title=Orig_BLE_Flows
Program Version=4.10
Number of Profiles= 7
Profile Names=10-year,25-year,50-year,1pct_min,100-year,1pct_plu,500-year
River Rch & RM=LAKE CREEK TRIBU,Reach-1         ,9462
    1141    1566    1919     770    2327    7027    3418
River Rch & RM=LAKE CREEK TRIBU,Reach-1         ,2820
    1458    2023    2497    1009    3046    9199    4532
Boundary for River Rch & Prof#=LAKE CREEK TRIBU,Reach-1         , 1
Up Type= 0
Dn Type= 3
Dn Slope=0.005
Boundary for River Rch & Prof#=LAKE CREEK TRIBU,Reach-1         , 2
Up Type= 0
Dn Type= 3
Dn Slope=0.005
Boundary for River Rch & Prof#=LAKE CREEK TRIBU,Reach-1         , 3
Up Type= 0
Dn Type= 3
Dn Slope=0.005
Boundary for River Rch & Prof#=LAKE CREEK TRIBU,Reach-1         , 4
Up Type= 0
Dn Type= 3
Dn Slope=0.005
Boundary for River Rch & Prof#=LAKE CREEK TRIBU,Reach-1         , 5
Up Type= 0
Dn Type= 3
Dn Slope=0.005
Boundary for River Rch & Prof#=LAKE CREEK TRIBU,Reach-1         , 6
Up Type= 0
Dn Type= 3
Dn Slope=0.005
Boundary for River Rch & Prof#=LAKE CREEK TRIBU,Reach-1         , 7
Up Type= 0
Dn Type= 3
Dn Slope=0.005
DSS Import GetInterval= 0
DSS Import GetPeak= 0
DSS Import FillOption= 0

--- LAKE CREEK TRIBUTARY NO 11 2.g01 (geometry) ---

Geom Title=Existing Conditions
Program Version=4.10

River Reach=LAKE CREEK TRIBU,Reach-1
Reach XY= 30
      3772418.23     10093241.84      3772448.23     10092906.84
      3772628.23     10092896.84      3772638.23     10092796.84
      3772518.23     10092556.84      3772218.23     10092256.84
      3772168.23     10092086.84      3772218.23     10091846.84
      3772148.23     10091686.84      3772188.23     10091416.84
      3771999.41     10091201.63      3772128.23     10090876.84
      3772008.23     10090686.84      3772098.23     10090696.84
      3772128.23     10090566.84      3772238.23     10090536.84
      3772358.23     10090156.84      3772488.23     10090006.84
      3772688.23     10089846.84      3772858.23     10089866.84
      3772968.23     10089796.84      3773018.23     10089446.84
      3773158.23     10089246.84      3773348.23     10089336.84
      3773378.23     10089216.84      3773568.23     10089196.84
      3773708.08     10088298.89      3773612.15     10088038.76
      3773812.15     10087060.76      3773615.32     10086119.75

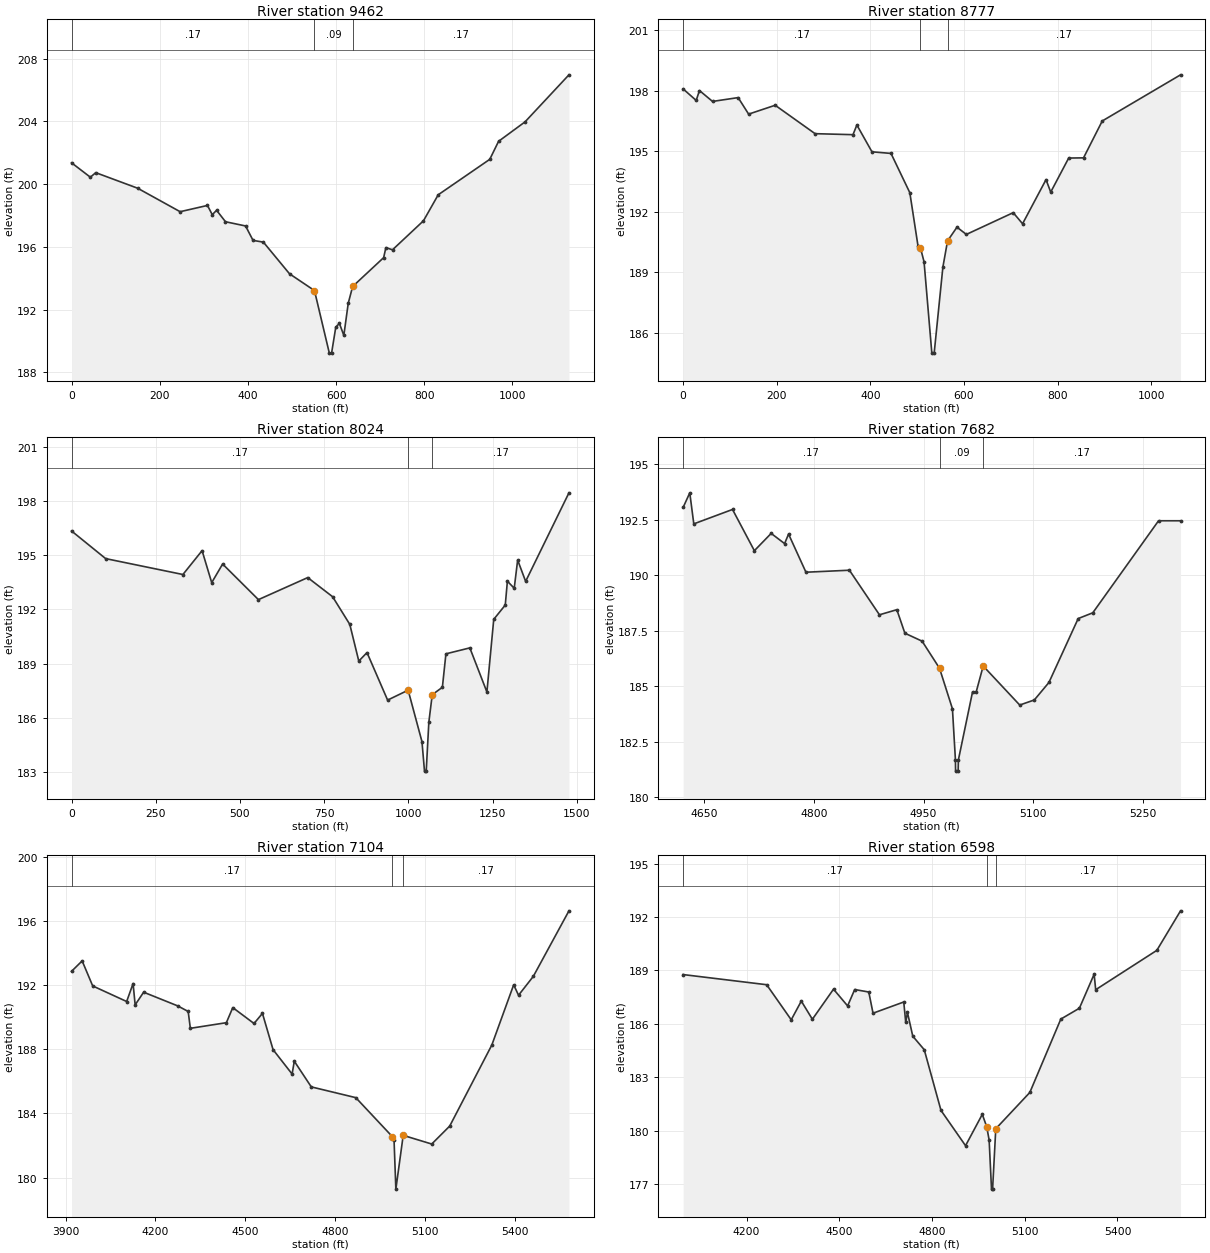
Type RM Length L Ch R = 1 ,9462    ,685,685,685
BEGIN DESCRIPTION:
LAKE CREEK TRIBUTARY NO. 11. 2 14.0
END DESCRIPTION:
XS GIS Cut Line= 5
      3772857.48     10093473.17      3772795.04     10093285.82
      3772418.23     10093186.84      3772117.85     10093161.07
      3771878.25     10093161.73
#Sta/Elev= 30
       0  201.36    42.7  200.44    54.9  200.73   149.8  199.74   246.3  198.24
   308.3  198.64   319.2  198.05     329  198.33   349.2   197.6   394.7  197.33
   411.7  196.41   435.1   196.3   494.4  194.28     551  193.21   584.7  189.22
   589.8  189.22   599.3  190.87   607.5  191.12   617.6  190.35   627.6   192.4
   637.6  193.47   707.9  195.31     713  195.95     728  195.81   798.2  197.66
   831.7  199.32   948.6  201.58   968.6  202.73  1028.6  203.97  1128.2  206.97
#Mann= 3 ,-1 , 0
       0     .17       0     551     .09       0   637.6     .17       0
Bank Sta=551,637.6
XS Rating Curve= 0 ,0
Exp/Cntr=0.3,0.1

Type RM Length L Ch R = 1 ,8777    ,753,753,753
BEGIN DESCRIPTION:
LAKE CREEK TRIBUTARY NO. 11. 2 13.0
END DESCRIPTION:
XS GIS Cut Line= 4
      3772989.24     10093035.96      3772865.81     10092791.62
      3772610.11     10092751.66      3772078.86     10092777.71
#Sta/Elev= 30
       0   198.1    27.9  197.53    34.9  198.02    62.8  197.48   117.5  197.67
   139.9  196.85   196.6  197.29   281.8  195.88   362.8  195.83   371.1  196.31
   403.3  194.98     444   194.9   484.2  192.95   501.7   190.3   506.8  190.22
   514.6  189.52   531.2  184.99   536.2  184.99   554.8  189.26   564.8  190.56
   584.9  191.24   604.9  190.88     705  191.96     725  191.41   775.1   193.6
   785.1  192.98   823.5  194.67   855.2  194.68   895.2  196.51  1062.4   198.8
#Mann= 3 ,-1 , 0
       0     .17       0   506.8     .09       0   564.8     .17       0
Bank Sta=506.8,564.8
XS Rating Curve= 0 ,0
Exp/Cntr=0.3,0.1

Type RM Length L Ch R = 1 ,8024    ,342,342,342
BEGIN DESCRIPTION:
LAKE CREEK TRIBUTARY NO. 11. 2 12.0
END DESCRIPTION:
XS GIS Cut Line= 4
       3773013.2     10092712.54      3772838.13     10092333.31
      3772218.23     10092206.84      3771797.61     10092277.71
#Sta/Elev= 30
       0  196.34   101.3  194.81   330.7  193.93   387.6  195.25   416.2  193.48
   448.6  194.51   554.9  192.54   701.3  193.76   775.2   192.7   826.2  191.17
   852.9  189.14   877.3  189.61   938.5  186.98   999.4  187.53  1040.5  184.68
    1048  183.05  1053.1  183.05  1060.9  185.76    1071  187.28  1101.1  187.69
  1111.6  189.54  1182.6  189.87  1233.3  187.43  1253.6  191.45  1287.8  192.24
  1294.1  193.56  1314.4  193.17  1324.6  194.73  1348.3  193.55  1476.9  198.45
#Mann= 3 ,-1 , 0
       0     .17       0   999.4     .09       0    1071     .17       0
Bank Sta=999.4,1071
XS Rating Curve= 0 ,0
Exp/Cntr=0.3,0.1

Type RM Length L Ch R = 1 ,7682    ,578,578,578
BEGIN DESCRIPTION:
LAKE CREEK TRIBUTARY NO. 11. 2 11.0
END DESCRIPTION:
XS GIS Cut Line= 3
      3772567.81     10092061.06      3772202.13     10091907.91
       3771917.8     10091911.07
#Sta/Elev= 30
    4621  193.06  4630.1  193.72  4635.6  192.32  4688.6  192.97  4718.5  191.11
  4741.5  191.89  4759.9  191.43  4765.3  191.86  4789.1  190.14  4848.6  190.23
  4889.7  188.22  4913.5  188.45  4924.5  187.39  4948.1  187.03  4971.9  185.81
  4989.6  183.98  4993.7  181.67  4993.9  181.17  4997.4  181.17  4997.7  181.67
  5017.1  184.74  5022.1  184.74  5031.7  185.91  5081.7  184.15  5101.7  184.38
  5121.7  185.17  5161.7  188.05  5181.7  188.31  5271.7  192.46  5301.8  192.46
#Mann= 3 , 0 , 0
    4621     .17       0  4971.9     .09       0  5031.7     .17       0
Bank Sta=4971.9,5031.7
XS Rating Curve= 0 ,0
Exp/Cntr=0.3,0.1

Type RM Length L Ch R = 1 ,7104    ,506,506,506
BEGIN DESCRIPTION:
LAKE CREEK TRIBUTARY NO. 11. 2 10.0
END DESCRIPTION:
XS GIS Cut Line= 3
      3772967.83     10092011.05      3772264.63     10091338.47
      3771661.66     10091664.21
#Sta/Elev= 30
  3920.1  192.85  3955.5   193.5  3990.7  191.94  4103.9  190.97  4125.3  192.09
  4132.2  190.76  4160.5  191.55  4273.7   190.7    4309  190.35  4316.2   189.3
  4436.3  189.65  4457.7  190.59  4528.5   189.6  4556.6  190.23    4592  187.97
  4655.5  186.45  4662.8  187.25  4719.4  185.65  4867.8  184.98  4989.7  182.55
  4995.4  182.32  5001.4  179.28  5025.9  182.63    5121  182.09    5181  183.21
  5321.4  188.26  5394.2  192.01  5410.4  191.36  5459.8  192.54  5578.5  196.62
#Mann= 3 , 0 , 0
  3920.1     .17       0  4989.7     .09       0  5025.9     .17       0
Bank Sta=4989.7,5025.9
XS Rating Curve= 0 ,0
Exp/Cntr=0.3,0.1

Type RM Length L Ch R = 1 ,6598    ,957,957,957
BEGIN DESCRIPTION:
LAKE CREEK TRIBUTARY NO. 11. 2 9.0
END DESCRIPTION:
XS GIS Cut Line= 3
      3772993.83     10091442.65      3772084.11     10091015.29
      3771481.33     10091053.66
#Sta/Elev= 30
  3994.9  188.77  4265.1   188.2  4344.6  186.23  4377.2  187.28    4413  186.26
  4481.4  187.95    4527  187.01  4549.9  187.93  4595.5  187.79  4609.2   186.6
  4708.6  187.23    4715  186.09  4720.6  186.64  4737.8  185.31  4774.9  184.55
  4829.1  181.14  4908.5  179.16  4962.7  180.92    4977  180.22  4984.8  179.48
  4992.5  176.72    4996  176.72  5006.3  180.11  5116.5  182.15  5216.7  186.27
  5276.8  186.88  5324.5  188.79  5329.5  187.92  5527.3  190.13    5604  192.35
#Mann= 3 , 0 , 0
  3994.9     .17       0    4977     .09       0  5006.3     .17       0
Bank Sta=4977,5006.3
XS Rating Curve= 0 ,0
Exp/Cntr=0.3,0.1

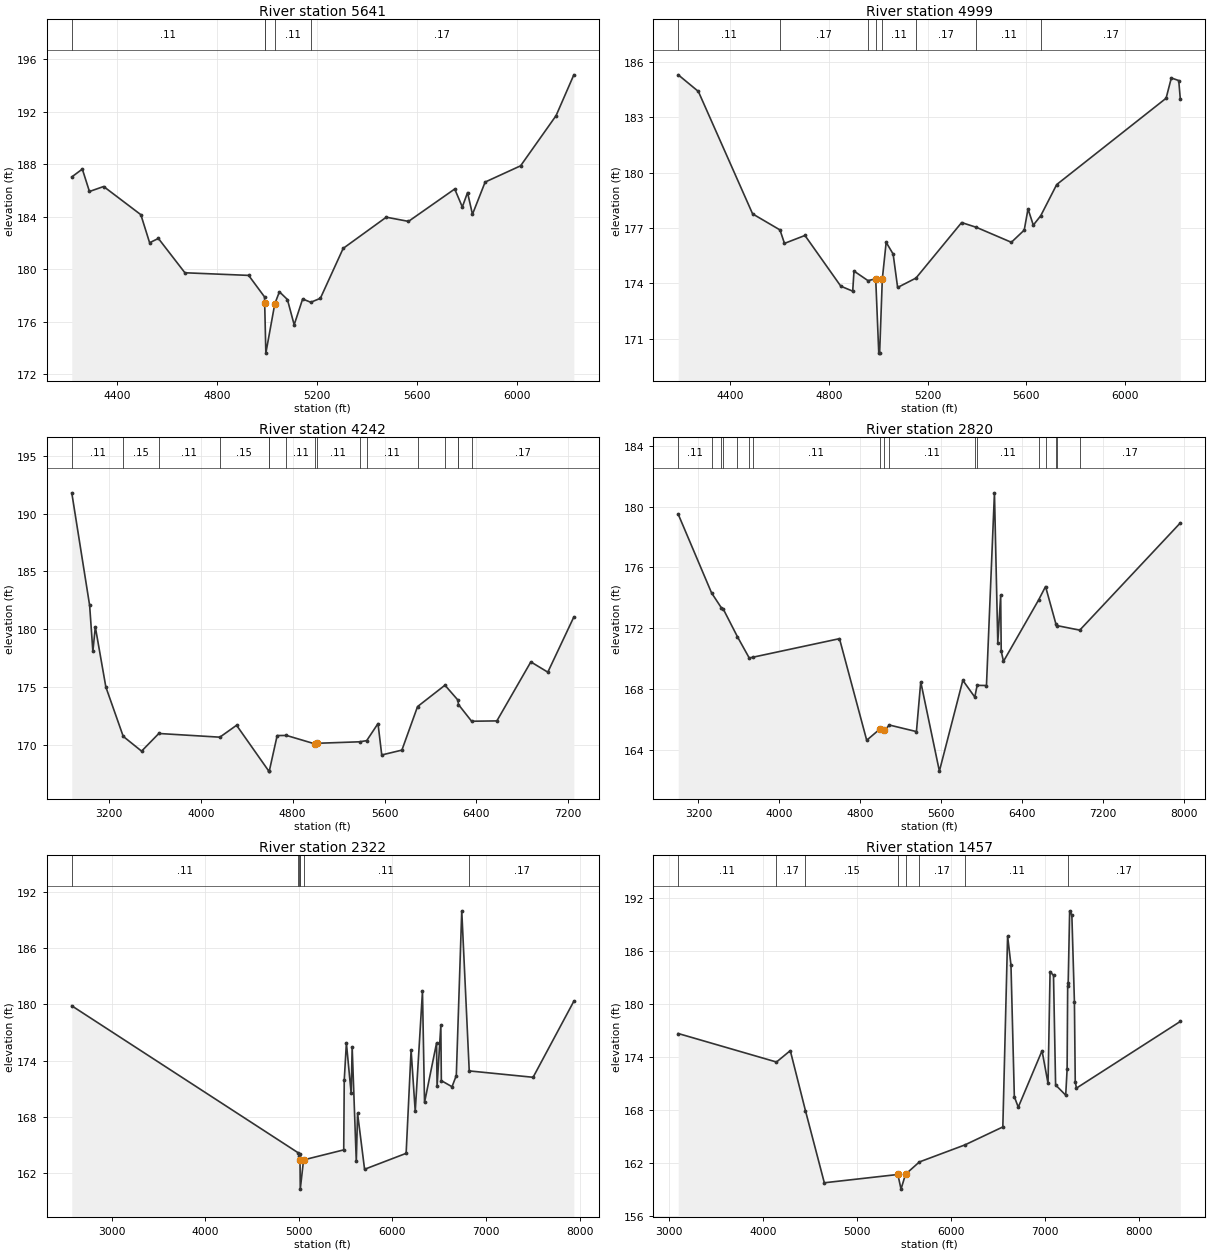
Type RM Length L Ch R = 1 ,5641    ,642,642,642
BEGIN DESCRIPTION:
LAKE CREEK TRIBUTARY NO. 11. 2 8.0
END DESCRIPTION:
XS GIS Cut Line= 3
      3772917.88      10090911.1      3772328.23     10090396.84
      3771117.84     10090611.07
#Sta/Elev= 30
  4217.6  187.04  4259.9  187.64  4288.4  185.93  4345.3  186.31  4494.4  184.16
  4529.5  182.02  4564.6  182.35  4670.9  179.73  4926.3  179.53  4989.9  177.89
 4990.55177.3974  4995.2   173.6  5030.9  177.35  5049.5  178.28  5081.6  177.69
  5108.7  175.76  5142.6  177.73  5175.2  177.48  5213.6  177.78    5305  181.59
  5477.7  183.97  5566.7  183.65  5751.9  186.12  5782.4  184.75  5803.3  185.85
    5823  184.19  5873.8  186.65  6015.9  187.89  6158.1  191.72  6229.2  194.83
#Mann= 5 ,-1 , 0
  4217.6     .11       0  4989.9     .08       0 4990.55     .06       0
  5030.9     .11       0  5175.2     .17       0
Bank Sta=4990.55,5030.9
XS Rating Curve= 0 ,0
Exp/Cntr=0.3,0.1

Type RM Length L Ch R = 1 ,4999    ,757,757,757
BEGIN DESCRIPTION:
LAKE CREEK TRIBUTARY NO. 11. 2 7.0
END DESCRIPTION:
XS GIS Cut Line= 4
      3772854.56     10090695.92      3772658.82     10089998.59
      3772540.56     10089880.32      3771562.37     10090475.39
#Sta/Elev= 30
  4188.4  185.31    4270  184.41  4490.1  177.77  4601.1   176.9  4619.3  176.17
  4702.4   176.6  4847.8  173.85  4896.1  173.58  4901.3  174.67  4958.1  174.15
  4989.4  174.25  5001.8  170.22  5005.3  170.22 5016.13174.2334  5031.8  176.23
  5060.1  175.59  5078.3  173.78  5152.7  174.29  5337.9   177.3    5398  177.04
  5539.6  176.23  5591.8  176.89  5607.2  178.04  5628.6  177.16  5658.8  177.67
  5723.5  179.36  6167.2  184.04  6188.5  185.14  6218.5     185  6224.9     184
#Mann= 8 ,-1 , 0
  4188.4     .11       0  4601.1     .17       0  4958.1     .11       0
  4989.4     .07       0 5016.13     .11       0  5152.7     .17       0
    5398     .11       0  5658.8     .17       0
Bank Sta=4989.4,5016.13
XS Rating Curve= 0 ,0
Exp/Cntr=0.3,0.1

Type RM Length L Ch R = 1 ,4242    ,1422,1422,1422
BEGIN DESCRIPTION:
LAKE CREEK TRIBUTARY NO. 11. 2 6.0
END DESCRIPTION:
XS GIS Cut Line= 4
      3774517.87     10091011.09      3773008.23     10089516.84
      3772769.84     10089177.46      3771152.51     10090042.74
#Sta/Elev= 30
  2875.9  191.81  3031.5  182.06  3059.7  178.08    3081   180.2  3172.9  174.99
  3324.1  170.72    3484  169.44  3634.2  170.97  4165.7  170.65  4311.3  171.68
  4592.2  167.71  4596.2  167.71  4664.9  170.79  4745.9   170.8  4990.2  170.08
 5009.94  170.12  5383.1  170.25  5444.7  170.35  5543.2  171.83  5575.8  169.11
  5751.3  169.53  5887.7   173.3  6126.4  175.15  6238.6  173.87  6244.3  173.47
  6358.6  172.03  6578.6  172.06  6874.4  177.17  7022.3  176.28    7249  181.06
#Mann= 16 ,-1 , 0
  2875.9     .11       0  3324.1     .15       0  3634.2     .11       0
  4165.7     .15       0  4592.2     .11       0  4596.2     .15       0
  4745.9     .11       0  4990.2     .07       0 5009.94     .11       0
  5383.1     .15       0  5444.7     .11       0  5887.7     .17       0
  6126.4     .11       0  6238.6     .17       0  6244.3     .11       0
  6358.6     .17       0
Bank Sta=4990.2,5009.94
XS Rating Curve= 0 ,0
Exp/Cntr=0.3,0.1

Type RM Length L Ch R = 1 ,2820    ,498,498,498
BEGIN DESCRIPTION:
LAKE CREEK TRIBUTARY NO. 11. 2 5.0
END DESCRIPTION:
XS GIS Cut Line= 4
      3775117.88      10090161.1      3773638.23     10088816.84
      3773267.85     10088761.07      3770956.91     10089923.54
#Sta/Elev= 30
  3000.9   179.5  3330.2  174.33  3426.9  173.35  3444.8  173.28  3585.6  171.45
  3702.4  170.05  3738.3   170.1    4594  171.32    4863  164.64  4990.3  165.36
    5038   165.3  5087.8  165.64  5354.3  165.21  5396.9  168.48  5581.1  162.61
  5812.6  168.58  5930.8  167.48  5954.3  168.25  6046.2  168.24  6125.1  180.91
  6158.1  171.06  6186.5  174.18    6192   170.5  6214.4  169.83  6561.8  173.87
  6629.9  174.75  6733.5  172.26  6742.5  172.18  6967.8  171.88  7961.4  178.93
#Mann= 17 ,-1 , 0
  3000.9     .11       0  3330.2     .15       0  3426.9     .11       0
  3444.8     .15       0  3585.6     .11       0  3702.4     .17       0
  3738.3     .11       0  4990.3     .09       0    5038     .15       0
  5087.8     .11       0  5930.8     .15       0  5954.3     .11       0
  6561.8     .17       0  6629.9     .11       0  6733.5     .17       0
  6742.5     .11       0  6967.8     .17       0
Bank Sta=4990.3,5038
XS Rating Curve= 0 ,0
Exp/Cntr=0.3,0.1

Type RM Length L Ch R = 1 ,2322    ,865,865,865
BEGIN DESCRIPTION:
LAKE CREEK TRIBUTARY NO. 11. 2 4.0
END DESCRIPTION:
XS GIS Cut Line= 3
      3775517.86     10089961.07      3773703.64     10088350.91
      3771043.68     10089598.03
#Sta/Elev= 30
  2574.3  179.84  4995.9  164.13  5005.7  163.82    5012  163.97  5012.5163.3985
  5015.3  160.27  5050.6  163.39  5479.5  164.46  5485.1   171.9  5507.9  175.87
  5559.1  170.49  5569.7  175.43  5613.8  163.22  5627.5  168.36  5702.2  162.39
  6146.2  164.09  6199.2  175.12  6243.4  168.56  6320.7  181.39  6342.8  169.52
  6471.2  175.87  6476.8  171.26  6516.9  177.75  6522.4  171.85  6636.5   171.2
  6682.2   172.4  6740.4  189.98  6820.3  172.89  7502.5  172.21  7937.8  180.33
#Mann= 7 ,-1 , 0
  2574.3     .11       0  4995.9     .15       0  5005.7     .11       0
    5012     .12       0  5012.5     .09       0  5050.6     .11       0
  6820.3     .17       0
Bank Sta=5012.5,5050.6
XS Rating Curve= 0 ,0
Exp/Cntr=0.3,0.1

Type RM Length L Ch R = 1 ,1457    ,691,691,691
BEGIN DESCRIPTION:
LAKE CREEK TRIBUTARY NO. 11. 2 2.0
END DESCRIPTION:
XS GIS Cut Line= 3
      3774967.84     10088961.06      3773712.44     10087538.89
       3770892.3     10089500.02
#Sta/Elev= 30
    3103  176.63  4146.3   173.4    4293  174.69  4454.1  167.88  4654.4  159.71
  5435.5  160.65    5469  158.99 5516.77160.6738  5663.7  162.07  6146.8     164
  6550.2  166.04  6600.8  187.68  6636.6   184.4  6672.4  169.46  6714.2  168.28
  6966.6  174.68  7030.2  170.97  7051.9  183.65  7088.4  183.21  7110.6   170.8
  7217.9  169.64  7232.8  172.56  7238.8  182.02  7244.4   182.4  7259.8  190.54
  7283.3  190.04  7310.4  180.23  7319.2  171.16    7332  170.44    8435     178
#Mann= 8 ,-1 , 0
    3103     .11       0  4146.3     .17       0  4454.1     .15       0
  5435.5     .09       0 5516.77     .15       0  5663.7     .17       0
  6146.8     .11       0  7244.4     .17       0
Bank Sta=5435.5,5516.77
XS Rating Curve= 0 ,0
Exp/Cntr=0.3,0.1

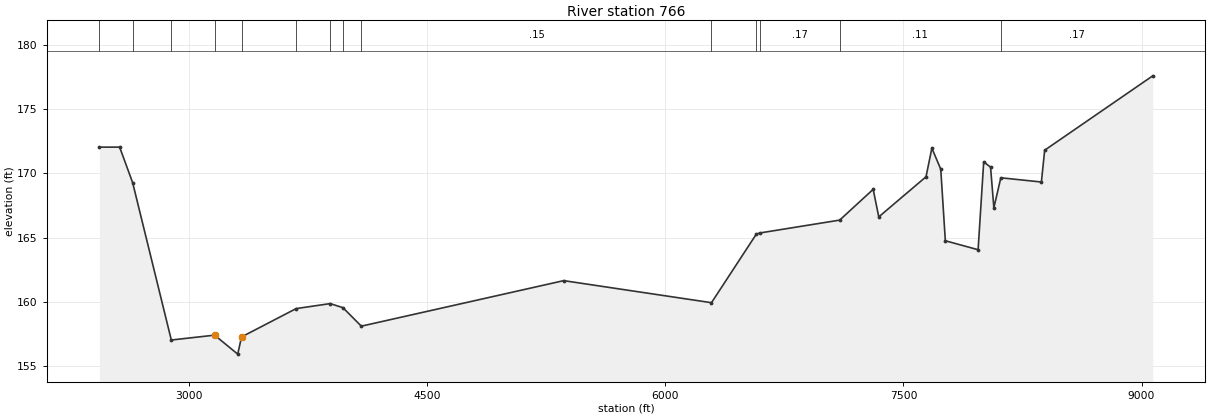
Type RM Length L Ch R = 1 ,766     ,0,0,0
BEGIN DESCRIPTION:
LAKE CREEK TRIBUTARY NO. 11. 2 1.0
END DESCRIPTION:
XS GIS Cut Line= 3
      3775817.84     10088461.06      3773811.43     10086860.19
      3770632.08     10089402.15
#Sta/Elev= 30
  2433.2  172.05  2561.1  172.05  2643.1  169.28  2886.7  157.01  3159.4  157.39
  3305.2  155.91  3329.1  157.25  3673.1  159.46  3887.9  159.85  3968.3  159.53
    4084  158.09  5359.2  161.64  6290.2  159.92    6573  165.27  6596.3  165.36
    7098  166.36  7309.1  168.76  7344.3  166.61  7642.1  169.74  7678.9  171.97
  7734.9  170.33  7763.7  164.75  7970.2  164.05  8005.5   170.9  8048.7  170.49
  8069.5  167.32  8113.4  169.66  8368.9  169.33  8389.7  171.81  9070.6  177.61
#Mann= 14 ,-1 , 0
  2433.2     .11       0  2643.1     .17       0  2886.7     .15       0
  3159.4     .09       0  3329.1     .15       0  3673.1     .17       0
  3887.9     .15       0  3968.3     .17       0    4084     .15       0
  6290.2     .17       0    6573     .11       0  6596.3     .17       0
    7098     .11       0  8113.4     .17       0
Bank Sta=3159.4,3329.1
XS Rating Curve= 0 ,0
Exp/Cntr=0.3,0.1

Chan Stop Cuts=-1
Use User Specified Reach Order=0
Composite Channel Slope=5