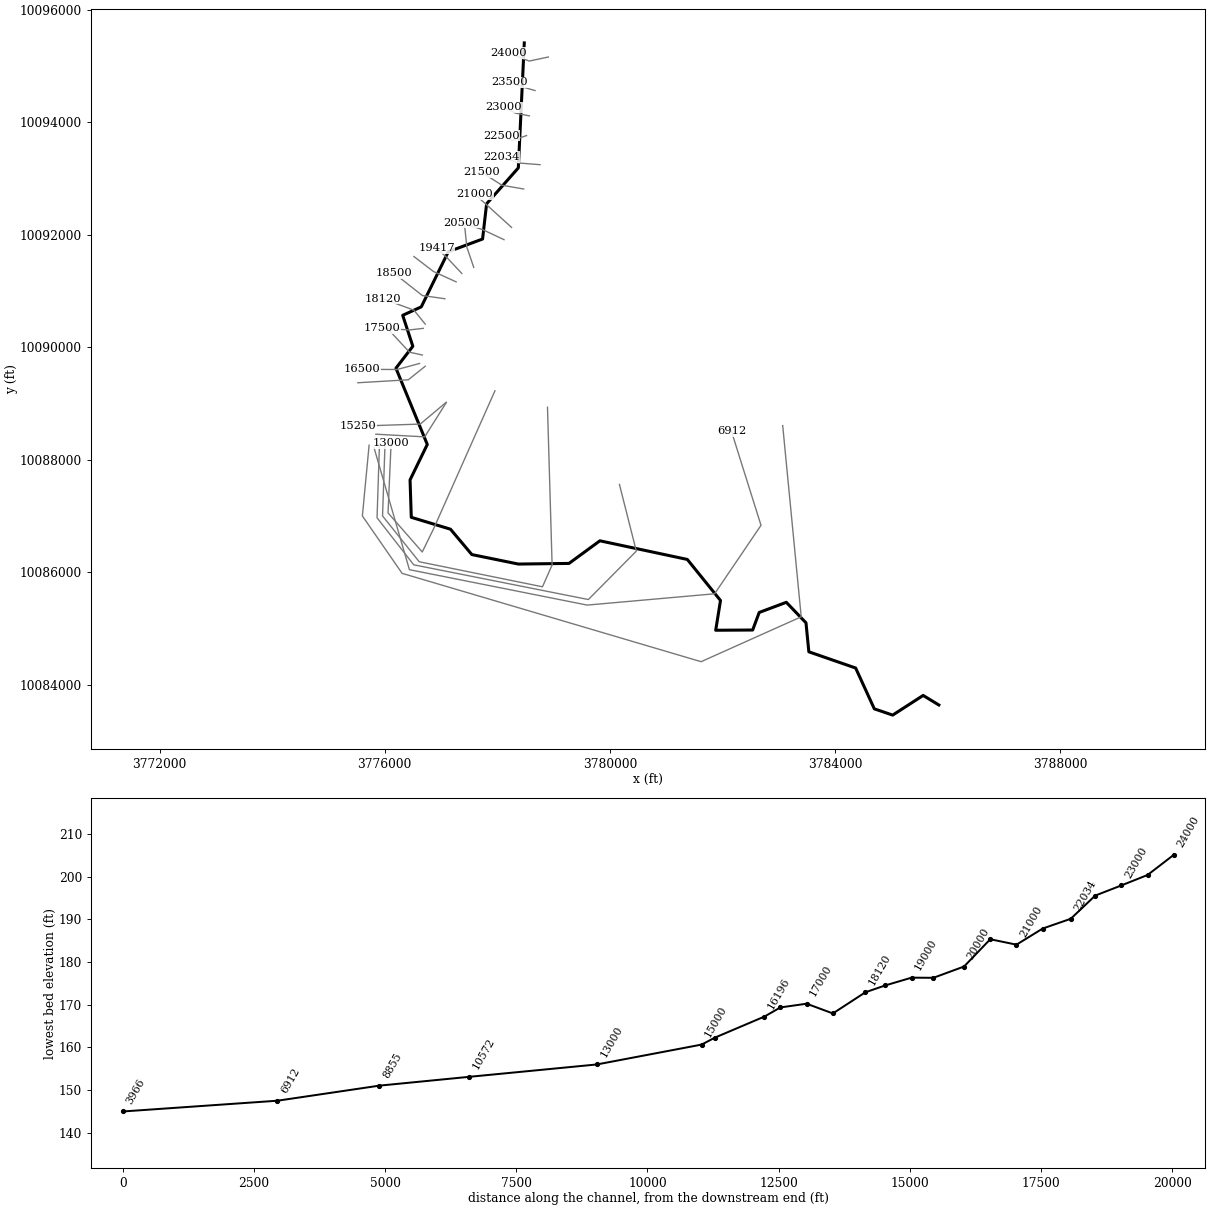
--- LAKE CREEK TRIBUTARY NO 11.prj (project) ---

Proj Title=LAKE CREEK TRIBUTARY NO 11 Base Level Engineering
Current Plan=p01
Default Exp/Contr=0.3,0.1
English Units
Geom File=g01
Flow File=f01
Flow File=f02
Plan File=p01
Y Axis Title=Elevation
X Axis Title(PF)=Main Channel Distance
X Axis Title(XS)=Station
BEGIN DESCRIPTION:
LAKE CREEK TRIBUTARY NO 11
END DESCRIPTION:
DSS Export Rating Curves= 0
DSS Export Rating Curve Sorted= 0
DSS Export Volume Flow Curves= 0
DXF OffsetX= 0
DXF OffsetY= 0
DXF ScaleX= 1
DXF ScaleY= 10

--- LAKE CREEK TRIBUTARY NO 11.p01 (plan) ---

Plan Title=Multiple Run
Short Identifier=Multiple
Geom File=g01
Flow File=f01
Subcritical Flow
K Sum by GR= 0
Std Step Tol= 0.01
Critical Tol= 0.01
Num of Std Step Trials= 20
Max Error Tol= 0.3
Flow Tol Ratio= 0.001
Split Flow NTrial= 30
Split Flow Tol= 0.02
Split Flow Ratio= 0.02
Log Output Level= 0
Friction Slope Method= 1
Unsteady Friction Slope Method= 2
Unsteady Bridges Friction Slope Method= 1
Parabolic Critical Depth
Global Vel Dist=  1 , 1 , 1
Global Log Level= 0
CheckData=True
Encroach Param= -1, 0, 0, 0
BEGIN DESCRIPTION:
Multiple Run
END DESCRIPTION:

--- LAKE CREEK TRIBUTARY NO 11.f01 (steady flow) ---

Flow Title=Multiple
Program Version=4.10
Number of Profiles= 7
Profile Names=10-year,25-year,50-year,1pct_min,100-year,1pct_plu,500-year
River Rch & RM=LAKE CREEK TRIBU,Reach-1         ,24000
     797    1093    1492     669    2020    6100    3836
River Rch & RM=LAKE CREEK TRIBU,Reach-1         ,20000
    1041    1434    1960     878    2653    8012    5034
River Rch & RM=LAKE CREEK TRIBU,Reach-1         ,6912
    1343    1870    2573    1160    3504   10582    6725
Boundary for River Rch & Prof#=LAKE CREEK TRIBU,Reach-1         , 1
Up Type= 0
Dn Type= 3
Dn Slope=0.005
Boundary for River Rch & Prof#=LAKE CREEK TRIBU,Reach-1         , 2
Up Type= 0
Dn Type= 3
Dn Slope=0.005
Boundary for River Rch & Prof#=LAKE CREEK TRIBU,Reach-1         , 3
Up Type= 0
Dn Type= 3
Dn Slope=0.005
Boundary for River Rch & Prof#=LAKE CREEK TRIBU,Reach-1         , 4
Up Type= 0
Dn Type= 3
Dn Slope=0.005
Boundary for River Rch & Prof#=LAKE CREEK TRIBU,Reach-1         , 5
Up Type= 0
Dn Type= 3
Dn Slope=0.005
Boundary for River Rch & Prof#=LAKE CREEK TRIBU,Reach-1         , 6
Up Type= 0
Dn Type= 3
Dn Slope=0.005
Boundary for River Rch & Prof#=LAKE CREEK TRIBU,Reach-1         , 7
Up Type= 0
Dn Type= 3
Dn Slope=0.005
DSS Import GetInterval= 0
DSS Import GetPeak= 0
DSS Import FillOption= 0

--- LAKE CREEK TRIBUTARY NO 11.f02 (steady flow) ---

Flow Title=Orig_BLE_Flows
Program Version=4.10
Number of Profiles= 7
Profile Names=10-year,25-year,50-year,1pct_min,100-year,1pct_plu,500-year
River Rch & RM=LAKE CREEK TRIBU,Reach-1         ,24000
     797    1072    1297     515    1554    4694    2230
River Rch & RM=LAKE CREEK TRIBU,Reach-1         ,20000
    1041    1406    1704     676    2041    6165    2927
River Rch & RM=LAKE CREEK TRIBU,Reach-1         ,6912
    1343    1833    2237     892    2695    8138    3910
Boundary for River Rch & Prof#=LAKE CREEK TRIBU,Reach-1         , 1
Up Type= 0
Dn Type= 3
Dn Slope=0.005
Boundary for River Rch & Prof#=LAKE CREEK TRIBU,Reach-1         , 2
Up Type= 0
Dn Type= 3
Dn Slope=0.005
Boundary for River Rch & Prof#=LAKE CREEK TRIBU,Reach-1         , 3
Up Type= 0
Dn Type= 3
Dn Slope=0.005
Boundary for River Rch & Prof#=LAKE CREEK TRIBU,Reach-1         , 4
Up Type= 0
Dn Type= 3
Dn Slope=0.005
Boundary for River Rch & Prof#=LAKE CREEK TRIBU,Reach-1         , 5
Up Type= 0
Dn Type= 3
Dn Slope=0.005
Boundary for River Rch & Prof#=LAKE CREEK TRIBU,Reach-1         , 6
Up Type= 0
Dn Type= 3
Dn Slope=0.005
Boundary for River Rch & Prof#=LAKE CREEK TRIBU,Reach-1         , 7
Up Type= 0
Dn Type= 3
Dn Slope=0.005
DSS Import GetInterval= 0
DSS Import GetPeak= 0
DSS Import FillOption= 0

--- LAKE CREEK TRIBUTARY NO 11.g01 (geometry) ---

Geom Title=Existing Conditions
Program Version=4.10

River Reach=LAKE CREEK TRIBU,Reach-1
Reach XY= 30
      3778477.72     10095407.39      3778371.98      10093186.7
       3777808.6      10092548.7      3777736.98     10091922.62
      3777128.23     10091696.84      3776648.23     10090716.84
      3776318.23     10090566.84      3776498.23     10090016.84
      3776198.23     10089626.84      3776754.99     10088271.36
        3776449.     10087642.02      3776470.71     10086976.87
      3777166.96      10086765.7       3777546.3     10086314.74
      3778372.69     10086146.14      3779271.74     10086157.47
      3779820.87     10086559.44      3781373.64     10086228.09
      3781962.74     10085498.96      3781877.68     10084969.89
       3782534.1     10084973.94      3782650.32     10085285.99
      3783131.84     10085466.45      3783481.13     10085101.56
       3783531.9     10084586.77      3784363.34     10084298.42
      3784694.66     10083573.23      3785020.99     10083461.91
      3785562.11      10083811.4      3785840.96     10083641.56

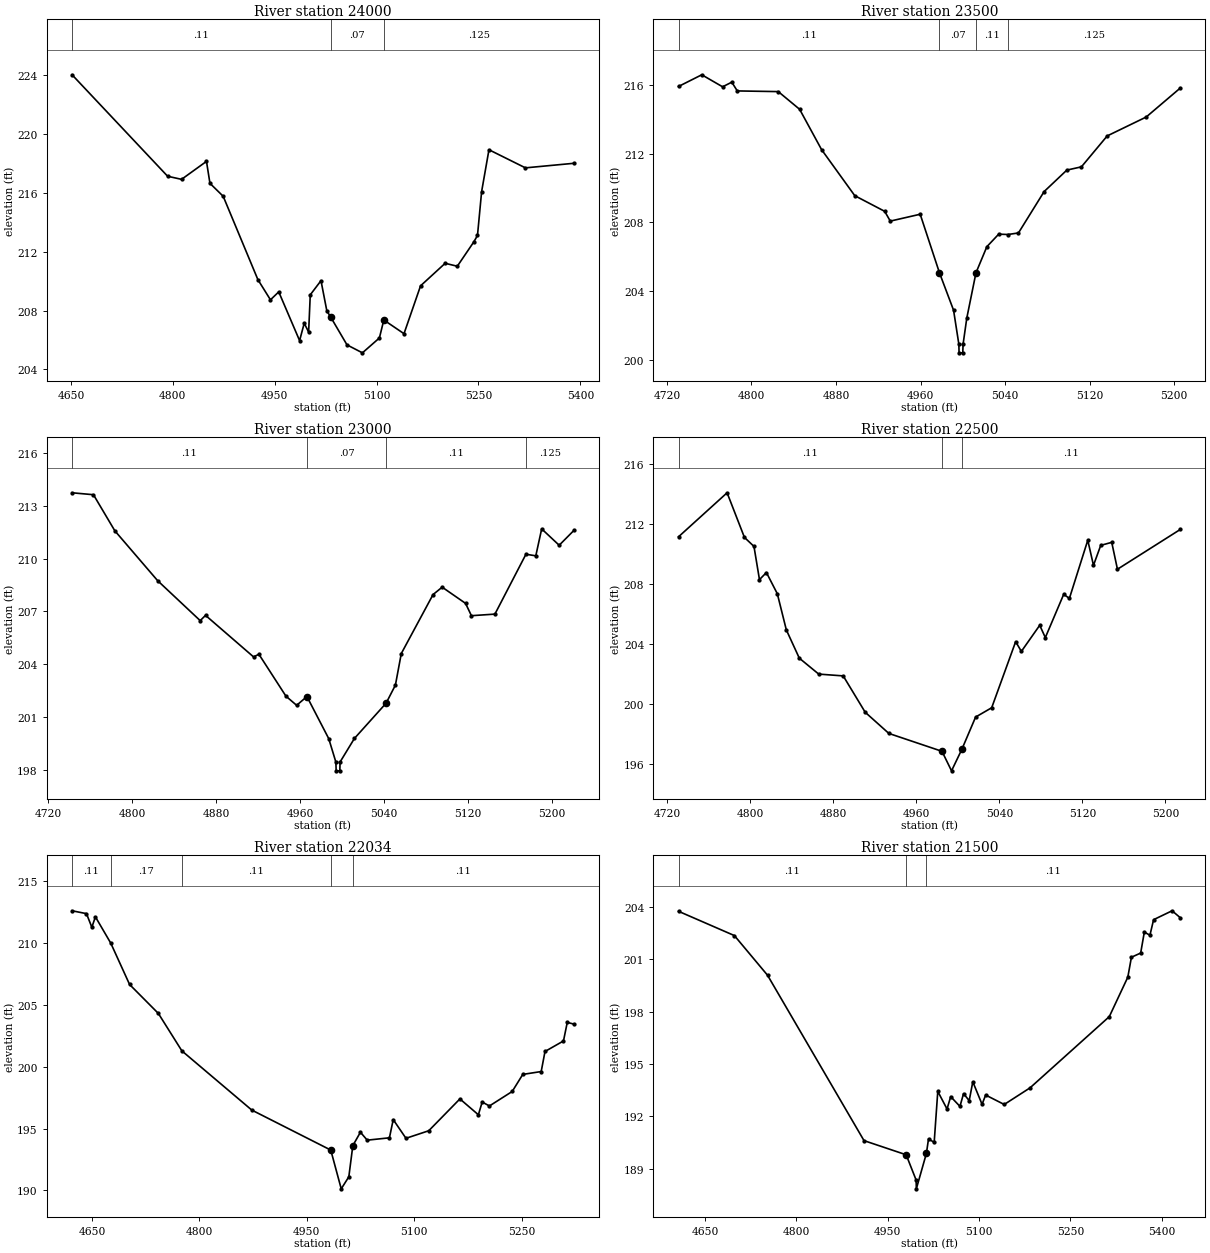
Type RM Length L Ch R = 1 ,24000   ,500,500,500
BEGIN DESCRIPTION:
LAKE CREEK TRIBUTARY NO. 11 48.0
END DESCRIPTION:
XS GIS Cut Line= 3
      3778905.53     10095157.33      3778564.81     10095085.07
      3778201.57     10095228.43
#Sta/Elev= 30
  4651.7  224.01  4792.4  217.12  4812.9  216.91  4849.6  218.13  4854.7  216.64
  4874.2  215.76  4925.3   210.1  4943.8  208.73    4956  209.27  4986.7  205.96
  4993.5  207.14    5000  206.54  5002.4  209.07  5018.2  210.03  5026.8  207.98
  5032.2  207.58  5056.5  205.67  5079.2  205.13  5104.2  206.14  5110.7  207.36
  5140.4  206.43  5164.8  209.68    5201  211.21  5218.9  211.01  5243.3  212.67
  5248.6   213.1  5254.7  216.08  5265.5  218.92  5319.2  217.69  5390.5     218
#Mann= 3 , 0 , 0
  4651.7     .11       0  5032.2     .07       0  5110.7    .125       0
Bank Sta=5032.2,5110.7
XS Rating Curve= 0 ,0
Exp/Cntr=0.3,0.1

Type RM Length L Ch R = 1 ,23500   ,500,500,500
BEGIN DESCRIPTION:
LAKE CREEK TRIBUTARY NO. 11 47.0
END DESCRIPTION:
XS GIS Cut Line= 3
      3778667.89     10094561.06      3778409.52     10094635.93
      3778217.82     10094711.08
#Sta/Elev= 30
    4731  215.91    4753  216.59  4772.7  215.89  4781.4  216.16  4786.6  215.65
  4825.4  215.61  4845.6  214.58  4866.4  212.23  4897.8  209.55  4926.1  208.64
  4931.4  208.07  4959.7  208.47 4977.97205.0562  4991.3  202.88  4996.3   200.9
  4996.5   200.4    5000   200.4  5000.3   200.9  5003.8  202.42  5012.5  205.06
  5022.8  206.58    5034  207.31  5042.7  207.29  5052.7  207.38    5077  209.79
  5098.5  211.04  5112.3  211.23  5136.7  213.03  5173.6  214.13  5205.9  215.82
#Mann= 4 ,-1 , 0
    4731     .11       0 4977.97     .07       0  5012.5     .11       0
  5042.7    .125       0
Bank Sta=4977.97,5012.5
XS Rating Curve= 0 ,0
Exp/Cntr=0.3,0.1

Type RM Length L Ch R = 1 ,23000   ,500,500,500
BEGIN DESCRIPTION:
LAKE CREEK TRIBUTARY NO. 11 46.0
END DESCRIPTION:
XS GIS Cut Line= 3
      3778567.85     10094111.07      3778315.48     10094161.71
      3778117.85     10094261.07
#Sta/Elev= 30
  4742.6  213.74    4763  213.63  4783.4  211.58  4824.2  208.75  4864.8  206.48
  4869.9  206.78  4915.7  204.42  4920.8  204.57  4946.6  202.19  4956.8  201.67
  4966.6  202.17  4987.4  199.78  4994.2  198.45  4994.5  197.95    4998  197.95
  4998.2  198.45  5011.9  199.79  5042.1  201.79    5051  202.82  5056.6  204.61
  5086.9  207.96  5095.6  208.38  5117.9  207.46  5123.5  206.76  5145.9  206.85
  5175.5  210.25  5184.9  210.16  5190.5  211.69  5207.2  210.76  5221.2   211.6
#Mann= 4 ,-1 , 0
  4742.6     .11       0  4966.6     .07       0  5042.1     .11       0
  5175.5    .125       0
Bank Sta=4966.6,5042.1
XS Rating Curve= 0 ,0
Exp/Cntr=0.3,0.1

Type RM Length L Ch R = 1 ,22500   ,466,466,466
BEGIN DESCRIPTION:
LAKE CREEK TRIBUTARY NO. 11 45.0
END DESCRIPTION:
XS GIS Cut Line= 3
      3778517.87     10093761.08      3778263.33     10093673.16
      3778067.88     10093761.06
#Sta/Elev= 30
  4730.7  211.14  4777.5  214.07  4794.2   211.1  4803.4   210.5  4808.7  208.29
  4815.4  208.76  4825.9  207.35  4834.6  204.94  4847.1  203.06  4865.8     202
  4889.4  201.88  4910.6  199.46  4933.4  198.05  4984.6  196.86  4993.8  195.56
  5003.8     197    5017  199.14  5032.5  199.76  5055.6  204.16  5061.1  203.51
  5078.8  205.25  5084.2  204.43  5101.9  207.31  5107.4  207.04  5125.1  210.91
  5130.6  209.24  5137.6  210.57  5148.2  210.77  5153.7  208.98  5214.3  211.63
#Mann= 3 , 0 , 0
  4730.7     .11       0  4984.6     .06       0  5003.8     .11       0
Bank Sta=4984.6,5003.8
XS Rating Curve= 0 ,0
Exp/Cntr=0.3,0.1

Type RM Length L Ch R = 1 ,22034   ,534,534,534
BEGIN DESCRIPTION:
LAKE CREEK TRIBUTARY NO. 11 44.0
END DESCRIPTION:
XS GIS Cut Line= 3
      3778757.93      10093243.7      3778380.37     10093273.66
      3778076.58     10093379.98
#Sta/Elev= 30
  4622.3  212.58  4642.4  212.35  4649.9  211.25  4654.9  212.09  4676.3  209.97
  4702.6  206.63  4742.8  204.29  4775.6  201.27  4873.2  196.49  4983.5  193.26
  4998.1  190.13  5008.7   191.1  5014.3  193.62  5024.9   194.7  5034.4  194.06
  5065.4  194.25  5070.7  195.72  5088.5  194.21  5120.3  194.82  5163.8  197.39
  5189.6  196.11  5194.9  197.14    5205  196.82  5236.8  197.99  5251.6  199.37
  5277.3   199.6  5282.6  201.22  5308.4  202.07  5313.7  203.57  5322.9  203.43
#Mann= 5 ,-1 , 0
  4622.3     .11       0  4676.3     .17       0  4775.6     .11       0
  4983.5     .06       0  5014.3     .11       0
Bank Sta=4983.5,5014.3
XS Rating Curve= 0 ,0
Exp/Cntr=0.3,0.1

Type RM Length L Ch R = 1 ,21500   ,500,500,500
BEGIN DESCRIPTION:
LAKE CREEK TRIBUTARY NO. 11 43.0
END DESCRIPTION:
XS GIS Cut Line= 3
       3778467.8     10092811.08      3778080.29     10092878.91
      3777717.87     10093111.06
#Sta/Elev= 30
  4606.6  203.74  4698.3  202.35  4752.7  200.08  4911.1  190.61  4980.3   189.8
  4996.7  188.35    4997  187.85 5013.52189.8783    5017  190.71  5026.3  190.51
  5032.2  193.43  5047.4  192.42  5053.4  193.13  5068.6  192.57  5074.5   193.3
  5083.8   192.9  5089.7  193.98  5104.9  192.69  5110.8  193.22  5141.3  192.68
  5183.6  193.63  5313.8  197.71  5344.2  199.97  5350.1  201.11  5365.3  201.35
  5371.3  202.55  5380.5  202.37  5386.5  203.26  5416.9  203.77  5430.4  203.37
#Mann= 3 , 0 , 0
  4606.6     .11       0  4980.3     .06       0 5013.52     .11       0
Bank Sta=4980.3,5013.52
XS Rating Curve= 0 ,0
Exp/Cntr=0.3,0.1

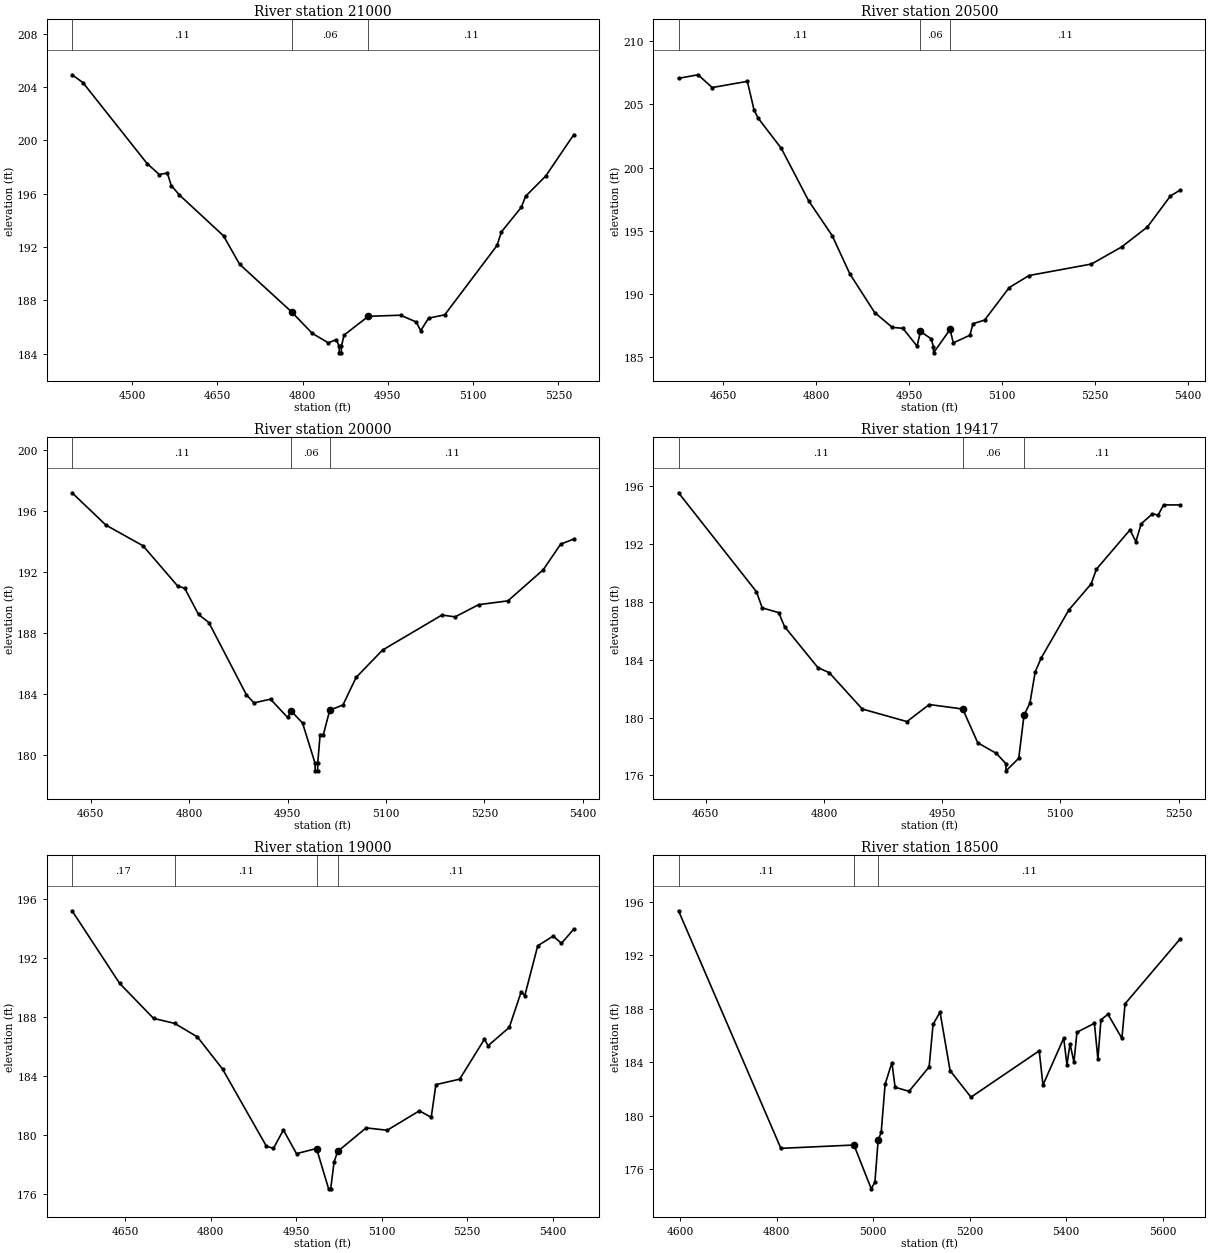
Type RM Length L Ch R = 1 ,21000   ,500,500,500
BEGIN DESCRIPTION:
LAKE CREEK TRIBUTARY NO. 11 42.0
END DESCRIPTION:
XS GIS Cut Line= 3
      3778251.89      10092128.7       3777803.6     10092535.72
      3777595.63     10092718.98
#Sta/Elev= 30
  4394.5  204.91  4413.5  204.33  4526.4  198.26    4548  197.43    4562  197.55
    4569  196.61  4583.1  195.91  4660.9  192.84  4689.2  190.71  4781.1  187.12
    4817  185.53  4845.3  184.82  4859.2  185.06  4864.3  184.57  4864.5  184.07
    4868  184.07  4868.3  184.57    4873   185.4  4915.6  186.81  4972.4  186.89
    5000  186.38  5007.7  185.73  5021.7  186.67  5050.1  186.92  5142.1  192.12
  5149.7  193.13  5184.8  194.98  5192.4  195.81  5227.5  197.31  5277.2  200.43
#Mann= 3 , 0 , 0
  4394.5     .11       0  4781.1     .06       0  4915.6     .11       0
Bank Sta=4781.1,4915.6
XS Rating Curve= 0 ,0
Exp/Cntr=0.3,0.1

Type RM Length L Ch R = 1 ,20500   ,500,500,500
BEGIN DESCRIPTION:
LAKE CREEK TRIBUTARY NO. 11 41.0
END DESCRIPTION:
XS GIS Cut Line= 3
      3778117.88     10091911.06      3777736.08     10092090.36
      3777367.86     10092211.07
#Sta/Elev= 30
  4578.2  207.07  4609.7  207.35  4632.5  206.34  4689.2  206.83  4699.8   204.6
  4706.4  203.93  4743.9  201.53  4788.1  197.37    4826  194.62  4854.4   191.6
  4894.5  188.53  4922.8  187.36  4940.1  187.28  4962.9  185.87  4968.4  187.03
  4985.7  186.45  4989.2  185.84  4989.5  185.34  5016.1  187.19  5021.4  186.13
    5048  186.73  5053.2  187.65  5071.8  187.93  5111.6  190.51  5143.5  191.46
  5244.2  192.37  5292.8  193.72  5334.5  195.31  5371.6  197.76  5387.5  198.23
#Mann= 3 , 0 , 0
  4578.2     .11       0  4968.4     .06       0  5016.1     .11       0
Bank Sta=4968.4,5016.1
XS Rating Curve= 0 ,0
Exp/Cntr=0.3,0.1

Type RM Length L Ch R = 1 ,20000   ,583,583,583
BEGIN DESCRIPTION:
LAKE CREEK TRIBUTARY NO. 11 40.0
END DESCRIPTION:
XS GIS Cut Line= 3
      3777580.01     10091418.66      3777457.97     10091776.84
      3777417.85     10092161.06
#Sta/Elev= 30
  4621.6  197.19  4673.2  195.07  4729.8  193.71  4782.6  191.07  4793.2  190.93
  4814.3  189.21    4830  188.68  4887.4  183.93  4898.8  183.41    4924  183.65
  4950.1  182.45  4955.4  182.88  4972.8  182.09  4991.9  179.45  4992.1  178.95
  4995.7  178.95    4996  179.45  4999.6  181.33  5004.6  181.33  5014.3  182.93
  5034.4  183.27  5054.5  185.08  5094.7  186.87  5185.2  189.17  5205.3  189.05
  5241.2  189.85  5285.8   190.1  5339.6  192.14  5366.2  193.82  5386.3  194.16
#Mann= 3 , 0 , 0
  4621.6     .11       0  4955.4     .06       0  5014.3     .11       0
Bank Sta=4955.4,5014.3
XS Rating Curve= 0 ,0
Exp/Cntr=0.3,0.1

Type RM Length L Ch R = 1 ,19417   ,417,417,417
BEGIN DESCRIPTION:
LAKE CREEK TRIBUTARY NO. 11 39.0
END DESCRIPTION:
XS GIS Cut Line= 3
      3777367.84     10091311.09      3777106.06      10091590.5
      3776917.84     10091761.08
#Sta/Elev= 30
  4615.4  195.56  4714.3  188.71  4721.6  187.59  4742.6  187.26  4749.9   186.3
  4792.4  183.45  4806.6  183.11  4848.6  180.59  4905.3  179.72  4933.6   180.9
  4976.1  180.59  4995.2  178.25  5018.8  177.52  5030.9  176.81  5031.1  176.31
  5047.2  177.18  5053.9  180.16  5061.4     181  5068.1  183.16  5075.6  184.11
  5110.7  187.44  5139.1  189.25  5145.8  190.27  5188.4  192.99  5195.9  192.18
  5202.6  193.41  5216.8   194.1  5224.2  194.02    5231  194.72  5252.3  194.72
#Mann= 3 , 0 , 0
  4615.4     .11       0  4976.1     .06       0  5053.9     .11       0
Bank Sta=4976.1,5053.9
XS Rating Curve= 0 ,0
Exp/Cntr=0.3,0.1

Type RM Length L Ch R = 1 ,19000   ,500,500,500
BEGIN DESCRIPTION:
LAKE CREEK TRIBUTARY NO. 11 38.0
END DESCRIPTION:
XS GIS Cut Line= 3
      3777267.86     10091161.07      3776864.99     10091345.05
      3776517.89     10091611.05
#Sta/Elev= 30
  4557.1  195.23  4640.5   190.3    4700  187.92    4737  187.58    4777  186.66
    4821  184.48  4897.9  179.24  4910.3  179.09  4927.8  180.34  4950.8  178.73
  4985.9  179.08  5007.1  176.34  5010.8  176.34  5016.7  178.17    5023  178.88
  5072.9  180.48  5109.8  180.32  5166.3  181.64  5187.1   181.2  5195.3  183.42
    5237  183.79  5280.5  186.51  5286.8  186.06    5324  187.31  5344.9  189.72
  5351.2  189.46  5373.9  192.85    5401  193.51  5415.6  193.02  5437.3  193.99
#Mann= 4 ,-1 , 0
  4557.1     .17       0    4737     .11       0  4985.9     .06       0
    5023     .11       0
Bank Sta=4985.9,5023
XS Rating Curve= 0 ,0
Exp/Cntr=0.3,0.1

Type RM Length L Ch R = 1 ,18500   ,380,380,380
BEGIN DESCRIPTION:
LAKE CREEK TRIBUTARY NO. 11 37.0
END DESCRIPTION:
XS GIS Cut Line= 3
      3777067.81     10090861.08      3776668.23     10090917.88
      3776167.84     10091311.08
#Sta/Elev= 30
  4596.4  195.34  4808.5  177.56    4960  177.81  4995.8  174.53  5003.4  175.03
  5010.1  178.18  5016.4  178.75  5024.5  182.35  5038.6  183.98  5045.3  182.13
  5074.2  181.83  5115.8  183.66  5123.9  186.84  5138.4  187.75  5159.2  183.38
  5202.5  181.39  5343.9  184.86  5351.7   182.3  5394.7  185.81  5401.4  183.82
  5407.8  185.38  5415.9  184.02  5422.2  186.25  5458.3  186.92  5465.6  184.24
  5471.9  187.18  5486.4   187.6  5515.3  185.79  5521.9  188.38  5636.4  193.25
#Mann= 3 , 0 , 0
  4596.4     .11       0    4960     .06       0  5010.1     .11       0
Bank Sta=4960,5010.1
XS Rating Curve= 0 ,0
Exp/Cntr=0.3,0.1

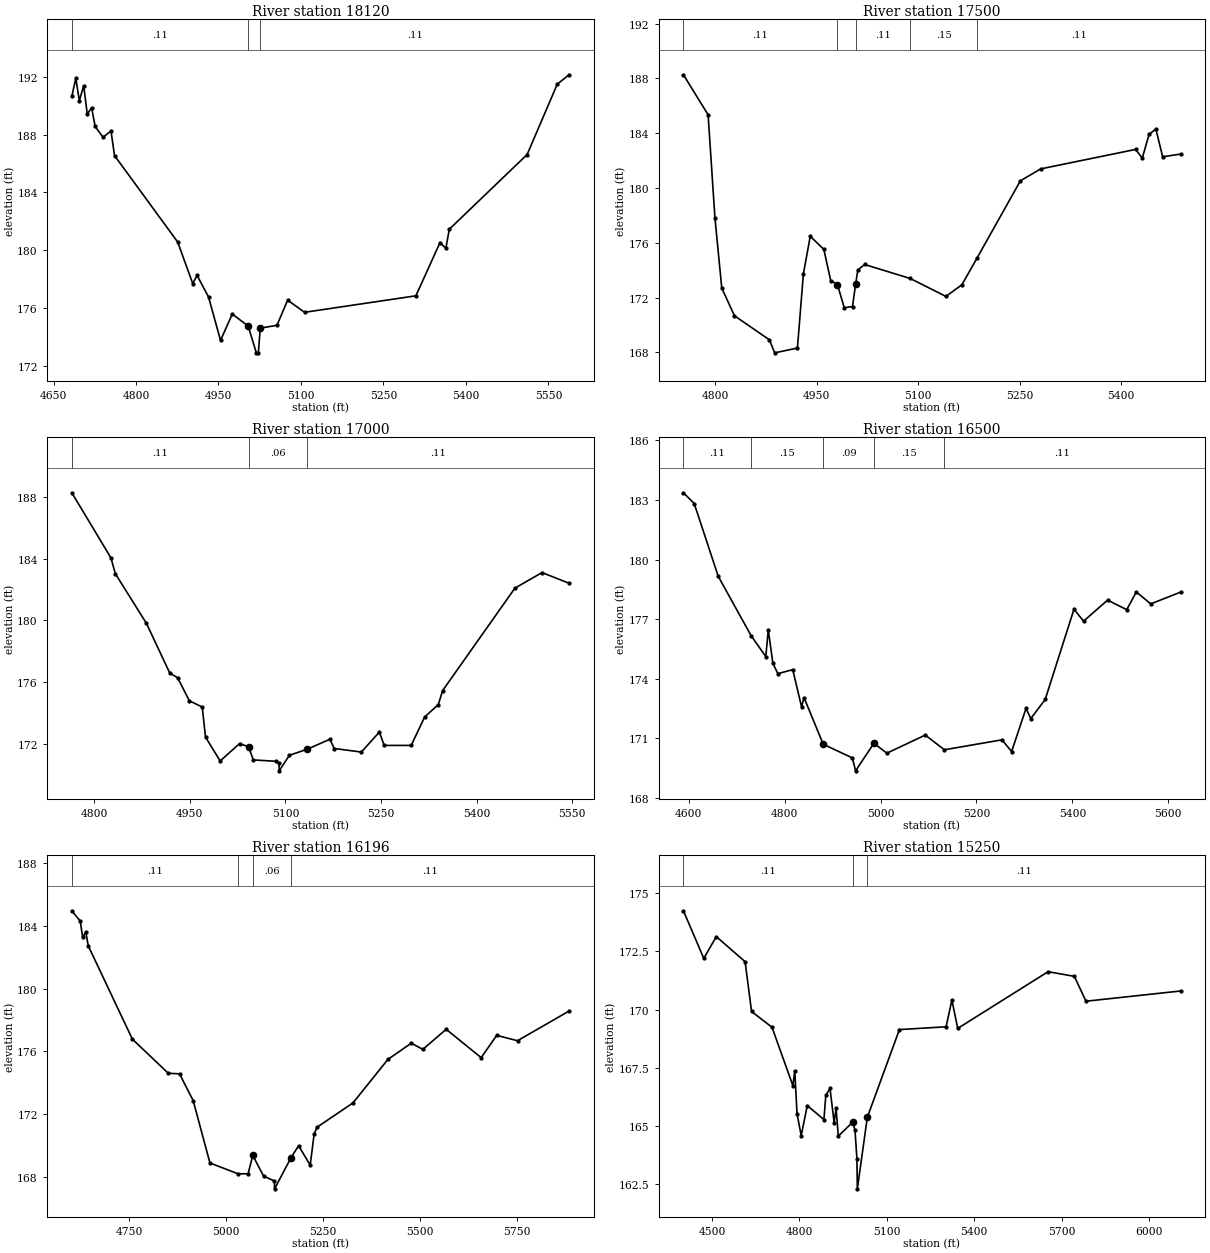
Type RM Length L Ch R = 1 ,18120   ,620,620,620
BEGIN DESCRIPTION:
LAKE CREEK TRIBUTARY NO. 11 36.0
END DESCRIPTION:
XS GIS Cut Line= 3
      3776717.88     10090411.04      3776517.52      10090658.2
      3775967.83     10090861.08
#Sta/Elev= 30
  4683.3  190.64  4690.5  191.88    4697  190.34  4704.9  191.38  4711.3  189.42
  4719.3  189.85  4725.7  188.56  4740.1  187.81  4754.5  188.25  4760.9  186.55
  4875.9  180.57  4903.2   177.7  4911.1  178.27  4931.9  176.78  4953.7  173.78
  4975.1   175.6    5004  174.77  5018.8  172.92  5022.5  172.92    5026  174.63
  5056.4  174.82  5075.7  176.56  5106.6  175.72    5309  176.86  5352.9  180.54
  5363.5  180.14  5369.8  181.46  5511.3  186.62  5566.1  191.48  5587.4  192.13
#Mann= 3 ,-1 , 0
  4683.3     .11       0    5004     .07       0    5026     .11       0
Bank Sta=5004,5026
XS Rating Curve= 0 ,0
Exp/Cntr=0.3,0.1

Type RM Length L Ch R = 1 ,17500   ,500,500,500
BEGIN DESCRIPTION:
LAKE CREEK TRIBUTARY NO. 11 35.0
END DESCRIPTION:
XS GIS Cut Line= 3
      3776684.14     10090335.28      3776438.63     10090306.45
      3775951.38      10090335.2
#Sta/Elev= 30
  4752.8  188.26  4789.3  185.34  4799.4  177.82  4809.5  172.69  4828.2  170.67
    4880  168.91  4887.8  167.96  4921.4  168.31  4930.3  173.75  4940.4  176.47
  4960.5  175.51  4970.6  173.24  4980.6  172.94  4990.7  171.25  5002.9  171.34
 5007.45  172.97  5010.8  174.01  5020.8  174.41  5088.2  173.39    5141  172.08
  5164.7  172.93  5187.3   174.9  5251.2  180.52  5281.3  181.39  5421.5  182.81
  5431.5  182.18  5441.5  183.91  5451.6   184.3  5461.6  182.27  5488.1  182.47
#Mann= 5 ,-1 , 0
  4752.8     .11       0  4980.6     .06       0 5007.45     .11       0
  5088.2     .15       0  5187.3     .11       0
#Block Obstruct= 2 , 0
         4940.99  176.49
Bank Sta=4980.6,5007.45
XS Rating Curve= 0 ,0
Exp/Cntr=0.3,0.1

Type RM Length L Ch R = 1 ,17000   ,500,500,500
BEGIN DESCRIPTION:
LAKE CREEK TRIBUTARY NO. 11 34.0
END DESCRIPTION:
XS GIS Cut Line= 3
      3776667.85     10089861.07      3776438.23     10089911.55
      3776067.85     10090311.08
#Sta/Elev= 30
  4764.9  188.29  4826.3  184.06  4833.1  183.04    4882  179.81  4918.5  176.59
  4930.9  176.28  4949.2  174.79  4969.5  174.38  4974.6  172.43  4997.6  170.88
    5028  172.01  5042.2   171.8  5049.6  170.95  5084.7  170.86  5089.9  170.74
  5090.2  170.24  5106.2  171.25  5134.6  171.65  5169.8  172.29  5176.6  171.69
  5219.1  171.46  5247.4  172.76  5254.8  171.89  5297.3  171.89  5318.3  173.73
  5339.8  174.54  5346.6  175.45    5460   182.1  5502.5  183.11  5544.8  182.42
#Mann= 3 , 0 , 0
  4764.9     .11       0  5042.2     .06       0  5134.6     .11       0
Bank Sta=5042.2,5134.6
XS Rating Curve= 0 ,0
Exp/Cntr=0.3,0.1

Type RM Length L Ch R = 1 ,16500   ,304,304,304
BEGIN DESCRIPTION:
LAKE CREEK TRIBUTARY NO. 11 33.0
END DESCRIPTION:
XS GIS Cut Line= 3
      3776617.85     10089711.07      3776221.18      10089603.9
      3775595.68     10089606.12
#Sta/Elev= 30
  4589.1  183.36  4611.6  182.82  4661.6  179.16  4730.2  176.17  4760.8  175.12
    4766  176.46  4775.6  174.78  4785.9  174.26    4817  174.46  4835.4  172.59
  4840.6  173.05  4880.5  170.71  4941.3  170.02    4948  169.37 4986.12170.7551
  5013.3  170.26  5093.3  171.17  5133.1  170.43  5253.3  170.93  5273.3  170.34
  5303.3  172.51  5313.3     172  5343.3  172.96  5403.3   177.5  5423.3   176.9
  5473.3  177.96  5513.3  177.48  5533.3  178.37  5563.3  177.77  5625.5  178.36
#Mann= 5 ,-1 , 0
  4589.1     .11       0  4730.2     .15       0  4880.5     .09       0
 4986.12     .15       0  5133.1     .11       0
Bank Sta=4880.5,4986.12
XS Rating Curve= 0 ,0
Exp/Cntr=0.3,0.1

Type RM Length L Ch R = 1 ,16196   ,946,946,946
BEGIN DESCRIPTION:
LAKE CREEK TRIBUTARY NO. 11 32.0
END DESCRIPTION:
XS GIS Cut Line= 3
      3776717.84     10089661.06      3776417.52     10089420.69
      3775521.82     10089368.23
#Sta/Elev= 30
  4602.9  184.97  4624.5  184.31  4630.9  183.27  4638.9  183.62  4645.3  182.73
    4759  176.78  4851.8   174.6  4880.6  174.57  4915.8  172.86    4959  168.88
  5031.4  168.19  5057.4  168.19  5069.5  169.36  5097.4  168.04  5125.3  167.73
  5125.6  167.23  5167.5  169.19  5187.6  169.98  5217.6  168.74  5227.6  170.72
  5235.1  171.16  5327.8  172.71    5418  175.49  5478.1  176.52  5508.1  176.13
  5568.2  177.41  5658.4   175.6  5698.5  177.02  5752.1  176.68  5884.8  178.57
#Mann= 4 ,-1 , 0
  4602.9     .11       0  5031.4     .15       0  5069.5     .06       0
  5167.5     .11       0
Bank Sta=5069.5,5167.5
XS Rating Curve= 0 ,0
Exp/Cntr=0.3,0.1

Type RM Length L Ch R = 1 ,15250   ,250,250,250
BEGIN DESCRIPTION:
LAKE CREEK TRIBUTARY NO. 11 31.0
END DESCRIPTION:
XS GIS Cut Line= 3
      3777088.55     10089019.24      3776630.19      10088633.8
      3775523.47     10088597.34
#Sta/Elev= 30
  4402.1  174.25    4472   172.2  4514.9  173.14  4613.8  172.06  4635.9  169.92
  4706.1  169.24  4777.7  166.73  4784.2  167.37    4792  165.52  4806.3  164.58
  4827.1  165.87  4884.3  165.27  4890.8  166.31  4905.1  166.61  4919.4  165.14
    4926  165.75  4933.7  164.56  4983.2  165.16  4990.9  164.82  4997.5  163.59
    4999  162.29  5033.3  165.37  5143.4  169.14  5303.5  169.26  5323.5  170.41
  5343.5  169.19  5653.7  171.63  5743.7  171.43  5783.7  170.36  6108.3   170.8
#Mann= 3 ,-1 , 0
  4402.1     .11       0  4983.2     .07       0  5033.3     .11       0
Bank Sta=4983.2,5033.3
XS Rating Curve= 0 ,0
Exp/Cntr=0.3,0.1

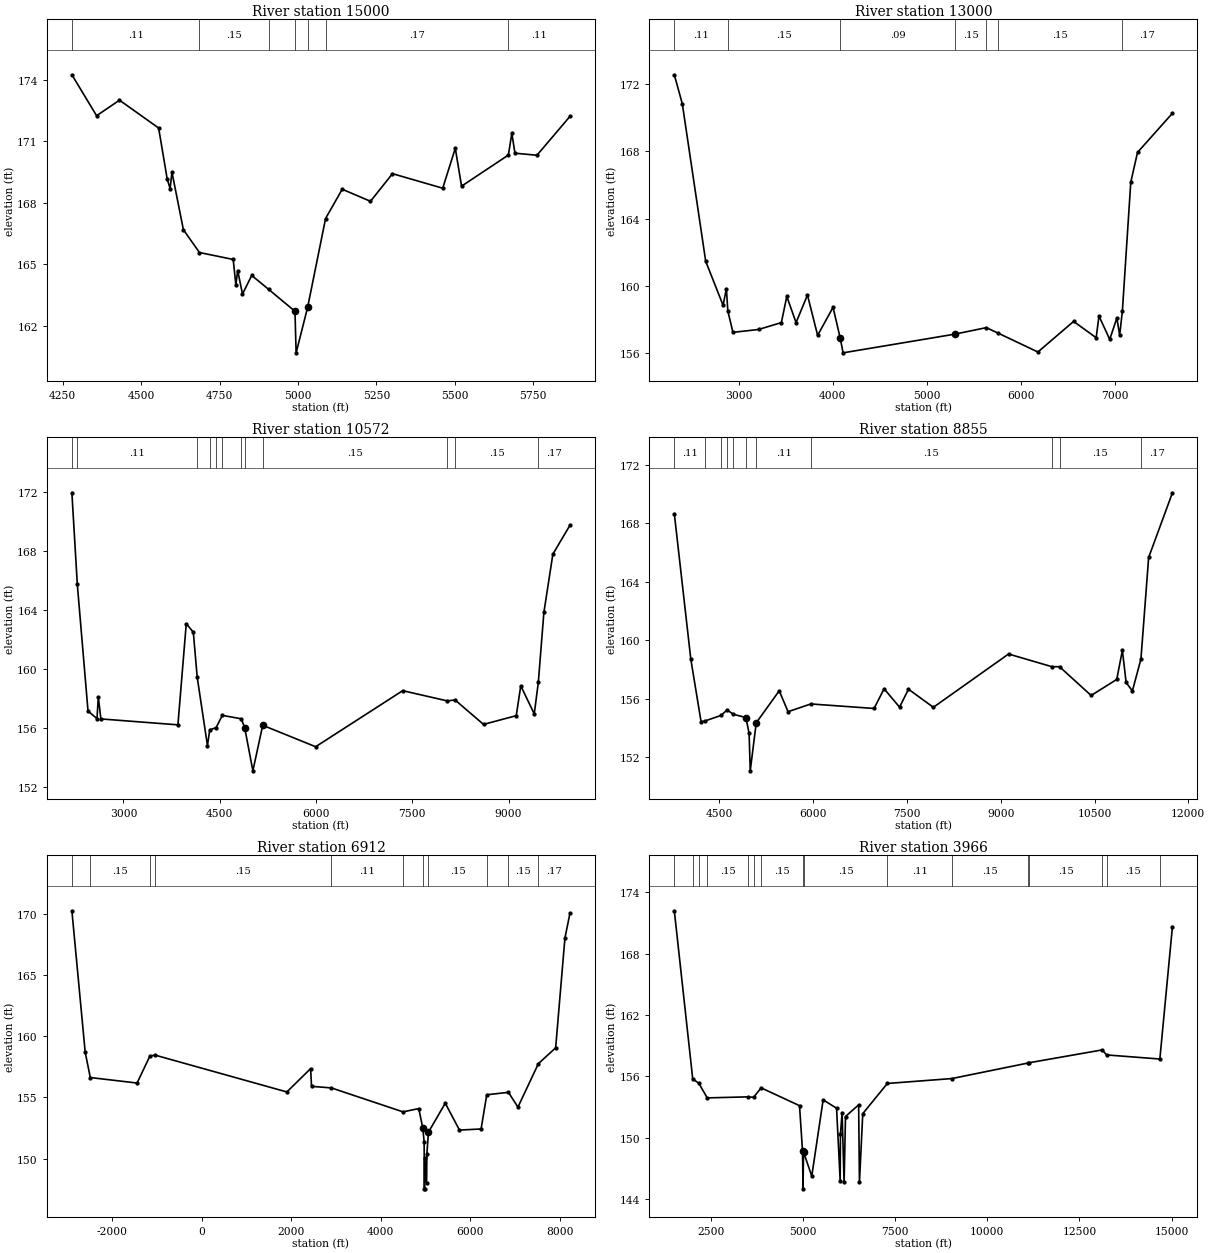
Type RM Length L Ch R = 1 ,15000   ,2000,2000,2000
BEGIN DESCRIPTION:
LAKE CREEK TRIBUTARY NO. 11 30.0
END DESCRIPTION:
XS GIS Cut Line= 3
      3777092.41     10089016.57      3776708.89     10088406.39
       3775842.6      10088454.1
#Sta/Elev= 30
  4279.3  174.25  4358.1  172.25  4431.1  173.01  4555.9  171.65  4583.1  169.17
  4592.5  168.69  4598.4  169.49  4634.9  166.68  4686.1  165.57  4793.7  165.23
  4802.1  163.99    4808  164.69  4823.3  163.54  4852.7  164.45  4906.7  163.77
  4990.6   162.7  4994.3  160.67  5031.1   162.9  5088.2  167.23  5141.3  168.66
  5231.4  168.07  5301.5  169.42  5461.7  168.71  5501.8  170.66  5521.8  168.81
  5671.1  170.33  5682.1  171.39  5692.1  170.42  5762.2  170.32  5867.6  172.22
#Mann= 7 ,-1 , 0
  4279.3     .11       0  4686.1     .15       0  4906.7     .11       0
  4990.6     .06       0  5031.1     .11       0  5088.2     .17       0
  5671.1     .11       0
Bank Sta=4990.6,5031.1
XS Rating Curve= 0 ,0
Exp/Cntr=0.3,0.1

Type RM Length L Ch R = 1 ,13000   ,2428,2428,2428
BEGIN DESCRIPTION:
LAKE CREEK TRIBUTARY NO. 11 26.0
END DESCRIPTION:
XS GIS Cut Line= 5
      3777956.76     10089225.49      3776865.43     10086769.44
      3776665.52      10086360.9      3776057.89     10087055.34
      3776112.14     10088292.36
#Sta/Elev= 30
  2312.4  172.56  2397.6  170.83  2646.6  161.46  2831.5  158.84  2866.8  159.83
  2882.2   158.5  2936.6  157.23  3208.8   157.4  3452.3  157.81    3510  159.37
  3608.5  157.81    3730  159.45  3838.3  157.05  4002.4  158.72    4079  156.88
  4109.3  156.01  5296.3  157.12  5634.5  157.51  5760.9  157.18  6183.5  156.06
  6563.5  157.88  6803.7  156.91  6833.8   158.2  6948.1  156.81  7023.9  158.08
    7054  157.06  7082.9   158.5  7172.3  166.17  7244.2  167.94  7615.8  170.27
#Mann= 7 ,-1 , 0
  2312.4     .11       0  2882.2     .15       0    4079     .09       0
  5296.3     .15       0  5634.5     .11       0  5760.9     .15       0
  7082.9     .17       0
Bank Sta=4079,5296.3
XS Rating Curve= 0 ,0
Exp/Cntr=0.3,0.1

Type RM Length L Ch R = 1 ,10572   ,1717,1717,1717
BEGIN DESCRIPTION:
LAKE CREEK TRIBUTARY NO. 11 10.0
END DESCRIPTION:
XS GIS Cut Line= 6
      3778889.92     10088932.47        3778972.     10086130.17
      3778800.78     10085742.16      3776611.27     10086187.28
      3775960.23     10087001.09      3776003.57     10088257.96
#Sta/Elev= 30
  2196.5  171.92    2281  165.73    2448  157.16  2588.1  156.65  2608.1  158.13
  2648.1  156.63  3848.6  156.23  3978.7  163.07  4088.7  162.49  4149.5  159.44
  4308.8  154.83  4344.7  155.89  4442.9  156.04  4541.2  156.87    4836  156.64
  4889.1  156.04  5016.6  153.12  5169.9   156.2  5994.7  154.75  7350.9  158.54
  8045.1  157.85  8167.3  157.91  8610.4  156.26  9120.8  156.85  9190.9  158.87
    9401  156.97  9464.5   159.1  9551.1  163.83  9691.2  167.77  9958.2  169.73
#Mann= 12 ,-1 , 0
  2196.5     .17       0    2281     .11       0  4149.5     .15       0
  4344.7     .11       0  4442.9     .15       0  4541.2     .11       0
    4836     .15       0  4889.1     .06       0  5169.9     .15       0
  8045.1     .11       0  8167.3     .15       0  9464.5     .17       0
Bank Sta=4889.1,5169.9
XS Rating Curve= 0 ,0
Exp/Cntr=0.3,0.1

Type RM Length L Ch R = 1 ,8855    ,1943,1943,1943
BEGIN DESCRIPTION:
LAKE CREEK TRIBUTARY NO. 11 8.0
END DESCRIPTION:
XS GIS Cut Line= 6
      3780167.84      10087561.1      3780467.66     10086375.83
      3779615.88     10085515.56      3776513.61     10086133.03
      3775862.57     10086968.53      3775905.98     10088281.47
#Sta/Elev= 30
  3777.4  168.66  4041.5  158.69  4205.6  154.41  4270.9  154.47  4522.3  154.84
  4622.8  155.22  4723.2  154.92  4922.4   154.7    4974  153.61  4992.1  151.05
  5088.1  154.34  5455.8  156.53  5597.2   155.1    5962  155.63  6973.3  155.32
  7133.3  156.67  7381.2  155.41  7523.9  156.64  7921.6   155.4  9124.7  159.05
    9819  158.18  9940.1  158.18 10445.9  156.21 10855.7  157.31 10945.8   159.3
 11005.8   157.1 11105.8  156.52 11242.5   158.7   11366  165.66 11746.6  170.09
#Mann= 11 ,-1 , 0
  3777.4     .11       0  4270.9     .15       0  4522.3     .11       0
  4622.8     .15       0  4723.2     .11       0  4922.4     .06       0
  5088.1     .11       0    5962     .15       0    9819     .11       0
  9940.1     .15       0 11242.5     .17       0
Bank Sta=4922.4,5088.1
XS Rating Curve= 0 ,0
Exp/Cntr=0.3,0.1

Type RM Length L Ch R = 1 ,6912    ,2946,2946,2946
BEGIN DESCRIPTION:
LAKE CREEK TRIBUTARY NO. 11 6.0
END DESCRIPTION:
XS GIS Cut Line= 6
      3775808.31     10088216.22      3776437.66     10086046.23
      3779595.21     10085416.88      3781858.28     10085618.02
      3782682.24     10086834.65      3782155.98     10088509.33
#Sta/Elev= 30
 -2893.4  170.28   -2596  158.69 -2482.3  156.63 -1438.3  156.18 -1150.9   158.4
 -1031.7  158.46  1904.8  155.45    2435  157.36  2455.4  155.91  2899.5  155.78
  4497.2  153.82    4849  154.09  4939.3  152.49  4969.4  151.34  4973.6  147.52
  4978.7  147.52  4981.3  150.04  5023.9  148.02  5029.9  150.38  5065.9  152.16
  5440.3  154.53  5757.8  152.33  6240.1  152.42  6366.6  155.22    6851  155.42
  7062.8  154.21  7519.3  157.77  7904.3  159.06  8111.3  168.04  8224.8   170.1
#Mann= 11 ,-1 , 0
 -2893.4     .17       0 -2482.3     .15       0 -1150.9     .11       0
 -1031.7     .15       0  2899.5     .11       0  4497.2     .15       0
  4939.3     .09       0  5065.9     .15       0  6366.6     .11       0
    6851     .15       0  7519.3     .17       0
Bank Sta=4939.3,5065.9
XS Rating Curve= 0 ,0
Exp/Cntr=0.3,0.1

Type RM Length L Ch R = 1 ,3966    ,0,0,0
BEGIN DESCRIPTION:
LAKE CREEK TRIBUTARY NO. 11 3.0
END DESCRIPTION:
XS GIS Cut Line= 6
      3783067.42     10088607.03      3783396.33      10085208.6
      3781617.85     10084411.07      3776307.45     10085981.12
      3775602.16     10087001.09      3775721.34     10088257.88
#Sta/Elev= 30
  1510.9  172.18  2010.3  155.75  2177.7  155.31  2403.6  153.89  3505.9  153.99
  3661.9  153.95  3865.7  154.87  4906.8  153.13 4989.46148.6703  5001.2     145
 5015.88 148.601  5239.4  146.24  5547.8   153.7  5911.9  152.88  6010.1   145.8
  6017.6  150.33    6062  152.46  6116.2  145.62  6154.7  152.07  6510.7  153.21
  6532.7  145.62  6622.5  152.35  7289.8   155.3  9040.3  155.78 11108.3   157.3
 11126.6  157.32   13119  158.58 13235.4  158.09 14681.2  157.69 15022.5  170.64
#Mann= 16 ,-1 , 0
  1510.9     .17       0  2010.3     .15       0  2177.7     .17       0
  2403.6     .15       0  3505.9     .17       0  3661.9     .11       0
  3865.7     .15       0 4989.46     .09       0 5015.88     .15       0
  7289.8     .11       0  9040.3     .15       0 11108.3     .11       0
 11126.6     .15       0   13119     .11       0 13235.4     .15       0
 14681.2     .17       0
Bank Sta=4989.46,5015.88
XS Rating Curve= 0 ,0
Exp/Cntr=0.3,0.1

Chan Stop Cuts=-1
Use User Specified Reach Order=0
Composite Channel Slope=5