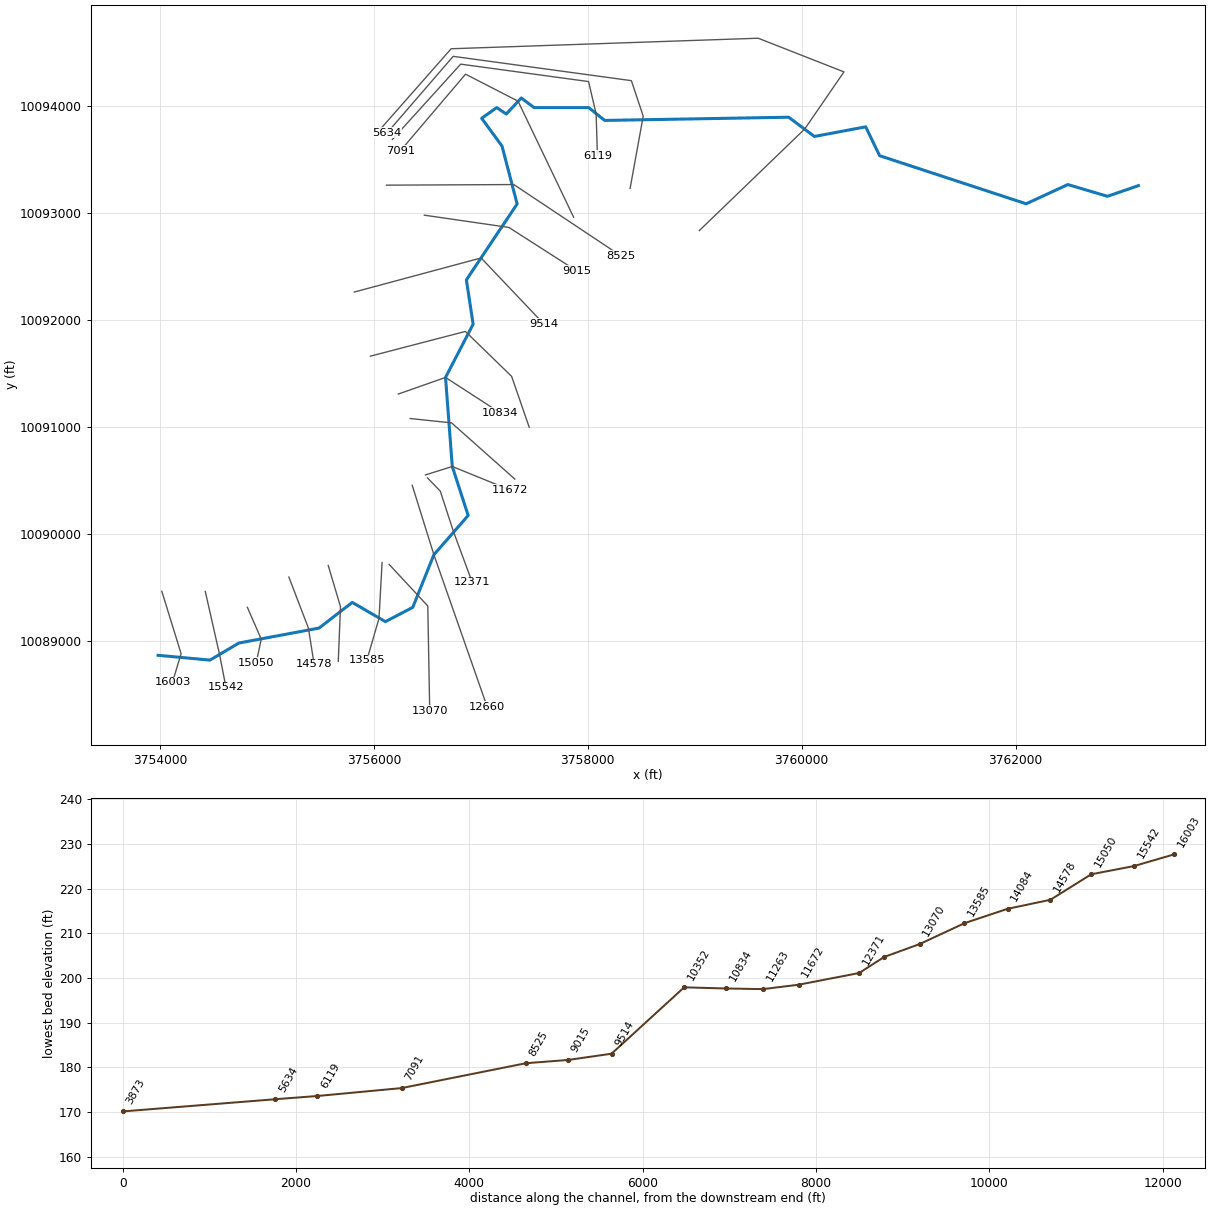
--- LAKE CREEK TRIBUTARY NO 12.prj (project) ---

Proj Title=LAKE CREEK TRIBUTARY NO 12 Base Level Engineering
Current Plan=p01
Default Exp/Contr=0.3,0.1
English Units
Geom File=g01
Flow File=f01
Flow File=f02
Plan File=p01
Y Axis Title=Elevation
X Axis Title(PF)=Main Channel Distance
X Axis Title(XS)=Station
BEGIN DESCRIPTION:
LAKE CREEK TRIBUTARY NO 12
END DESCRIPTION:
DSS Export Rating Curves= 0
DSS Export Rating Curve Sorted= 0
DSS Export Volume Flow Curves= 0
DXF OffsetX= 0
DXF OffsetY= 0
DXF ScaleX= 1
DXF ScaleY= 10

--- LAKE CREEK TRIBUTARY NO 12.p01 (plan) ---

Plan Title=Multiple Run
Short Identifier=Multiple
Geom File=g01
Flow File=f01
Subcritical Flow
K Sum by GR= 0
Std Step Tol= 0.01
Critical Tol= 0.01
Num of Std Step Trials= 20
Max Error Tol= 0.3
Flow Tol Ratio= 0.001
Split Flow NTrial= 30
Split Flow Tol= 0.02
Split Flow Ratio= 0.02
Log Output Level= 0
Friction Slope Method= 1
Unsteady Friction Slope Method= 2
Unsteady Bridges Friction Slope Method= 1
Parabolic Critical Depth
Global Vel Dist=  1 , 1 , 1
Global Log Level= 0
CheckData=True
Encroach Param= -1, 0, 0, 0
BEGIN DESCRIPTION:
Multiple Run
END DESCRIPTION:

--- LAKE CREEK TRIBUTARY NO 12.f01 (steady flow) ---

Flow Title=Multiple
Program Version=4.10
Number of Profiles= 7
Profile Names=10-year,25-year,50-year,1pct_min,100-year,1pct_plu,500-year
River Rch & RM=LAKE CREEK TRIBU,Reach-1         ,16003
     619     838    1135     506    1528    4614    2857
River Rch & RM=LAKE CREEK TRIBU,Reach-1         ,13070
    1010    1405    1934     875    2642    7979    5102
River Rch & RM=LAKE CREEK TRIBU,Reach-1         ,9514
    1279    1794    2483    1128    3407   10289    6634
Boundary for River Rch & Prof#=LAKE CREEK TRIBU,Reach-1         , 1
Up Type= 0
Dn Type= 3
Dn Slope=0.005
Boundary for River Rch & Prof#=LAKE CREEK TRIBU,Reach-1         , 2
Up Type= 0
Dn Type= 3
Dn Slope=0.005
Boundary for River Rch & Prof#=LAKE CREEK TRIBU,Reach-1         , 3
Up Type= 0
Dn Type= 3
Dn Slope=0.005
Boundary for River Rch & Prof#=LAKE CREEK TRIBU,Reach-1         , 4
Up Type= 0
Dn Type= 3
Dn Slope=0.005
Boundary for River Rch & Prof#=LAKE CREEK TRIBU,Reach-1         , 5
Up Type= 0
Dn Type= 3
Dn Slope=0.005
Boundary for River Rch & Prof#=LAKE CREEK TRIBU,Reach-1         , 6
Up Type= 0
Dn Type= 3
Dn Slope=0.005
Boundary for River Rch & Prof#=LAKE CREEK TRIBU,Reach-1         , 7
Up Type= 0
Dn Type= 3
Dn Slope=0.005
DSS Import GetInterval= 0
DSS Import GetPeak= 0
DSS Import FillOption= 0

--- LAKE CREEK TRIBUTARY NO 12.f02 (steady flow) ---

Flow Title=Orig_BLE_Flows
Program Version=4.10
Number of Profiles= 7
Profile Names=10-year,25-year,50-year,1pct_min,100-year,1pct_plu,500-year
River Rch & RM=LAKE CREEK TRIBU,Reach-1         ,16003
     619     822     987     389    1175    3548    1661
River Rch & RM=LAKE CREEK TRIBU,Reach-1         ,13070
    1010    1377    1682     673    2032    6138    2966
River Rch & RM=LAKE CREEK TRIBU,Reach-1         ,9514
    1279    1759    2159     868    2621    7914    3857
Boundary for River Rch & Prof#=LAKE CREEK TRIBU,Reach-1         , 1
Up Type= 0
Dn Type= 3
Dn Slope=0.005
Boundary for River Rch & Prof#=LAKE CREEK TRIBU,Reach-1         , 2
Up Type= 0
Dn Type= 3
Dn Slope=0.005
Boundary for River Rch & Prof#=LAKE CREEK TRIBU,Reach-1         , 3
Up Type= 0
Dn Type= 3
Dn Slope=0.005
Boundary for River Rch & Prof#=LAKE CREEK TRIBU,Reach-1         , 4
Up Type= 0
Dn Type= 3
Dn Slope=0.005
Boundary for River Rch & Prof#=LAKE CREEK TRIBU,Reach-1         , 5
Up Type= 0
Dn Type= 3
Dn Slope=0.005
Boundary for River Rch & Prof#=LAKE CREEK TRIBU,Reach-1         , 6
Up Type= 0
Dn Type= 3
Dn Slope=0.005
Boundary for River Rch & Prof#=LAKE CREEK TRIBU,Reach-1         , 7
Up Type= 0
Dn Type= 3
Dn Slope=0.005
DSS Import GetInterval= 0
DSS Import GetPeak= 0
DSS Import FillOption= 0

--- LAKE CREEK TRIBUTARY NO 12.g01 (geometry) ---

Geom Title=Existing Conditions
Program Version=4.10

River Reach=LAKE CREEK TRIBU,Reach-1
Reach XY= 30
      3753983.23     10088861.84      3754468.23     10088816.84
      3754738.23     10088976.64      3755488.23     10089116.84
      3755798.23     10089356.84      3756108.23     10089176.84
      3756363.99     10089310.63      3756561.39     10089802.67
       3756881.7     10090170.29      3756733.29     10090628.64
      3756670.33     10091461.95      3756928.23     10091960.22
       3756865.2     10092375.15       3757339.6     10093085.07
      3757198.23     10093626.84      3757008.23     10093886.84
      3757148.23     10093986.84      3757238.23     10093926.84
      3757378.23     10094076.84      3757498.23     10093986.84
      3758008.23     10093986.84      3758158.23     10093866.84
      3759878.23     10093896.84      3760118.23     10093716.84
      3760598.23     10093806.84      3760728.23     10093536.84
      3762098.23     10093086.84      3762488.23     10093266.84
      3762858.23     10093156.84      3763148.23     10093256.84

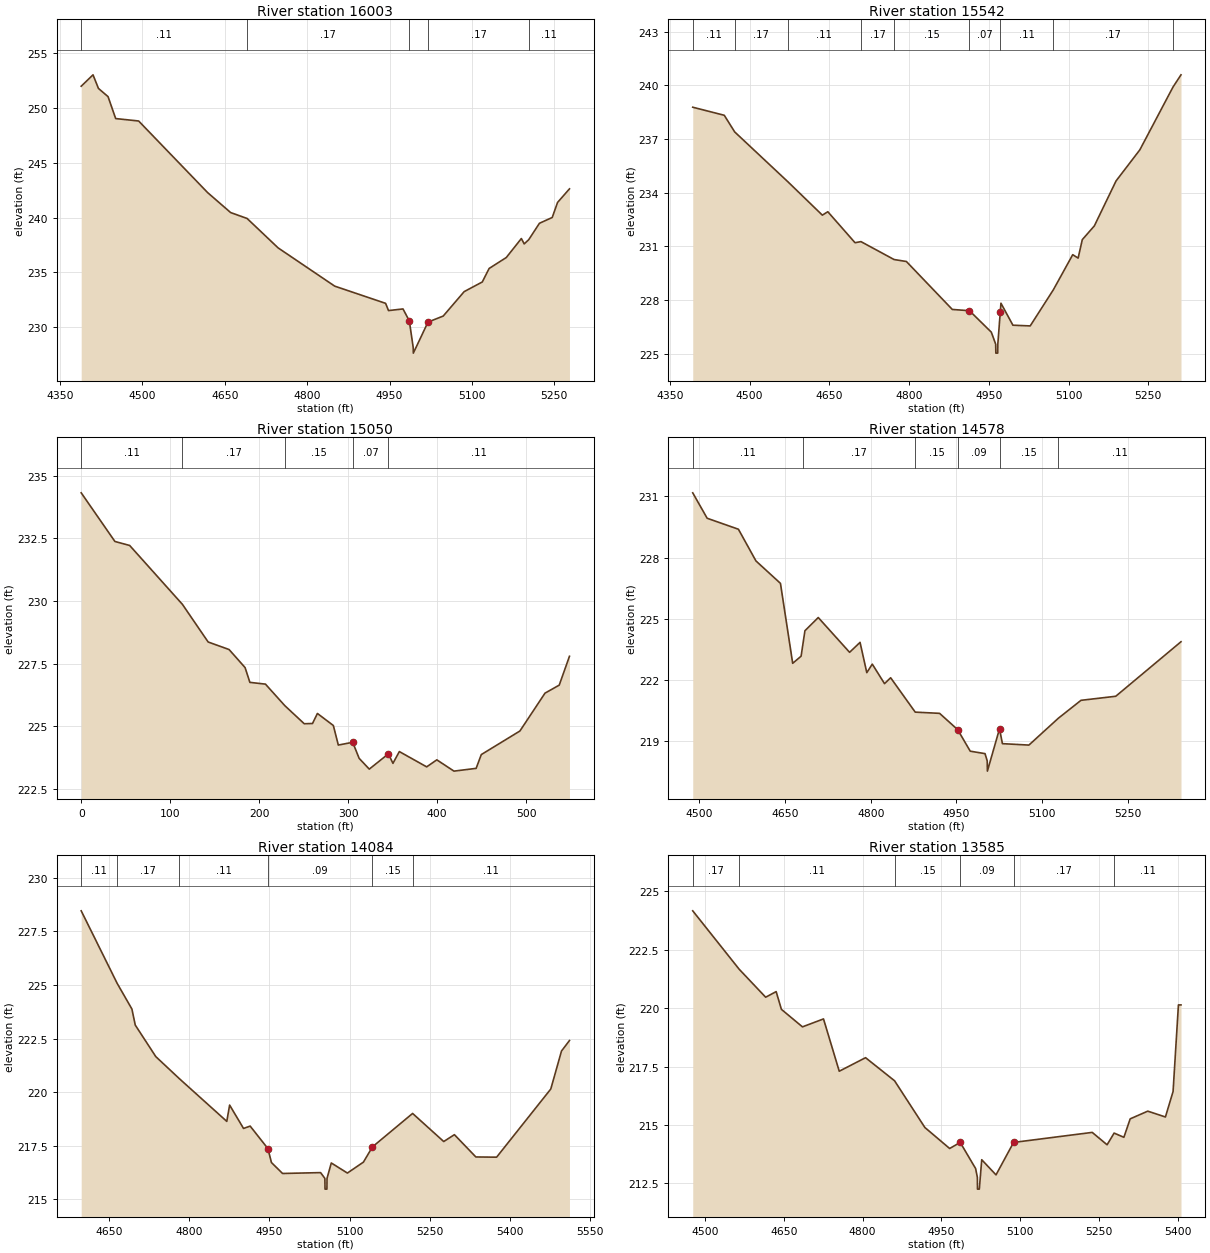
Type RM Length L Ch R = 1 ,16003   ,461,461,461
BEGIN DESCRIPTION:
LAKE CREEK TRIBUTARY NO. 12 30.0
END DESCRIPTION:
XS GIS Cut Line= 3
      3754017.86     10089461.03      3754198.23     10088876.84
      3754117.84     10088611.04
#Sta/Elev= 30
  4388.6  251.98  4410.1  253.02    4420  251.78  4437.5  251.03  4451.4  249.03
  4493.2  248.81  4618.8  242.28  4660.7  240.46  4690.7  239.92  4747.1  237.24
  4850.2  233.75  4942.9  232.18  4948.2  231.52  4974.6  231.67  4986.1  230.58
  4993.2  228.14  4993.4  227.64  5020.1  230.47  5047.8  231.02    5086  233.25
    5119  234.13  5131.4  235.36  5162.7  236.36  5190.1  238.09  5195.3   237.6
  5203.6  237.99    5223  239.48  5246.3  240.01    5256  241.38  5277.7  242.62
#Mann= 5 ,-1 , 0
  4388.6     .11       0  4690.7     .17       0  4986.1     .09       0
  5020.1     .17       0  5203.6     .11       0
Bank Sta=4986.1,5020.1
XS Rating Curve= 0 ,0
Exp/Cntr=0.3,0.1

Type RM Length L Ch R = 1 ,15542   ,492,492,492
BEGIN DESCRIPTION:
LAKE CREEK TRIBUTARY NO. 12 29.0
END DESCRIPTION:
XS GIS Cut Line= 3
      3754424.42     10089458.91      3754558.23     10088866.84
      3754617.85      10088561.1
#Sta/Elev= 30
    4393  238.78  4452.3  238.33  4471.9   237.4  4571.8  234.62  4636.8  232.75
  4647.1  232.94  4698.3  231.21  4709.5  231.27  4771.7  230.27  4794.9  230.16
  4881.3  227.48  4913.6  227.41  4954.7  226.21  4962.9  225.54  4963.2  225.04
  4966.7  225.04  4966.9  225.54  4971.6227.3644  4972.8  227.83  4995.3   226.6
  5027.8  226.56  5071.2  228.57  5107.8  230.54    5118  230.35  5125.8  231.38
  5148.5  232.15  5189.3  234.66  5234.1   236.4  5296.5  239.91  5311.5  240.59
#Mann= 9 ,-1 , 0
    4393     .11       0  4471.9     .17       0  4571.8     .11       0
  4709.5     .17       0  4771.7     .15       0  4913.6     .07       0
  4971.6     .11       0  5071.2     .17       0  5296.5     .11       0
Bank Sta=4913.6,4971.6
XS Rating Curve= 0 ,0
Exp/Cntr=0.3,0.1

Type RM Length L Ch R = 1 ,15050   ,472,472,472
BEGIN DESCRIPTION:
LAKE CREEK TRIBUTARY NO. 12 28.0
END DESCRIPTION:
XS GIS Cut Line= 3
      3754817.85     10089311.07      3754947.56     10089011.95
      3754900.17     10088792.41
#Sta/Elev= 30
       0  234.31    37.9  232.37    54.5  232.21   113.8  229.86   142.7  228.36
   166.2  228.06   184.2  227.34   189.6  226.75   207.1  226.68   228.9  225.82
   250.7   225.1     260  225.11   265.5  225.51   283.4  225.03     289  224.25
   305.2  224.36   312.4  223.72   323.8  223.29   345.3   223.9   350.4  223.52
   357.6  223.99   388.3  223.38   399.7  223.66     419  223.21   443.9  223.32
   449.7  223.87   493.1  224.81   521.3  226.32   537.3  226.64   548.8  227.79
#Mann= 5 ,-1 , 0
       0     .11       0   113.8     .17       0   228.9     .15       0
   305.2     .07       0   345.3     .11       0
Bank Sta=305.2,345.3
XS Rating Curve= 0 ,0
Exp/Cntr=0.3,0.1

Type RM Length L Ch R = 1 ,14578   ,494,494,494
BEGIN DESCRIPTION:
LAKE CREEK TRIBUTARY NO. 12 27.0
END DESCRIPTION:
XS GIS Cut Line= 3
      3755205.67     10089594.34      3755388.23     10089116.84
      3755441.78     10088778.35
#Sta/Elev= 30
  4488.8  231.18    4514  229.93  4568.7  229.39  4599.4  227.83  4642.2  226.73
  4663.6   222.8  4678.3  223.15  4681.8   223.8    4685   224.4  4708.3  225.05
  4763.1  223.34  4781.4  223.83  4793.2  222.34  4802.8  222.76  4824.2   221.8
  4834.9  222.09  4877.9   220.4  4920.5  220.34  4952.1  219.54  4974.1  218.48
    5000  218.36  5003.8     218  5004.1   217.5  5025.3  219.58  5030.4  218.85
  5076.7  218.78  5128.2   220.1  5167.8  220.98  5228.6  221.18  5342.7  223.86
#Mann= 6 ,-1 , 0
  4488.8     .11       0  4681.8     .17       0  4877.9     .15       0
  4952.1     .09       0  5025.3     .15       0  5128.2     .11       0
Bank Sta=4952.1,5025.3
XS Rating Curve= 0 ,0
Exp/Cntr=0.3,0.1

Type RM Length L Ch R = 1 ,14084   ,499,499,499
BEGIN DESCRIPTION:
LAKE CREEK TRIBUTARY NO. 12 26.0
END DESCRIPTION:
XS GIS Cut Line= 3
      3755573.72     10089701.98      3755688.23     10089316.84
      3755667.47     10088806.17
#Sta/Elev= 30
  4598.2  228.46  4665.6  225.07    4693  223.88  4699.3  223.13  4737.7  221.66
  4781.8  220.63  4870.4  218.64  4875.7   219.4  4901.7  218.31  4914.1  218.42
  4947.3  217.37  4953.9  216.72  4974.7  216.21  5045.8  216.25  5053.8  215.98
  5054.1  215.48  5057.6  215.48  5057.8  215.98  5065.8   216.7  5095.9  216.23
  5125.9  216.74 5142.73217.4498  5217.8  219.01    5276   217.7    5296  218.02
  5336.1  216.98  5374.9  216.97  5476.2  220.15  5496.2  221.92  5511.1  222.41
#Mann= 6 ,-1 , 0
  4598.2     .11       0  4665.6     .17       0  4781.8     .11       0
  4947.3     .09       0 5142.73     .15       0  5217.8     .11       0
Bank Sta=4947.3,5142.73
XS Rating Curve= 0 ,0
Exp/Cntr=0.3,0.1

Type RM Length L Ch R = 1 ,13585   ,515,515,515
BEGIN DESCRIPTION:
LAKE CREEK TRIBUTARY NO. 12 25.0
END DESCRIPTION:
XS GIS Cut Line= 3
      3756077.19     10089729.74      3756048.23     10089206.84
      3755934.84     10088816.59
#Sta/Elev= 30
  4476.3  224.17  4564.7  221.67  4615.2  220.47  4635.2  220.71  4645.2  219.95
  4685.3   219.2  4725.4  219.54  4755.4   217.3  4805.5  217.88  4860.8  216.89
  4918.5  214.89  4965.7  213.99  4985.8  214.25  5015.2  213.13  5018.5  212.75
  5018.7  212.25  5022.2  212.25  5026.8  213.51    5054  212.86  5087.5  214.25
  5237.3  214.68  5265.6  214.15    5279  214.65  5297.6  214.47  5309.6  215.26
  5343.1  215.59  5376.7  215.34  5391.3  216.43  5401.5  220.14  5406.4  220.14
#Mann= 6 ,-1 , 0
  4476.3     .17       0  4564.7     .11       0  4860.8     .15       0
  4985.8     .09       0  5087.5     .17       0    5279     .11       0
Bank Sta=4985.8,5087.5
XS Rating Curve= 0 ,0
Exp/Cntr=0.3,0.1

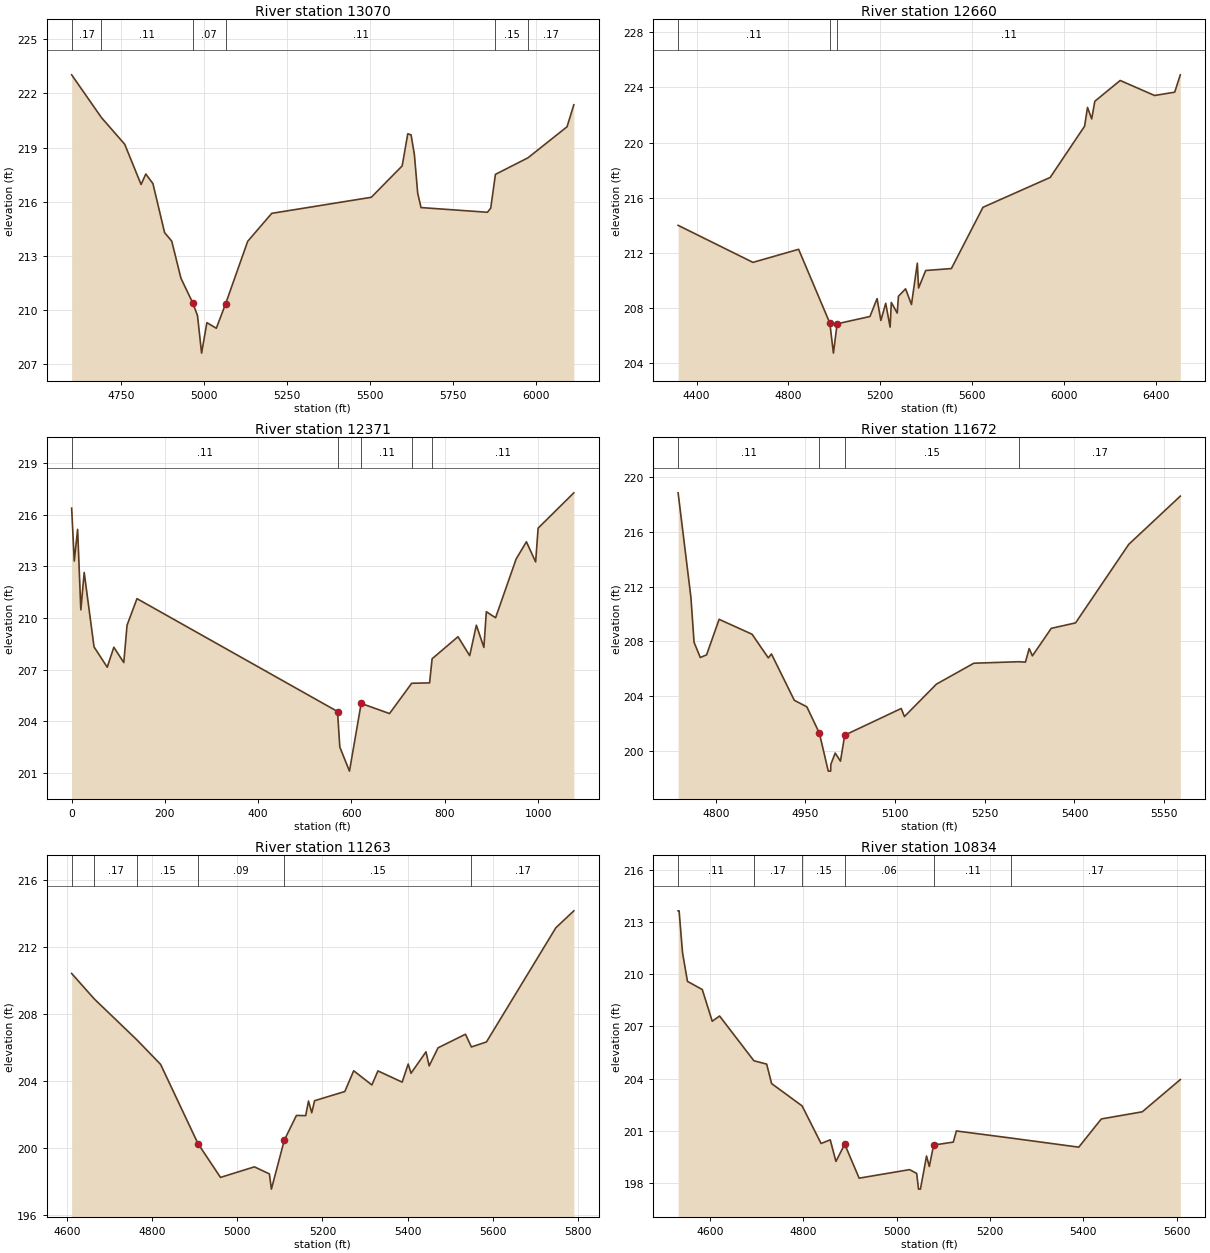
Type RM Length L Ch R = 1 ,13070   ,410,410,410
BEGIN DESCRIPTION:
LAKE CREEK TRIBUTARY NO. 12 24.0
END DESCRIPTION:
XS GIS Cut Line= 3
      3756143.15     10089712.42      3756504.28     10089323.52
      3756522.46      10088340.6
#Sta/Elev= 30
  4600.3  223.03  4690.1  220.66  4760.3  219.18  4809.6  216.95  4823.8  217.53
  4845.3     217  4880.5  214.28    4902  213.81  4929.8  211.75  4965.5  210.38
  4979.7  209.68    4992   207.6    5008  209.29  5036.4  208.98  5064.7  210.35
    5131   213.8  5203.5  215.35  5503.5  216.24  5596.6  217.98  5613.5  219.76
  5623.5   219.7  5633.5   218.6  5643.5  216.46  5653.5  215.67  5853.6  215.41
  5863.6  215.64  5877.7  217.51  5975.9  218.43  6093.6  220.15  6114.1  221.37
#Mann= 6 ,-1 , 0
  4600.3     .17       0  4690.1     .11       0  4965.5     .07       0
  5064.7     .11       0  5877.7     .15       0  5975.9     .17       0
Bank Sta=4965.5,5064.7
XS Rating Curve= 0 ,0
Exp/Cntr=0.3,0.1

Type RM Length L Ch R = 1 ,12660   ,289,289,289
BEGIN DESCRIPTION:
LAKE CREEK TRIBUTARY NO. 12 23.0
END DESCRIPTION:
XS GIS Cut Line= 3
      3756358.96     10090452.36      3756561.39     10089802.67
      3757059.66     10088379.47
#Sta/Elev= 30
  4319.5  213.99  4645.6   211.3  4844.6  212.25  4980.7  206.89  4996.3  204.71
  5012.3  206.84  5155.5  207.37  5186.6  208.67    5203  207.08  5224.2  208.33
  5243.3   206.6  5248.6  208.39  5274.3  207.62  5279.6  208.84  5310.7  209.38
  5336.4  208.24  5361.9  211.24  5367.4  209.44  5398.4  210.71  5510.3  210.85
    5648   215.3    5941  217.47  6090.8  221.19  6103.6  222.55  6121.8  221.72
  6135.4     223  6245.9  224.51  6395.7  223.42  6483.5  223.66  6507.9  224.92
#Mann= 3 , 0 , 0
  4319.5     .11       0  4980.7     .06       0  5012.3     .11       0
Bank Sta=4980.7,5012.3
XS Rating Curve= 0 ,0
Exp/Cntr=0.3,0.1

Type RM Length L Ch R = 1 ,12371   ,699,699,699
BEGIN DESCRIPTION:
LAKE CREEK TRIBUTARY NO. 12 22.0
END DESCRIPTION:
XS GIS Cut Line= 4
      3756500.99     10090522.19      3756621.01     10090398.61
      3756745.85     10090015.34      3756920.07       10089544.
#Sta/Elev= 30
       0  216.38     5.6  213.31    12.8  215.15    19.7  210.48    26.9  212.65
      48  208.33    76.3  207.15    90.5  208.31   111.8  207.42   118.8  209.59
   140.1  211.13   570.1  204.58     575  202.52   595.7  201.12   620.8  205.05
   681.6  204.46   729.2  206.22   767.5  206.24   772.9  207.64   828.4  208.92
   853.5  207.82   867.8  209.59   883.9   208.3   889.2  210.37     909  210.02
   953.1  213.43   975.1  214.43   994.9  213.26  1000.2  215.22  1076.8  217.27
#Mann= 5 ,-1 , 0
       0     .11       0   570.1     .07       0   620.8     .11       0
   729.2     .17       0   772.9     .11       0
Bank Sta=570.1,620.8
XS Rating Curve= 0 ,0
Exp/Cntr=0.3,0.1

Type RM Length L Ch R = 1 ,11672   ,409,409,409
BEGIN DESCRIPTION:
LAKE CREEK TRIBUTARY NO. 12 21.0
END DESCRIPTION:
XS GIS Cut Line= 3
      3756482.43     10090549.67      3756733.29     10090628.64
      3757267.81     10090411.09
#Sta/Elev= 30
    4737  218.85  4758.4  211.21  4763.7  207.92  4774.1  206.81  4784.6     207
  4805.6   209.6  4860.7  208.51  4887.9  206.78  4893.1  207.07  4931.4  203.68
  4952.4   203.2  4973.3  201.28  4988.2   198.5  4992.2   198.5  4992.5     199
  4999.8  199.82  5008.6  199.23  5015.7  201.13  5110.2  203.08  5115.6  202.49
  5169.1  204.86  5231.7  206.39  5306.9   206.5    5318  206.47  5324.3  207.46
  5329.7  206.93  5361.2  208.94  5401.9  209.34  5490.8  215.08  5577.1  218.61
#Mann= 4 ,-1 , 0
    4737     .11       0  4973.3     .07       0  5015.7     .15       0
  5306.9     .17       0
Bank Sta=4973.3,5015.7
XS Rating Curve= 0 ,0
Exp/Cntr=0.3,0.1

Type RM Length L Ch R = 1 ,11263   ,429,429,429
BEGIN DESCRIPTION:
LAKE CREEK TRIBUTARY NO. 12 20.0
END DESCRIPTION:
XS GIS Cut Line= 3
      3756340.04     10091077.51      3756727.18     10091036.61
      3757317.84     10090511.08
#Sta/Elev= 30
  4610.7   210.4  4664.2  208.87  4763.8  206.44  4819.7  204.97  4907.5  200.24
  4960.4  198.22  5040.1  198.85  5075.3  198.43    5080  197.52  5110.4  200.45
  5138.8  201.92  5160.6  201.91  5167.2  202.78  5174.8  202.08  5181.5   202.8
  5252.5  203.35  5273.4  204.59  5316.1  203.74  5330.3  204.58  5387.2  203.91
  5401.4  204.99  5408.1  204.44  5443.2  205.72  5450.7  204.88  5471.6  205.96
    5536  206.77  5549.9  206.01  5585.3  206.31  5748.4  213.13  5790.6  214.14
#Mann= 6 ,-1 , 0
  4610.7     .11       0  4664.2     .17       0  4763.8     .15       0
  4907.5     .09       0  5110.4     .15       0  5549.9     .17       0
Bank Sta=4907.5,5110.4
XS Rating Curve= 0 ,0
Exp/Cntr=0.3,0.1

Type RM Length L Ch R = 1 ,10834   ,482,482,482
BEGIN DESCRIPTION:
LAKE CREEK TRIBUTARY NO. 12 19.0
END DESCRIPTION:
XS GIS Cut Line= 3
      3756228.94     10091306.68      3756670.33     10091461.95
       3757180.3      10091131.1
#Sta/Elev= 30
  4532.1  213.64  4534.2  213.64  4541.5  211.25  4552.1  209.59  4583.9  209.12
  4605.2   207.3  4620.9   207.6  4694.5  205.03  4721.8  204.84  4732.4  203.72
  4797.7  202.44  4838.4  200.28    4858  200.49  4870.2  199.25    4889  200.24
  4919.9  198.29    5028  198.78  5043.2  198.56  5047.1  197.66  5051.2  197.66
  5064.3  199.56  5070.2  198.96  5079.4  200.19  5121.6  200.36  5128.2     201
  5245.9  200.59  5390.4  200.07  5438.7  201.69  5526.4   202.1  5607.9  203.95
#Mann= 6 ,-1 , 0
  4532.1     .11       0  4694.5     .17       0  4797.7     .15       0
    4889     .06       0  5079.4     .11       0  5245.9     .17       0
Bank Sta=4889,5079.4
XS Rating Curve= 0 ,0
Exp/Cntr=0.3,0.1

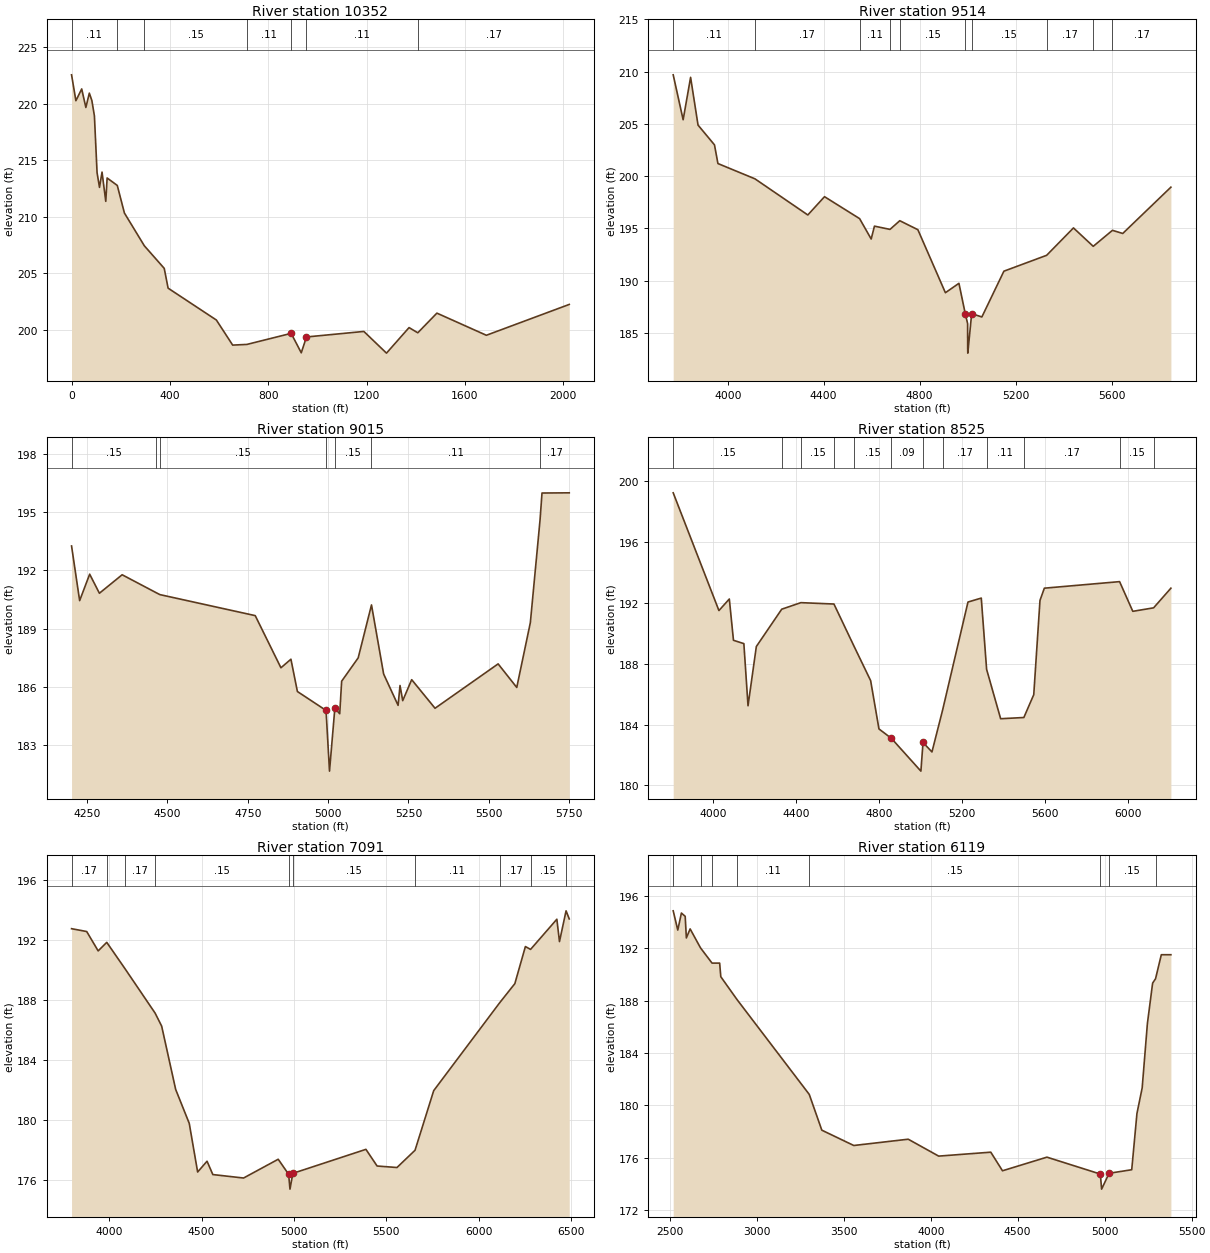
Type RM Length L Ch R = 1 ,10352   ,838,838,838
BEGIN DESCRIPTION:
LAKE CREEK TRIBUTARY NO. 12 18.0
END DESCRIPTION:
XS GIS Cut Line= 4
      3755967.85     10091661.07      3756856.09     10091892.51
      3757288.15     10091471.73      3757452.53     10090996.09
#Sta/Elev= 30
       0  222.55    17.7  220.26    41.3   221.3    58.2  219.66    72.3  220.93
    82.7  220.27      93  218.91   103.8  213.89   113.7  212.59     124  213.94
   139.2  211.35   144.7  213.42     186  212.76     215  210.32     296  207.42
     377  205.42   392.7  203.67     589  200.85   655.3  198.63     713  198.69
   893.1  199.67   934.3  197.95   955.5  199.35  1188.8  199.84  1280.9  197.92
  1372.7  200.18  1408.2  199.72  1485.9  201.46  1687.1   199.5  2024.2  202.23
#Mann= 7 ,-1 , 0
       0     .11       0     186     .17       0     296     .15       0
     713     .11       0   893.1     .06       0   955.5     .11       0
  1408.2     .17       0
Bank Sta=893.1,955.5
XS Rating Curve= 0 ,0
Exp/Cntr=0.3,0.1

Type RM Length L Ch R = 1 ,9514    ,499,499,499
BEGIN DESCRIPTION:
LAKE CREEK TRIBUTARY NO. 12 17.0
END DESCRIPTION:
XS GIS Cut Line= 3
      3755817.86     10092261.07      3757002.79     10092580.01
      3757586.15     10091965.51
#Sta/Elev= 30
  3772.9   209.7  3814.3   205.4  3845.4  209.46  3876.4  204.89  3944.9     203
  3959.3  201.21  4113.5  199.75    4334  196.29  4403.6  198.04  4549.8  195.94
  4598.1  193.99  4611.7  195.22  4676.5  194.91  4717.3  195.74  4792.7  194.88
  4907.4  188.85  4963.8  189.75 4990.72186.7854    5000   185.9  5000.3  183.57
  5000.7  183.07  5016.9  186.85  5059.4  186.53  5151.2  190.91  5329.4  192.43
  5441.2  195.05  5523.6  193.29  5603.7  194.82  5646.6  194.52  5847.3  198.95
#Mann= 10 ,-1 , 0
  3772.9     .11       0  4113.5     .17       0  4549.8     .11       0
  4676.5     .17       0  4717.3     .15       0 4990.72     .09       0
  5016.9     .15       0  5329.4     .17       0  5523.6     .15       0
  5603.7     .17       0
Bank Sta=4990.72,5016.9
XS Rating Curve= 0 ,0
Exp/Cntr=0.3,0.1

Type RM Length L Ch R = 1 ,9015    ,490,490,490
BEGIN DESCRIPTION:
LAKE CREEK TRIBUTARY NO. 12 16.0
END DESCRIPTION:
XS GIS Cut Line= 3
      3756472.02     10092980.28      3757262.34      10092865.6
      3757894.24     10092460.32
#Sta/Elev= 30
  4201.4  193.25  4226.6  190.44  4257.8   191.8  4288.1  190.82  4358.9  191.77
  4464.6  190.85  4476.4  190.75  4773.2  189.67  4853.2  186.99  4884.3  187.43
  4904.5  185.77  4993.6   184.8  5004.4  181.68    5021  184.91  5036.2  184.63
  5042.2   186.3  5093.7   187.5  5135.1  190.22  5172.9  186.67  5217.9  185.06
  5223.9  186.08  5232.3   185.3  5260.2  186.38  5332.9  184.91  5529.3  187.19
  5587.3  185.98  5629.6  189.31  5659.8  194.59  5665.9  195.97  5750.7  195.98
#Mann= 7 ,-1 , 0
  4201.4     .15       0  4464.6     .17       0  4476.4     .15       0
  4993.6     .09       0    5021     .15       0  5135.1     .11       0
  5659.8     .17       0
Bank Sta=4993.6,5021
XS Rating Curve= 0 ,0
Exp/Cntr=0.3,0.1

Type RM Length L Ch R = 1 ,8525    ,1434,1434,1434
BEGIN DESCRIPTION:
LAKE CREEK TRIBUTARY NO. 12 15.0
END DESCRIPTION:
XS GIS Cut Line= 3
      3756117.84     10093261.07      3757308.23     10093266.84
      3758310.43     10092599.07
#Sta/Elev= 30
  3809.6  199.21  4029.6  191.48  4079.6  192.24  4099.6  189.53  4149.6  189.31
  4169.6  185.23  4209.6  189.12  4331.7  191.57    4424     192    4583  191.91
  4677.5   189.2  4759.6  186.88  4799.6  183.71  4859.6  183.09  5001.4  180.94
  5011.6  182.82  5054.6   182.2  5105.7  184.94  5227.9  192.04  5291.9   192.3
  5317.6  187.62  5385.1  184.38  5496.8  184.46  5544.4  185.96  5574.4  192.15
  5595.4  192.95  5957.4  193.38    6021  191.43  6121.1  191.66  6204.3  192.95
#Mann= 12 ,-1 , 0
  3809.6     .15       0  4331.7     .17       0    4424     .15       0
    4583     .11       0  4677.5     .15       0  4859.6     .09       0
  5011.6     .15       0  5105.7     .17       0  5317.6     .11       0
  5496.8     .17       0  5957.4     .15       0  6121.1     .11       0
Bank Sta=4859.6,5011.6
XS Rating Curve= 0 ,0
Exp/Cntr=0.3,0.1

Type RM Length L Ch R = 1 ,7091    ,972,972,972
BEGIN DESCRIPTION:
LAKE CREEK TRIBUTARY NO. 12 14.0
END DESCRIPTION:
XS GIS Cut Line= 4
      3757867.85     10092961.08      3757348.23     10094046.84
      3756857.48     10094299.68      3756249.76     10093584.46
#Sta/Elev= 30
  3796.3  192.73  3878.4  192.54  3940.4  191.25  3986.9  191.82  4085.9  190.06
    4249   187.1  4284.1  186.24    4360  182.02  4433.5  179.76  4478.9  176.52
  4529.8  177.24  4561.2  176.35  4727.5  176.12  4915.1  177.37  4971.5  176.37
  4978.8  175.38  4994.2  176.43  5389.9  178.03  5450.4  176.92    5558  176.82
  5655.8  177.97  5756.8  181.94  6113.6  187.79  6196.1  189.07  6253.2  191.54
  6281.2  191.35  6423.5  193.36  6437.7  191.87  6473.4  193.92  6490.6  193.38
#Mann= 10 ,-1 , 0
  3796.3     .17       0  3986.9     .11       0  4085.9     .17       0
    4249     .15       0  4971.5     .09       0  4994.2     .15       0
  5655.8     .11       0  6113.6     .17       0  6281.2     .15       0
  6473.4     .17       0
Bank Sta=4971.5,4994.2
XS Rating Curve= 0 ,0
Exp/Cntr=0.3,0.1

Type RM Length L Ch R = 1 ,6119    ,485,485,485
BEGIN DESCRIPTION:
LAKE CREEK TRIBUTARY NO. 12 12.0
END DESCRIPTION:
XS GIS Cut Line= 5
      3756173.37     10093688.61       3756811.8     10094393.55
      3758007.59      10094230.5      3758078.23     10093926.84
      3758090.04     10093536.01
#Sta/Elev= 30
    2520  194.85  2546.3  193.38  2567.2  194.68  2588.9  194.43  2595.6  192.78
  2617.3  193.47  2677.1  192.02  2743.2  190.86  2786.9  190.86  2793.6  189.82
  2886.7  188.08    3302  180.84  3374.2  178.11  3557.9  176.94  3870.8  177.42
    4046  176.13  4345.4  176.43  4412.7  175.01  4668.1  176.05  4975.1  174.76
  4982.4  173.61  5025.5  174.82  5155.5  175.09  5185.5  179.38  5215.6  181.34
  5245.6  186.25  5275.6  189.33  5292.5  189.67  5325.6   191.5  5380.7   191.5
#Mann= 8 ,-1 , 0
    2520     .17       0  2677.1     .15       0  2743.2     .17       0
  2886.7     .11       0    3302     .15       0  4975.1     .09       0
  5025.5     .15       0  5292.5     .17       0
Bank Sta=4975.1,5025.5
XS Rating Curve= 0 ,0
Exp/Cntr=0.3,0.1

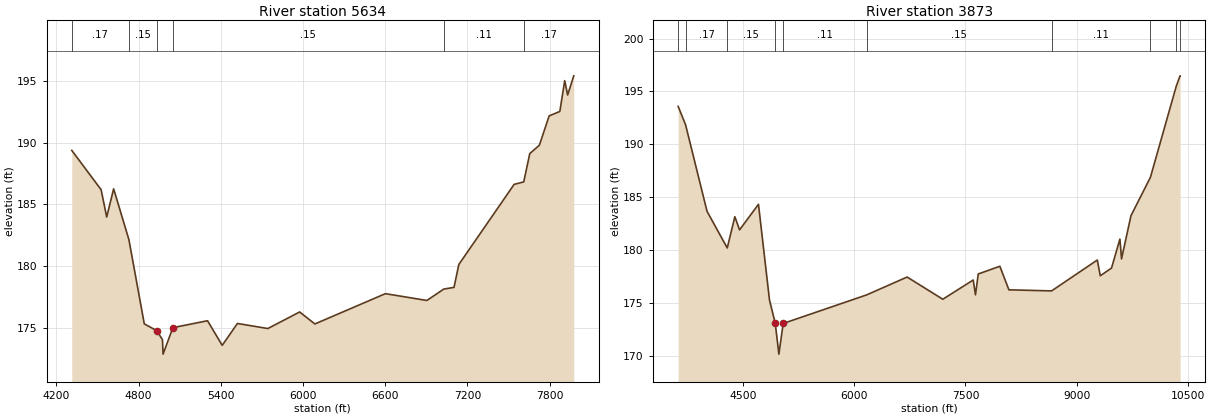
Type RM Length L Ch R = 1 ,5634    ,1761,1761,1761
BEGIN DESCRIPTION:
LAKE CREEK TRIBUTARY NO. 12 11.0
END DESCRIPTION:
XS GIS Cut Line= 5
      3758395.59     10093230.27      3758518.23     10093906.84
      3758407.71     10094238.97      3756741.88     10094466.49
      3756124.76     10093751.12
#Sta/Elev= 30
  4312.4  189.37  4526.6  186.19  4567.3  183.98  4618.1  186.26  4729.3  182.16
  4841.7  175.34  4933.2  174.78  4974.4  174.06  4978.8  172.89  5050.3  175.03
  5303.4  175.59  5410.4   173.6  5521.5  175.37  5743.5  174.96  5975.6   176.3
  6086.7  175.33  6601.4  177.78  6904.2  177.23  7027.3  178.15  7102.2  178.29
  7137.3  180.14    7541  186.62    7611  186.82  7655.1  189.11  7725.3  189.79
  7796.6  192.16  7874.5  192.52  7910.1  195.01  7931.5  193.85  7976.1   195.4
#Mann= 6 ,-1 , 0
  4312.4     .17       0  4729.3     .15       0  4933.2     .09       0
  5050.3     .15       0  7027.3     .11       0    7611     .17       0
Bank Sta=4933.2,5050.3
XS Rating Curve= 0 ,0
Exp/Cntr=0.3,0.1

Type RM Length L Ch R = 1 ,3873    ,0,0,0
BEGIN DESCRIPTION:
LAKE CREEK TRIBUTARY NO. 12 7.0
END DESCRIPTION:
XS GIS Cut Line= 6
      3759042.84     10092836.06      3760028.23     10093786.84
      3760394.94     10094321.02      3759592.85     10094636.07
      3756722.64     10094537.54      3756055.35     10093778.94
#Sta/Elev= 30
  3630.7  193.59  3730.6  191.86  4019.7  183.67  4292.1   180.2  4394.5  183.16
    4458  181.91  4712.7  184.33  4861.2  175.27 4938.34173.0872  4987.6  170.16
  5045.5  173.06    6169  175.76  6714.8  177.45  7195.1  175.35  7605.3  177.17
  7635.3  175.77  7672.9  177.74  7963.8  178.47  8085.6  176.24  8661.1  176.14
  9276.3  179.06  9316.3  177.57  9467.8   178.3  9580.7  181.04  9602.5  179.17
  9729.6  183.25  9991.6  186.88 10339.2  195.49 10390.9  196.48 10391.9  196.47
#Mann= 10 ,-1 , 0
  3630.7     .15       0  3730.6     .17       0  4292.1     .15       0
 4938.34     .06       0  5045.5     .11       0    6169     .15       0
  8661.1     .11       0  9991.6     .17       0 10339.2     .11       0
 10390.9     .15       0
Bank Sta=4938.34,5045.5
XS Rating Curve= 0 ,0
Exp/Cntr=0.3,0.1

Chan Stop Cuts=-1
Use User Specified Reach Order=0
Composite Channel Slope=5