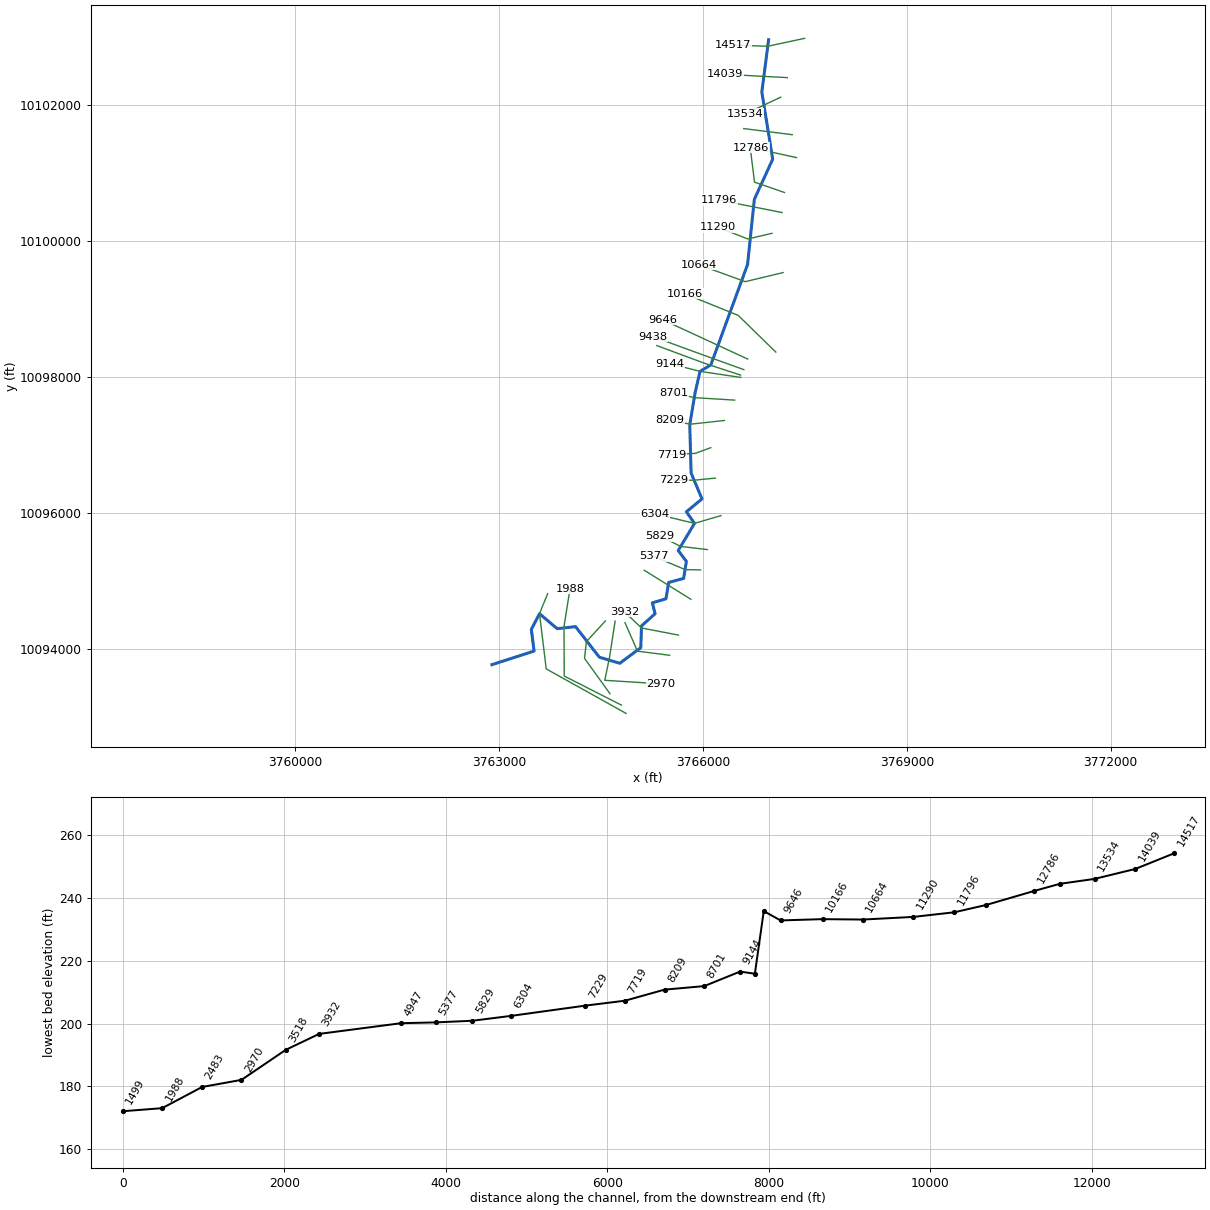
--- LAKE CREEK TRIBUTARY NO 13 A.prj (project) ---

Proj Title=LAKE CREEK TRIBUTARY NO 13 A Base Level Engineering
Current Plan=p01
Default Exp/Contr=0.3,0.1
English Units
Geom File=g01
Flow File=f01
Flow File=f02
Plan File=p01
Y Axis Title=Elevation
X Axis Title(PF)=Main Channel Distance
X Axis Title(XS)=Station
BEGIN DESCRIPTION:
LAKE CREEK TRIBUTARY NO 13 A
END DESCRIPTION:
DSS Export Rating Curves= 0
DSS Export Rating Curve Sorted= 0
DSS Export Volume Flow Curves= 0
DXF OffsetX= 0
DXF OffsetY= 0
DXF ScaleX= 1
DXF ScaleY= 10

--- LAKE CREEK TRIBUTARY NO 13 A.p01 (plan) ---

Plan Title=Multiple Run
Short Identifier=Multiple
Geom File=g01
Flow File=f01
Subcritical Flow
K Sum by GR= 0
Std Step Tol= 0.01
Critical Tol= 0.01
Num of Std Step Trials= 20
Max Error Tol= 0.3
Flow Tol Ratio= 0.001
Split Flow NTrial= 30
Split Flow Tol= 0.02
Split Flow Ratio= 0.02
Log Output Level= 0
Friction Slope Method= 1
Unsteady Friction Slope Method= 2
Unsteady Bridges Friction Slope Method= 1
Parabolic Critical Depth
Global Vel Dist=  1 , 1 , 1
Global Log Level= 0
CheckData=True
Encroach Param= -1, 0, 0, 0
BEGIN DESCRIPTION:
Multiple Run
END DESCRIPTION:

--- LAKE CREEK TRIBUTARY NO 13 A.f01 (steady flow) ---

Flow Title=Multiple
Program Version=4.10
Number of Profiles= 7
Profile Names=10-year,25-year,50-year,1pct_min,100-year,1pct_plu,500-year
River Rch & RM=LAKE CREEK TRIBU,Reach-1         ,14517
     617     829    1114     492    1487    4491    2742
River Rch & RM=LAKE CREEK TRIBU,Reach-1         ,9328
     698     947    1279     569    1717    5185    3201
River Rch & RM=LAKE CREEK TRIBU,Reach-1         ,6304
     773    1052    1425     635    1918    5792    3588
Boundary for River Rch & Prof#=LAKE CREEK TRIBU,Reach-1         , 1
Up Type= 0
Dn Type= 3
Dn Slope=0.005
Boundary for River Rch & Prof#=LAKE CREEK TRIBU,Reach-1         , 2
Up Type= 0
Dn Type= 3
Dn Slope=0.005
Boundary for River Rch & Prof#=LAKE CREEK TRIBU,Reach-1         , 3
Up Type= 0
Dn Type= 3
Dn Slope=0.005
Boundary for River Rch & Prof#=LAKE CREEK TRIBU,Reach-1         , 4
Up Type= 0
Dn Type= 3
Dn Slope=0.005
Boundary for River Rch & Prof#=LAKE CREEK TRIBU,Reach-1         , 5
Up Type= 0
Dn Type= 3
Dn Slope=0.005
Boundary for River Rch & Prof#=LAKE CREEK TRIBU,Reach-1         , 6
Up Type= 0
Dn Type= 3
Dn Slope=0.005
Boundary for River Rch & Prof#=LAKE CREEK TRIBU,Reach-1         , 7
Up Type= 0
Dn Type= 3
Dn Slope=0.005
DSS Import GetInterval= 0
DSS Import GetPeak= 0
DSS Import FillOption= 0

--- LAKE CREEK TRIBUTARY NO 13 A.f02 (steady flow) ---

Flow Title=Orig_BLE_Flows
Program Version=4.10
Number of Profiles= 7
Profile Names=10-year,25-year,50-year,1pct_min,100-year,1pct_plu,500-year
River Rch & RM=LAKE CREEK TRIBU,Reach-1         ,14517
     617     813     969     379    1144    3456    1594
River Rch & RM=LAKE CREEK TRIBU,Reach-1         ,9328
     698     928    1112     437    1321    3989    1861
River Rch & RM=LAKE CREEK TRIBU,Reach-1         ,6304
     773    1031    1239     488    1475    4454    2086
Boundary for River Rch & Prof#=LAKE CREEK TRIBU,Reach-1         , 1
Up Type= 0
Dn Type= 3
Dn Slope=0.005
Boundary for River Rch & Prof#=LAKE CREEK TRIBU,Reach-1         , 2
Up Type= 0
Dn Type= 3
Dn Slope=0.005
Boundary for River Rch & Prof#=LAKE CREEK TRIBU,Reach-1         , 3
Up Type= 0
Dn Type= 3
Dn Slope=0.005
Boundary for River Rch & Prof#=LAKE CREEK TRIBU,Reach-1         , 4
Up Type= 0
Dn Type= 3
Dn Slope=0.005
Boundary for River Rch & Prof#=LAKE CREEK TRIBU,Reach-1         , 5
Up Type= 0
Dn Type= 3
Dn Slope=0.005
Boundary for River Rch & Prof#=LAKE CREEK TRIBU,Reach-1         , 6
Up Type= 0
Dn Type= 3
Dn Slope=0.005
Boundary for River Rch & Prof#=LAKE CREEK TRIBU,Reach-1         , 7
Up Type= 0
Dn Type= 3
Dn Slope=0.005
DSS Import GetInterval= 0
DSS Import GetPeak= 0
DSS Import FillOption= 0

--- LAKE CREEK TRIBUTARY NO 13 A.g01 (geometry) ---

Geom Title=Existing Conditions
Program Version=4.10

River Reach=LAKE CREEK TRIBU,Reach-1
Reach XY= 30
      3766968.23     10102966.84      3766868.23     10102196.84
      3767028.23     10101206.84      3766758.23     10100616.84
      3766658.23     10099656.84      3766118.42     10098179.68
      3765958.91     10098084.22      3765888.23     10097776.84
      3765808.23     10097296.84      3765828.23     10096586.84
      3765988.23     10096206.84      3765758.23     10096016.84
      3765878.23     10095846.84      3765638.23     10095446.84
      3765758.23     10095286.84      3765718.23     10095036.84
      3765498.23     10094976.84      3765458.23     10094736.84
      3765258.23     10094676.84      3765298.23     10094516.84
      3765098.23     10094336.84      3765088.23     10094016.84
      3764778.23     10093786.84      3764478.23     10093876.84
      3764128.23     10094326.84      3763858.23     10094296.84
      3763598.23     10094516.84      3763478.23     10094286.84
      3763518.23     10093966.84      3762898.23     10093766.84

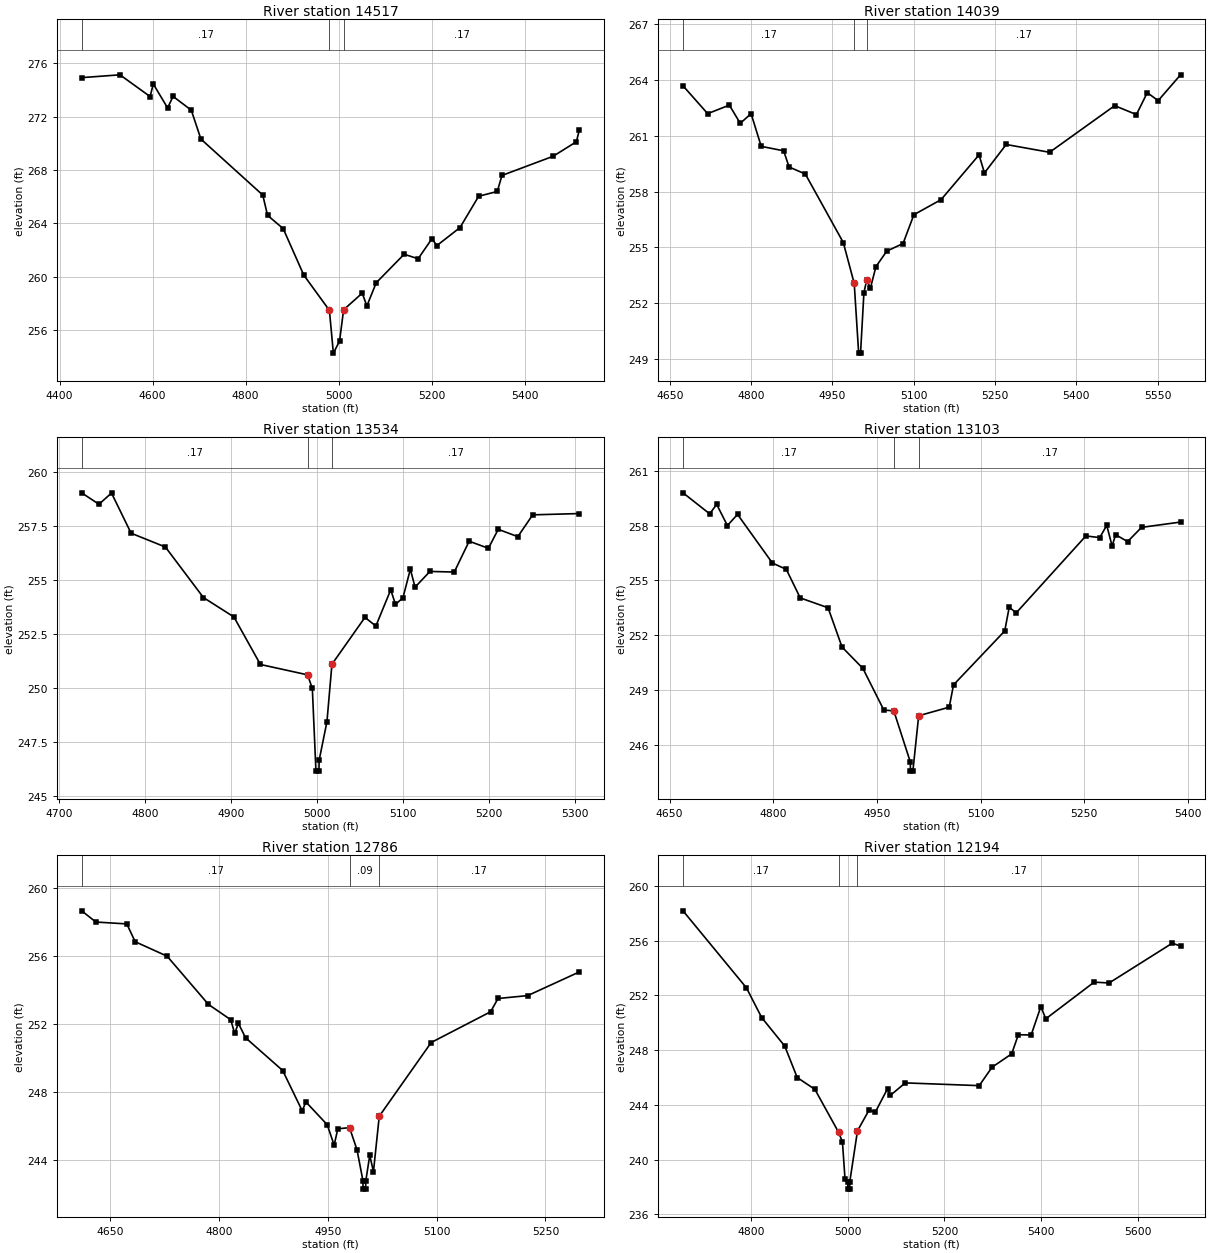
Type RM Length L Ch R = 1 ,14517   ,478,478,478
BEGIN DESCRIPTION:
LAKE CREEK TRIBUTARY NO. 13 A 14.0
END DESCRIPTION:
XS GIS Cut Line= 3
      3767498.32     10102986.55      3766956.61     10102870.22
       3766441.9     10102885.82
#Sta/Elev= 30
  4447.6  274.94  4529.9  275.15  4594.6  273.52  4601.5  274.46  4632.2  272.67
    4644  273.53  4683.1   272.5  4703.8  270.33  4836.7  266.13    4847  264.61
  4880.6  263.61  4924.9  260.12  4979.9  257.48  4988.4  254.27  5001.7  255.17
  5010.4  257.52  5050.4  258.77  5060.4  257.81  5080.5  259.55  5140.5  261.69
  5170.5  261.35  5200.5  262.87  5210.5  262.33  5260.5  263.69  5300.6  266.04
  5340.6   266.4  5350.6   267.6  5460.6  269.04  5510.6  270.13  5516.6  270.98
#Mann= 3 , 0 , 0
  4447.6     .17       0  4979.9     .09       0  5010.4     .17       0
Bank Sta=4979.9,5010.4
XS Rating Curve= 0 ,0
Exp/Cntr=0.3,0.1

Type RM Length L Ch R = 1 ,14039   ,505,505,505
BEGIN DESCRIPTION:
Mapping XS e0bcd2d7
END DESCRIPTION:
XS GIS Cut Line= 2
      3767243.27     10102408.24      3766326.56     10102456.85
#Sta/Elev= 30
  4674.5   263.7    4720   262.2    4760  262.66  4780.1  261.68  4800.1   262.2
  4818.8  260.44  4860.2   260.2  4870.2  259.33  4900.2  258.95  4970.3  255.26
  4990.4  253.06  4998.6  249.31  5002.1  249.31  5008.3  252.57  5013.3  253.22
  5020.4  252.82  5030.4  253.96  5050.4   254.8  5080.5  255.21  5100.5  256.76
  5150.6  257.57  5220.7  259.98  5230.7  259.01  5270.8  260.54  5350.9  260.12
    5471  262.63  5511.1  262.15  5531.1  263.33  5551.2   262.9  5592.5  264.29
#Mann= 3 , 0 , 0
  4674.5     .17       0  4990.4     .09       0  5013.3     .17       0
Bank Sta=4990.4,5013.3
XS Rating Curve= 0 ,0
Exp/Cntr=0.3,0.1

Type RM Length L Ch R = 1 ,13534   ,431,431,431
BEGIN DESCRIPTION:
Mapping XS ce6f5243
END DESCRIPTION:
XS GIS Cut Line= 2
      3767146.01     10102120.04      3766622.31      10101873.8
#Sta/Elev= 30
  4726.2  259.03  4746.3   258.5  4760.9  259.02  4783.7  257.16  4823.6  256.52
  4867.8  254.18  4903.3  253.28  4934.1  251.08  4988.9   250.6  4994.5  249.97
  4998.7  246.14  5002.2  246.14  5002.4  246.64  5011.5  248.43  5017.3  251.09
  5055.7  253.26  5068.4  252.86  5085.7  254.54  5091.2  253.86  5099.9  254.17
  5108.5  255.49    5114  254.66  5131.3  255.39  5159.6  255.36  5176.9  256.79
  5199.3  256.46  5210.7  257.34  5233.5     257  5250.8  258.01  5304.9  258.07
#Mann= 3 , 0 , 0
  4726.2     .17       0  4988.9     .09       0  5017.3     .17       0
Bank Sta=4988.9,5017.3
XS Rating Curve= 0 ,0
Exp/Cntr=0.3,0.1

Type RM Length L Ch R = 1 ,13103   ,317,317,317
BEGIN DESCRIPTION:
Mapping XS 06480fe1
END DESCRIPTION:
XS GIS Cut Line= 2
      3767316.13     10101567.97       3766601.9     10101658.11
#Sta/Elev= 30
  4669.5  259.79  4708.1  258.64  4718.2  259.16  4733.7     258  4748.4  258.61
  4798.8  255.95    4819   255.6  4839.1  254.04  4879.4   253.5  4899.6  251.35
  4929.8  250.18  4960.1   247.9  4974.5  247.86  4998.4  245.06  4998.6  244.56
  5002.1  244.56  5010.5  247.59  5054.7  248.06  5060.9  249.28    5135  252.23
  5141.5  253.53  5151.6  253.22  5252.4  257.43  5272.5  257.34  5282.6  258.01
  5290.4  256.88  5295.5   257.5  5312.8  257.12    5333   257.9  5389.4  258.19
#Mann= 3 , 0 , 0
  4669.5     .17       0  4974.5     .09       0  5010.5     .17       0
Bank Sta=4974.5,5010.5
XS Rating Curve= 0 ,0
Exp/Cntr=0.3,0.1

Type RM Length L Ch R = 1 ,12786   ,592,592,592
BEGIN DESCRIPTION:
Mapping XS 3f6824e2
END DESCRIPTION:
XS GIS Cut Line= 2
      3767378.63     10101231.17      3766708.51     10101376.99
#Sta/Elev= 30
  4610.7  258.67  4630.3  258.01  4672.9   257.9  4684.5  256.85  4728.5     256
  4785.5  253.16  4816.2  252.26  4821.6  251.45  4826.7  252.05  4836.6   251.2
  4887.8  249.27  4914.7   246.9  4919.8  247.42  4949.2  246.08  4958.7  244.88
  4963.8  245.84  4979.9  245.91  4990.2  244.61  4998.4  242.79  4998.6  242.29
  5002.1  242.29  5002.4  242.79  5007.8  244.28  5012.9  243.32  5020.9  246.58
  5092.5  250.92  5174.4  252.73  5184.6  253.51  5225.5  253.68  5296.5  255.07
#Mann= 3 , 0 , 0
  4610.7     .17       0  4979.9     .09       0  5020.9     .17       0
Bank Sta=4979.9,5020.9
XS Rating Curve= 0 ,0
Exp/Cntr=0.3,0.1

Type RM Length L Ch R = 1 ,12194   ,398,398,398
BEGIN DESCRIPTION:
Mapping XS c7a29684
END DESCRIPTION:
XS GIS Cut Line= 3
       3767201.6     10100717.26      3766760.61     10100870.05
      3766691.35     10101427.55
#Sta/Elev= 30
  4659.7  258.17  4790.7  252.55  4822.4  250.37    4870  248.29  4895.8  245.99
  4932.3  245.13  4981.2     242  4989.3  241.28  4994.6  238.58  5000.3  238.34
  5000.6  237.84  5004.1  237.84  5004.3  238.34  5020.4   242.1  5044.7  243.64
  5056.9  243.44  5082.7  245.19    5088  244.68  5119.2   245.6    5272   245.4
  5298.7  246.75  5339.1  247.72  5352.9  249.12  5379.4   249.1  5399.5  251.18
  5409.6  250.28  5509.6  252.96  5540.6   252.9  5671.3  255.81  5688.2  255.59
#Mann= 3 , 0 , 0
  4659.7     .17       0  4981.2     .09       0  5020.4     .17       0
Bank Sta=4981.2,5020.4
XS Rating Curve= 0 ,0
Exp/Cntr=0.3,0.1

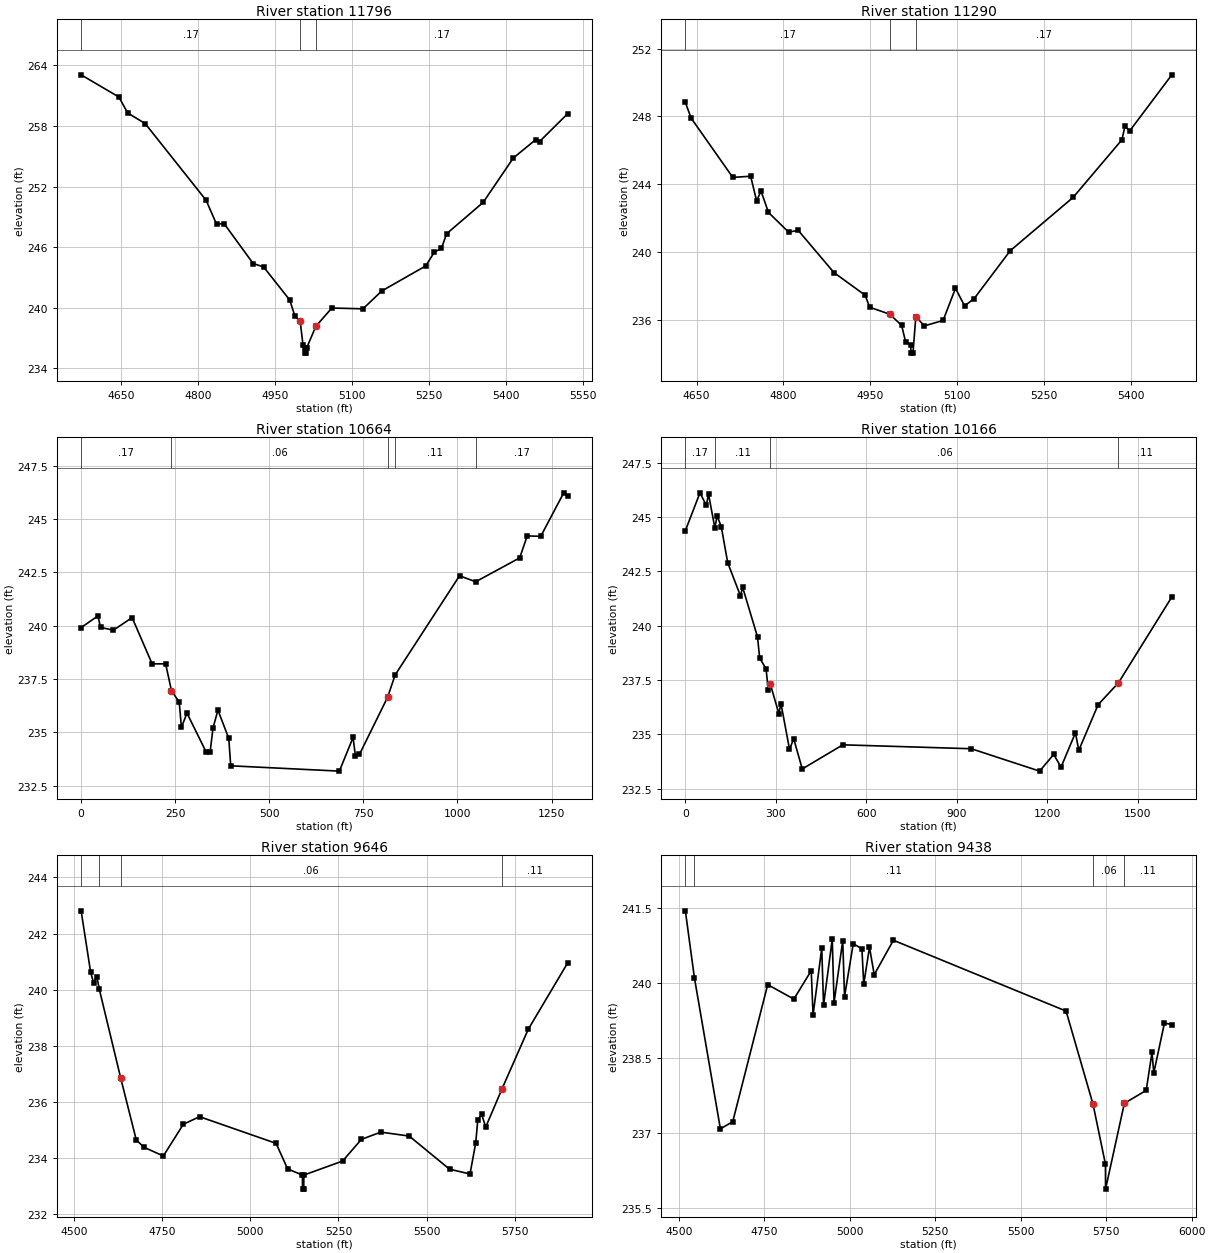
Type RM Length L Ch R = 1 ,11796   ,506,506,506
BEGIN DESCRIPTION:
Mapping XS 7fc82279
END DESCRIPTION:
XS GIS Cut Line= 2
      3767166.88     10100422.12       3766236.5     10100606.12
#Sta/Elev= 30
  4571.6  263.07  4645.3  260.87  4662.4  259.29  4696.5  258.24  4815.3  250.64
  4835.6  248.27  4850.3  248.33    4907  244.37  4927.4  244.03  4978.4  240.75
  4988.6  239.12  4998.7  238.65  5004.1  236.33  5007.2  235.99  5007.4  235.49
  5010.9  235.49  5011.2  235.99  5029.3  238.15  5060.4  239.96  5121.1  239.88
  5157.8  241.65  5243.4  244.13  5260.4  245.51    5274  245.86  5284.2  247.32
  5355.5  250.43  5414.1  254.82  5457.5  256.63  5465.4  256.46    5520  259.21
#Mann= 3 , 0 , 0
  4571.6     .17       0  4998.7     .09       0  5029.3     .17       0
Bank Sta=4998.7,5029.3
XS Rating Curve= 0 ,0
Exp/Cntr=0.3,0.1

Type RM Length L Ch R = 1 ,11290   ,626,626,626
BEGIN DESCRIPTION:
Mapping XS 9ac98535
END DESCRIPTION:
XS GIS Cut Line= 3
      3767017.58     10100116.58      3766663.38     10100033.24
      3766219.98     10100206.45
#Sta/Elev= 30
  4630.6  248.83  4640.6   247.9  4712.5   244.4  4743.3  244.47  4753.6  243.02
  4761.3  243.59  4774.1  242.33  4808.8  241.17  4825.5  241.27  4887.1  238.78
    4941  237.44  4948.8  236.73  4983.4  236.32    5004  235.66  5011.1  234.65
  5019.9  234.52  5020.1  234.02  5023.6  234.02  5028.5  236.17  5043.3  235.63
  5075.6  235.95    5097  237.85  5112.7  236.81  5129.2  237.24  5191.5  240.07
  5300.1  243.22  5384.3  246.62  5389.6  247.42  5397.6  247.14  5470.5  250.46
#Mann= 3 , 0 , 0
  4630.6     .17       0  4983.4     .09       0  5028.5     .17       0
Bank Sta=4983.4,5028.5
XS Rating Curve= 0 ,0
Exp/Cntr=0.3,0.1

Type RM Length L Ch R = 1 ,10664   ,498,498,498
BEGIN DESCRIPTION:
Mapping XS fe8b66e1
END DESCRIPTION:
XS GIS Cut Line= 3
      3767181.33     10099538.56      3766625.19     10099404.77
      3765948.11      10099651.3
#Sta/Elev= 30
       0  239.91    44.7  240.46    51.6  239.92    85.9  239.79   135.5  240.38
   188.7  238.21   224.6  238.21   240.1  236.95   260.7  236.42   266.5  235.23
   281.3   235.9   332.7  234.06     343   234.1   350.4   235.2   363.6  236.04
   392.4  234.71   397.5  233.43   686.2  233.18   722.7  234.76   728.8   233.9
   739.5  233.96   814.5  236.65   834.4  237.69  1005.5  242.34  1048.4  242.06
  1165.4  243.18  1185.4  244.21  1221.3  244.19  1282.4  246.23  1292.6  246.07
#Mann= 5 ,-1 , 0
       0     .17       0   240.1     .06       0   814.5     .15       0
   834.4     .11       0  1048.4     .17       0
Bank Sta=240.1,814.5
XS Rating Curve= 0 ,0
Exp/Cntr=0.3,0.1

Type RM Length L Ch R = 1 ,10166   ,520,520,520
BEGIN DESCRIPTION:
Mapping XS 4da015eb
END DESCRIPTION:
XS GIS Cut Line= 3
      3767073.69     10098368.42      3766521.02     10098908.24
      3765739.77     10099224.21
#Sta/Elev= 30
       0  244.37    48.5  246.11    69.6  245.53    76.8  246.05    97.9  244.49
   105.1  245.05   119.2  244.55   140.4   242.9   182.8  241.37   189.9  241.77
   239.4  239.48   246.4  238.51   267.7  238.02   274.7  237.06   281.8  237.31
   310.1  235.96   317.1  236.42   345.4  234.32   359.5  234.79   387.8  233.41
   522.3  234.52   948.3  234.34  1175.1  233.31  1221.9  234.08    1246  233.49
  1293.8  235.07  1305.1  234.27  1369.3  236.37  1436.5  237.37  1613.6  241.32
#Mann= 4 ,-1 , 0
       0     .17       0    97.9     .11       0   281.8     .06       0
  1436.5     .11       0
Bank Sta=281.8,1436.5
XS Rating Curve= 0 ,0
Exp/Cntr=0.3,0.1

Type RM Length L Ch R = 1 ,9646    ,208,208,208
BEGIN DESCRIPTION:
Mapping XS fe9b5edc
END DESCRIPTION:
XS GIS Cut Line= 2
      3766659.95     10098265.86      3765406.47     10098845.73
#Sta/Elev= 30
  4519.3  242.81  4546.4  240.62  4554.7  240.25  4563.8  240.47  4571.1  240.01
  4631.8  236.85  4675.9  234.65  4697.9  234.39  4752.7  234.08  4809.6  235.21
  4855.5  235.48  5072.8  234.53  5105.6  233.62  5147.6   233.4  5147.9   232.9
  5151.4   232.9  5151.6   233.4  5261.7   233.9  5314.9  234.67    5370  234.93
  5450.7  234.79  5565.3  233.61  5623.4  233.44  5639.6  234.54  5645.5  235.37
  5656.5  235.56    5668  235.11  5713.9  236.46  5788.7  238.59  5900.4  240.95
#Mann= 4 ,-1 , 0
  4519.3     .17       0  4571.1     .11       0  4631.8     .06       0
  5713.9     .11       0
Bank Sta=4631.8,5713.9
XS Rating Curve= 0 ,0
Exp/Cntr=0.3,0.1

Type RM Length L Ch R = 1 ,9438    ,110,110,110
BEGIN DESCRIPTION:
Mapping XS 35ca2c95
END DESCRIPTION:
XS GIS Cut Line= 3
      3766604.39     10098109.62      3765958.52     10098342.27
      3765267.54     10098595.75
#Sta/Elev= 30
  4519.5  241.45  4545.9  240.11  4621.9  237.08  4657.9  237.22  4760.3  239.97
  4836.8  239.68  4887.6  240.25  4892.9  239.36  4918.3   240.7  4923.6  239.56
    4949  240.88  4954.3  239.61  4979.7  240.85    4985  239.73  5010.4  240.79
  5035.7  240.69  5041.1  239.98  5057.9  240.72  5071.8  240.17  5127.8  240.86
  5632.8  239.44  5711.7  237.57  5747.9  236.37  5748.2  235.87  5803.2  237.59
  5867.1  237.85    5884  238.61  5889.3   238.2  5920.4   239.2    5942  239.17
#Mann= 4 ,-1 , 0
  4519.5     .17       0  4545.9     .11       0  5711.7     .06       0
  5803.2     .11       0
Bank Sta=5711.7,5803.2
XS Rating Curve= 0 ,0
Exp/Cntr=0.3,0.1

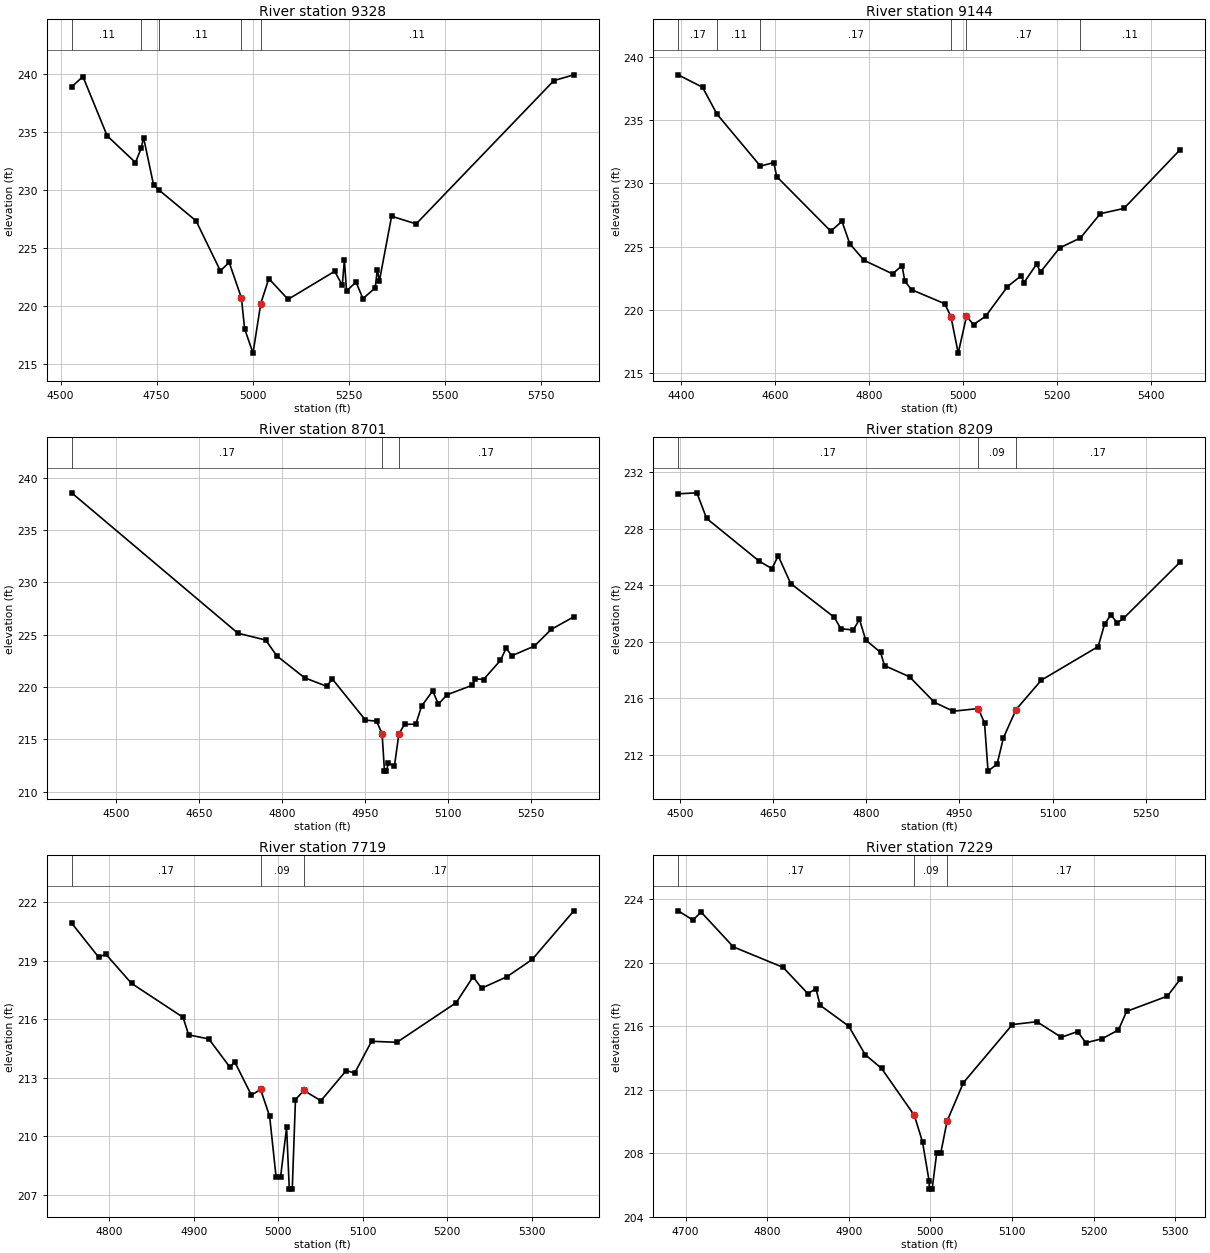
Type RM Length L Ch R = 1 ,9328    ,184,184,184
BEGIN DESCRIPTION:
Mapping XS 79d822d1
END DESCRIPTION:
XS GIS Cut Line= 3
      3766555.71     10098029.78      3766034.91     10098199.91
      3765323.14     10098463.79
#Sta/Elev= 30
  4528.8  238.88  4558.1  239.77  4621.2  234.66  4694.9  232.35    4710  233.61
  4715.9  234.51  4742.2  230.39  4755.8  229.99  4852.7  227.32  4915.8  223.01
  4938.8  223.74  4970.7  220.66  4978.9  218.02  5000.8  215.91    5021  220.19
    5042  222.34    5092  220.55  5213.5  222.97  5233.2  221.76  5238.6  223.94
  5244.2  221.27  5268.9  222.04  5286.9  220.61  5318.8  221.54  5324.4  223.12
  5329.7  222.13  5361.5  227.72  5425.5  227.06  5783.8  239.42  5835.8  239.92
#Mann= 5 ,-1 , 0
  4528.8     .11       0    4710     .17       0  4755.8     .11       0
  4970.7     .06       0    5021     .11       0
Bank Sta=4970.7,5021
XS Rating Curve= 0 ,0
Exp/Cntr=0.3,0.1

Type RM Length L Ch R = 1 ,9144    ,443,443,443
BEGIN DESCRIPTION:
LAKE CREEK TRIBUTARY NO. 13 A 13.0
END DESCRIPTION:
XS GIS Cut Line= 3
      3766559.22     10097995.05      3765958.91     10098084.22
      3765511.76     10098199.61
#Sta/Elev= 30
  4393.1  238.56    4445  237.58  4475.9  235.45  4568.2  231.35  4596.7  231.63
    4603  230.52    4718  226.21  4741.8  226.99  4758.4  225.22  4788.8  223.91
  4849.4  222.84  4869.6  223.49  4875.6  222.26  4889.9  221.59  4960.6  220.48
 4973.69219.4596  4989.2  216.58  5006.8  219.48  5021.8  218.84  5047.5  219.49
    5094  221.83  5123.7  222.71  5128.8  222.13    5156  223.61  5164.3  222.99
    5205  224.89  5249.3  225.68  5291.5  227.59  5341.9  228.01  5461.8  232.66
#Mann= 6 ,-1 , 0
  4393.1     .17       0  4475.9     .11       0  4568.2     .17       0
 4973.69     .09       0  5006.8     .17       0  5249.3     .11       0
Bank Sta=4973.69,5006.8
XS Rating Curve= 0 ,0
Exp/Cntr=0.3,0.1

Type RM Length L Ch R = 1 ,8701    ,492,492,492
BEGIN DESCRIPTION:
LAKE CREEK TRIBUTARY NO. 13 A 12.0
END DESCRIPTION:
XS GIS Cut Line= 3
      3766467.83     10097661.07      3765888.23     10097696.84
      3765567.81     10097761.08
#Sta/Elev= 30
  4419.3  238.54  4719.8  225.13  4769.9  224.48    4790  222.97  4840.1  220.88
  4880.2  220.06  4890.2  220.77  4950.3  216.83  4970.3  216.73  4980.3  215.53
  4984.6  211.96  4988.1  211.96  4991.4  212.69  5002.7  212.48  5010.6  215.51
  5020.8  216.43  5041.2  216.44  5051.7  218.17  5071.8  219.63    5082  218.35
  5097.5  219.25  5143.2  220.16  5148.5  220.78  5163.6  220.71  5194.2  222.54
  5204.5   223.7  5214.6  222.98  5255.4   223.9    5286   225.5  5326.8   226.7
#Mann= 3 , 0 , 0
  4419.3     .17       0  4980.3     .09       0  5010.6     .17       0
Bank Sta=4980.3,5010.6
XS Rating Curve= 0 ,0
Exp/Cntr=0.3,0.1

Type RM Length L Ch R = 1 ,8209    ,490,490,490
BEGIN DESCRIPTION:
LAKE CREEK TRIBUTARY NO. 13 A 11.0
END DESCRIPTION:
XS GIS Cut Line= 3
       3766317.9     10097361.08      3765818.23     10097306.84
      3765517.89     10097361.07
#Sta/Elev= 30
  4497.4  230.46  4527.6  230.53  4543.2  228.72  4628.2  225.68  4648.3  225.17
  4658.4  226.07  4678.5  224.11  4748.9  221.71    4759  220.91  4779.1  220.82
  4789.1  221.57  4799.2  220.11  4823.1  219.23  4829.4   218.3  4869.6  217.51
  4909.7   215.7    4940  215.07  4980.3  215.26  4990.3  214.23  4995.9  210.83
  5010.5  211.33  5020.7  213.19    5041  215.19  5081.7  217.27  5173.1  219.65
  5183.3  221.22  5193.5   221.9  5203.6  221.32  5213.8  221.64  5305.2  225.64
#Mann= 3 , 0 , 0
  4497.4     .17       0  4980.3     .09       0    5041     .17       0
Bank Sta=4980.3,5041
XS Rating Curve= 0 ,0
Exp/Cntr=0.3,0.1

Type RM Length L Ch R = 1 ,7719    ,490,490,490
BEGIN DESCRIPTION:
LAKE CREEK TRIBUTARY NO. 13 A 10.0
END DESCRIPTION:
XS GIS Cut Line= 3
      3766117.87     10096961.08      3765888.23     10096876.84
      3765538.74     10096857.98
#Sta/Elev= 30
  4755.4  220.94  4787.4  219.19  4795.8  219.35  4826.3  217.85  4887.3  216.11
  4893.9  215.21  4917.8     215    4943  213.54  4948.3  213.84  4968.2  212.12
  4979.1  212.41  4989.8  211.04  4997.5   207.9  5002.7   207.9  5009.9  210.46
  5013.1   207.3  5016.6   207.3  5020.4  211.89  5030.4  212.36  5050.5  211.83
  5080.5  213.38  5090.5  213.25  5110.5  214.88  5140.6  214.83  5210.7  216.86
  5230.7  218.19  5240.7   217.6  5270.8  218.19  5300.8  219.08    5350  221.57
#Mann= 3 , 0 , 0
  4755.4     .17       0  4979.1     .09       0  5030.4     .17       0
Bank Sta=4979.1,5030.4
XS Rating Curve= 0 ,0
Exp/Cntr=0.3,0.1

Type RM Length L Ch R = 1 ,7229    ,925,925,925
BEGIN DESCRIPTION:
LAKE CREEK TRIBUTARY NO. 13 A 9.0
END DESCRIPTION:
XS GIS Cut Line= 3
      3766185.95     10096513.13      3765868.26     10096481.88
      3765572.08     10096481.88
#Sta/Elev= 30
  4690.8  223.26    4709  222.68    4719  223.18  4758.5  220.99  4819.5   219.7
  4849.7  218.05  4859.7  218.35  4864.9  217.31  4899.9     216    4920  214.21
  4940.1  213.34  4980.3  210.38  4990.3  208.71  4998.4  206.24  4998.6  205.74
  5002.1  205.74  5007.7  208.02  5012.7  208.02  5020.4  210.02  5040.4  212.44
  5100.4   216.1  5130.4  216.28  5160.4   215.3  5180.4  215.66  5190.4  214.95
  5210.4  215.21  5230.4  215.76  5240.4  216.93  5290.4  217.89  5306.2  218.96
#Mann= 3 , 0 , 0
  4690.8     .17       0  4980.3     .09       0  5020.4     .17       0
Bank Sta=4980.3,5020.4
XS Rating Curve= 0 ,0
Exp/Cntr=0.3,0.1

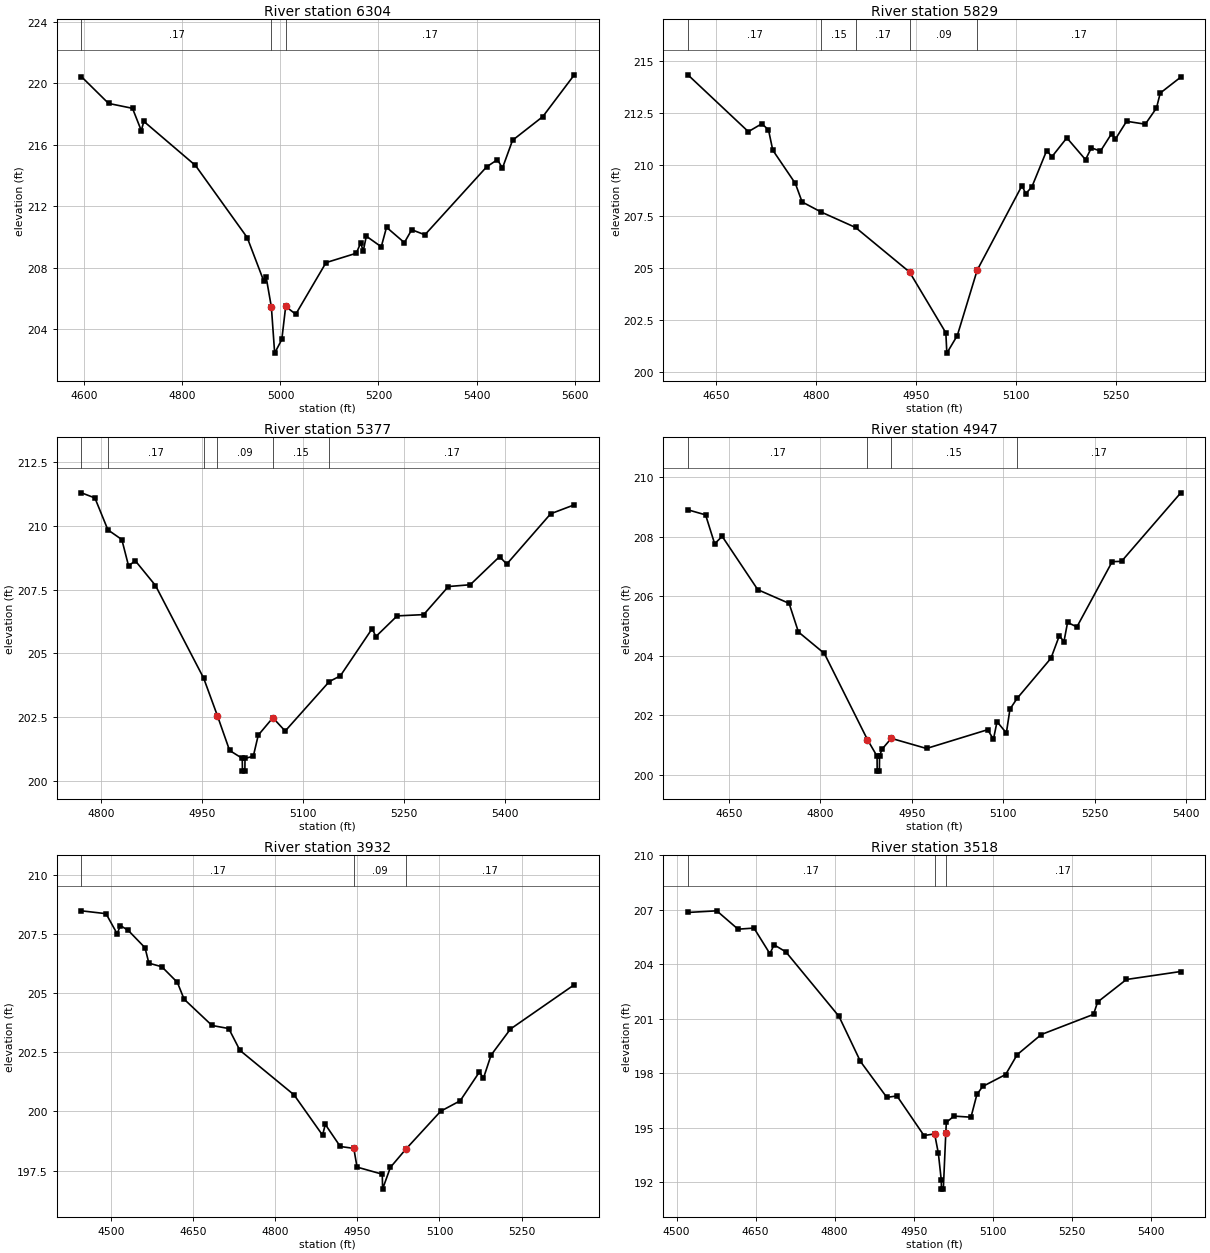
Type RM Length L Ch R = 1 ,6304    ,475,475,475
BEGIN DESCRIPTION:
LAKE CREEK TRIBUTARY NO. 13 A 8.0
END DESCRIPTION:
XS GIS Cut Line= 3
      3766267.83     10095961.07      3765878.23     10095846.84
      3765295.36     10095987.08
#Sta/Elev= 30
    4594  220.44  4649.3   218.7  4698.2  218.38  4716.1  216.93  4721.3  217.53
  4826.7  214.66  4932.2  209.97  4965.6  207.17  4970.8   207.4 4981.51205.4457
  4988.2  202.45  5002.8  203.34  5010.7  205.49  5031.2  204.98    5093  208.34
  5154.7  208.95  5163.7  209.62  5168.9  209.09  5175.2  210.06  5205.7  209.37
  5216.4  210.64  5252.8  209.64  5267.8  210.48  5294.7  210.15  5420.6  214.57
  5442.7  215.04  5452.9  214.49  5473.5   216.3  5535.2  217.84  5599.5  220.56
#Mann= 3 , 0 , 0
    4594     .17       0 4981.51     .09       0  5010.7     .17       0
Bank Sta=4981.51,5010.7
XS Rating Curve= 0 ,0
Exp/Cntr=0.3,0.1

Type RM Length L Ch R = 1 ,5829    ,452,452,452
BEGIN DESCRIPTION:
LAKE CREEK TRIBUTARY NO. 13 A 7.0
END DESCRIPTION:
XS GIS Cut Line= 3
      3766067.85     10095461.07      3765678.23     10095506.84
      3765367.84     10095661.08
#Sta/Elev= 30
  4607.7  214.33  4698.3  211.59  4718.5  211.97  4728.5  211.68  4734.9   210.7
  4768.8  209.09  4778.9   208.2  4807.7  207.71    4859  206.97    4940  204.82
  4994.4  201.89  4995.9  200.91  5011.6  201.76  5041.4  204.91  5108.6  208.99
  5114.1   208.6  5123.3  208.92  5145.6  210.68  5153.4  210.38  5175.8  211.29
  5203.8  210.24  5212.6  210.81  5226.2  210.65    5243   211.5  5248.6  211.23
  5265.4  212.09  5293.4  211.95  5310.2  212.73  5315.8  213.45  5346.6  214.22
#Mann= 5 ,-1 , 0
  4607.7     .17       0  4807.7     .15       0    4859     .17       0
    4940     .09       0  5041.4     .17       0
Bank Sta=4940,5041.4
XS Rating Curve= 0 ,0
Exp/Cntr=0.3,0.1

Type RM Length L Ch R = 1 ,5377    ,430,430,430
BEGIN DESCRIPTION:
LAKE CREEK TRIBUTARY NO. 13 A 6.0
END DESCRIPTION:
XS GIS Cut Line= 3
      3765967.86     10095161.07      3765738.23     10095166.84
      3765275.53     10095362.83
#Sta/Elev= 30
  4770.3  211.29  4790.3  211.09  4809.6  209.84  4830.3  209.46  4840.3  208.43
  4850.3  208.63  4880.3  207.66  4951.9  204.03  4972.3  202.56  4990.4   201.2
  5009.2  200.89  5009.5  200.39  5013.1  200.39  5013.3  200.89  5025.6  200.97
    5033   201.8  5054.7  202.48    5073  201.96  5138.6   203.9  5154.9  204.12
  5202.2  205.97  5207.7  205.66  5239.3  206.47  5278.7  206.52  5315.4  207.62
  5347.9  207.69  5391.4  208.79  5402.2   208.5  5467.4  210.47  5502.5  210.82
#Mann= 6 ,-1 , 0
  4770.3     .11       0  4809.6     .17       0  4951.9     .15       0
  4972.3     .09       0  5054.7     .15       0  5138.6     .17       0
Bank Sta=4972.3,5054.7
XS Rating Curve= 0 ,0
Exp/Cntr=0.3,0.1

Type RM Length L Ch R = 1 ,4947    ,1015,1015,1015
BEGIN DESCRIPTION:
Mapping XS 754c422f
END DESCRIPTION:
XS GIS Cut Line= 2
      3765825.13     10094729.25      3765138.67     10095156.38
#Sta/Elev= 30
  4582.9   208.9  4611.9  208.73  4626.8  207.76  4639.1  208.01  4697.5  206.22
  4748.9  205.76  4764.2   204.8  4806.7  204.08 4877.35201.1904  4893.2  200.63
  4893.4  200.13    4897  200.13  4897.3  200.63  4901.1  200.86  4916.5  201.23
  4974.3  200.89  5074.6  201.52  5084.1   201.2    5090  201.79  5105.3  201.41
  5111.2  202.21  5122.9  202.57  5178.5  203.92  5192.1  204.67  5199.8  204.48
  5205.7  205.12    5221  204.97  5278.9  207.16  5294.2  207.17  5391.4  209.47
#Mann= 4 ,-1 , 0
  4582.9     .17       0 4877.35     .09       0  4916.5     .15       0
  5122.9     .17       0
Bank Sta=4877.35,4916.5
XS Rating Curve= 0 ,0
Exp/Cntr=0.3,0.1

Type RM Length L Ch R = 1 ,3932    ,414,414,414
BEGIN DESCRIPTION:
LAKE CREEK TRIBUTARY NO. 13 A 5.0
END DESCRIPTION:
XS GIS Cut Line= 3
      3765641.91     10094202.51      3765098.23     10094306.84
      3764848.06     10094546.01
#Sta/Elev= 30
  4446.4  208.47  4491.3  208.35  4511.6   207.5  4517.5  207.85    4532  207.64
  4562.5  206.91  4569.5  206.26  4593.1  206.11  4621.5  205.45  4633.8  204.74
  4684.7  203.63  4715.3   203.5  4735.7  202.58  4834.5   200.7  4886.5     199
  4891.6  199.45  4918.9  198.52  4943.6  198.44  4949.5  197.65  4995.6  197.35
  4996.1  196.72  5010.4  197.64  5038.7  198.41  5102.2  200.01  5137.8  200.45
    5173  201.67  5180.2   201.4  5194.2  202.38  5229.6  203.48  5346.1  205.35
#Mann= 3 , 0 , 0
  4446.4     .17       0  4943.6     .09       0  5038.7     .17       0
Bank Sta=4943.6,5038.7
XS Rating Curve= 0 ,0
Exp/Cntr=0.3,0.1

Type RM Length L Ch R = 1 ,3518    ,548,548,548
BEGIN DESCRIPTION:
Mapping XS 2d59e2e1
END DESCRIPTION:
XS GIS Cut Line= 3
      3765512.21     10093904.78      3765038.89     10093965.86
      3764855.69     10094385.68
#Sta/Elev= 30
  4521.5  206.86  4576.3  206.95  4616.6  205.94  4646.9     206  4677.1  204.59
    4685  205.08  4707.4  204.69  4808.2  201.14  4848.9  198.66    4899  196.68
  4918.2  196.76  4969.5  194.58  4989.7  194.67  4996.8   193.6  5002.3  192.13
  5002.6  191.63  5006.2  191.63 5010.92194.7247  5011.9   195.3  5026.3  195.65
  5058.7  195.59  5069.9  196.84  5080.8  197.28  5124.5  197.94  5146.3  199.03
  5192.1  200.14  5291.2  201.25    5299  201.93  5353.6  203.17  5456.8  203.61
#Mann= 3 , 0 , 0
  4521.5     .17       0  4989.7     .09       0 5010.92     .17       0
Bank Sta=4989.7,5010.92
XS Rating Curve= 0 ,0
Exp/Cntr=0.3,0.1

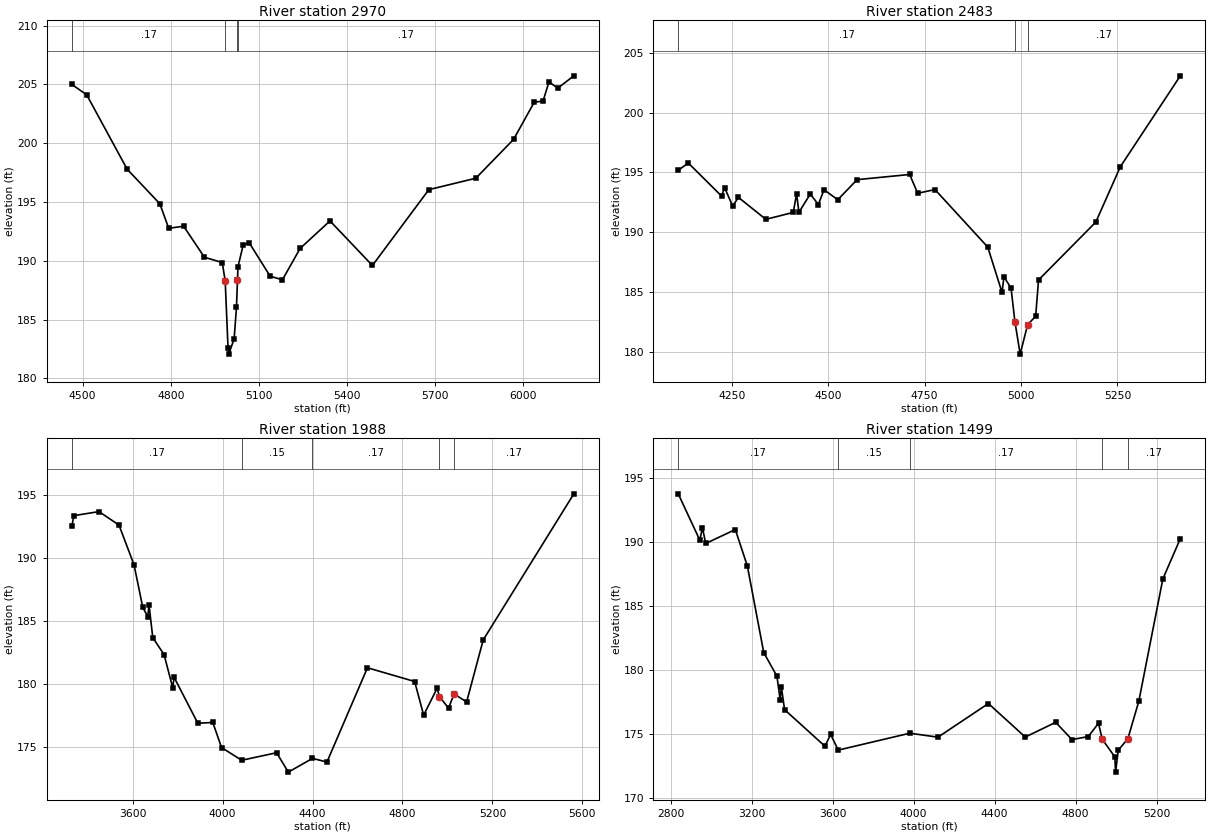
Type RM Length L Ch R = 1 ,2970    ,487,487,487
BEGIN DESCRIPTION:
LAKE CREEK TRIBUTARY NO. 13 A 4.0
END DESCRIPTION:
XS GIS Cut Line= 4
      3764710.43     10094407.31      3764628.23     10093876.84
      3764558.58     10093536.68      3765382.42     10093484.93
#Sta/Elev= 30
  4463.2     205  4513.9  204.12  4651.7  197.79    4763  194.85  4793.3  192.76
  4844.1  192.94  4914.8   190.3  4975.5  189.85  4985.6  188.29  4995.3  182.56
  4997.8  182.06  5016.1  183.37    5024  186.05 5027.42188.3567  5029.1  189.49
  5046.7  191.32  5067.1  191.54  5138.6  188.69  5180.4  188.38  5240.7  191.05
  5342.4  193.39  5486.8   189.6    5679  196.05  5838.9  197.02  5967.7  200.33
  6037.9  203.49  6067.9  203.58    6088  205.22    6118  204.68  6172.7  205.73
#Mann= 4 ,-1 , 0
  4463.2     .17       0  4985.6     .09       0 5027.42     .12       0
  5029.1     .17       0
Bank Sta=4985.6,5027.42
XS Rating Curve= 0 ,0
Exp/Cntr=0.3,0.1

Type RM Length L Ch R = 1 ,2483    ,495,495,495
BEGIN DESCRIPTION:
LAKE CREEK TRIBUTARY NO. 13 A 3.0
END DESCRIPTION:
XS GIS Cut Line= 4
       3764634.3     10093339.89       3764260.1     10093859.87
      3764288.23     10094106.84      3764567.84     10094411.06
#Sta/Elev= 30
  4110.8  195.17  4136.9  195.78  4223.1  193.02  4231.2  193.71  4252.1  192.17
  4266.8  192.91    4338  191.07  4409.2  191.65  4417.8   193.2  4423.9  191.66
  4453.4  193.19  4474.2  192.31    4489  193.54  4524.6  192.71  4574.9  194.39
  4711.1  194.82    4732  193.25  4776.8  193.56  4913.7  188.75  4950.7  184.96
  4955.7  186.26  4974.1  185.33  4984.1  182.52  4997.8   179.8  5017.1  182.26
    5038  182.97  5045.4     186    5194  190.84  5257.5  195.46  5413.2  203.07
#Mann= 3 , 0 , 0
  4110.8     .17       0  4984.1     .09       0  5017.1     .17       0
Bank Sta=4984.1,5017.1
XS Rating Curve= 0 ,0
Exp/Cntr=0.3,0.1

Type RM Length L Ch R = 1 ,1988    ,489,489,489
BEGIN DESCRIPTION:
LAKE CREEK TRIBUTARY NO. 13 A 2.0
END DESCRIPTION:
XS GIS Cut Line= 4
       3764802.2     10093171.96       3763961.7     10093599.39
      3763958.23     10094326.84      3764046.49     10094881.87
#Sta/Elev= 30
  3329.6  192.55  3339.4  193.39  3450.6  193.71  3539.6  192.64  3606.4  189.49
  3645.3  186.11  3667.5  185.38  3673.1  186.31  3689.8  183.71  3739.9  182.37
  3778.7  179.72  3784.4  180.57    3890  176.92  3956.7  176.98  3995.6  174.99
  4085.2  173.98  4240.4  174.58  4292.4  173.04  4399.9  174.13  4464.2  173.84
  4644.2  181.32  4854.2  180.23  4894.2  177.56  4954.2   179.7  4964.2  179.04
  5004.7  178.12  5029.5  179.24  5085.3  178.61    5159  183.53    5562  195.12
#Mann= 5 ,-1 , 0
  3329.6     .17       0  4085.2     .15       0  4399.9     .17       0
  4964.2     .09       0  5029.5     .17       0
#Block Obstruct= 2 , 0
         4697.98  181.51
Bank Sta=4964.2,5029.5
XS Rating Curve= 0 ,0
Exp/Cntr=0.3,0.1

Type RM Length L Ch R = 1 ,1499    ,0,0,0
BEGIN DESCRIPTION:
LAKE CREEK TRIBUTARY NO. 13 A 1.0
END DESCRIPTION:
XS GIS Cut Line= 4
      3764870.94     10093049.81      3763697.01     10093704.65
      3763598.23     10094516.84      3763717.85     10094811.06
#Sta/Elev= 30
  2837.6   193.8  2944.2  190.18  2957.2  191.16  2973.2  189.92  3119.5  191.01
  3178.9  188.17    3260   181.4  3325.2  179.55  3341.2  177.69  3346.9  178.72
  3362.9  176.94  3562.5  174.08  3590.3  175.01  3627.9  173.78  3981.5   175.1
  4120.5  174.79  4369.6  177.42  4551.8   174.8    4702  175.95  4782.6   174.6
  4863.2  174.84  4913.6  175.88 4931.44174.6424  4994.2  173.25  4997.8  172.06
  5011.1  173.77  5058.5  174.67  5112.5  177.59  5231.3  187.15  5317.6   190.3
#Mann= 5 ,-1 , 0
  2837.6     .17       0  3627.9     .15       0  3981.5     .17       0
 4931.44     .09       0  5058.5     .17       0
#Block Obstruct= 2 , 0
         4361.02  177.34
Bank Sta=4931.44,5058.5
XS Rating Curve= 0 ,0
Exp/Cntr=0.3,0.1

Chan Stop Cuts=-1
Use User Specified Reach Order=0
Composite Channel Slope=5