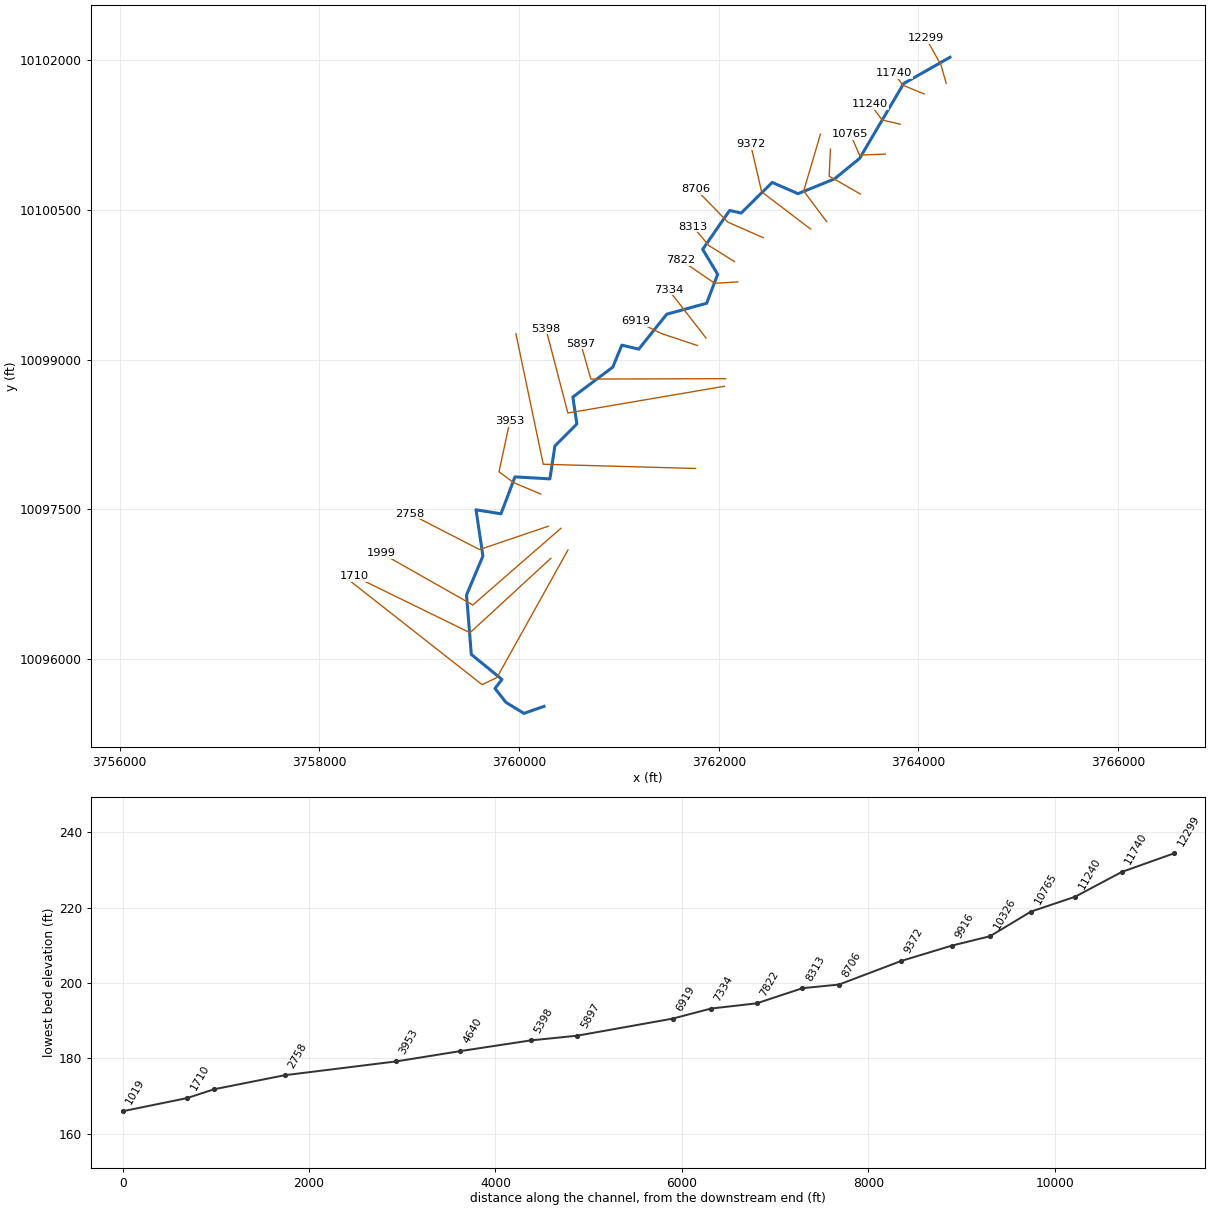
--- LAKE CREEK TRIBUTARY NO 14.prj (project) ---

Proj Title=LAKE CREEK TRIBUTARY NO 14 Base Level Engineering
Current Plan=p01
Default Exp/Contr=0.3,0.1
English Units
Geom File=g01
Flow File=f01
Flow File=f02
Plan File=p01
Y Axis Title=Elevation
X Axis Title(PF)=Main Channel Distance
X Axis Title(XS)=Station
BEGIN DESCRIPTION:
LAKE CREEK TRIBUTARY NO 14
END DESCRIPTION:
DSS Export Rating Curves= 0
DSS Export Rating Curve Sorted= 0
DSS Export Volume Flow Curves= 0
DXF OffsetX= 0
DXF OffsetY= 0
DXF ScaleX= 1
DXF ScaleY= 10

--- LAKE CREEK TRIBUTARY NO 14.p01 (plan) ---

Plan Title=Multiple Run
Short Identifier=Multiple
Geom File=g01
Flow File=f01
Subcritical Flow
K Sum by GR= 0
Std Step Tol= 0.01
Critical Tol= 0.01
Num of Std Step Trials= 20
Max Error Tol= 0.3
Flow Tol Ratio= 0.001
Split Flow NTrial= 30
Split Flow Tol= 0.02
Split Flow Ratio= 0.02
Log Output Level= 0
Friction Slope Method= 1
Unsteady Friction Slope Method= 2
Unsteady Bridges Friction Slope Method= 1
Parabolic Critical Depth
Global Vel Dist=  1 , 1 , 1
Global Log Level= 0
CheckData=True
Encroach Param= -1, 0, 0, 0
BEGIN DESCRIPTION:
Multiple Run
END DESCRIPTION:

--- LAKE CREEK TRIBUTARY NO 14.f01 (steady flow) ---

Flow Title=Multiple
Program Version=4.10
Number of Profiles= 7
Profile Names=10-year,25-year,50-year,1pct_min,100-year,1pct_plu,500-year
River Rch & RM=LAKE CREEK TRIBU,Reach-1         ,12299
     502     671     900     398    1201    3627    2208
River Rch & RM=LAKE CREEK TRIBU,Reach-1         ,8313
     703     953    1288     573    1730    5225    3228
Boundary for River Rch & Prof#=LAKE CREEK TRIBU,Reach-1         , 1
Up Type= 0
Dn Type= 3
Dn Slope=0.005
Boundary for River Rch & Prof#=LAKE CREEK TRIBU,Reach-1         , 2
Up Type= 0
Dn Type= 3
Dn Slope=0.005
Boundary for River Rch & Prof#=LAKE CREEK TRIBU,Reach-1         , 3
Up Type= 0
Dn Type= 3
Dn Slope=0.005
Boundary for River Rch & Prof#=LAKE CREEK TRIBU,Reach-1         , 4
Up Type= 0
Dn Type= 3
Dn Slope=0.005
Boundary for River Rch & Prof#=LAKE CREEK TRIBU,Reach-1         , 5
Up Type= 0
Dn Type= 3
Dn Slope=0.005
Boundary for River Rch & Prof#=LAKE CREEK TRIBU,Reach-1         , 6
Up Type= 0
Dn Type= 3
Dn Slope=0.005
Boundary for River Rch & Prof#=LAKE CREEK TRIBU,Reach-1         , 7
Up Type= 0
Dn Type= 3
Dn Slope=0.005
DSS Import GetInterval= 0
DSS Import GetPeak= 0
DSS Import FillOption= 0

--- LAKE CREEK TRIBUTARY NO 14.f02 (steady flow) ---

Flow Title=Orig_BLE_Flows
Program Version=4.10
Number of Profiles= 7
Profile Names=10-year,25-year,50-year,1pct_min,100-year,1pct_plu,500-year
River Rch & RM=LAKE CREEK TRIBU,Reach-1         ,12299
     502     658     783     306     924    2790    1284
River Rch & RM=LAKE CREEK TRIBU,Reach-1         ,8313
     703     934    1120     441    1331    4020    1877
Boundary for River Rch & Prof#=LAKE CREEK TRIBU,Reach-1         , 1
Up Type= 0
Dn Type= 3
Dn Slope=0.005
Boundary for River Rch & Prof#=LAKE CREEK TRIBU,Reach-1         , 2
Up Type= 0
Dn Type= 3
Dn Slope=0.005
Boundary for River Rch & Prof#=LAKE CREEK TRIBU,Reach-1         , 3
Up Type= 0
Dn Type= 3
Dn Slope=0.005
Boundary for River Rch & Prof#=LAKE CREEK TRIBU,Reach-1         , 4
Up Type= 0
Dn Type= 3
Dn Slope=0.005
Boundary for River Rch & Prof#=LAKE CREEK TRIBU,Reach-1         , 5
Up Type= 0
Dn Type= 3
Dn Slope=0.005
Boundary for River Rch & Prof#=LAKE CREEK TRIBU,Reach-1         , 6
Up Type= 0
Dn Type= 3
Dn Slope=0.005
Boundary for River Rch & Prof#=LAKE CREEK TRIBU,Reach-1         , 7
Up Type= 0
Dn Type= 3
Dn Slope=0.005
DSS Import GetInterval= 0
DSS Import GetPeak= 0
DSS Import FillOption= 0

--- LAKE CREEK TRIBUTARY NO 14.g01 (geometry) ---

Geom Title=Existing Conditions
Program Version=4.10

River Reach=LAKE CREEK TRIBU,Reach-1
Reach XY= 30
       3764315.4     10102031.53      3763851.51     10101768.33
       3763409.5     10101017.29      3763157.76     10100812.43
      3762793.18     10100664.86       3762534.5     10100777.71
      3762223.74     10100470.41      3762108.23     10100496.84
      3761838.23     10100106.84      3761988.23     10099856.84
      3761878.23     10099566.84      3761478.23     10099456.84
      3761198.23     10099106.84      3761028.23     10099146.84
      3760938.23     10098926.84      3760538.23     10098626.84
      3760578.23     10098356.84      3760358.23     10098136.84
      3760308.23     10097806.84      3759958.23     10097826.84
      3759818.23     10097456.84      3759568.23     10097496.84
      3759637.08      10097033.8      3759473.25     10096643.93
      3759521.03     10096047.76      3759828.23     10095796.84
      3759758.23     10095706.84      3759868.23     10095566.84
      3760048.23     10095456.84      3760248.23     10095526.84

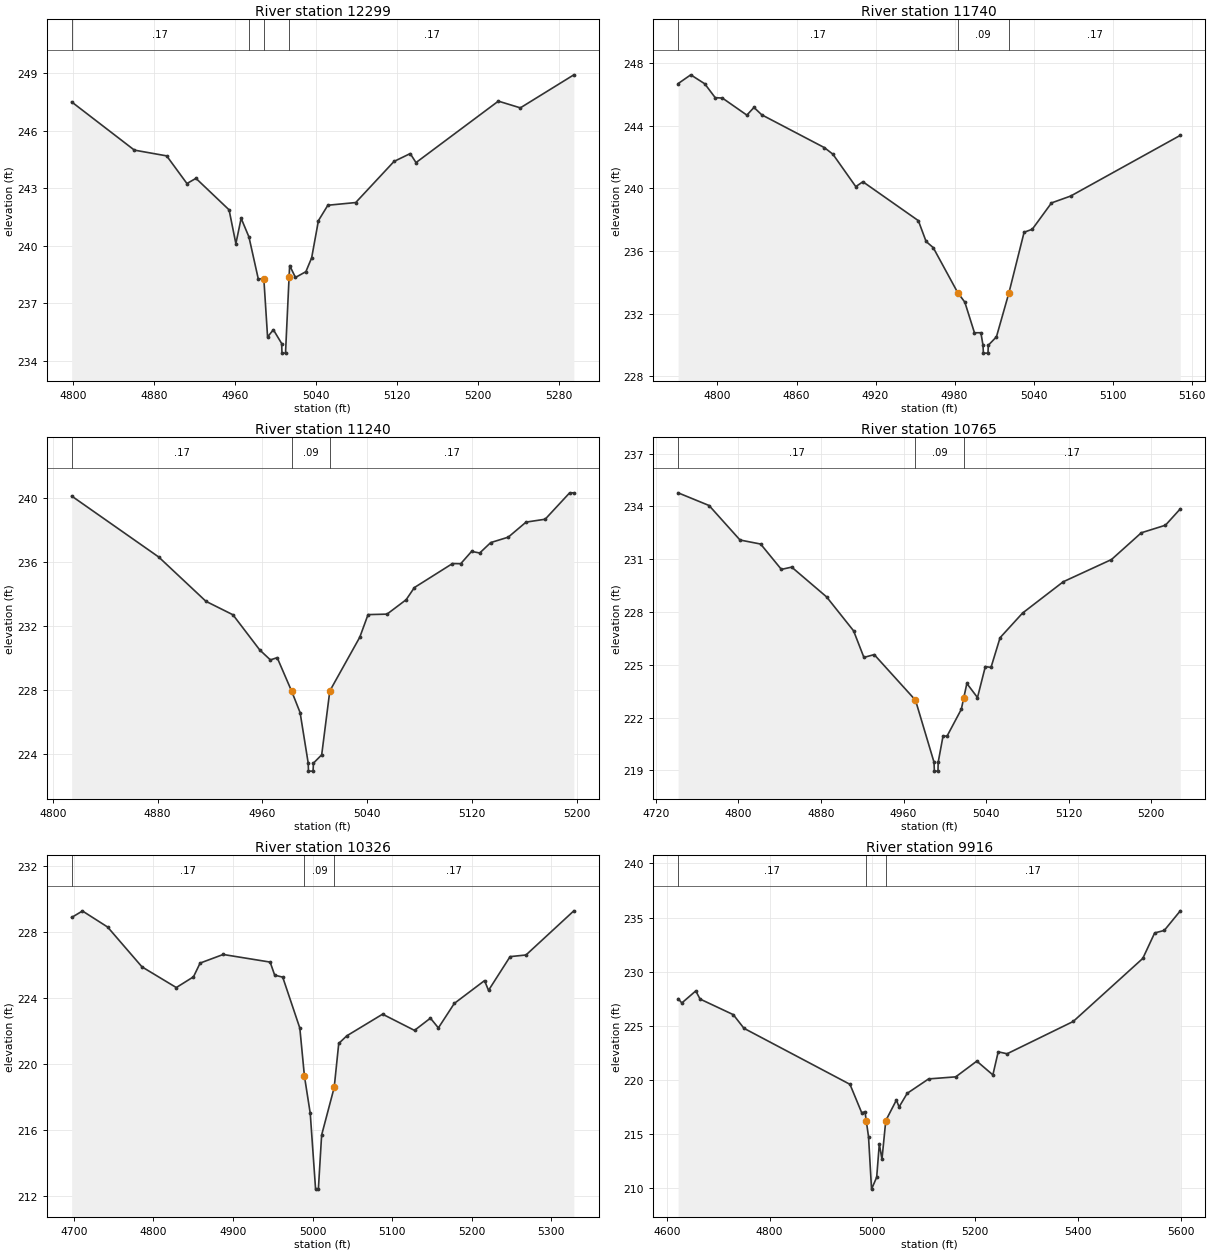
Type RM Length L Ch R = 1 ,12299   ,559,559,559
BEGIN DESCRIPTION:
LAKE CREEK TRIBUTARY NO. 14 21.0
END DESCRIPTION:
XS GIS Cut Line= 3
      3764276.89     10101771.44      3764226.51     10101951.66
      3764076.86     10102221.52
#Sta/Elev= 30
  4798.9  247.49  4860.8  244.98  4892.7  244.68  4912.7  243.24  4921.6  243.51
  4954.3  241.87    4961  240.11  4966.2  241.43  4973.9  240.46  4983.1  238.28
  4988.6  238.28  4992.3  235.25    4998  235.63  5006.2  234.91  5006.5  234.41
    5010  234.41 5013.51238.3548  5014.1  238.97  5019.8  238.35  5030.1  238.65
  5035.8  239.37  5042.5  241.31  5051.8  242.11  5079.3  242.25  5117.1  244.39
  5133.1   244.8  5138.8  244.33  5220.1  247.53  5241.8  247.18  5294.6   248.9
#Mann= 4 ,-1 , 0
  4798.9     .17       0  4973.9     .15       0  4988.6     .09       0
 5013.51     .17       0
Bank Sta=4988.6,5013.51
XS Rating Curve= 0 ,0
Exp/Cntr=0.3,0.1

Type RM Length L Ch R = 1 ,11740   ,500,500,500
BEGIN DESCRIPTION:
LAKE CREEK TRIBUTARY NO. 14 20.0
END DESCRIPTION:
XS GIS Cut Line= 3
      3764056.57     10101664.39      3763843.87     10101751.66
      3763752.83     10101872.63
#Sta/Elev= 30
  4770.1  246.68  4779.7  247.24  4790.3  246.67  4798.3  245.78  4803.7  245.76
  4822.3  244.67  4827.7  245.16  4833.6  244.69  4881.1   242.6  4887.6  242.18
    4905  240.11  4910.4  240.42  4952.5  237.94  4958.4  236.61  4963.8  236.22
  4982.4  233.35  4987.8  232.74  4995.1  230.79    5000  230.79  5001.6  229.99
  5001.9  229.49  5005.4  229.49  5005.6  229.99  5011.8  230.53 5021.26233.3308
  5032.8   237.2    5039  237.39  5053.6  239.07  5068.2  239.51  5151.4  243.38
#Mann= 3 , 0 , 0
  4770.1     .17       0  4982.4     .09       0 5021.26     .17       0
Bank Sta=4982.4,5021.26
XS Rating Curve= 0 ,0
Exp/Cntr=0.3,0.1

Type RM Length L Ch R = 1 ,11240   ,475,475,475
BEGIN DESCRIPTION:
LAKE CREEK TRIBUTARY NO. 14 19.0
END DESCRIPTION:
XS GIS Cut Line= 3
      3763817.82     10101361.08      3763636.93     10101403.05
      3763517.83      10101561.1
#Sta/Elev= 30
  4814.3  240.11  4880.8   236.3  4916.9  233.53  4937.5  232.69    4958  230.49
  4966.1  229.87  4971.3  230.01  4982.3227.9242  4988.8  226.58    4995  223.42
  4995.2  222.92  4998.7  222.92    4999  223.42  5005.3  223.94  5011.5  227.93
  5034.4  231.29  5040.7   232.7  5055.2  232.73  5069.8  233.63  5076.1  234.39
  5105.2  235.89  5111.5  235.88  5119.8  236.65    5126  236.55  5134.4   237.2
  5147.8  237.54  5161.4  238.48    5176  238.66  5194.7  240.31  5197.9  240.31
#Mann= 3 , 0 , 0
  4814.3     .17       0  4982.3     .09       0  5011.5     .17       0
Bank Sta=4982.3,5011.5
XS Rating Curve= 0 ,0
Exp/Cntr=0.3,0.1

Type RM Length L Ch R = 1 ,10765   ,439,439,439
BEGIN DESCRIPTION:
LAKE CREEK TRIBUTARY NO. 14 18.0
END DESCRIPTION:
XS GIS Cut Line= 3
      3763667.84     10101061.07       3763409.5     10101052.01
      3763317.84      10101261.1
#Sta/Elev= 30
  4741.5  234.77  4771.5  234.05  4801.5  232.09  4821.5  231.86  4841.6  230.42
  4851.6  230.55  4885.4  228.86  4911.6  226.93  4921.6  225.42  4931.6  225.58
  4971.6  222.99  4989.6  219.46  4989.9  218.96  4993.4  218.96  4993.6  219.46
  4998.3  220.95  5002.2  220.95    5016  222.47 5018.27 223.088  5021.4  223.94
  5031.7  223.14  5039.3   224.9  5044.8  224.85  5053.6  226.54  5075.4  227.94
  5114.9  229.72  5161.6  230.98  5190.5   232.5  5213.9  232.93  5228.3  233.86
#Mann= 3 , 0 , 0
  4741.5     .17       0  4971.6     .09       0 5018.27     .17       0
Bank Sta=4971.6,5018.27
XS Rating Curve= 0 ,0
Exp/Cntr=0.3,0.1

Type RM Length L Ch R = 1 ,10326   ,410,410,410
BEGIN DESCRIPTION:
LAKE CREEK TRIBUTARY NO. 14 17.0
END DESCRIPTION:
XS GIS Cut Line= 3
      3763417.81      10100661.1      3763105.46     10100840.65
      3763117.85     10101111.08
#Sta/Elev= 30
  4697.3  228.86  4710.9  229.25  4742.5  228.28  4785.7  225.87  4828.8  224.62
  4850.4  225.27  4858.7   226.1  4887.7  226.62  4946.7  226.16  4952.4  225.37
  4962.5  225.25    4984  222.17  4989.8  219.26  4997.1  217.01  5003.8  212.43
  5007.3  212.43  5011.4   215.7  5027.2  218.58  5032.9  221.24    5043   221.7
    5088  223.01  5128.1  222.03  5148.1  222.77  5158.1  222.18  5178.1  223.66
  5216.1  225.04  5221.1  224.45  5248.2  226.49  5268.2  226.59  5328.3  229.26
#Mann= 3 , 0 , 0
  4697.3     .17       0  4989.8     .09       0  5027.2     .17       0
Bank Sta=4989.8,5027.2
XS Rating Curve= 0 ,0
Exp/Cntr=0.3,0.1

Type RM Length L Ch R = 1 ,9916    ,544,544,544
BEGIN DESCRIPTION:
LAKE CREEK TRIBUTARY NO. 14 16.0
END DESCRIPTION:
XS GIS Cut Line= 3
      3763080.03     10100383.99      3762849.98     10100692.17
      3763017.84     10101261.04
#Sta/Elev= 30
  4621.8  227.51  4629.1  227.12  4656.2  228.23  4664.5  227.48  4729.2  226.04
    4750  224.78  4956.4  219.61  4979.3  216.98  4985.6  217.09 4988.24216.2061
  4992.5  214.78  4998.4  209.94  5008.4  211.04  5013.5   214.1  5018.7  212.71
  5026.1  216.26  5046.8  218.16    5052  217.52  5067.8  218.78  5109.5  220.11
  5162.3   220.3  5203.3  221.75  5234.6  220.48    5245  222.61  5262.3  222.43
    5391  225.41  5526.5  231.23  5549.6  233.58  5568.3  233.81  5599.5  235.62
#Mann= 3 , 0 , 0
  4621.8     .17       0 4988.24     .09       0  5026.1     .17       0
Bank Sta=4988.24,5026.1
XS Rating Curve= 0 ,0
Exp/Cntr=0.3,0.1

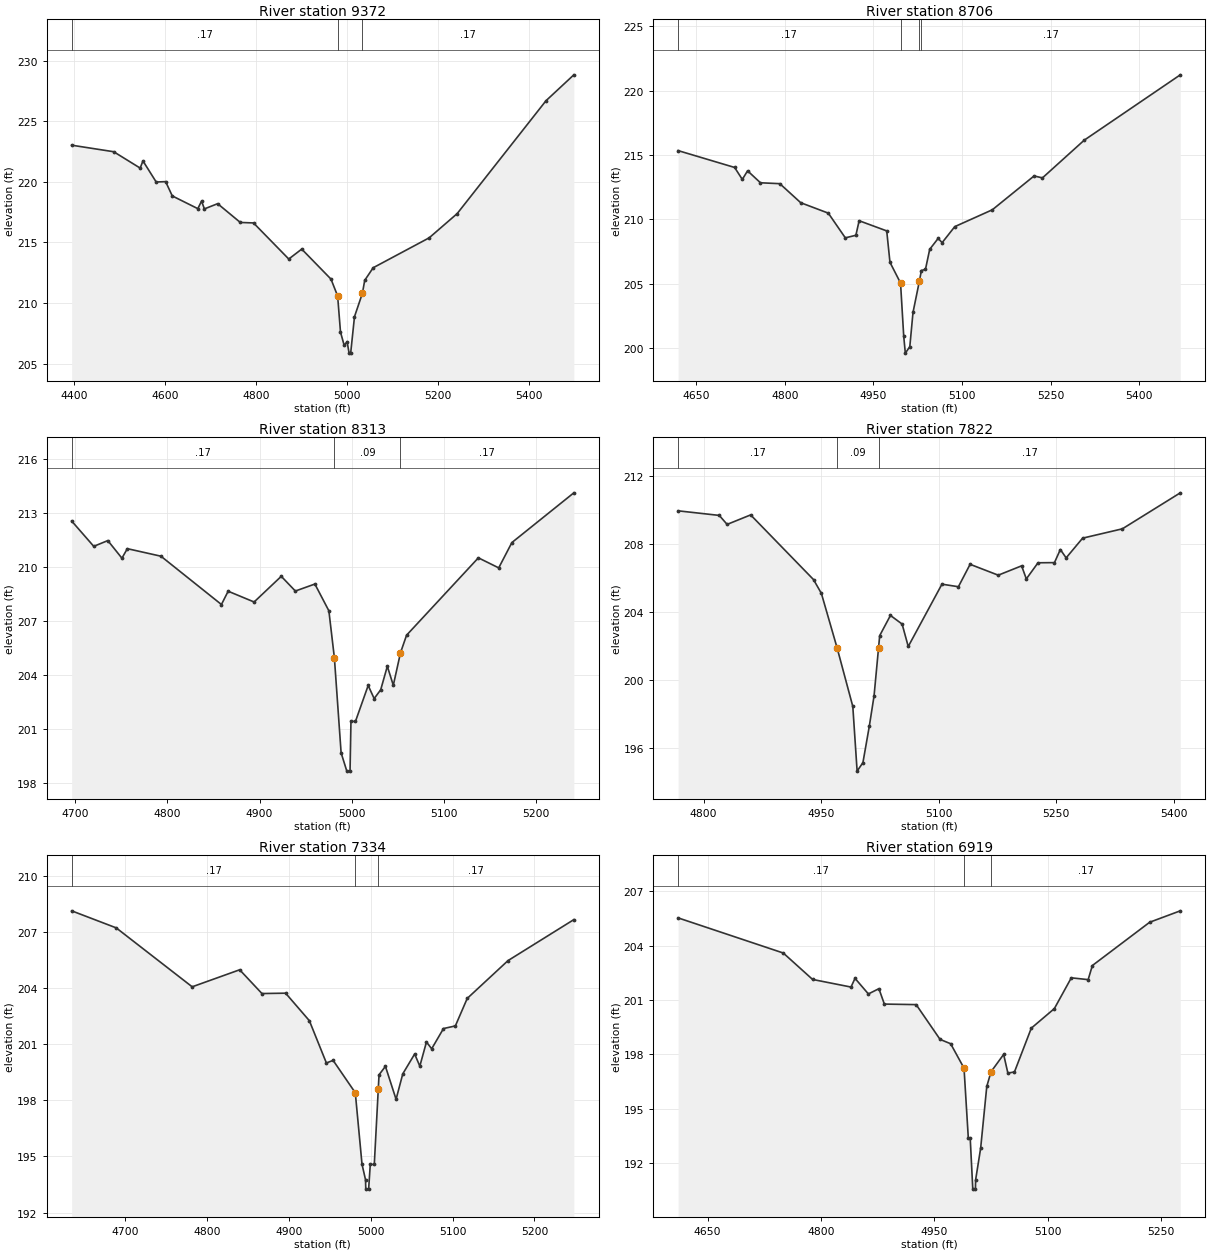
Type RM Length L Ch R = 1 ,9372    ,666,666,666
BEGIN DESCRIPTION:
LAKE CREEK TRIBUTARY NO. 14 15.0
END DESCRIPTION:
XS GIS Cut Line= 3
      3762917.84     10100311.08      3762428.97     10100683.49
      3762317.85     10101161.07
#Sta/Elev= 30
  4394.3  223.03  4486.8  222.49    4545  221.14  4551.2  221.73  4580.3  219.99
  4601.1  220.02  4615.7  218.84  4671.9  217.79  4680.1  218.41  4686.4  217.77
  4715.5   218.2  4765.4  216.65  4794.4  216.61    4872  213.63  4900.5  214.45
  4964.9  211.97  4979.5  210.58  4985.8   207.6    4994  206.49  5000.3  206.81
  5004.7  205.86  5008.2  205.86  5016.6  208.87    5034   210.8  5039.1  211.87
  5057.7  212.91  5180.9  215.38  5242.5  217.38  5437.9   226.7  5499.2  228.84
#Mann= 3 , 0 , 0
  4394.3     .17       0  4979.5     .09       0    5034     .17       0
Bank Sta=4979.5,5034
XS Rating Curve= 0 ,0
Exp/Cntr=0.3,0.1

Type RM Length L Ch R = 1 ,8706    ,393,393,393
BEGIN DESCRIPTION:
LAKE CREEK TRIBUTARY NO. 14 14.0
END DESCRIPTION:
XS GIS Cut Line= 3
       3762445.5     10100223.69      3762090.43     10100379.67
      3761767.85     10100711.08
#Sta/Elev= 30
  4619.2  215.35  4714.9  214.04  4727.9  213.11  4736.8  213.78  4758.6  212.85
  4791.4  212.78  4826.8   211.3  4873.5  210.49  4902.3  208.57  4920.2  208.77
  4925.7   209.9  4972.4  209.11  4977.9  206.67  4995.8  205.06  5001.2  200.92
  5003.9  199.61  5011.5  200.11  5016.9  202.77 5027.84205.2331  5031.1  206.03
    5038  206.12  5045.2  207.68  5059.4  208.52  5066.3   208.2  5087.6  209.44
  5151.2  210.75  5221.9  213.38  5236.1  213.23  5306.8  216.16  5469.5  221.24
#Mann= 4 ,-1 , 0
  4619.2     .17       0  4995.8     .09       0 5027.84     .12       0
  5031.1     .17       0
Bank Sta=4995.8,5027.84
XS Rating Curve= 0 ,0
Exp/Cntr=0.3,0.1

Type RM Length L Ch R = 1 ,8313    ,491,491,491
BEGIN DESCRIPTION:
LAKE CREEK TRIBUTARY NO. 14 13.0
END DESCRIPTION:
XS GIS Cut Line= 3
      3762155.51     10099984.72      3761898.23     10100146.84
      3761743.22      10100331.9
#Sta/Elev= 30
  4695.9  212.57  4719.9  211.16  4735.2  211.48  4750.5   210.5  4756.4  211.03
  4792.9  210.61  4858.6  207.92  4865.9  208.66  4894.1  208.06  4923.6  209.49
  4938.9  208.67  4960.1  209.06  4975.3  207.57  4981.3  204.95  4988.6  199.66
  4994.8  198.64  4998.3  198.64  4999.3  201.41  5004.2  201.41    5018  203.41
  5024.5  202.68  5031.6  203.17  5038.8  204.48  5045.3  203.42  5053.1  205.23
  5059.7  206.21  5137.7  210.52  5159.8  209.96  5174.1  211.37  5241.4  214.14
#Mann= 3 , 0 , 0
  4695.9     .17       0  4981.3     .09       0  5053.1     .17       0
Bank Sta=4981.3,5053.1
XS Rating Curve= 0 ,0
Exp/Cntr=0.3,0.1

Type RM Length L Ch R = 1 ,7822    ,488,488,488
BEGIN DESCRIPTION:
LAKE CREEK TRIBUTARY NO. 14 12.0
END DESCRIPTION:
XS GIS Cut Line= 3
      3762190.22     10099780.71      3761958.23     10099766.84
      3761621.71     10099997.71
#Sta/Elev= 30
  4767.6  209.95  4820.1  209.68  4830.1  209.15  4860.1  209.71  4940.3   205.9
  4950.3  205.09  4970.3  201.89  4990.4  198.43  4995.9  194.62  5003.3  195.12
  5011.4  197.25  5017.5  199.05 5023.26201.8898  5024.7   202.6  5038.4  203.79
  5053.3  203.28  5061.1  201.96  5104.1  205.63  5125.1  205.48    5140   206.8
  5175.9  206.16  5205.7  206.71  5211.7  205.94  5226.6  206.89  5247.6   206.9
  5255.1  207.67  5262.5  207.18  5283.5  208.34  5334.2  208.89  5408.1  211.01
#Mann= 3 , 0 , 0
  4767.6     .17       0  4970.3     .09       0 5023.26     .17       0
Bank Sta=4970.3,5023.26
XS Rating Curve= 0 ,0
Exp/Cntr=0.3,0.1

Type RM Length L Ch R = 1 ,7334    ,415,415,415
BEGIN DESCRIPTION:
LAKE CREEK TRIBUTARY NO. 14 11.0
END DESCRIPTION:
XS GIS Cut Line= 3
      3761871.74     10099218.03      3761648.23     10099506.84
       3761495.8      10099702.6
#Sta/Elev= 30
  4634.8  208.12  4689.2  207.21    4782  204.06    4840  204.97  4867.2   203.7
  4896.1  203.72  4925.1  202.25  4945.9  199.99  4954.1  200.13  4981.2   198.4
  4989.4  194.58  4993.7  193.75    4994  193.25  4997.5  193.25  4999.5  194.57
  5004.4  194.57 5009.31198.6249  5010.2  199.36    5018  199.81    5031  198.05
  5039.2  199.41  5053.7  200.47    5060  199.82  5068.1  201.11  5074.5  200.75
  5088.9  201.83  5103.4  201.97  5117.9  203.44  5167.7  205.46  5248.1  207.65
#Mann= 3 , 0 , 0
  4634.8     .17       0  4981.2     .09       0 5009.31     .17       0
Bank Sta=4981.2,5009.31
XS Rating Curve= 0 ,0
Exp/Cntr=0.3,0.1

Type RM Length L Ch R = 1 ,6919    ,1022,1022,1022
BEGIN DESCRIPTION:
LAKE CREEK TRIBUTARY NO. 14 10.0
END DESCRIPTION:
XS GIS Cut Line= 3
      3761786.62     10099142.69      3761422.03     10099264.22
       3761171.6     10099389.43
#Sta/Elev= 30
  4610.9  205.54    4750   203.6  4788.8  202.14  4839.6  201.72  4844.9   202.2
  4862.6  201.34  4876.5  201.63  4883.7  200.78  4925.8  200.75  4957.4  198.83
  4971.4  198.59  4989.1  197.24  4994.8  193.36  4997.3  193.36  5000.7  190.56
  5004.2  190.56  5004.4  191.06  5011.1  192.82  5019.2  196.23  5024.8  197.04
  5041.5     198  5047.1  196.97  5055.8  197.03  5078.1  199.45  5108.6  200.53
    5131  202.23  5153.3  202.13  5158.9  202.91  5234.7   205.3  5275.2  205.93
#Mann= 3 , 0 , 0
  4610.9     .17       0  4989.1     .09       0  5024.8     .17       0
Bank Sta=4989.1,5024.8
XS Rating Curve= 0 ,0
Exp/Cntr=0.3,0.1

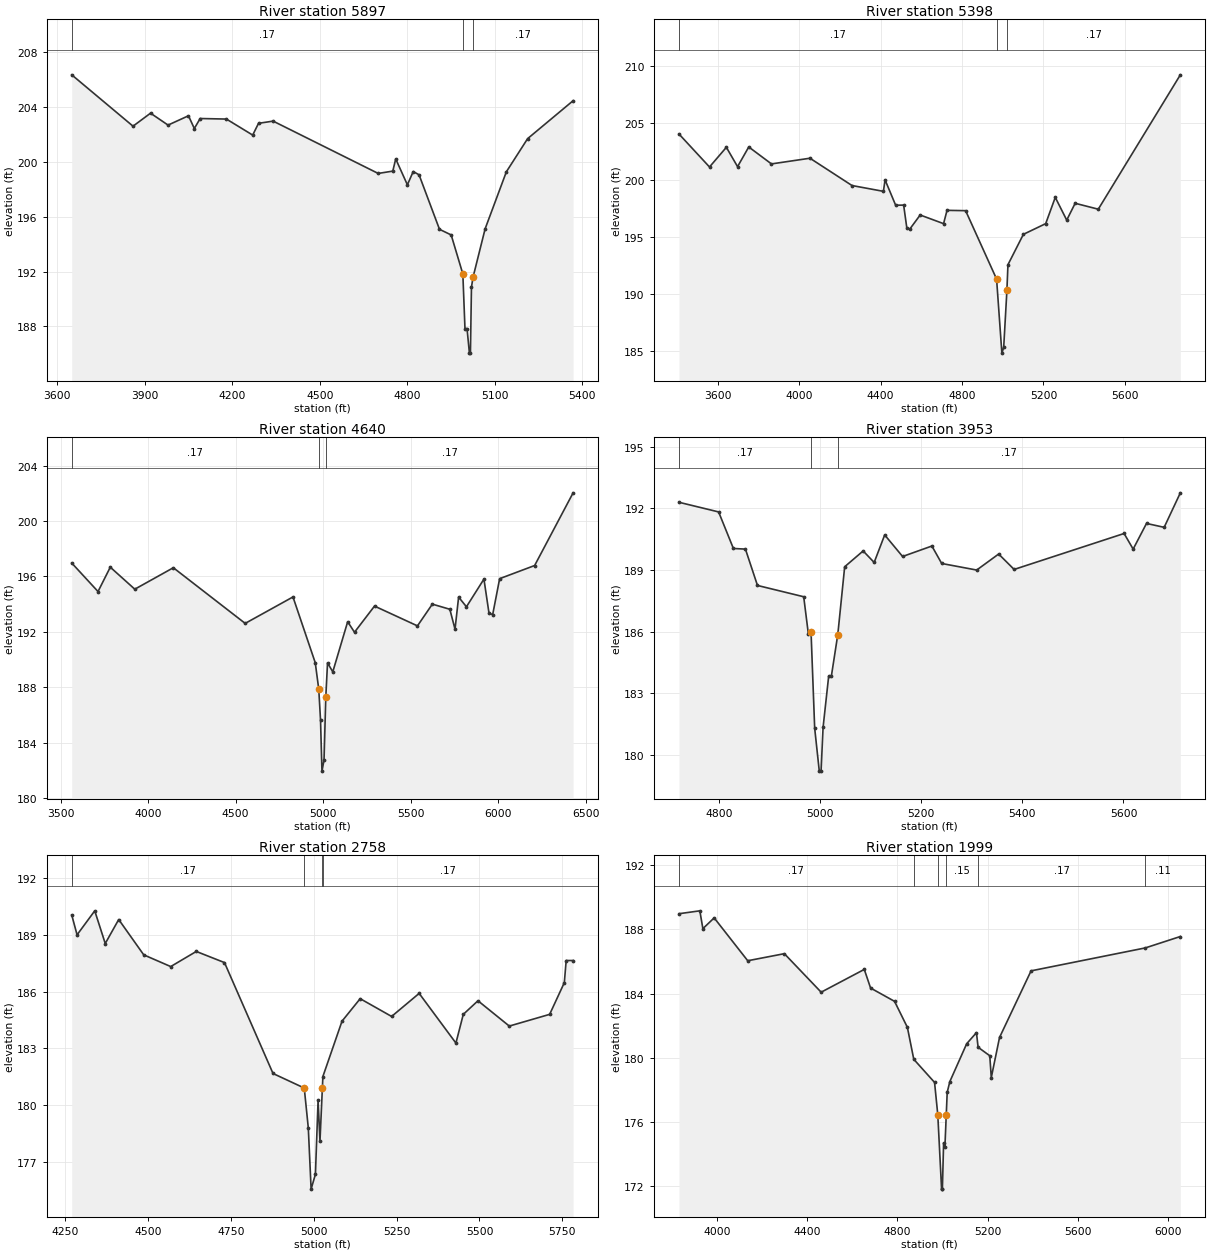
Type RM Length L Ch R = 1 ,5897    ,499,499,499
BEGIN DESCRIPTION:
LAKE CREEK TRIBUTARY NO. 14 9.0
END DESCRIPTION:
XS GIS Cut Line= 3
      3762067.82     10098811.07      3760718.23     10098806.84
      3760617.84      10099161.1
#Sta/Elev= 30
  3650.4  206.36  3860.4  202.61  3920.4  203.56  3980.4  202.69  4050.4  203.37
  4070.4  202.44  4090.4  203.17  4180.4  203.13  4270.4  201.96  4290.4  202.82
  4340.4  202.98  4700.4  199.16  4750.4  199.33  4760.4  200.22  4800.4  198.33
  4820.4   199.3  4840.4  199.06  4910.4  195.08  4950.4  194.67  4990.4  191.82
  4997.7  187.83  5004.8  187.83  5012.9  186.04  5016.4  186.04  5019.9  190.85
  5025.2  191.57  5066.8  195.12  5139.5  199.28  5212.3   201.7  5368.2  204.47
#Mann= 3 , 0 , 0
  3650.4     .17       0  4990.4     .09       0  5025.2     .17       0
Bank Sta=4990.4,5025.2
XS Rating Curve= 0 ,0
Exp/Cntr=0.3,0.1

Type RM Length L Ch R = 1 ,5398    ,758,758,758
BEGIN DESCRIPTION:
LAKE CREEK TRIBUTARY NO. 14 8.0
END DESCRIPTION:
XS GIS Cut Line= 3
      3762055.71      10098734.7      3760488.23     10098466.84
      3760267.86     10099311.06
#Sta/Elev= 30
  3409.8  204.05  3559.8  201.15  3642.6  202.88  3697.6  201.18  3752.6  202.91
  3864.1  201.42  4053.3  201.92  4259.8  199.52    4414  199.01  4422.1  200.02
  4474.1  197.79  4513.4   197.8  4529.1  195.78  4543.9   195.7  4594.6  196.93
  4709.5  196.17  4726.5  197.34  4817.8  197.31  4969.9   191.3  4995.9  184.79
  5004.8  185.29  5020.6   190.3  5025.7  192.56  5101.5  195.23  5211.1  196.17
  5258.2  198.48  5314.4  196.48  5355.8  197.96  5469.4  197.44  5872.5  209.25
#Mann= 3 , 0 , 0
  3409.8     .17       0  4969.9     .09       0  5020.6     .17       0
Bank Sta=4969.9,5020.6
XS Rating Curve= 0 ,0
Exp/Cntr=0.3,0.1

Type RM Length L Ch R = 1 ,4640    ,687,687,687
BEGIN DESCRIPTION:
LAKE CREEK TRIBUTARY NO. 14 7.0
END DESCRIPTION:
XS GIS Cut Line= 3
      3761767.86     10097911.07      3760241.47     10097953.45
      3759967.86     10099261.05
#Sta/Elev= 30
  3563.9  196.97    3714  194.91    3784  196.67    3924  195.08  4144.1  196.63
  4554.3  192.61  4827.2  194.52  4954.4  189.77  4974.5  187.85  4984.5  185.63
  4992.7  181.94  5004.5  182.74  5014.5  187.27  5024.5  189.76  5054.5  189.11
  5139.5  192.73  5178.5  191.97  5292.8  193.86    5538  192.43    5623     194
  5722.9  193.63  5752.5  192.19    5773  194.51  5817.7  193.81  5917.6  195.81
  5946.6  193.34  5967.6  193.25  6007.3  195.84  6207.1  196.79  6426.8  202.04
#Mann= 3 , 0 , 0
  3563.9     .17       0  4974.5     .09       0  5014.5     .17       0
Bank Sta=4974.5,5014.5
XS Rating Curve= 0 ,0
Exp/Cntr=0.3,0.1

Type RM Length L Ch R = 1 ,3953    ,1195,1195,1195
BEGIN DESCRIPTION:
LAKE CREEK TRIBUTARY NO. 14 6.0
END DESCRIPTION:
XS GIS Cut Line= 4
      3760215.27     10097655.81      3759941.88     10097770.38
      3759798.65     10097878.45      3759906.72     10098382.33
#Sta/Elev= 30
  4721.3   192.3  4799.7  191.83  4828.9  190.05  4852.7  190.02  4876.5  188.25
  4967.9   187.7    4977  185.91  4982.4  185.99  4989.6   181.3  4998.7  179.21
  5002.2  179.21  5006.2  181.34  5017.2  183.82  5022.5  183.82  5035.3  185.86
  5048.9  189.16  5085.4  189.93  5107.2  189.37    5128  190.71  5163.4  189.66
  5221.3  190.17  5240.7  189.32  5309.9     189  5353.3  189.78  5383.9  189.03
  5601.3  190.78  5619.2  190.02  5645.6  191.27  5680.5  191.08  5712.5  192.76
#Mann= 3 , 0 , 0
  4721.3     .17       0  4982.4     .09       0  5035.3     .17       0
Bank Sta=4982.4,5035.3
XS Rating Curve= 0 ,0
Exp/Cntr=0.3,0.1

Type RM Length L Ch R = 1 ,2758    ,759,759,759
BEGIN DESCRIPTION:
LAKE CREEK TRIBUTARY NO. 14 5.0
END DESCRIPTION:
XS GIS Cut Line= 3
      3760293.55     10097332.79      3759603.45     10097098.42
      3758906.63     10097456.81
#Sta/Elev= 30
    4270  190.06  4286.1  189.01  4339.4  190.28  4371.1  188.55  4411.7  189.82
  4487.2  187.95  4568.6  187.33  4645.7  188.13  4730.8  187.54  4877.2  181.67
  4971.4   180.9  4983.6  178.79  4992.1  175.55  5005.1  176.34  5013.1  180.25
  5018.8  178.09  5026.1180.9271  5027.6  181.51  5085.3  184.44  5140.1  185.63
  5234.9  184.69    5318  185.91  5428.9  183.28  5451.1   184.8  5495.4  185.52
  5589.9  184.18  5711.6   184.8  5755.9  186.48  5761.5  187.65  5782.4  187.65
#Mann= 4 ,-1 , 0
    4270     .17       0  4971.4     .09       0  5026.1     .12       0
  5027.6     .17       0
Bank Sta=4971.4,5026.1
XS Rating Curve= 0 ,0
Exp/Cntr=0.3,0.1

Type RM Length L Ch R = 1 ,1999    ,289,289,289
BEGIN DESCRIPTION:
LAKE CREEK TRIBUTARY NO. 14 4.0
END DESCRIPTION:
XS GIS Cut Line= 3
      3760417.89      10097311.1       3759536.2     10096543.05
      3758618.17     10097063.72
#Sta/Elev= 30
  3830.7  188.98  3923.3  189.16  3936.8  188.05  3986.9  188.72  4135.8  186.05
  4298.3  186.49  4461.6  184.09    4653  185.51  4680.9  184.35  4787.3  183.52
  4844.2   181.9  4872.6  179.91  4964.8  178.47  4979.1  176.46    4996  171.82
  4999.5  171.82    5005  174.71  5010.7  174.44  5016.6176.4125  5020.9  177.85
  5032.6  178.52  5107.4  180.88  5150.7  181.57    5158  180.66  5209.8  180.13
  5216.5  178.77  5253.1  181.27    5393  185.42  5900.2  186.85  6055.4  187.56
#Mann= 6 ,-1 , 0
  3830.7     .17       0  4872.6     .15       0  4979.1     .09       0
  5016.6     .15       0    5158     .17       0  5900.2     .11       0
Bank Sta=4979.1,5016.6
XS Rating Curve= 0 ,0
Exp/Cntr=0.3,0.1

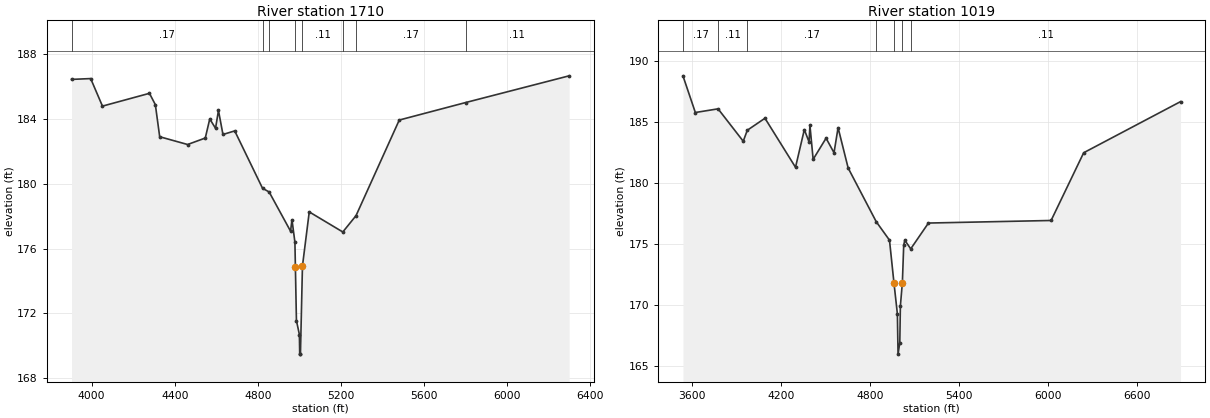
Type RM Length L Ch R = 1 ,1710    ,691,691,691
BEGIN DESCRIPTION:
LAKE CREEK TRIBUTARY NO. 14 3.0
END DESCRIPTION:
XS GIS Cut Line= 3
      3760317.83     10097011.05      3759507.97     10096265.08
      3758344.75     10096833.67
#Sta/Elev= 30
  3903.1  186.44  3995.2  186.49  4051.9  184.79  4278.2  185.58  4306.6  184.88
  4327.5   182.9  4461.9  182.42    4547  182.82  4568.6     184  4596.4  183.42
  4610.5  184.52  4632.1  183.04  4688.8  183.26  4822.6  179.72  4854.5  179.49
  4957.6  177.07  4964.4  177.77  4978.6  176.39 4980.93174.8451  4985.9  171.55
  5000.1  170.69  5001.7  169.48  5005.2  169.48  5014.9 174.919  5047.6  178.26
  5209.2  177.02  5272.9  178.03    5481  183.93  5800.4  185.01  6298.9  186.66
#Mann= 8 ,-1 , 0
  3903.1     .17       0  4822.6     .15       0  4854.5     .11       0
 4980.93     .06       0  5014.9     .11       0  5209.2     .15       0
  5272.9     .17       0  5800.4     .11       0
Bank Sta=4980.93,5014.9
XS Rating Curve= 0 ,0
Exp/Cntr=0.3,0.1

Type RM Length L Ch R = 1 ,1019    ,0,0,0
BEGIN DESCRIPTION:
LAKE CREEK TRIBUTARY NO. 14 2.0
END DESCRIPTION:
XS GIS Cut Line= 4
      3760488.86     10097094.06      3759778.23     10095816.84
      3759629.49     10095744.25      3758271.91     10096811.23
#Sta/Elev= 30
  3538.4  188.75  3621.9  185.75  3775.1  186.05  3944.8   183.4  3972.2   184.3
  4091.2  185.28  4297.1  181.27  4356.5  184.35  4388.5  183.34  4394.2  184.71
  4415.9  181.92  4503.1  183.65  4556.6  182.46    4584  184.51  4651.9  181.21
  4841.2  176.82  4930.5  175.31  4960.8   171.8  4983.7  169.28  4988.2  165.99
    5000  166.93  5003.9  169.93 5017.36171.8405  5026.4  174.91  5033.8   175.3
  5073.7   174.6    5193  176.71  6019.8  176.92  6239.4  182.46  6892.2  186.64
#Mann= 7 ,-1 , 0
  3538.4     .17       0  3775.1     .11       0  3972.2     .17       0
  4841.2     .15       0  4960.8     .09       0 5017.36     .15       0
  5073.7     .11       0
Bank Sta=4960.8,5017.36
XS Rating Curve= 0 ,0
Exp/Cntr=0.3,0.1

Chan Stop Cuts=-1
Use User Specified Reach Order=0
Composite Channel Slope=5