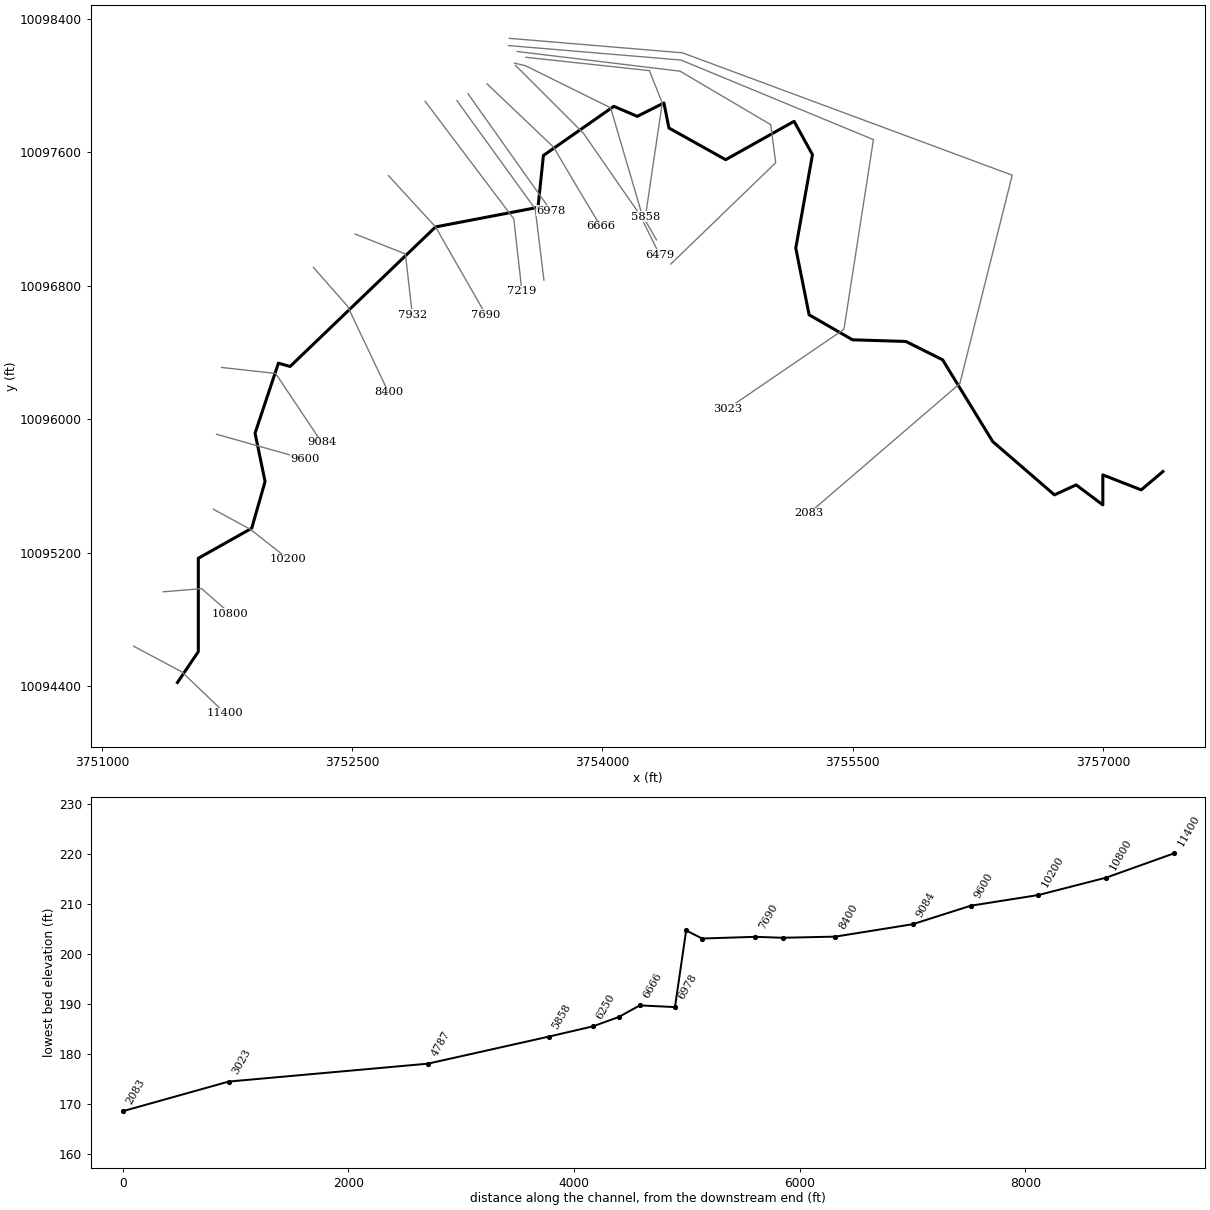
--- LAKE CREEK TRIBUTARY NO 15.prj (project) ---

Proj Title=LAKE CREEK TRIBUTARY NO 15 Base Level Engineering
Current Plan=p01
Default Exp/Contr=0.3,0.1
English Units
Geom File=g01
Flow File=f01
Flow File=f02
Plan File=p01
Y Axis Title=Elevation
X Axis Title(PF)=Main Channel Distance
X Axis Title(XS)=Station
BEGIN DESCRIPTION:
LAKE CREEK TRIBUTARY NO 15
END DESCRIPTION:
DSS Export Rating Curves= 0
DSS Export Rating Curve Sorted= 0
DSS Export Volume Flow Curves= 0
DXF OffsetX= 0
DXF OffsetY= 0
DXF ScaleX= 1
DXF ScaleY= 10

--- LAKE CREEK TRIBUTARY NO 15.p01 (plan) ---

Plan Title=Multiple Run
Short Identifier=Multiple
Geom File=g01
Flow File=f01
Subcritical Flow
K Sum by GR= 0
Std Step Tol= 0.01
Critical Tol= 0.01
Num of Std Step Trials= 20
Max Error Tol= 0.3
Flow Tol Ratio= 0.001
Split Flow NTrial= 30
Split Flow Tol= 0.02
Split Flow Ratio= 0.02
Log Output Level= 0
Friction Slope Method= 1
Unsteady Friction Slope Method= 2
Unsteady Bridges Friction Slope Method= 1
Parabolic Critical Depth
Global Vel Dist=  1 , 1 , 1
Global Log Level= 0
CheckData=True
Encroach Param= -1, 0, 0, 0
BEGIN DESCRIPTION:
Multiple Run
END DESCRIPTION:

--- LAKE CREEK TRIBUTARY NO 15.f01 (steady flow) ---

Flow Title=Multiple
Program Version=4.10
Number of Profiles= 7
Profile Names=10-year,25-year,50-year,1pct_min,100-year,1pct_plu,500-year
River Rch & RM=LAKE CREEK TRIBU,Reach-1         ,11400
     724     990    1347     603    1820    5496    3438
River Rch & RM=LAKE CREEK TRIBU,Reach-1         ,7077
    1091    1528    2114     960    2900    8758    5652
River Rch & RM=LAKE CREEK TRIBU,Reach-1         ,3023
    1132    1577    2172     983    2968    8963    5731
Boundary for River Rch & Prof#=LAKE CREEK TRIBU,Reach-1         , 1
Up Type= 0
Dn Type= 3
Dn Slope=0.005
Boundary for River Rch & Prof#=LAKE CREEK TRIBU,Reach-1         , 2
Up Type= 0
Dn Type= 3
Dn Slope=0.005
Boundary for River Rch & Prof#=LAKE CREEK TRIBU,Reach-1         , 3
Up Type= 0
Dn Type= 3
Dn Slope=0.005
Boundary for River Rch & Prof#=LAKE CREEK TRIBU,Reach-1         , 4
Up Type= 0
Dn Type= 3
Dn Slope=0.005
Boundary for River Rch & Prof#=LAKE CREEK TRIBU,Reach-1         , 5
Up Type= 0
Dn Type= 3
Dn Slope=0.005
Boundary for River Rch & Prof#=LAKE CREEK TRIBU,Reach-1         , 6
Up Type= 0
Dn Type= 3
Dn Slope=0.005
Boundary for River Rch & Prof#=LAKE CREEK TRIBU,Reach-1         , 7
Up Type= 0
Dn Type= 3
Dn Slope=0.005
DSS Import GetInterval= 0
DSS Import GetPeak= 0
DSS Import FillOption= 0

--- LAKE CREEK TRIBUTARY NO 15.f02 (steady flow) ---

Flow Title=Orig_BLE_Flows
Program Version=4.10
Number of Profiles= 7
Profile Names=10-year,25-year,50-year,1pct_min,100-year,1pct_plu,500-year
River Rch & RM=LAKE CREEK TRIBU,Reach-1         ,11400
     724     971    1171     464    1400    4229    1999
River Rch & RM=LAKE CREEK TRIBU,Reach-1         ,7077
    1091    1498    1838     739    2231    6738    3286
River Rch & RM=LAKE CREEK TRIBU,Reach-1         ,3023
    1132    1546    1889     756    2283    6895    3332
Boundary for River Rch & Prof#=LAKE CREEK TRIBU,Reach-1         , 1
Up Type= 0
Dn Type= 3
Dn Slope=0.005
Boundary for River Rch & Prof#=LAKE CREEK TRIBU,Reach-1         , 2
Up Type= 0
Dn Type= 3
Dn Slope=0.005
Boundary for River Rch & Prof#=LAKE CREEK TRIBU,Reach-1         , 3
Up Type= 0
Dn Type= 3
Dn Slope=0.005
Boundary for River Rch & Prof#=LAKE CREEK TRIBU,Reach-1         , 4
Up Type= 0
Dn Type= 3
Dn Slope=0.005
Boundary for River Rch & Prof#=LAKE CREEK TRIBU,Reach-1         , 5
Up Type= 0
Dn Type= 3
Dn Slope=0.005
Boundary for River Rch & Prof#=LAKE CREEK TRIBU,Reach-1         , 6
Up Type= 0
Dn Type= 3
Dn Slope=0.005
Boundary for River Rch & Prof#=LAKE CREEK TRIBU,Reach-1         , 7
Up Type= 0
Dn Type= 3
Dn Slope=0.005
DSS Import GetInterval= 0
DSS Import GetPeak= 0
DSS Import FillOption= 0

--- LAKE CREEK TRIBUTARY NO 15.g01 (geometry) ---

Geom Title=Existing Conditions
Program Version=4.10

River Reach=LAKE CREEK TRIBU,Reach-1
Reach XY= 30
      3751453.23     10094421.84      3751578.23     10094606.84
      3751578.23     10095166.84      3751898.23     10095346.84
      3751978.23     10095626.84      3751918.23     10095916.84
      3752058.23     10096336.84      3752128.23     10096316.84
       3752999.8     10097153.74      3753613.59     10097271.04
      3753646.08     10097582.05      3754068.23     10097876.84
      3754208.23     10097816.84      3754368.23     10097896.84
      3754398.23     10097746.84      3754738.23     10097556.84
      3755148.23     10097786.84      3755258.23     10097586.84
      3755158.23     10097026.84      3755238.23     10096626.84
      3755498.23     10096476.84      3755818.23     10096466.84
      3756038.23     10096356.84      3756338.23     10095866.84
      3756708.23     10095546.84      3756838.23     10095606.84
      3756998.23     10095486.84      3756998.23     10095666.84
      3757228.23     10095576.84      3757358.23     10095686.84

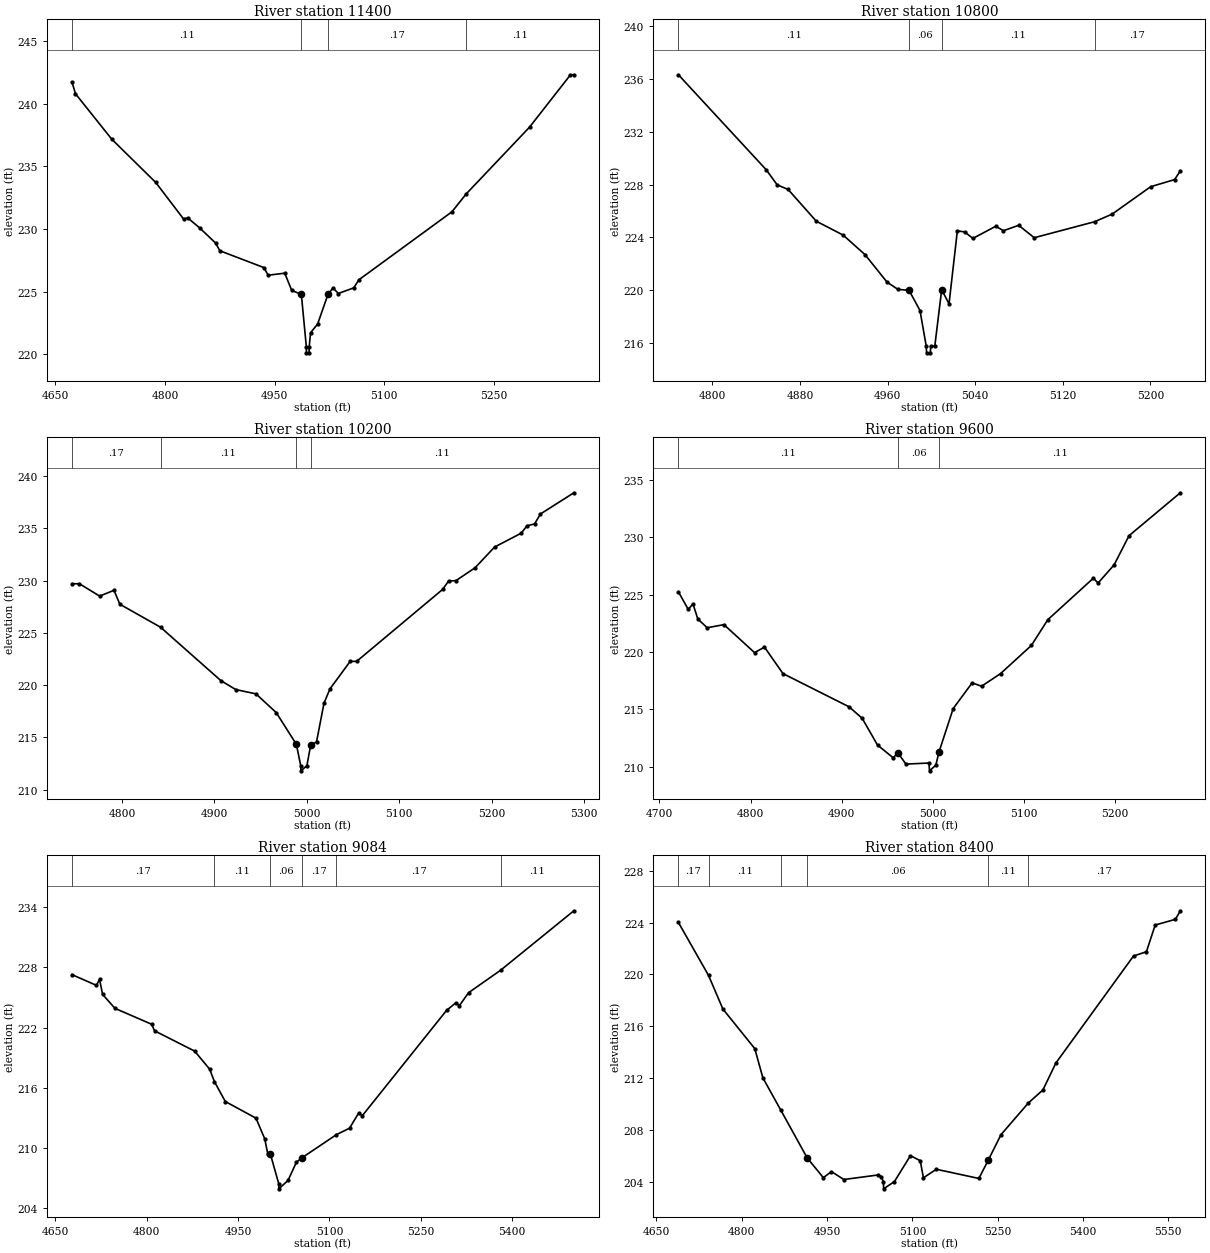
Type RM Length L Ch R = 1 ,11400   ,600,600,600
BEGIN DESCRIPTION:
LAKE CREEK TRIBUTARY NO. 15 19.0
END DESCRIPTION:
XS GIS Cut Line= 3
      3751190.87     10094639.53      3751479.63     10094485.45
      3751739.49     10094236.74
#Sta/Elev= 30
  4672.7  241.72  4677.5  240.78  4727.1  237.16  4787.3  233.71  4825.5  230.79
  4831.2  230.88  4847.5  230.08  4869.4  228.87  4875.1  228.26  4935.3  226.92
  4941.3  226.31    4964  226.47  4973.5   225.1  4986.7  224.78  4993.5  220.62
  4993.7  220.12  4997.2  220.12  4997.5  220.62  4999.3  221.72    5009  222.42
  5023.2  224.79  5030.1   225.3  5037.3  224.85  5058.4   225.3  5065.6  225.95
  5192.7  231.36  5212.5   232.8    5299  238.11  5355.1  242.29  5359.7  242.29
#Mann= 4 ,-1 , 0
  4672.7     .11       0  4986.7     .09       0  5023.2     .17       0
  5212.5     .11       0
Bank Sta=4986.7,5023.2
XS Rating Curve= 0 ,0
Exp/Cntr=0.3,0.1

Type RM Length L Ch R = 1 ,10800   ,600,600,600
BEGIN DESCRIPTION:
LAKE CREEK TRIBUTARY NO. 15 18.0
END DESCRIPTION:
XS GIS Cut Line= 3
      3751367.97     10094965.92      3751598.23     10094984.45
      3751769.52     10094835.03
#Sta/Elev= 30
    4769  236.31  4849.1  229.13  4859.2  227.98  4869.2  227.63  4894.9  225.23
  4919.4  224.18  4939.4   222.7  4959.5  220.62  4969.5  220.07  4979.6     220
  4989.6  218.47  4995.3  215.77  4995.6  215.27  4999.1  215.27  4999.3  215.77
  5003.1  215.77  5009.4  220.05  5016.1  218.98  5023.7   224.5  5030.3  224.42
  5037.9  223.93  5058.8  224.85  5065.8  224.51  5079.7  224.92  5093.9  223.98
    5149  225.19  5165.1  225.77  5200.2  227.84  5222.1  228.38  5227.3  229.04
#Mann= 4 ,-1 , 0
    4769     .11       0  4979.6     .06       0  5009.4     .11       0
    5149     .17       0
Bank Sta=4979.6,5009.4
XS Rating Curve= 0 ,0
Exp/Cntr=0.3,0.1

Type RM Length L Ch R = 1 ,10200   ,600,600,600
BEGIN DESCRIPTION:
LAKE CREEK TRIBUTARY NO. 15 17.0
END DESCRIPTION:
XS GIS Cut Line= 3
      3751667.85     10095461.07       3751891.1     10095339.71
      3752117.88     10095161.05
#Sta/Elev= 30
  4745.9   229.7    4754   229.7  4775.8  228.52  4791.4  229.07  4797.7  227.74
  4841.7  225.54  4906.9  220.43  4923.1  219.57  4944.9  219.16  4966.8  217.37
  4988.6  214.33  4993.3  212.29  4993.6  211.79    5000  212.29  5004.1  214.26
  5010.4  214.56  5018.5  218.27  5024.9  219.63  5046.8  222.27  5053.8  222.27
  5146.8  229.16  5153.2  229.96  5161.2     230    5182  231.24  5202.9  233.21
  5231.7  234.54  5238.1  235.25  5246.2  235.43  5252.6  236.38  5288.7  238.41
#Mann= 4 ,-1 , 0
  4745.9     .17       0  4841.7     .11       0  4988.6     .06       0
  5004.1     .11       0
Bank Sta=4988.6,5004.1
XS Rating Curve= 0 ,0
Exp/Cntr=0.3,0.1

Type RM Length L Ch R = 1 ,9600    ,516,516,516
BEGIN DESCRIPTION:
LAKE CREEK TRIBUTARY NO. 15 16.0
END DESCRIPTION:
XS GIS Cut Line= 3
      3751687.39     10095910.37      3751956.16     10095834.77
      3752217.88     10095761.06
#Sta/Elev= 30
  4720.8  225.26  4731.6  223.73  4736.8  224.21  4742.1  222.89  4752.4  222.13
  4770.8   222.4  4804.4  219.96  4815.3  220.44  4835.6  218.13  4908.3  215.23
  4922.6  214.23  4939.4   211.9  4956.6  210.79  4961.8  211.22  4970.6  210.24
  4995.9  210.33  4996.5  209.65  5003.5  210.15  5006.8211.2651  5022.5  215.08
  5043.3  217.32  5053.7  217.03  5074.5  218.13  5108.4  220.59  5126.4  222.83
  5176.4  226.45  5181.6  226.03  5199.2  227.61  5215.6  230.16  5271.9   233.9
#Mann= 3 , 0 , 0
  4720.8     .11       0  4961.8     .06       0  5006.8     .11       0
Bank Sta=4961.8,5006.8
XS Rating Curve= 0 ,0
Exp/Cntr=0.3,0.1

Type RM Length L Ch R = 1 ,9084    ,684,684,684
BEGIN DESCRIPTION:
LAKE CREEK TRIBUTARY NO. 15 15.0
END DESCRIPTION:
XS GIS Cut Line= 3
      3751717.82     10096311.08      3752041.56     10096274.95
      3752317.86     10095861.05
#Sta/Elev= 30
  4677.6  227.28  4717.8  226.21  4722.8  226.81  4727.9  225.31  4748.1  223.92
  4808.2  222.34  4813.2  221.68  4878.9  219.66  4903.5  217.86  4911.4  216.61
  4929.2  214.64  4979.5  212.98  4993.9  210.92    4999  209.37  5003.3  209.37
  5016.9  206.44  5017.1  205.94  5032.1  206.78  5045.9   208.6  5054.9  209.03
  5111.5  211.34    5133  211.98    5148  213.49    5154  213.23  5292.2  223.72
  5307.2  224.46  5313.2  224.19  5328.3  225.48  5380.9  227.72    5501  233.64
#Mann= 6 ,-1 , 0
  4677.6     .17       0  4911.4     .11       0  5003.3     .06       0
  5054.9     .17       0  5111.5     .17       0  5380.9     .11       0
Bank Sta=5003.3,5054.9
XS Rating Curve= 0 ,0
Exp/Cntr=0.3,0.1

Type RM Length L Ch R = 1 ,8400    ,468,468,468
BEGIN DESCRIPTION:
LAKE CREEK TRIBUTARY NO. 15 14.0
END DESCRIPTION:
XS GIS Cut Line= 3
      3752267.88     10096911.04      3752473.19     10096677.05
      3752717.83     10096161.11
#Sta/Elev= 30
  4688.7  224.01  4741.7  219.92  4766.9  217.33  4822.9  214.28  4837.2  212.02
  4868.2  209.57    4915  205.85  4943.5  204.32  4957.7  204.79  4979.5  204.18
  5039.8  204.53  5045.6   204.4  5049.2  203.96  5049.4  203.46  5068.4  204.02
  5096.6  206.02  5113.8  205.63  5119.4  204.31  5142.1  204.97  5216.9  204.26
  5233.1  205.65  5255.8  207.64  5303.8  210.08  5329.5  211.09  5352.3  213.17
  5488.7  221.42  5511.4  221.75  5526.8  223.81  5562.4  224.25    5571  224.91
#Mann= 6 ,-1 , 0
  4688.7     .17       0  4741.7     .11       0  4868.2     .17       0
    4915     .06       0  5233.1     .11       0  5303.8     .17       0
Bank Sta=4915,5233.1
XS Rating Curve= 0 ,0
Exp/Cntr=0.3,0.1

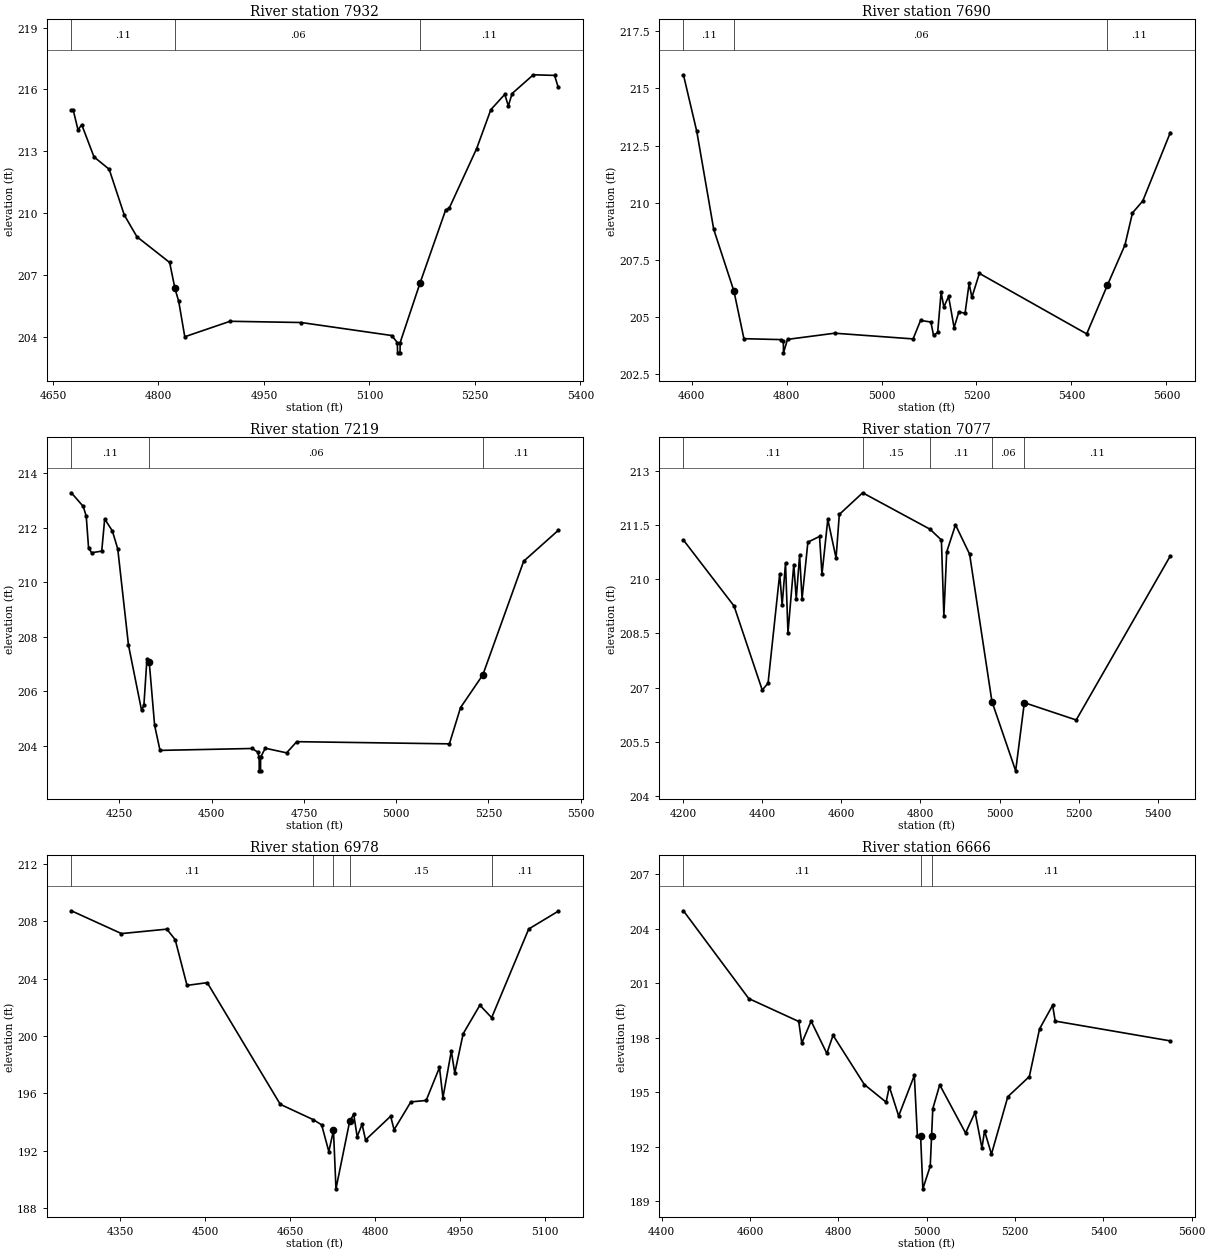
Type RM Length L Ch R = 1 ,7932    ,242,242,242
BEGIN DESCRIPTION:
LAKE CREEK TRIBUTARY NO. 15 13.0
END DESCRIPTION:
XS GIS Cut Line= 3
      3752517.87     10097111.06      3752818.93     10096991.85
      3752860.98     10096625.86
#Sta/Elev= 30
  4676.2     215  4678.9     215  4685.7  214.04    4691  214.29  4708.4  212.73
    4730  212.13  4751.5  209.91  4769.4  208.86    4816  207.61  4823.5  206.35
  4828.9  205.72  4837.5  204.01  4901.9  204.76  5002.9   204.7  5131.6  204.07
  5139.7  203.73    5140  203.23  5143.5  203.23  5143.7  203.73  5171.9  206.61
  5208.4  210.16  5213.4  210.24  5252.4  213.13  5272.6  215.02  5292.4  215.76
  5297.5   215.2  5302.8   215.8    5333  216.71  5363.2  216.68  5368.4   216.1
#Mann= 3 , 0 , 0
  4676.2     .11       0  4823.5     .06       0  5171.9     .11       0
Bank Sta=4823.5,5171.9
XS Rating Curve= 0 ,0
Exp/Cntr=0.3,0.1

Type RM Length L Ch R = 1 ,7690    ,471,471,471
BEGIN DESCRIPTION:
LAKE CREEK TRIBUTARY NO. 15 12.0
END DESCRIPTION:
XS GIS Cut Line= 3
      3752717.83     10097461.09       3752999.8     10097153.74
      3753301.86     10096625.85
#Sta/Elev= 30
  4582.9   215.6    4611  213.12  4646.7  208.83  4689.3  206.12  4710.3  204.04
    4788     204  4793.3  203.92  4793.6  203.42  4802.1  204.01  4901.4  204.28
  5066.5  204.03  5082.3  204.84  5103.9  204.77  5109.7  204.18  5118.3  204.32
  5125.5  206.07  5131.3  205.43  5141.3  205.89  5152.9  204.52  5162.9  205.22
  5175.9  205.15  5184.5  206.46  5190.3  205.85  5206.1   206.9  5432.1  204.25
  5475.4  206.37  5512.6  208.14  5528.5  209.55  5550.1  210.07  5608.2  213.07
#Mann= 3 , 0 , 0
  4582.9     .11       0  4689.3     .06       0  5475.4     .11       0
Bank Sta=4689.3,5475.4
XS Rating Curve= 0 ,0
Exp/Cntr=0.3,0.1

Type RM Length L Ch R = 1 ,7219    ,142,142,142
BEGIN DESCRIPTION:
Mapping XS 875c2c71
END DESCRIPTION:
XS GIS Cut Line= 3
      3752937.41     10097906.87      3753468.64     10097202.03
      3753517.25     10096768.05
#Sta/Elev= 30
  4119.8  213.28  4152.1  212.78  4160.2  212.42  4166.5  211.26  4174.8  211.08
  4202.2  211.14  4210.2  212.32    4231  211.88  4245.6  211.22  4274.7  207.69
  4310.1   205.3  4316.4  205.48  4324.7  207.19  4330.9  207.07  4345.5  204.75
  4360.1  203.83  4609.9   203.9  4624.5  203.77  4628.7  203.58    4629  203.08
  4632.5  203.08  4632.7  203.58  4645.3  203.91  4703.1  203.74  4730.7  204.15
  5144.2  204.07  5174.4   205.4  5234.8   206.6  5345.5  210.77  5439.1   211.9
#Mann= 3 , 0 , 0
  4119.8     .11       0  4330.9     .06       0  5234.8     .11       0
Bank Sta=4330.9,5234.8
XS Rating Curve= 0 ,0
Exp/Cntr=0.3,0.1

Type RM Length L Ch R = 1 ,7077    ,99,99,99
BEGIN DESCRIPTION:
LAKE CREEK TRIBUTARY NO. 15 11.0
END DESCRIPTION:
XS GIS Cut Line= 3
      3753128.38     10097910.35      3753597.11     10097261.06
      3753649.07     10096835.03
#Sta/Elev= 30
  4201.3  211.09  4329.2  209.26  4400.4  206.93  4415.1  207.12  4444.5  210.15
  4450.7  209.29  4459.2  210.45  4465.4  208.52  4480.1  210.41  4486.3  209.46
  4494.8  210.67    4501  209.46  4515.7  211.03  4545.1  211.19  4551.3  210.14
    4566  211.66  4586.9  210.59  4595.1   211.8  4654.1   212.4  4824.2  211.39
    4853  211.09  4859.2  208.99  4866.4  210.76  4888.6  211.51  4924.2   210.7
  4980.7  206.61  5040.6  204.69  5062.5  206.58  5193.5   206.1  5431.3  210.65
#Mann= 5 ,-1 , 0
  4201.3     .11       0  4654.1     .15       0  4824.2     .11       0
  4980.7     .06       0  5062.5     .11       0
Bank Sta=4980.7,5062.5
XS Rating Curve= 0 ,0
Exp/Cntr=0.3,0.1

Type RM Length L Ch R = 1 ,6978    ,312,312,312
BEGIN DESCRIPTION:
Mapping XS 5b1dcb99
END DESCRIPTION:
XS GIS Cut Line= 2
      3753194.33     10097952.04      3753690.89     10097250.62
#Sta/Elev= 30
  4263.5  208.73    4352  207.14  4432.1  207.45  4446.8  206.72  4467.7  203.53
  4503.4  203.72  4632.3  195.24  4690.6  194.17  4705.3  193.81    4718  191.95
  4726.2  193.42  4730.6  189.35  4754.8  194.06  4761.9  194.55    4768  192.99
  4776.7  193.85  4782.8  192.76  4827.1  194.41  4833.2  193.47  4862.8  195.41
  4889.8  195.51  4913.3  197.81  4919.4   195.7  4934.2  198.95  4940.3  197.42
  4955.1  200.16  4984.6  202.15  5005.4  201.28  5070.8  207.46  5122.9   208.7
#Mann= 5 ,-1 , 0
  4263.5     .11       0  4690.6     .15       0  4726.2     .09       0
  4754.8     .15       0  5005.4     .11       0
Bank Sta=4726.2,4754.8
XS Rating Curve= 0 ,0
Exp/Cntr=0.3,0.1

Type RM Length L Ch R = 1 ,6666    ,187,187,187
BEGIN DESCRIPTION:
LAKE CREEK TRIBUTARY NO. 15 10.0
END DESCRIPTION:
XS GIS Cut Line= 4
      3753308.91     10098011.07      3753707.61     10097631.19
      3753864.48     10097365.23      3753989.46     10097156.92
#Sta/Elev= 30
  4449.3  204.99  4597.2  200.16  4710.3   198.9  4717.3  197.71  4738.4  198.92
    4774  197.14  4788.1  198.14  4858.9  195.43  4908.2  194.46  4915.5  195.31
  4936.6   193.7  4972.1  195.93    4979  192.61  4986.3  192.59  4991.4  189.69
  5008.1  190.94 5011.13192.5908  5013.9   194.1  5029.6  195.41  5088.1  192.76
  5109.6   193.9  5125.2  191.93    5131  192.88  5146.7   191.6  5183.8  194.76
  5232.5  195.87  5255.6  198.49  5285.2  199.79    5291  198.92  5551.7  197.83
#Mann= 3 , 0 , 0
  4449.3     .11       0  4986.3     .06       0 5011.13     .11       0
Bank Sta=4986.3,5011.13
XS Rating Curve= 0 ,0
Exp/Cntr=0.3,0.1

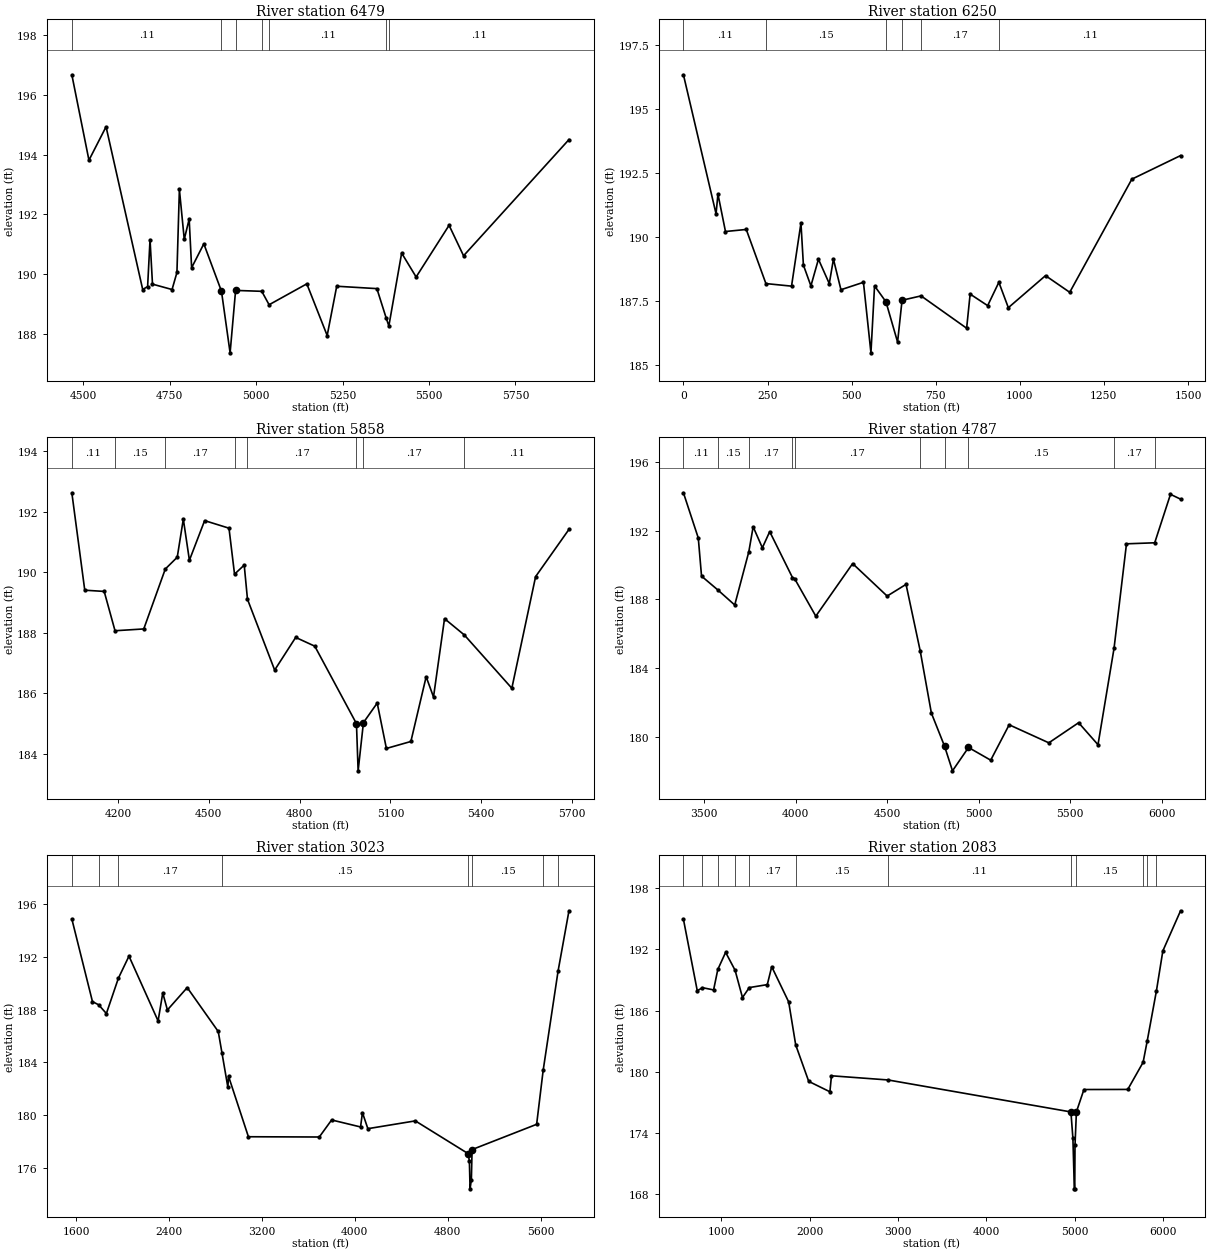
Type RM Length L Ch R = 1 ,6479    ,229,229,229
BEGIN DESCRIPTION:
Mapping XS 2304869f
END DESCRIPTION:
XS GIS Cut Line= 4
      3753479.02     10098122.21      3753885.31     10097715.92
      3754222.11     10097229.81      3754342.87     10096986.04
#Sta/Elev= 30
    4467  196.67  4516.5  193.81    4566  194.93    4672  189.48  4686.2  189.58
  4693.2  191.15  4700.3  189.66  4756.9  189.48    4771  190.05  4778.1  192.83
  4792.2  191.16  4806.4  191.84  4813.5  190.21  4848.8  191.01 4899.83189.4226
  4924.8  187.36  4940.7  189.45  5016.4  189.42  5037.6  188.97  5146.7  189.67
  5205.6  187.94  5233.2  189.59  5349.4  189.51  5376.7  188.51    5384  188.26
    5421   190.7  5462.9   189.9  5558.2  191.63  5600.1  190.61    5905   194.5
#Mann= 7 ,-1 , 0
    4467     .11       0 4899.83     .07       0  4940.7     .11       0
  5016.4     .17       0  5037.6     .11       0  5376.7     .17       0
    5384     .11       0
Bank Sta=4899.83,4940.7
XS Rating Curve= 0 ,0
Exp/Cntr=0.3,0.1

Type RM Length L Ch R = 1 ,6250    ,392,392,392
BEGIN DESCRIPTION:
LAKE CREEK TRIBUTARY NO. 15 9.0
END DESCRIPTION:
XS GIS Cut Line= 5
      3753472.92     10098135.99      3753539.26     10098119.88
      3754048.85     10097867.99      3754238.08     10097223.89
      3754324.01     10097075.73
#Sta/Elev= 30
       0  196.33      97  190.91   102.6  191.68     125  190.22   186.8   190.3
   245.2  188.19   321.4  188.09   349.4  190.55   356.7  188.91     379   188.1
   401.4  189.14   433.6  188.19     446  189.14   468.3  187.95   535.2  188.24
   557.5  185.49   568.2   188.1   602.1  187.48   636.7  185.91     650  187.54
   706.5  187.71     842  186.45   852.4  187.78   904.5  187.33   937.8  188.24
     966  187.25  1076.5   188.5  1148.5  187.85  1333.1  192.26    1478  193.18
#Mann= 6 ,-1 , 0
       0     .11       0   245.2     .15       0   602.1     .09       0
     650     .15       0   706.5     .17       0   937.8     .11       0
Bank Sta=602.1,650
XS Rating Curve= 0 ,0
Exp/Cntr=0.3,0.1

Type RM Length L Ch R = 1 ,5858    ,1071,1071,1071
BEGIN DESCRIPTION:
LAKE CREEK TRIBUTARY NO. 15 8.0
END DESCRIPTION:
XS GIS Cut Line= 4
      3753541.57     10098170.78      3754281.14     10098090.92
      3754358.23     10097896.84      3754257.11     10097214.29
#Sta/Elev= 30
  4047.3  192.62    4090   189.4  4154.2  189.36    4190  188.06    4285  188.12
  4356.1   190.1  4395.6  190.49  4415.7  191.75  4435.8  190.39  4486.1   191.7
  4566.6  191.45  4584.9  189.93  4616.9  190.23  4627.7   189.1  4717.5  186.76
    4787  187.84  4850.1  187.55  4987.8  184.99  4993.3  183.43 5010.84 185.024
  5056.4  185.67  5086.7  184.17  5167.6   184.4  5218.1  186.54  5242.4  185.87
  5278.8  188.46  5344.3  187.92  5501.2  186.16  5579.8  189.85    5690  191.41
#Mann= 8 ,-1 , 0
  4047.3     .11       0    4190     .15       0  4356.1     .17       0
  4584.9     .15       0  4627.7     .17       0  4987.8     .09       0
 5010.84     .17       0  5344.3     .11       0
Bank Sta=4987.8,5010.84
XS Rating Curve= 0 ,0
Exp/Cntr=0.3,0.1

Type RM Length L Ch R = 1 ,4787    ,1764,1764,1764
BEGIN DESCRIPTION:
LAKE CREEK TRIBUTARY NO. 15 7.0
END DESCRIPTION:
XS GIS Cut Line= 5
      3753489.52      10098205.5      3754465.17     10098087.45
      3755008.23     10097766.84      3755038.09     10097538.84
      3754409.64     10096931.23
#Sta/Elev= 30
  3386.6   194.2  3467.8  191.57  3485.6  189.35  3575.3  188.54    3667  187.67
  3744.1  190.77  3767.7  192.22  3818.1     191  3858.3  191.94  3982.5  189.27
    3994  189.21  4110.2  187.02  4311.6  190.08  4500.2  188.19  4603.5  188.87
  4680.9     185    4742  181.38  4813.8  179.46  4857.4  178.02  4944.9  179.38
  5066.3  178.64  5167.2   180.7    5384  179.65  5546.8  180.82  5652.8  179.54
  5740.5  185.15  5808.5  191.23  5962.8  191.29    6049  194.11  6104.1  193.83
#Mann= 10 ,-1 , 0
  3386.6     .11       0  3575.3     .15       0  3744.1     .17       0
  3982.5     .15       0    3994     .17       0  4680.9     .15       0
  4813.8     .09       0  4944.9     .15       0  5740.5     .17       0
  5962.8     .11       0
Bank Sta=4813.8,4944.9
XS Rating Curve= 0 ,0
Exp/Cntr=0.3,0.1

Type RM Length L Ch R = 1 ,3023    ,940,940,940
BEGIN DESCRIPTION:
LAKE CREEK TRIBUTARY NO. 15 5.0
END DESCRIPTION:
XS GIS Cut Line= 5
      3753437.41     10098241.09      3754470.38     10098154.29
      3755623.71     10097677.04      3755446.94     10096539.71
      3754748.14     10096062.26
#Sta/Elev= 30
  1563.1  194.85  1740.8   188.6  1793.8  188.36  1860.7   187.7  1964.1  190.37
  2055.3  192.04  2306.1  187.14  2346.3  189.25  2386.4  187.97    2557  189.66
  2824.2  186.34  2856.3  184.72  2907.1  182.12  2912.6  182.96    3084  178.38
  3694.5  178.36  3800.9  179.65    4050  179.12  4066.4   180.2  4112.9  178.99
  4521.8  179.58  4977.2   177.1  4987.4  176.53  4993.4  174.44  5004.6  175.14
  5010.6  177.41  5566.7  179.32  5622.9   183.4  5751.4  190.91  5845.2  195.47
#Mann= 8 ,-1 , 0
  1563.1     .11       0  1793.8     .15       0  1964.1     .17       0
  2856.3     .15       0  4977.2     .09       0  5010.6     .15       0
  5622.9     .17       0  5751.4     .11       0
Bank Sta=4977.2,5010.6
XS Rating Curve= 0 ,0
Exp/Cntr=0.3,0.1

Type RM Length L Ch R = 1 ,2083    ,0,0,0
BEGIN DESCRIPTION:
LAKE CREEK TRIBUTARY NO. 15 3.0
END DESCRIPTION:
XS GIS Cut Line= 5
       3753441.7      10098284.5      3754479.06     10098197.69
      3756455.28     10097463.84      3756141.39     10096214.19
      3755238.59     10095437.26
#Sta/Elev= 30
   570.3  194.97     727  187.95   785.8  188.25   911.9  188.03   959.6  190.04
  1048.1  191.72  1155.2  189.96  1238.8  187.28  1316.2  188.26  1519.8  188.55
  1569.9  190.31  1762.1  186.85  1841.5  182.63    1989  179.05  2228.7  178.03
  2246.3   179.6  2886.7  179.19  4957.5  176.05  4980.1  173.45  4996.3   168.5
    5001   168.5  5003.8  172.77  5019.7  176.06  5104.8  178.25  5601.2  178.26
  5774.8  180.92    5821     183  5925.3  187.92  5998.4  191.86  6198.9   195.8
#Mann= 12 ,-1 , 0
   570.3     .11       0   785.8     .15       0   959.6     .17       0
  1155.2     .11       0  1316.2     .17       0  1841.5     .15       0
  2886.7     .11       0  4957.5     .09       0  5019.7     .15       0
  5774.8     .17       0    5821     .15       0  5925.3     .17       0
Bank Sta=4957.5,5019.7
XS Rating Curve= 0 ,0
Exp/Cntr=0.3,0.1

Chan Stop Cuts=-1
Use User Specified Reach Order=0
Composite Channel Slope=5