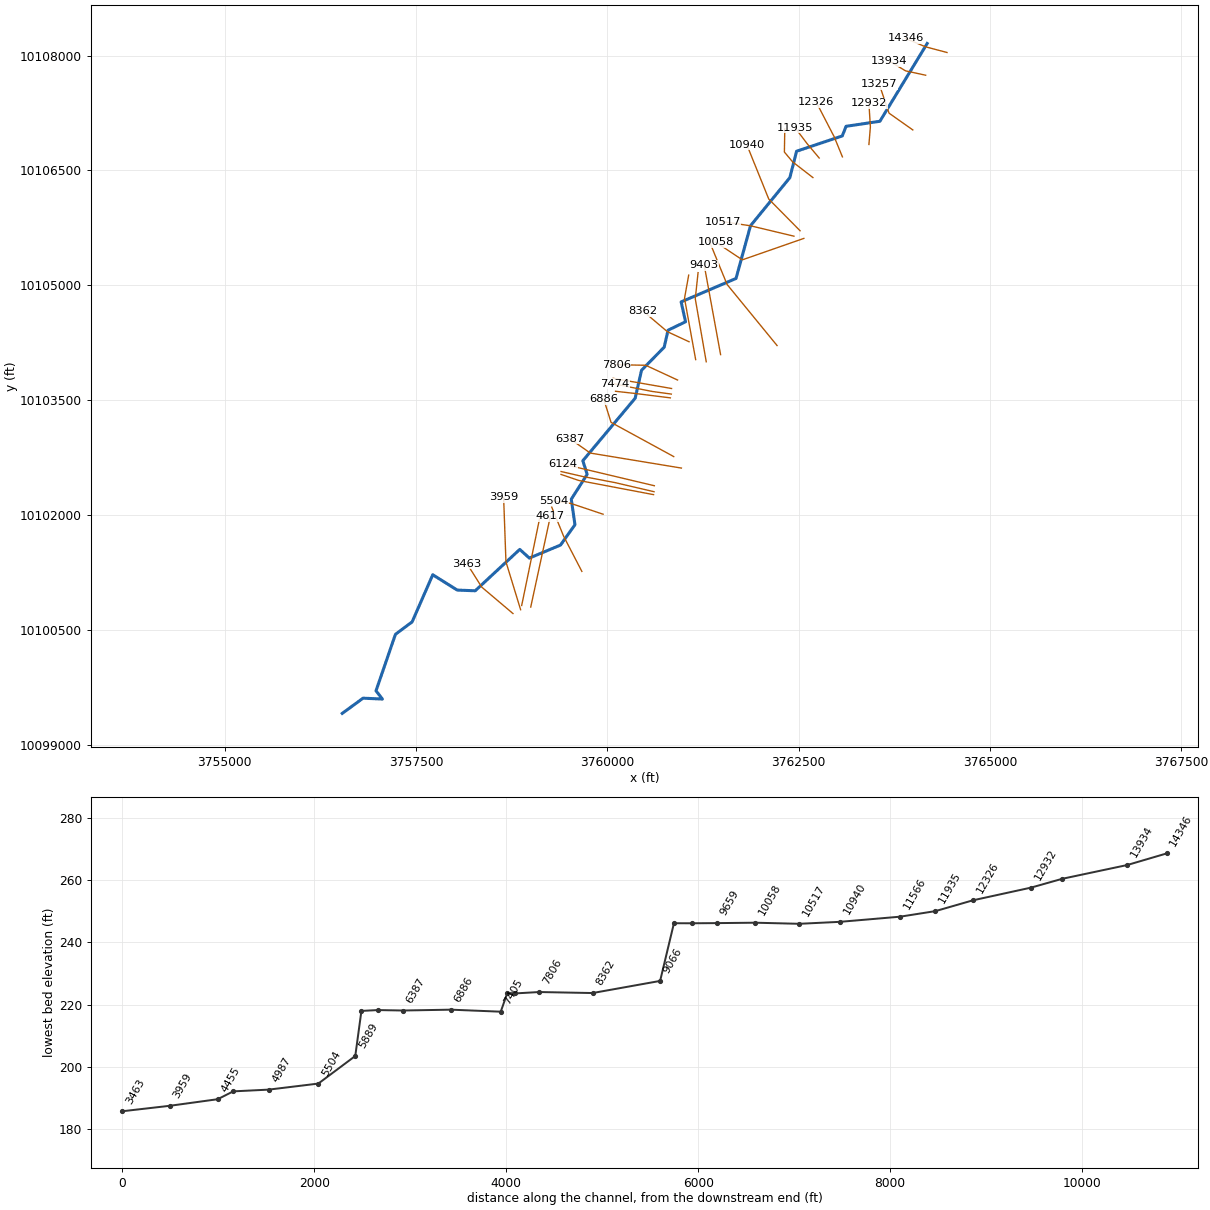
--- LAKE CREEK TRIBUTARY NO 16.prj (project) ---

Proj Title=LAKE CREEK TRIBUTARY NO 16 Base Level Engineering
Current Plan=p01
Default Exp/Contr=0.3,0.1
English Units
Geom File=g01
Flow File=f01
Flow File=f02
Plan File=p01
Y Axis Title=Elevation
X Axis Title(PF)=Main Channel Distance
X Axis Title(XS)=Station
BEGIN DESCRIPTION:
LAKE CREEK TRIBUTARY NO 16
END DESCRIPTION:
DSS Export Rating Curves= 0
DSS Export Rating Curve Sorted= 0
DSS Export Volume Flow Curves= 0
DXF OffsetX= 0
DXF OffsetY= 0
DXF ScaleX= 1
DXF ScaleY= 10

--- LAKE CREEK TRIBUTARY NO 16.p01 (plan) ---

Plan Title=Multiple Run
Short Identifier=Multiple
Geom File=g01
Flow File=f01
Subcritical Flow
K Sum by GR= 0
Std Step Tol= 0.01
Critical Tol= 0.01
Num of Std Step Trials= 20
Max Error Tol= 0.3
Flow Tol Ratio= 0.001
Split Flow NTrial= 30
Split Flow Tol= 0.02
Split Flow Ratio= 0.02
Log Output Level= 0
Friction Slope Method= 1
Unsteady Friction Slope Method= 2
Unsteady Bridges Friction Slope Method= 1
Parabolic Critical Depth
Global Vel Dist=  1 , 1 , 1
Global Log Level= 0
CheckData=True
Encroach Param= -1, 0, 0, 0
BEGIN DESCRIPTION:
Multiple Run
END DESCRIPTION:

--- LAKE CREEK TRIBUTARY NO 16.f01 (steady flow) ---

Flow Title=Multiple
Program Version=4.10
Number of Profiles= 7
Profile Names=10-year,25-year,50-year,1pct_min,100-year,1pct_plu,500-year
River Rch & RM=LAKE CREEK TRIBU,Reach-1         ,14346
     891    1239    1705     773    2334    7049    4515
River Rch & RM=LAKE CREEK TRIBU,Reach-1         ,11566
    1217    1720    2392    1094    3303    9975    6514
River Rch & RM=LAKE CREEK TRIBU,Reach-1         ,8362
    1652    2372    3334    1538    4646   14031    9340
Boundary for River Rch & Prof#=LAKE CREEK TRIBU,Reach-1         , 1
Up Type= 0
Dn Type= 3
Dn Slope=0.005
Boundary for River Rch & Prof#=LAKE CREEK TRIBU,Reach-1         , 2
Up Type= 0
Dn Type= 3
Dn Slope=0.005
Boundary for River Rch & Prof#=LAKE CREEK TRIBU,Reach-1         , 3
Up Type= 0
Dn Type= 3
Dn Slope=0.005
Boundary for River Rch & Prof#=LAKE CREEK TRIBU,Reach-1         , 4
Up Type= 0
Dn Type= 3
Dn Slope=0.005
Boundary for River Rch & Prof#=LAKE CREEK TRIBU,Reach-1         , 5
Up Type= 0
Dn Type= 3
Dn Slope=0.005
Boundary for River Rch & Prof#=LAKE CREEK TRIBU,Reach-1         , 6
Up Type= 0
Dn Type= 3
Dn Slope=0.005
Boundary for River Rch & Prof#=LAKE CREEK TRIBU,Reach-1         , 7
Up Type= 0
Dn Type= 3
Dn Slope=0.005
DSS Import GetInterval= 0
DSS Import GetPeak= 0
DSS Import FillOption= 0

--- LAKE CREEK TRIBUTARY NO 16.f02 (steady flow) ---

Flow Title=Orig_BLE_Flows
Program Version=4.10
Number of Profiles= 7
Profile Names=10-year,25-year,50-year,1pct_min,100-year,1pct_plu,500-year
River Rch & RM=LAKE CREEK TRIBU,Reach-1         ,14346
     891    1215    1483     594    1795    5421    2625
River Rch & RM=LAKE CREEK TRIBU,Reach-1         ,11566
    1217    1686    2080     841    2541    7674    3787
River Rch & RM=LAKE CREEK TRIBU,Reach-1         ,8362
    1652    2325    2899    1183    3574   10793    5430
Boundary for River Rch & Prof#=LAKE CREEK TRIBU,Reach-1         , 1
Up Type= 0
Dn Type= 3
Dn Slope=0.005
Boundary for River Rch & Prof#=LAKE CREEK TRIBU,Reach-1         , 2
Up Type= 0
Dn Type= 3
Dn Slope=0.005
Boundary for River Rch & Prof#=LAKE CREEK TRIBU,Reach-1         , 3
Up Type= 0
Dn Type= 3
Dn Slope=0.005
Boundary for River Rch & Prof#=LAKE CREEK TRIBU,Reach-1         , 4
Up Type= 0
Dn Type= 3
Dn Slope=0.005
Boundary for River Rch & Prof#=LAKE CREEK TRIBU,Reach-1         , 5
Up Type= 0
Dn Type= 3
Dn Slope=0.005
Boundary for River Rch & Prof#=LAKE CREEK TRIBU,Reach-1         , 6
Up Type= 0
Dn Type= 3
Dn Slope=0.005
Boundary for River Rch & Prof#=LAKE CREEK TRIBU,Reach-1         , 7
Up Type= 0
Dn Type= 3
Dn Slope=0.005
DSS Import GetInterval= 0
DSS Import GetPeak= 0
DSS Import FillOption= 0

--- LAKE CREEK TRIBUTARY NO 16.g01 (geometry) ---

Geom Title=Existing Conditions
Program Version=4.10

River Reach=LAKE CREEK TRIBU,Reach-1
Reach XY= 30
      3764178.23     10108156.84      3763560.92     10107140.97
      3763118.87     10107074.97      3763069.19     10106949.28
      3762472.44     10106749.59      3762385.01     10106405.35
      3761870.26     10105775.81      3761681.46     10105087.87
      3760964.44     10104781.67      3761022.33     10104522.24
      3760793.53     10104411.51      3760743.21      10104189.9
      3760447.53     10103889.04      3760364.17     10103523.67
      3759680.37     10102706.81      3759737.14     10102529.06
      3759529.53     10102204.31      3759577.35     10101871.16
      3759389.31     10101605.31      3758982.11     10101435.43
      3758856.63     10101548.59      3758274.79     10101008.19
      3758039.84     10101017.22      3757720.29     10101217.56
      3757450.55     10100601.56      3757232.68     10100439.46
      3756979.01     10099701.76      3757063.06     10099593.59
      3756809.97     10099605.46      3756538.23     10099406.84

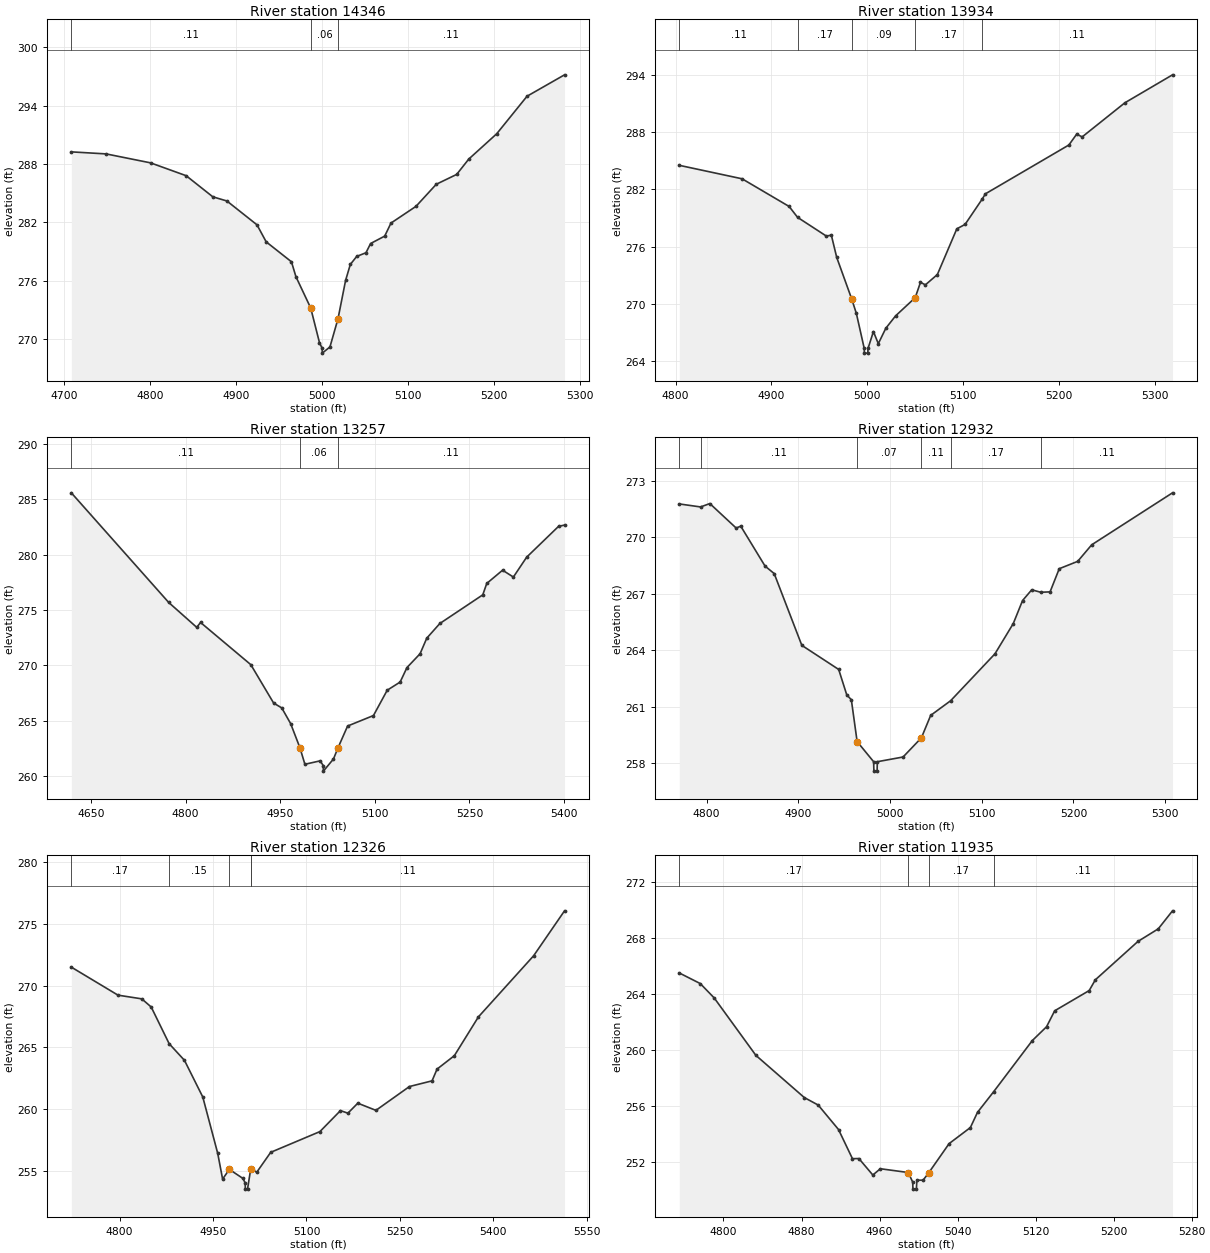
Type RM Length L Ch R = 1 ,14346   ,412,412,412
BEGIN DESCRIPTION:
LAKE CREEK TRIBUTARY NO. 16 25.0
END DESCRIPTION:
XS GIS Cut Line= 3
      3764436.94     10108039.31      3764153.07     10108114.83
      3763895.26      10108224.2
#Sta/Elev= 30
    4708  289.26  4748.5  289.05  4800.2  288.13  4841.6  286.81  4872.6  284.64
    4889  284.21    4924  281.76  4934.7  280.01  4964.1  277.96  4969.3  276.43
  4986.5  273.21  4996.7  269.65  4999.8  269.07    5000  268.57  5008.9  269.21
  5018.3  272.12  5027.1  276.05  5032.6  277.69    5040  278.51  5050.8  278.89
  5056.2  279.84  5072.6   280.6  5079.9  281.94    5109  283.66  5132.6  285.93
  5156.3  286.94  5170.4  288.52  5202.9  291.12  5238.2  294.98  5281.8  297.18
#Mann= 3 , 0 , 0
    4708     .11       0  4986.5     .06       0  5018.3     .11       0
Bank Sta=4986.5,5018.3
XS Rating Curve= 0 ,0
Exp/Cntr=0.3,0.1

Type RM Length L Ch R = 1 ,13934   ,677,677,677
BEGIN DESCRIPTION:
Mapping XS b7e9b9d3
END DESCRIPTION:
XS GIS Cut Line= 3
      3764158.29     10107742.43      3763895.25     10107799.73
      3763685.37      10107926.7
#Sta/Elev= 30
  4803.9  284.51  4869.4   283.1  4918.5   280.2  4927.3  279.06  4957.3   277.1
  4962.5   277.2  4968.1  274.87  4983.6270.5533  4988.6     269  4996.8  265.34
    4997  264.84  5000.5  264.84  5000.8  265.34  5006.4   267.1  5011.5  265.83
  5019.3  267.44  5029.5  268.74    5050  270.65  5055.5  272.26  5060.6  271.99
  5073.1  273.07  5093.4  277.86    5102  278.32  5119.7  280.95  5123.3  281.53
  5210.3  286.64  5218.4  287.77  5224.2  287.49  5268.7  291.06  5318.4  293.99
#Mann= 5 ,-1 , 0
  4803.9     .11       0  4927.3     .17       0  4983.6     .09       0
    5050     .17       0  5119.7     .11       0
Bank Sta=4983.6,5050
XS Rating Curve= 0 ,0
Exp/Cntr=0.3,0.1

Type RM Length L Ch R = 1 ,13257   ,325,325,325
BEGIN DESCRIPTION:
LAKE CREEK TRIBUTARY NO. 16 24.0
END DESCRIPTION:
XS GIS Cut Line= 3
      3763990.37     10107027.97      3763680.45     10107246.74
      3763550.82     10107627.83
#Sta/Elev= 30
  4618.8   285.6  4773.2  275.68  4817.6  273.43  4823.7  273.87  4903.4  270.05
  4939.5  266.58  4952.4  266.14  4966.5  264.72  4981.3  262.52  4989.1  261.04
  5013.3  261.35  5018.2  260.92  5018.4  260.42  5034.4  261.52 5041.66262.5405
  5056.8   264.5  5097.8  265.45  5119.6  267.74  5140.1  268.48  5150.9  269.79
  5171.7  271.04  5182.3  272.45  5203.1  273.78  5271.1  276.37  5277.4   277.4
  5302.5   278.6  5319.6  277.98  5340.7  279.78  5391.3  282.57  5400.7  282.68
#Mann= 3 , 0 , 0
  4618.8     .11       0  4981.3     .06       0 5041.66     .11       0
Bank Sta=4981.3,5041.66
XS Rating Curve= 0 ,0
Exp/Cntr=0.3,0.1

Type RM Length L Ch R = 1 ,12932   ,606,606,606
BEGIN DESCRIPTION:
LAKE CREEK TRIBUTARY NO. 16 23.0
END DESCRIPTION:
XS GIS Cut Line= 3
      3763417.43     10106837.89      3763436.45      10107066.9
      3763417.43     10107374.31
#Sta/Elev= 30
  4770.2  271.78  4793.4  271.62  4803.5   271.8  4832.2   270.5  4837.2   270.6
  4863.7  268.48  4873.7  268.08  4903.8  264.27    4944  262.99  4952.8  261.64
  4957.8  261.38  4964.1  259.16  4982.1  258.09  4982.4  257.59  4985.9  257.59
  4986.1  258.09  5014.2  258.34  5034.2  259.36  5044.3  260.55  5066.1  261.33
  5114.4  263.82  5134.4  265.43  5144.5  266.65  5154.5  267.22  5164.3  267.09
  5174.5  267.11  5184.5  268.34  5204.6  268.73  5219.9  269.61    5308  272.37
#Mann= 6 ,-1 , 0
  4770.2     .17       0  4793.4     .11       0  4964.1     .07       0
  5034.2     .11       0  5066.1     .17       0  5164.3     .11       0
Bank Sta=4964.1,5034.2
XS Rating Curve= 0 ,0
Exp/Cntr=0.3,0.1

Type RM Length L Ch R = 1 ,12326   ,391,391,391
BEGIN DESCRIPTION:
LAKE CREEK TRIBUTARY NO. 16 22.0
END DESCRIPTION:
XS GIS Cut Line= 3
      3763071.09     10106676.39       3762964.3     10106936.84
      3762729.95     10107389.93
#Sta/Elev= 30
  4722.6  271.49  4797.5  269.22  4835.7  268.92  4850.8  268.26  4879.6  265.29
  4904.2  263.94  4933.6  260.97  4957.6   256.4  4965.4  254.32  4976.2  255.11
  4997.9  254.38  5001.7  254.01  5001.9  253.51  5005.4  253.51  5010.5  255.13
  5010.9  255.22  5020.1  254.87  5042.6  256.49  5121.6  258.17  5154.6  259.87
  5166.5  259.66  5182.4  260.47  5211.5  259.89  5265.3  261.82  5301.6  262.28
  5309.6  263.23  5337.4  264.32    5376  267.46  5464.6  272.41  5514.2  276.05
#Mann= 5 ,-1 , 0
  4722.6     .17       0  4879.6     .15       0  4976.2     .09       0
  5010.5     .12       0  5010.9     .11       0
Bank Sta=4976.2,5010.5
XS Rating Curve= 0 ,0
Exp/Cntr=0.3,0.1

Type RM Length L Ch R = 1 ,11935   ,369,369,369
BEGIN DESCRIPTION:
LAKE CREEK TRIBUTARY NO. 16 21.0
END DESCRIPTION:
XS GIS Cut Line= 3
      3762767.86     10106661.06      3762609.83     10106848.67
      3762453.26     10107056.61
#Sta/Elev= 30
  4754.7  265.52  4776.2  264.76  4790.5  263.73  4833.2  259.62  4882.8   256.6
  4897.1  256.06  4917.9  254.31  4932.2  252.22  4938.8  252.23  4953.1  251.05
  4960.8   251.5  4989.4  251.23    4994  250.54  4994.2  250.04  4997.7  250.04
  4998.3  250.68  5004.6  250.68  5010.4  251.21  5031.3   253.3  5053.1  254.45
  5060.4  255.54    5077  257.02  5116.6  260.68  5131.2  261.67  5139.5  262.81
  5174.9  264.26  5181.2  265.03  5224.9  267.78  5245.7  268.68  5260.3  269.97
#Mann= 4 ,-1 , 0
  4754.7     .17       0  4989.4     .09       0  5010.4     .17       0
    5077     .11       0
Bank Sta=4989.4,5010.4
XS Rating Curve= 0 ,0
Exp/Cntr=0.3,0.1

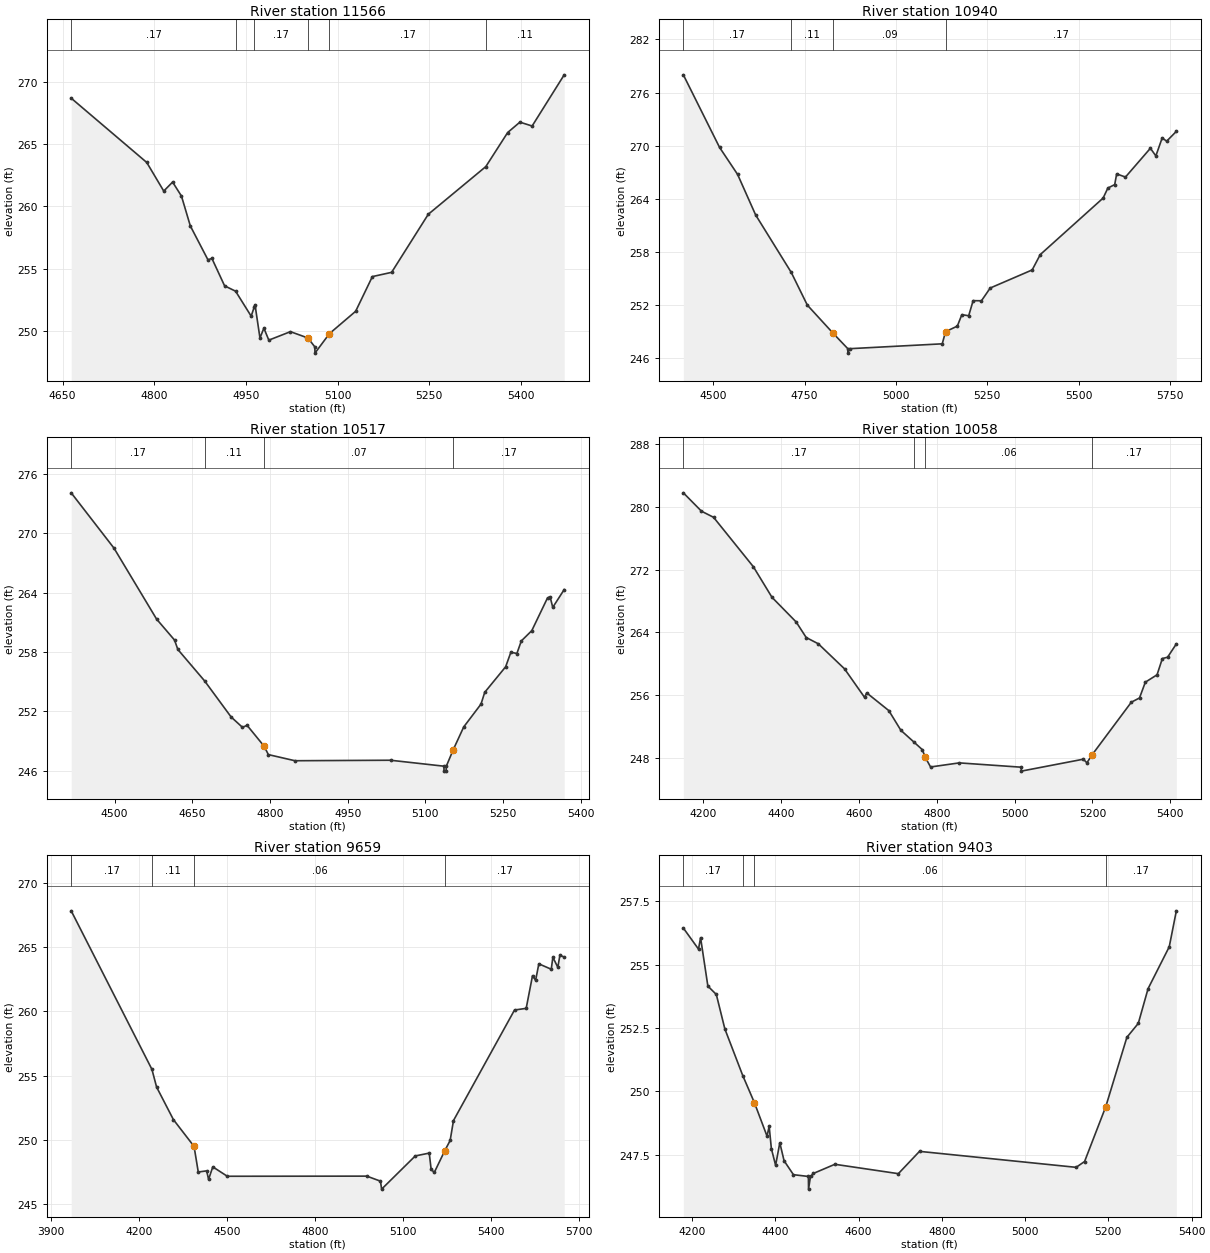
Type RM Length L Ch R = 1 ,11566   ,626,626,626
BEGIN DESCRIPTION:
LAKE CREEK TRIBUTARY NO. 16 20.0
END DESCRIPTION:
XS GIS Cut Line= 4
      3762685.62     10106405.62      3762420.03     10106611.32
      3762313.26     10106738.93      3762318.47     10107043.57
#Sta/Elev= 30
    4664  268.67  4787.7  263.52  4815.5  261.23    4830  261.95  4844.5  260.83
    4859  258.44  4887.9  255.72  4894.3  255.84  4915.1  253.64  4933.1  253.21
  4958.6  251.21  4963.8  251.97  4964.9  252.13    4973  249.46  4979.4  250.25
  4987.5  249.29  5022.9  249.97  5051.6  249.46  5062.8  248.75    5063  248.25
  5086.7  249.81  5129.6   251.6    5157  254.38  5188.5  254.72  5248.5  259.37
  5342.7  263.19  5378.5  265.92  5398.5  266.75  5418.5  266.44    5471  270.54
#Mann= 6 ,-1 , 0
    4664     .17       0  4933.1     .15       0  4963.8     .17       0
  5051.6     .09       0  5086.7     .17       0  5342.7     .11       0
Bank Sta=5051.6,5086.7
XS Rating Curve= 0 ,0
Exp/Cntr=0.3,0.1

Type RM Length L Ch R = 1 ,10940   ,423,423,423
BEGIN DESCRIPTION:
LAKE CREEK TRIBUTARY NO. 16 19.0
END DESCRIPTION:
XS GIS Cut Line= 3
      3762517.88     10105711.05      3762108.98      10106125.2
      3761821.43     10106837.01
#Sta/Elev= 30
    4418  278.01    4517  269.83  4566.5  266.77    4616  262.19  4713.4  255.71
  4757.4  252.02  4828.1  248.84  4868.3   247.1  4868.6   246.6  4872.9   247.1
  5126.8  247.65  5135.8  249.02  5168.1  249.65  5180.4  250.94  5199.2  250.82
  5211.3  252.52  5234.1  252.51  5258.2  253.95    5373  255.99  5395.1  257.72
  5567.2   264.1  5580.2  265.23  5598.9  265.62  5604.3  266.83  5628.4  266.47
  5696.6  269.72  5711.6  268.86  5728.9  270.89  5741.2  270.52  5767.7  271.63
#Mann= 4 ,-1 , 0
    4418     .17       0  4713.4     .11       0  4828.1     .09       0
  5135.8     .17       0
Bank Sta=4828.1,5135.8
XS Rating Curve= 0 ,0
Exp/Cntr=0.3,0.1

Type RM Length L Ch R = 1 ,10517   ,459,459,459
BEGIN DESCRIPTION:
LAKE CREEK TRIBUTARY NO. 16 18.0
END DESCRIPTION:
XS GIS Cut Line= 3
      3762438.24     10105639.97      3761870.26     10105775.81
      3761505.98     10105830.07
#Sta/Elev= 30
    4416  274.08  4498.7  268.49  4580.9  261.33  4615.6  259.21    4622  258.26
  4673.6  255.09  4724.9  251.44  4746.9  250.39  4755.7   250.6  4788.9  248.47
  4796.8  247.64  4848.2  247.02  5032.8  247.07  5135.9  246.47  5136.2  245.97
  5140.2  245.97  5140.6  246.47  5154.1  248.15  5174.3  250.44  5207.6  252.74
  5214.8  253.93  5255.2  256.51  5265.3  257.98  5276.9  257.85  5285.5  259.12
  5305.7  260.16  5336.1  263.47  5341.1  263.57  5346.2  262.51  5368.3  264.31
#Mann= 4 ,-1 , 0
    4416     .17       0  4673.6     .11       0  4788.9     .07       0
  5154.1     .17       0
Bank Sta=4788.9,5154.1
XS Rating Curve= 0 ,0
Exp/Cntr=0.3,0.1

Type RM Length L Ch R = 1 ,10058   ,399,399,399
BEGIN DESCRIPTION:
LAKE CREEK TRIBUTARY NO. 16 17.0
END DESCRIPTION:
XS GIS Cut Line= 3
      3762567.82     10105611.06      3761763.92     10105330.93
      3761417.86     10105561.07
#Sta/Elev= 30
  4148.7  281.77  4195.3  279.43  4226.4  278.65  4328.7  272.35  4376.5  268.46
  4438.6  265.32  4464.4  263.34  4495.5  262.54  4562.9  259.35  4614.5  255.71
  4619.8  256.29  4676.7  254.03  4707.7  251.52  4740.2  250.07  4762.9  249.05
  4769.9  248.12    4784  246.85  4857.8  247.37    5017  246.82  5017.3  246.32
  5176.6  247.84  5185.7  247.38  5199.4  248.42  5299.9   255.1  5320.9  255.64
  5335.9  257.65    5366  258.59  5379.6  260.66  5393.1  260.83  5415.6  262.53
#Mann= 4 ,-1 , 0
  4148.7     .17       0  4740.2     .11       0  4769.9     .06       0
  5199.4     .17       0
Bank Sta=4769.9,5199.4
XS Rating Curve= 0 ,0
Exp/Cntr=0.3,0.1

Type RM Length L Ch R = 1 ,9659    ,256,256,256
BEGIN DESCRIPTION:
LAKE CREEK TRIBUTARY NO. 16 16.0
END DESCRIPTION:
XS GIS Cut Line= 3
      3762217.84     10104211.08      3761564.27     10105009.75
      3761317.83     10105611.11
#Sta/Elev= 30
    3968  267.82  4243.4   255.5  4259.4  254.12  4316.8  251.59  4387.2  249.51
  4401.5  247.52  4430.2  247.61  4436.7  246.95  4451.1  247.92  4500.6  247.19
  4976.5   247.2    5023  246.81  5027.1  246.19  5141.9  248.77  5189.5  248.99
    5196  247.72  5206.8  247.49  5242.8  249.19  5260.8  249.97  5272.2  251.52
  5480.4  260.11  5520.2  260.24  5541.8  262.78  5552.4  262.42  5563.4   263.7
  5605.8  263.28  5611.2  264.21  5628.2  263.43  5635.2  264.36  5649.9  264.23
#Mann= 4 ,-1 , 0
    3968     .17       0  4243.4     .11       0  4387.2     .06       0
  5242.8     .17       0
Bank Sta=4387.2,5242.8
XS Rating Curve= 0 ,0
Exp/Cntr=0.3,0.1

Type RM Length L Ch R = 1 ,9403    ,193,193,193
BEGIN DESCRIPTION:
Mapping XS 73534ae1
END DESCRIPTION:
XS GIS Cut Line= 2
      3761479.92     10104093.14      3761266.73     10105257.89
#Sta/Elev= 30
  4179.2  256.44  4215.6  255.61  4220.6  256.06  4238.1  254.15  4258.4  253.82
  4278.9  252.46  4321.9  250.62  4349.9  249.55  4380.2  248.23  4385.3  248.62
  4390.6  247.74  4400.8  247.08  4410.9  247.97  4421.1  247.26  4443.6  246.71
  4479.5  246.64  4479.9  246.14  4484.6  246.64  4491.7  246.76  4543.1  247.12
  4695.6  246.75  4746.4  247.63  5122.6     247  5142.9  247.23  5193.7  249.39
  5244.5  252.13  5271.9  252.68  5295.4  254.05  5346.2   255.7  5363.3  257.12
#Mann= 4 ,-1 , 0
  4179.2     .17       0  4321.9     .11       0  4349.9     .06       0
  5193.7     .17       0
Bank Sta=4349.9,5193.7
XS Rating Curve= 0 ,0
Exp/Cntr=0.3,0.1

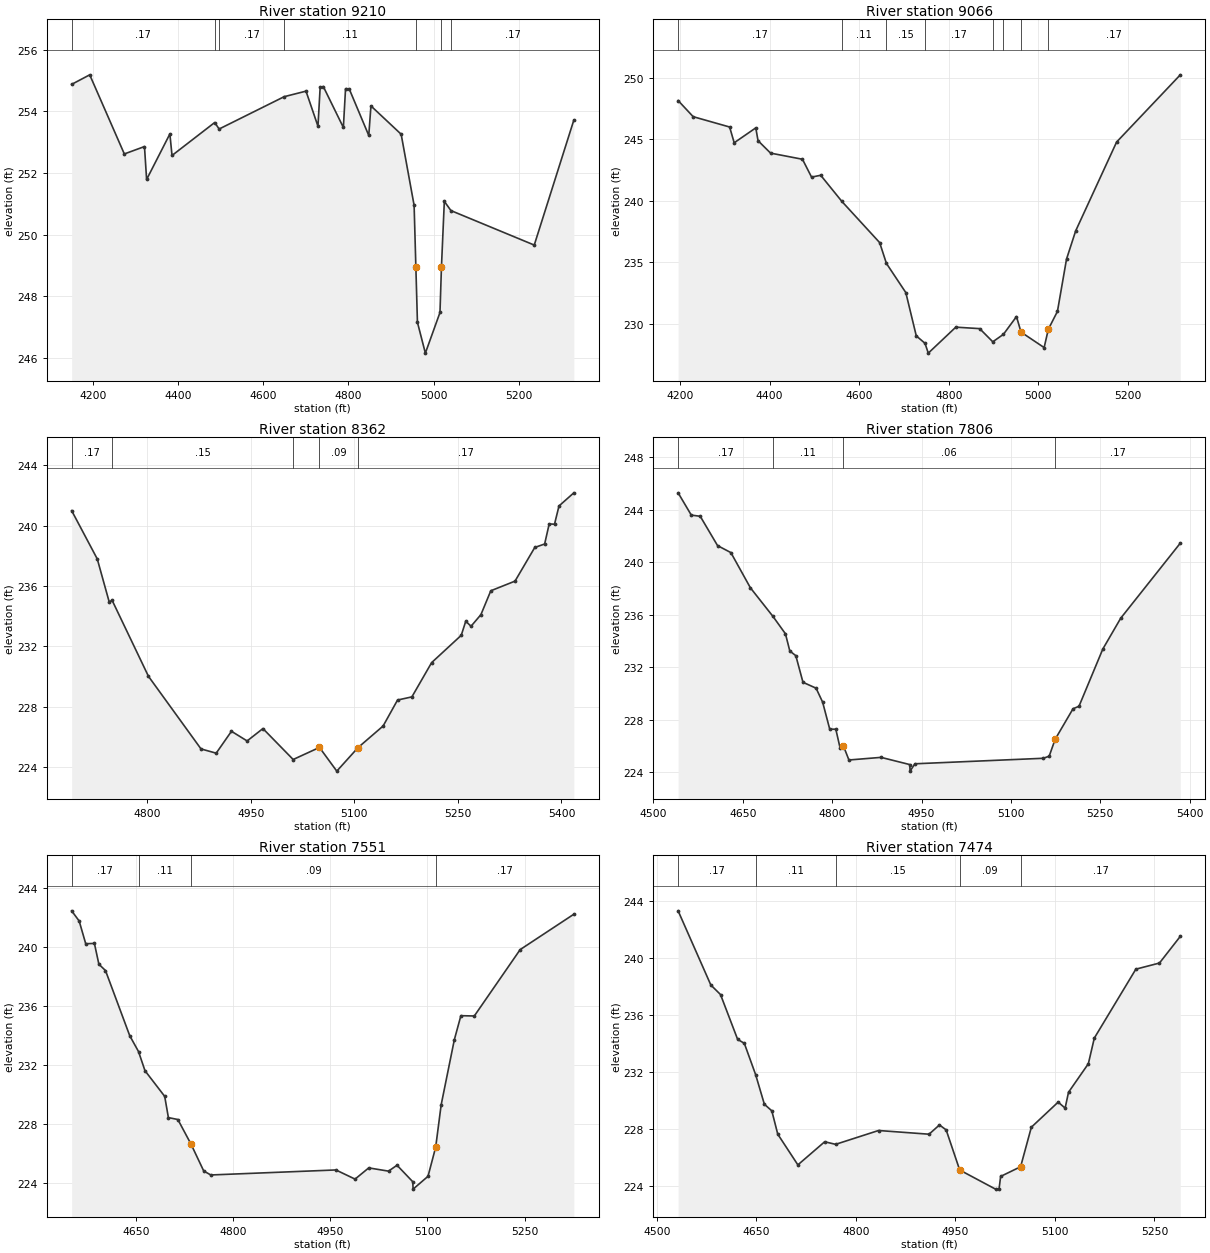
Type RM Length L Ch R = 1 ,9210    ,144,144,144
BEGIN DESCRIPTION:
LAKE CREEK TRIBUTARY NO. 16 15.0
END DESCRIPTION:
XS GIS Cut Line= 3
      3761292.43     10103999.34       3761149.2     10104822.26
      3761185.66     10105163.42
#Sta/Elev= 30
  4150.6  254.88    4193  255.19  4274.2  252.62  4321.5  252.86  4326.5  251.79
  4381.1  253.27  4386.1  252.57  4486.2  253.64  4496.7  253.43  4649.3  254.48
  4700.5  254.66  4728.6  253.52  4733.7  254.78  4741.1  254.81  4788.2  253.48
  4793.3  254.74    4802  254.73  4847.8  253.22  4852.9  254.18  4923.8  253.26
  4954.2  250.95 4958.34248.9332    4962  247.15  4980.6  246.15  5014.9  247.47
  5018.3248.9345  5025.1  251.08  5040.6  250.78  5236.1  249.66    5329  253.72
#Mann= 7 ,-1 , 0
  4150.6     .17       0  4486.2     .11       0  4496.7     .17       0
  4649.3     .11       0 4958.34     .06       0  5018.3     .11       0
  5040.6     .17       0
Bank Sta=4958.34,5018.3
XS Rating Curve= 0 ,0
Exp/Cntr=0.3,0.1

Type RM Length L Ch R = 1 ,9066    ,704,704,704
BEGIN DESCRIPTION:
LAKE CREEK TRIBUTARY NO. 16 14.0
END DESCRIPTION:
XS GIS Cut Line= 3
      3761154.41     10104027.97      3761008.57     10104827.47
      3761063.06     10105131.03
#Sta/Elev= 30
  4195.8  248.15  4229.4  246.84  4310.8     246    4321  244.72  4369.2  245.93
  4374.2  244.89  4402.2  243.88  4473.4  243.38  4493.7  241.93  4514.1  242.08
  4561.5  239.95  4645.7  236.61  4660.8  234.92  4704.1  232.55  4727.5  229.03
  4746.9  228.43  4754.3  227.63  4815.7  229.74    4869  229.62  4898.3  228.55
  4922.1  229.16  4951.2   230.6  4961.3  229.34  5012.9  228.08  5022.3  229.57
  5042.6  231.02  5062.9  235.27  5083.3  237.56  5174.7  244.78  5316.9  250.24
#Mann= 8 ,-1 , 0
  4195.8     .17       0  4561.5     .11       0  4660.8     .15       0
  4746.9     .17       0  4898.3     .11       0  4922.1     .17       0
  4961.3     .09       0  5022.3     .17       0
Bank Sta=4961.3,5022.3
XS Rating Curve= 0 ,0
Exp/Cntr=0.3,0.1

Type RM Length L Ch R = 1 ,8362    ,556,556,556
BEGIN DESCRIPTION:
LAKE CREEK TRIBUTARY NO. 16 13.0
END DESCRIPTION:
XS GIS Cut Line= 3
      3761067.81     10104261.09      3760784.61     10104392.57
      3760467.84     10104661.08
#Sta/Elev= 30
  4690.4     241  4727.5   237.8  4744.8  234.95    4749  235.06  4801.7  230.02
  4877.8  225.21  4899.8  224.93  4921.9  226.38  4944.6  225.74  4967.5  226.56
  5011.3  224.51  5049.4  225.31  5074.5  223.74  5105.3   225.3  5141.6  226.73
  5162.5  228.45  5183.3  228.66  5211.9  230.93  5254.8  232.74  5261.3  233.67
    5269  233.34  5283.3  234.11  5297.6  235.69  5332.7  236.33  5361.3  238.56
  5375.6  238.79  5382.2  240.12  5389.9   240.1  5396.4  241.31  5417.9  242.18
#Mann= 5 ,-1 , 0
  4690.4     .17       0    4749     .15       0  5011.3     .17       0
  5049.4     .09       0  5105.3     .17       0
Bank Sta=5049.4,5105.3
XS Rating Curve= 0 ,0
Exp/Cntr=0.3,0.1

Type RM Length L Ch R = 1 ,7806    ,255,255,255
BEGIN DESCRIPTION:
LAKE CREEK TRIBUTARY NO. 16 12.0
END DESCRIPTION:
XS GIS Cut Line= 3
      3760917.87     10103761.06        3760502.     10103953.88
      3760117.86     10103961.07
#Sta/Elev= 30
  4541.6   245.3  4563.7   243.6  4578.7  243.51  4607.8  241.27  4630.1  240.74
  4662.9  238.05  4700.7  235.87  4721.7  234.54    4729  233.23  4739.1  232.87
  4751.1  230.84  4773.1  230.39  4784.1  229.32    4796  227.26  4806.2  227.26
  4813.3  225.84  4818.9  225.99  4828.2  224.91  4882.1  225.11  4930.3  224.56
  4930.8  224.06  4938.9  224.62  5154.2  225.04  5164.2   225.2  5174.2  226.49
  5204.2  228.82  5214.2  229.01  5254.2  233.38  5284.2  235.73  5384.2  241.46
#Mann= 4 ,-1 , 0
  4541.6     .17       0  4700.7     .11       0  4818.9     .06       0
  5174.2     .17       0
Bank Sta=4818.9,5174.2
XS Rating Curve= 0 ,0
Exp/Cntr=0.3,0.1

Type RM Length L Ch R = 1 ,7551    ,77,77,77
BEGIN DESCRIPTION:
Mapping XS 67686555
END DESCRIPTION:
XS GIS Cut Line= 2
      3760839.27     10103650.39      3760076.25      10103783.2
#Sta/Elev= 30
  4551.2  242.48  4562.8  241.79  4572.9  240.25  4586.3  240.27  4593.2  238.86
  4603.4  238.43  4640.8  234.01  4654.3  232.94  4664.3  231.64  4694.7   229.9
  4700.4  228.46    4715  228.33  4735.3  226.66  4754.9  224.84  4765.8  224.57
  4958.7  224.91  4988.3  224.29  5009.4  225.05  5039.9  224.83    5053  225.23
  5077.3  224.11  5077.8  223.61  5100.8  224.48  5112.6  226.45  5121.1  229.33
  5141.4  233.74  5151.5  235.37  5172.2  235.35  5242.9  239.85  5325.7  242.25
#Mann= 4 ,-1 , 0
  4551.2     .17       0  4654.3     .11       0  4735.3     .09       0
  5112.6     .17       0
Bank Sta=4735.3,5112.6
XS Rating Curve= 0 ,0
Exp/Cntr=0.3,0.1

Type RM Length L Ch R = 1 ,7474    ,69,69,69
BEGIN DESCRIPTION:
Mapping XS 6dbf00b9
END DESCRIPTION:
XS GIS Cut Line= 4
      3760836.69     10103577.47       3760589.3     10103611.32
      3760271.59     10103673.82      3760092.37     10103712.78
#Sta/Elev= 30
  4532.1  243.31  4581.4  238.11    4596  237.44  4621.8   234.3  4631.9  234.02
  4648.9  231.83  4662.1  229.75  4673.3  229.29  4682.3  227.65  4712.6   225.5
    4753  227.12  4769.5  226.94  4834.2  227.91  4910.3  227.65    4926   228.3
  4936.1  227.95  4956.5  225.14  5010.5   223.8  5015.8   223.8  5018.2  224.69
  5048.3  225.37  5064.5  228.14  5104.9   229.9  5115.4  229.48  5120.5  230.59
  5150.4  232.59  5159.4  234.39    5222  239.22  5257.6  239.65    5289  241.52
#Mann= 5 ,-1 , 0
  4532.1     .17       0  4648.9     .11       0  4769.5     .15       0
  4956.5     .09       0  5048.3     .17       0
Bank Sta=4956.5,5048.3
XS Rating Curve= 0 ,0
Exp/Cntr=0.3,0.1

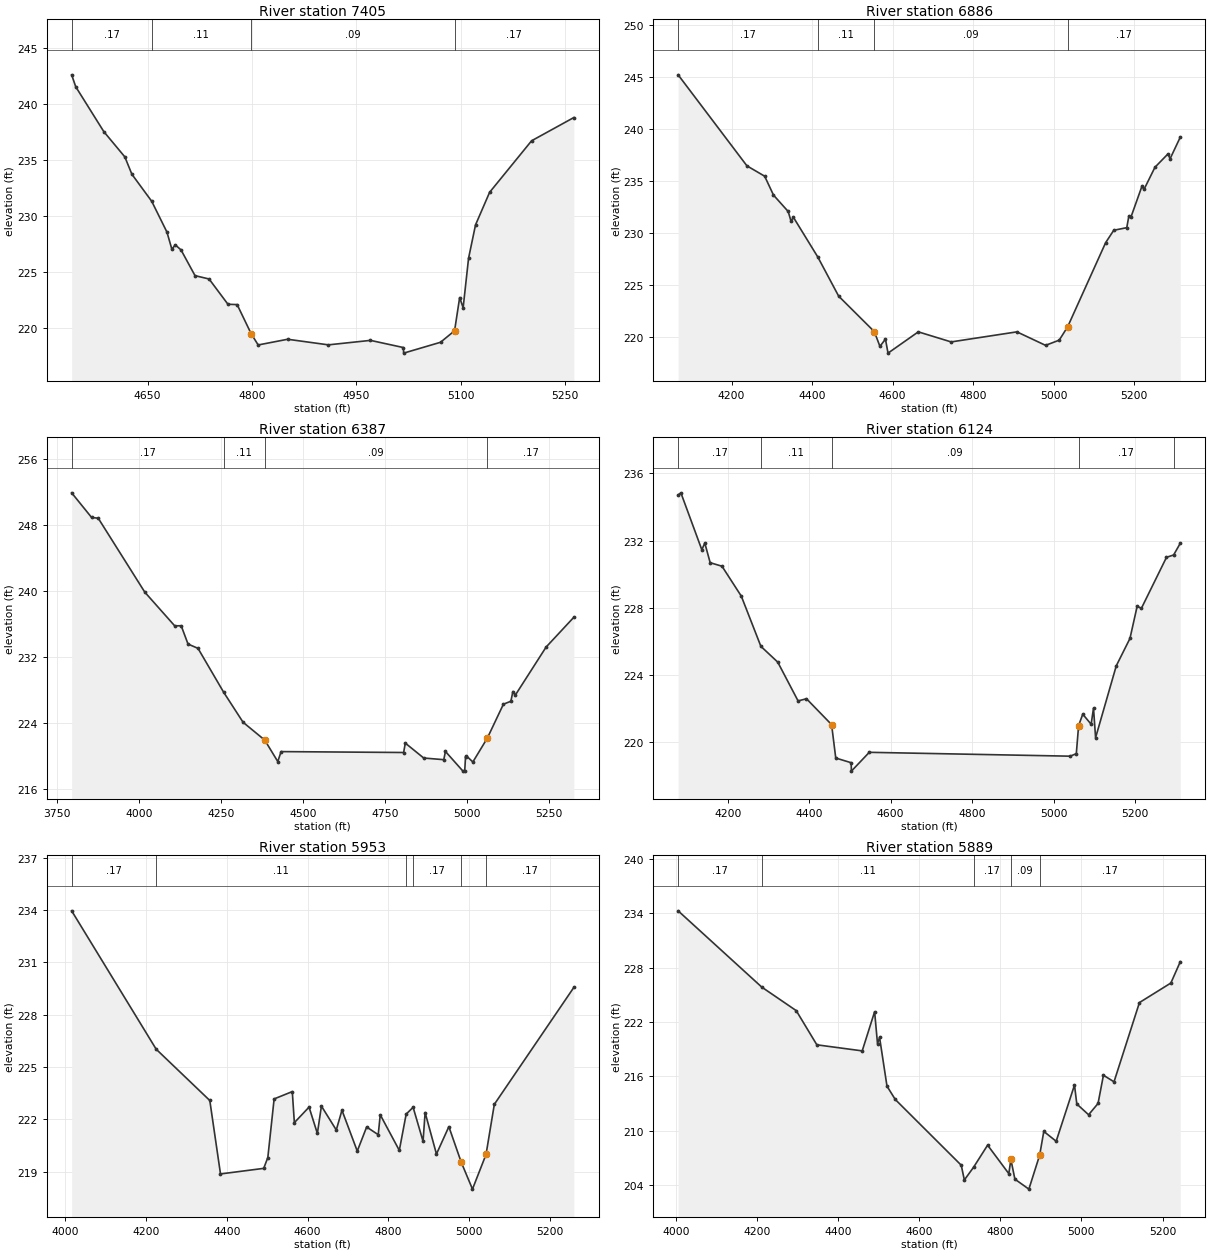
Type RM Length L Ch R = 1 ,7405    ,519,519,519
BEGIN DESCRIPTION:
LAKE CREEK TRIBUTARY NO. 16 11.0
END DESCRIPTION:
XS GIS Cut Line= 3
       3760823.7     10103527.99      3760365.34     10103585.28
      3760107.56     10103613.92
#Sta/Elev= 30
    4541  242.64  4546.9  241.57  4587.2  237.56  4617.4   235.3  4627.5  233.75
    4656  231.33  4677.9  228.57  4684.9  227.05  4689.9  227.43  4698.1  226.98
  4718.2  224.68  4738.4  224.38  4765.5  222.12  4778.7  222.09  4798.8  219.49
  4808.9  218.48  4851.2  218.99  4909.7  218.49  4970.2  218.89  5017.4  218.25
  5017.9  217.75  5070.8  218.72    5091  219.75  5098.3  222.72  5103.3  221.81
  5111.1  226.24  5121.1  229.22  5141.3  232.13  5201.6  236.74  5262.3  238.82
#Mann= 4 ,-1 , 0
    4541     .17       0    4656     .11       0  4798.8     .09       0
    5091     .17       0
Bank Sta=4798.8,5091
XS Rating Curve= 0 ,0
Exp/Cntr=0.3,0.1

Type RM Length L Ch R = 1 ,6886    ,499,499,499
BEGIN DESCRIPTION:
LAKE CREEK TRIBUTARY NO. 16 10.0
END DESCRIPTION:
XS GIS Cut Line= 3
      3760867.89     10102761.05      3760049.13     10103207.78
      3759954.47      10103507.9
#Sta/Elev= 30
  4067.3  245.22  4238.2  236.45  4282.3  235.45  4304.2  233.63  4340.7  232.05
  4347.8  231.11  4353.5   231.5  4414.3  227.66  4466.1  223.89  4554.7  220.47
  4568.6  219.05  4582.3  219.75  4588.7   218.4  4663.9  220.45  4745.5  219.48
  4908.8  220.45    4980  219.15  5013.9  219.65  5034.9  220.94  5129.3  229.05
  5149.4  230.24  5181.7  230.49    5187  231.63  5192.3  231.53  5219.4  234.48
  5224.6  234.18  5251.7  236.31  5284.1   237.6  5289.3  237.13  5314.7  239.22
#Mann= 4 ,-1 , 0
  4067.3     .17       0  4414.3     .11       0  4554.7     .09       0
  5034.9     .17       0
Bank Sta=4554.7,5034.9
XS Rating Curve= 0 ,0
Exp/Cntr=0.3,0.1

Type RM Length L Ch R = 1 ,6387    ,263,263,263
BEGIN DESCRIPTION:
LAKE CREEK TRIBUTARY NO. 16 9.0
END DESCRIPTION:
XS GIS Cut Line= 3
      3760967.82     10102611.08      3759778.44     10102806.94
      3759511.99     10102993.56
#Sta/Elev= 30
  3794.6   251.9  3855.4  248.91  3875.6  248.82  4017.5  239.85  4108.7  235.76
  4128.5  235.77  4149.3  233.55  4179.7  233.03  4257.8  227.71  4317.1  224.06
  4383.3  221.89  4422.9  219.29    4433   220.5  4806.5  220.39  4811.6  221.53
  4867.7  219.72  4928.9  219.52  4933.9  220.52  4987.3  218.13  4992.7  218.13
  4995.1  219.82  4997.8  219.98  5017.5  219.24  5061.8  222.15  5110.6  226.25
  5133.4  226.61  5139.5  227.79  5147.2  227.37  5240.7  233.18  5325.3   236.8
#Mann= 4 ,-1 , 0
  3794.6     .17       0  4257.8     .11       0  4383.3     .09       0
  5061.8     .17       0
Bank Sta=4383.3,5061.8
XS Rating Curve= 0 ,0
Exp/Cntr=0.3,0.1

Type RM Length L Ch R = 1 ,6124    ,171,171,171
BEGIN DESCRIPTION:
Mapping XS 665f262a
END DESCRIPTION:
XS GIS Cut Line= 2
      3760614.44     10102380.43      3759414.86     10102665.13
#Sta/Elev= 30
  4078.3  234.71  4085.1  234.84  4136.5  231.45  4143.8  231.85    4157  230.68
    4186  230.47  4233.4  228.69  4281.5   225.7  4322.9  224.76  4372.8  222.45
  4393.4  222.58  4455.1  221.04  4465.3  219.05  4503.2  218.77  4503.7  218.27
  4547.6  219.39  5040.9  219.16  5055.9  219.31  5061.5  220.98  5071.7  221.66
  5092.3  221.06  5098.1  222.02  5103.2  220.26    5154  224.54  5187.6  226.17
  5205.3  228.09  5215.6  227.96  5277.3     231  5294.8  231.14  5311.2  231.84
#Mann= 5 ,-1 , 0
  4078.3     .17       0  4281.5     .11       0  4455.1     .09       0
  5061.5     .17       0  5294.8     .11       0
Bank Sta=4455.1,5061.5
XS Rating Curve= 0 ,0
Exp/Cntr=0.3,0.1

Type RM Length L Ch R = 1 ,5953    ,64,64,64
BEGIN DESCRIPTION:
Mapping XS b676fc68
END DESCRIPTION:
XS GIS Cut Line= 5
      3760611.01     10102302.29      3760104.06     10102420.35
      3759824.55     10102474.17      3759689.13     10102498.47
      3759395.98     10102566.12
#Sta/Elev= 30
  4015.8  233.95  4225.1  226.02  4357.9  223.08  4384.4  218.87  4491.4  219.19
  4501.6  219.81  4517.2  223.17  4562.2  223.59  4567.3  221.81  4603.7   222.7
  4624.3  221.19  4634.3  222.76  4671.1  221.39  4685.2  222.52  4723.1  220.18
  4746.3  221.56    4775  221.12    4780  222.26  4827.2  220.22  4844.2   222.3
  4861.4  222.69    4886  220.74  4891.1  222.39  4919.2  220.01  4949.9  221.58
  4980.4  219.55  5008.4     218    5042  219.99  5062.5  222.86  5259.4  229.56
#Mann= 6 ,-1 , 0
  4015.8     .17       0  4225.1     .11       0  4844.2     .15       0
  4861.4     .17       0  4980.4     .09       0    5042     .17       0
Bank Sta=4980.4,5042
XS Rating Curve= 0 ,0
Exp/Cntr=0.3,0.1

Type RM Length L Ch R = 1 ,5889    ,385,385,385
BEGIN DESCRIPTION:
LAKE CREEK TRIBUTARY NO. 16 8.0
END DESCRIPTION:
XS GIS Cut Line= 3
      3760604.05      10102264.1      3759626.66     10102449.39
      3759395.76     10102527.98
#Sta/Elev= 30
  4005.2  234.29  4211.5  225.86  4296.5  223.26  4347.4  219.48  4459.3  218.81
  4489.9  223.14    4497  219.61  4502.1   220.3  4520.4  214.91  4540.8  213.44
  4703.6  206.17  4711.2  204.54    4734  205.95  4768.6  208.39  4820.9  205.24
    4826  206.81  4835.9  204.63  4870.4  203.53    4897  207.29  4907.2  209.91
  4937.7  208.82  4982.9  215.03  4988.6  212.94  5017.7  211.75    5041     213
  5054.3  216.12  5080.4  215.39  5143.1  224.15  5220.6  226.31  5243.9  228.67
#Mann= 5 ,-1 , 0
  4005.2     .17       0  4211.5     .11       0    4734     .17       0
    4826     .09       0    4897     .17       0
Bank Sta=4826,4897
XS Rating Curve= 0 ,0
Exp/Cntr=0.3,0.1

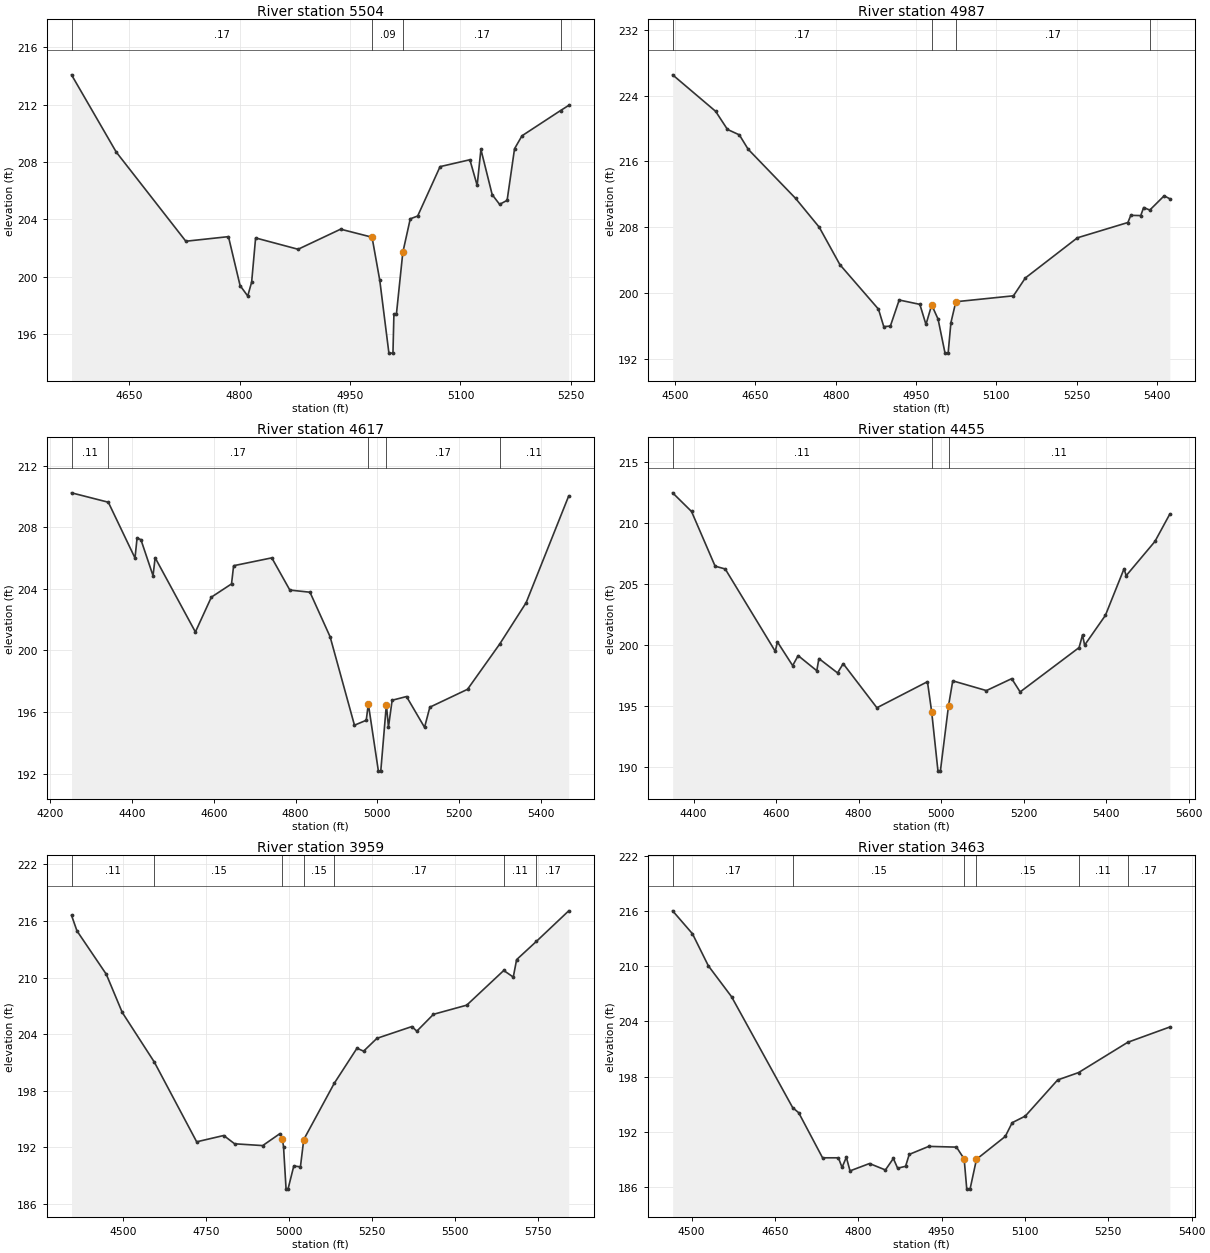
Type RM Length L Ch R = 1 ,5504    ,517,517,517
BEGIN DESCRIPTION:
LAKE CREEK TRIBUTARY NO. 16 7.0
END DESCRIPTION:
XS GIS Cut Line= 3
      3759944.95     10102008.29      3759526.48     10102148.65
      3759295.08     10102184.23
#Sta/Elev= 30
  4571.6  214.07  4632.3  208.69  4726.9  202.47  4784.8  202.79  4800.6  199.38
    4811  198.65  4816.3  199.62  4821.7   202.7  4879.4  201.91  4937.2  203.31
  4979.9  202.75  4990.4  199.74  5002.8  194.67  5008.3  194.67  5009.6  197.39
    5013  197.39  5021.7  201.69  5031.8  204.03  5041.9  204.23  5072.3  207.67
  5112.8  208.15  5122.7  206.36  5127.8  208.87  5143.1  205.72  5153.2  205.04
  5163.4  205.32  5173.5  208.92  5183.6  209.82    5236  211.58  5247.1  211.94
#Mann= 4 ,-1 , 0
  4571.6     .17       0  4979.9     .09       0  5021.7     .17       0
    5236     .11       0
Bank Sta=4979.9,5021.7
XS Rating Curve= 0 ,0
Exp/Cntr=0.3,0.1

Type RM Length L Ch R = 1 ,4987    ,370,370,370
BEGIN DESCRIPTION:
LAKE CREEK TRIBUTARY NO. 16 6.0
END DESCRIPTION:
XS GIS Cut Line= 3
      3759667.87     10101261.04      3759430.45     10101718.96
      3759274.19     10102100.92
#Sta/Elev= 30
  4495.4  226.52  4575.7  222.09  4597.8  219.89    4620  219.23  4636.4  217.49
    4725  211.52  4769.2  208.02  4807.8  203.47  4879.8  198.07  4889.7  195.95
    4902  196.01  4918.5  199.18  4957.1  198.65  4968.5  196.21  4979.2  198.58
  4991.1  196.86  5004.1  192.73  5009.9  192.73  5015.1  196.43  5024.3  198.97
  5131.9  199.69    5154  201.85  5251.2  206.73  5345.6  208.59    5351  209.46
  5369.6  209.43    5375  210.41  5386.5   210.1  5413.3  211.83  5423.9  211.47
#Mann= 4 ,-1 , 0
  4495.4     .17       0  4979.2     .09       0  5024.3     .17       0
  5386.5     .11       0
Bank Sta=4979.2,5024.3
XS Rating Curve= 0 ,0
Exp/Cntr=0.3,0.1

Type RM Length L Ch R = 1 ,4617    ,162,162,162
BEGIN DESCRIPTION:
Mapping XS 84ceddc7
END DESCRIPTION:
XS GIS Cut Line= 2
      3758999.88     10100795.31      3759256.83     10101982.83
#Sta/Elev= 30
  4252.6  210.23  4342.5  209.62  4407.7     206  4412.8   207.3  4422.2  207.19
  4451.8  204.85  4456.9  206.02  4555.3   201.2  4594.3  203.46  4643.6  204.32
  4648.7   205.5    4742  206.01  4786.1  203.92  4835.3  203.78  4884.5  200.89
    4944  195.15  4972.8  195.47  4977.9  196.53  5002.5  192.17  5008.3  192.17
    5022  196.49  5027.1  195.03  5036.1  196.77  5071.2  197.01  5115.3  195.01
  5128.2  196.32  5220.3  197.48    5299  200.42  5363.5   203.1  5467.6  210.03
#Mann= 5 ,-1 , 0
  4252.6     .11       0  4342.5     .17       0  4977.9     .09       0
    5022     .17       0    5299     .11       0
Bank Sta=4977.9,5022
XS Rating Curve= 0 ,0
Exp/Cntr=0.3,0.1

Type RM Length L Ch R = 1 ,4455    ,496,496,496
BEGIN DESCRIPTION:
LAKE CREEK TRIBUTARY NO. 16 5.0
END DESCRIPTION:
XS GIS Cut Line= 3
      3758881.84     10100816.19      3759013.23     10101453.58
      3759124.83     10101996.43
#Sta/Elev= 30
  4349.2  212.49    4395  210.96  4452.2  206.47  4476.7  206.24    4598  199.48
  4603.1  200.26  4640.1  198.31  4653.4  199.13  4698.6  197.89  4703.7  198.89
  4748.9  197.71  4762.6  198.47  4844.3  194.85  4966.8  196.99    4977  194.52
  4992.3  189.65  4998.1  189.65  5017.9  195.02  5028.1  197.06  5109.7  196.26
    5171  197.24  5191.4  196.15  5334.3  199.79  5342.6  200.83  5347.7  199.99
    5398  202.43  5443.3  206.26  5448.4  205.69  5518.1   208.5  5554.2  210.75
#Mann= 3 , 0 , 0
  4349.2     .11       0    4977     .06       0  5017.9     .11       0
Bank Sta=4977,5017.9
XS Rating Curve= 0 ,0
Exp/Cntr=0.3,0.1

Type RM Length L Ch R = 1 ,3959    ,496,496,496
BEGIN DESCRIPTION:
LAKE CREEK TRIBUTARY NO. 16 4.0
END DESCRIPTION:
XS GIS Cut Line= 3
      3758867.84     10100761.09      3758676.23     10101386.71
      3758645.78     10102227.76
#Sta/Elev= 30
  4345.7   216.6  4362.1  214.95  4450.3  210.35  4498.3   206.3    4595  201.02
  4722.2  192.57  4803.6  193.24  4836.4  192.36  4920.9  192.17  4972.7  193.44
 4980.37 192.829  4983.6  192.03  4991.2  187.55    4997  187.55  5014.4     190
  5034.4  189.92  5044.4  192.81    5136  198.77  5204.5   202.5  5224.5  202.19
  5264.5  203.55  5369.7   204.8  5384.6  204.31  5434.6   206.1  5534.7  207.07
  5646.1  210.75  5674.8  210.05  5684.8   211.9  5744.4  213.84  5841.6  217.08
#Mann= 7 ,-1 , 0
  4345.7     .11       0    4595     .15       0 4980.37     .09       0
  5044.4     .15       0    5136     .17       0  5646.1     .11       0
  5744.4     .17       0
Bank Sta=4980.37,5044.4
XS Rating Curve= 0 ,0
Exp/Cntr=0.3,0.1

Type RM Length L Ch R = 1 ,3463    ,520,520,520
BEGIN DESCRIPTION:
LAKE CREEK TRIBUTARY NO. 16 3.0
END DESCRIPTION:
XS GIS Cut Line= 3
      3758767.86     10100711.06      3758360.17     10101055.95
      3758167.84     10101361.09
#Sta/Elev= 30
    4466     216  4501.7  213.51  4530.3  210.03    4572  206.68    4682  194.64
  4692.9  194.08  4735.8  189.19  4764.3  189.19  4770.9  188.15  4778.6  189.25
  4785.2  187.77  4820.3  188.57  4848.9  187.87  4863.2  189.12  4870.9  188.06
  4885.2  188.27  4891.8  189.56  4926.9  190.43  4976.8  190.35  4990.6  189.07
  4995.3  185.79  5001.2  185.79  5012.8  189.03  5064.6  191.51    5077     193
  5100.6  193.72  5158.8  197.64  5196.4  198.44    5285  201.73  5360.7  203.39
#Mann= 6 ,-1 , 0
    4466     .17       0    4682     .15       0  4990.6     .09       0
  5012.8     .15       0  5196.4     .11       0    5285     .17       0
Bank Sta=4990.6,5012.8
XS Rating Curve= 0 ,0
Exp/Cntr=0.3,0.1