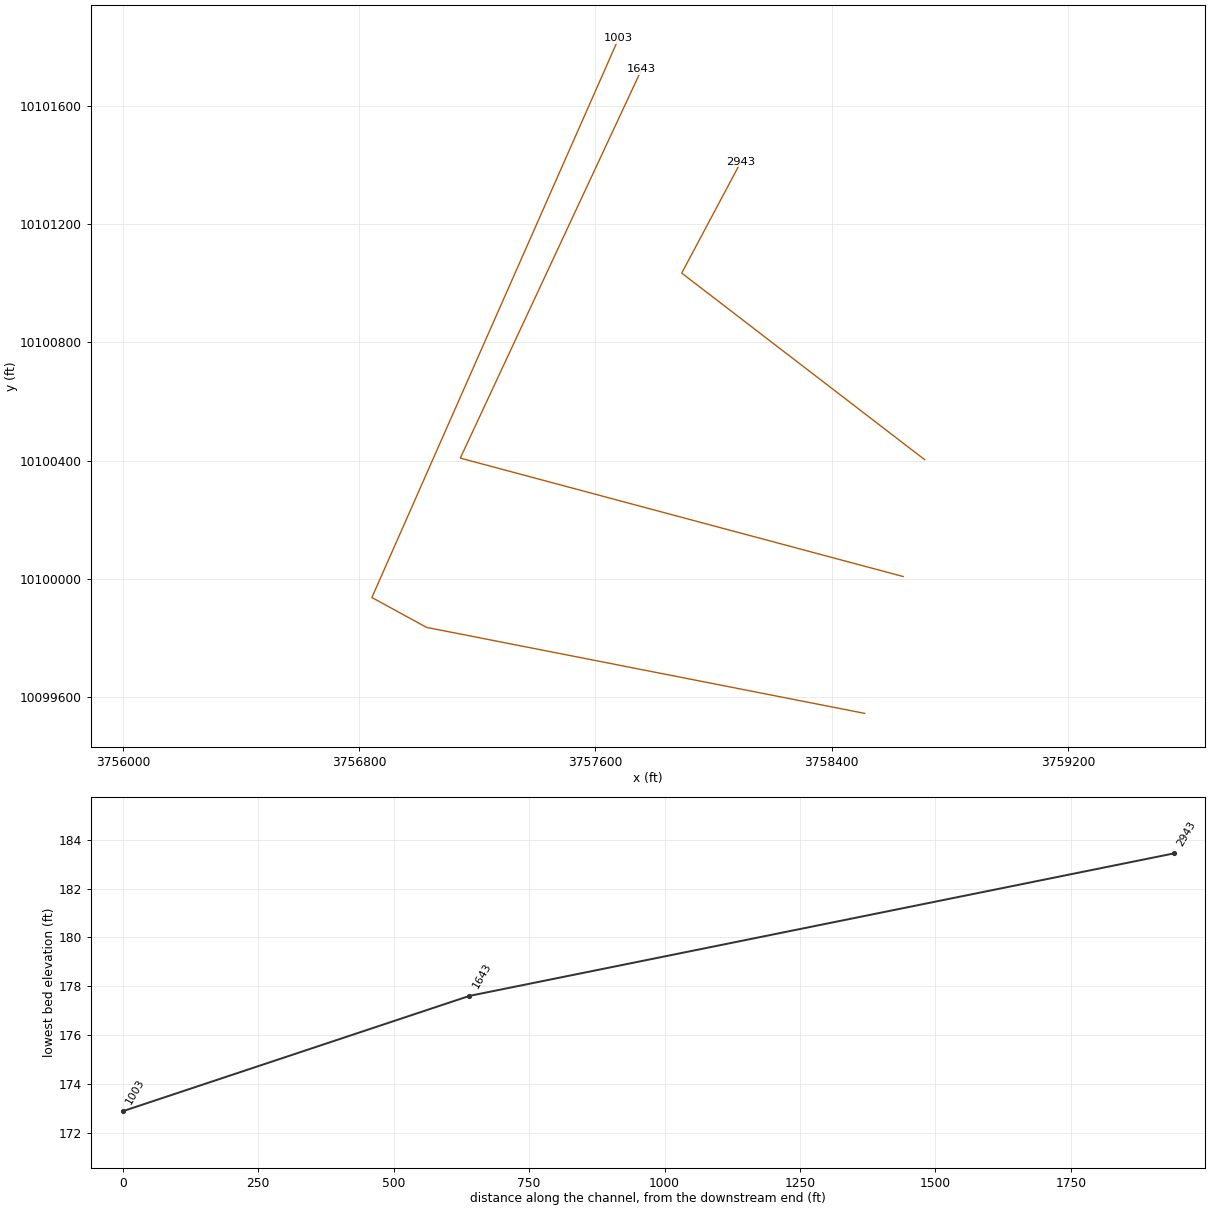
HEC-RAS study LAKE CREEK TRIBUTARY NO 16.prj: LAKE CREEK TRIBUTARY NO 16 Base Level Engineering

--- LAKE CREEK TRIBUTARY NO 16.g01 (geometry) --- (continued)

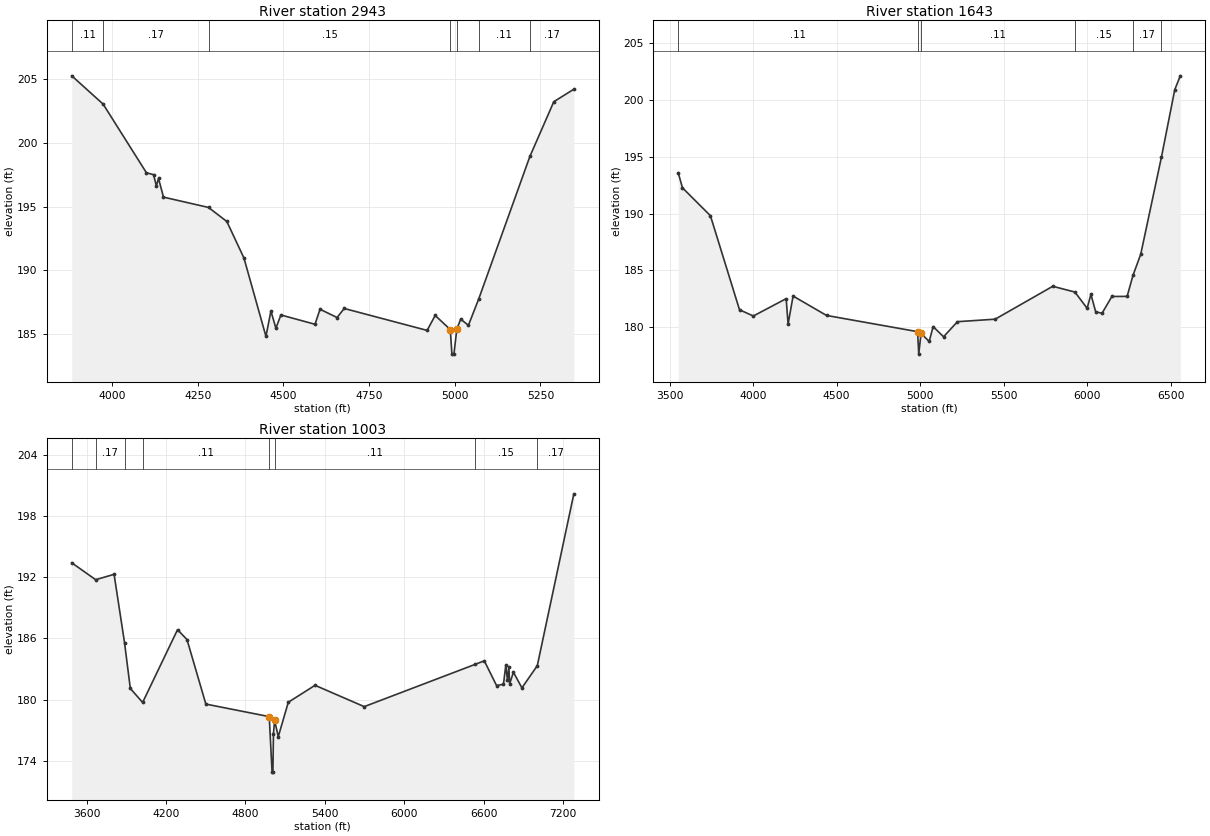
Type RM Length L Ch R = 1 ,2943    ,1300,1300,1300
BEGIN DESCRIPTION:
LAKE CREEK TRIBUTARY NO. 16 2.0
END DESCRIPTION:
XS GIS Cut Line= 3
      3758715.18     10100402.98      3757892.25     10101034.93
      3758093.27      10101412.7
#Sta/Elev= 30
    3882  205.26  3973.6  203.04  4099.9  197.66  4120.7  197.51  4128.9  196.63
  4135.2  197.21  4149.7  195.75  4281.1  194.94  4334.6  193.84  4384.5  190.98
  4448.8  184.83  4463.3  186.82  4477.8  185.47  4492.4  186.51    4592  185.78
  4606.6  186.96  4656.4  186.31  4677.2  187.02  4919.2   185.3  4942.8  186.47
  4986.8  185.37  4991.6  183.44  4997.5  183.44 5005.93185.4006  5017.2  186.18
  5039.8   185.7  5070.3   187.8  5219.2  198.94    5289  203.23  5347.5  204.21
#Mann= 7 ,-1 , 0
    3882     .11       0  3973.6     .17       0  4281.1     .15       0
  4986.8     .09       0 5005.93     .15       0  5070.3     .11       0
  5219.2     .17       0
Bank Sta=4986.8,5005.93
XS Rating Curve= 0 ,0
Exp/Cntr=0.3,0.1

Type RM Length L Ch R = 1 ,1643    ,640,640,640
BEGIN DESCRIPTION:
Mapping XS cf464da9
END DESCRIPTION:
XS GIS Cut Line= 3
      3758642.28     10100007.15      3757142.25      10100408.2
      3757756.84     10101725.91
#Sta/Elev= 30
    3552  193.59  3577.3  192.27  3744.7  189.81  3918.9  181.52  4001.7  180.97
  4198.4   182.5  4209.9  180.25  4239.7  182.73    4440  181.02  4985.3  179.59
  4992.4  177.61  5005.8  179.43  5055.1  178.73  5078.2  180.04    5141  179.14
  5224.1  180.47  5449.9  180.69  5794.9  183.59  5927.6  183.08  6000.6  181.65
  6023.5  182.88  6051.9  181.34  6089.9  181.21  6148.8  182.69  6240.3   182.7
  6275.2  184.55  6321.6  186.41  6445.8  194.98  6525.7  200.93  6558.7  202.14
#Mann= 6 ,-1 , 0
    3552     .11       0  4985.3     .06       0  5005.8     .11       0
  5927.6     .15       0  6275.2     .17       0  6445.8     .11       0
Bank Sta=4985.3,5005.8
XS Rating Curve= 0 ,0
Exp/Cntr=0.3,0.1

Type RM Length L Ch R = 1 ,1003    ,0,0,0
BEGIN DESCRIPTION:
LAKE CREEK TRIBUTARY NO. 16 1.0
END DESCRIPTION:
XS GIS Cut Line= 4
      3758512.01     10099543.62      3757027.82     10099834.91
      3756842.85     10099936.07      3757678.72      10101830.1
#Sta/Elev= 30
  3487.5  193.41  3668.1  191.75  3807.2  192.28  3886.1  185.59  3929.9  181.09
  4022.9  179.72  4286.6  186.85    4358  185.89  4500.6  179.56  4979.6  178.33
    5001  172.89  5007.1  172.89  5011.4  176.66  5020.2  177.98  5047.7  176.36
  5123.6  179.74  5325.6   181.4  5697.2  179.31  6534.8  183.45  6604.5   183.8
  6697.1  181.38  6749.2   181.5  6767.1  183.37  6779.4  181.93  6790.3   183.2
  6795.9  181.55  6824.6  182.68  6888.7  181.15  7004.8  183.32  7281.1  200.17
#Mann= 8 ,-1 , 0
  3487.5     .11       0  3668.1     .17       0  3886.1     .15       0
  4022.9     .11       0  4979.6     .06       0  5020.2     .11       0
  6534.8     .15       0  7004.8     .17       0
Bank Sta=4979.6,5020.2
XS Rating Curve= 0 ,0
Exp/Cntr=0.3,0.1

Chan Stop Cuts=-1
Use User Specified Reach Order=0
Composite Channel Slope=5