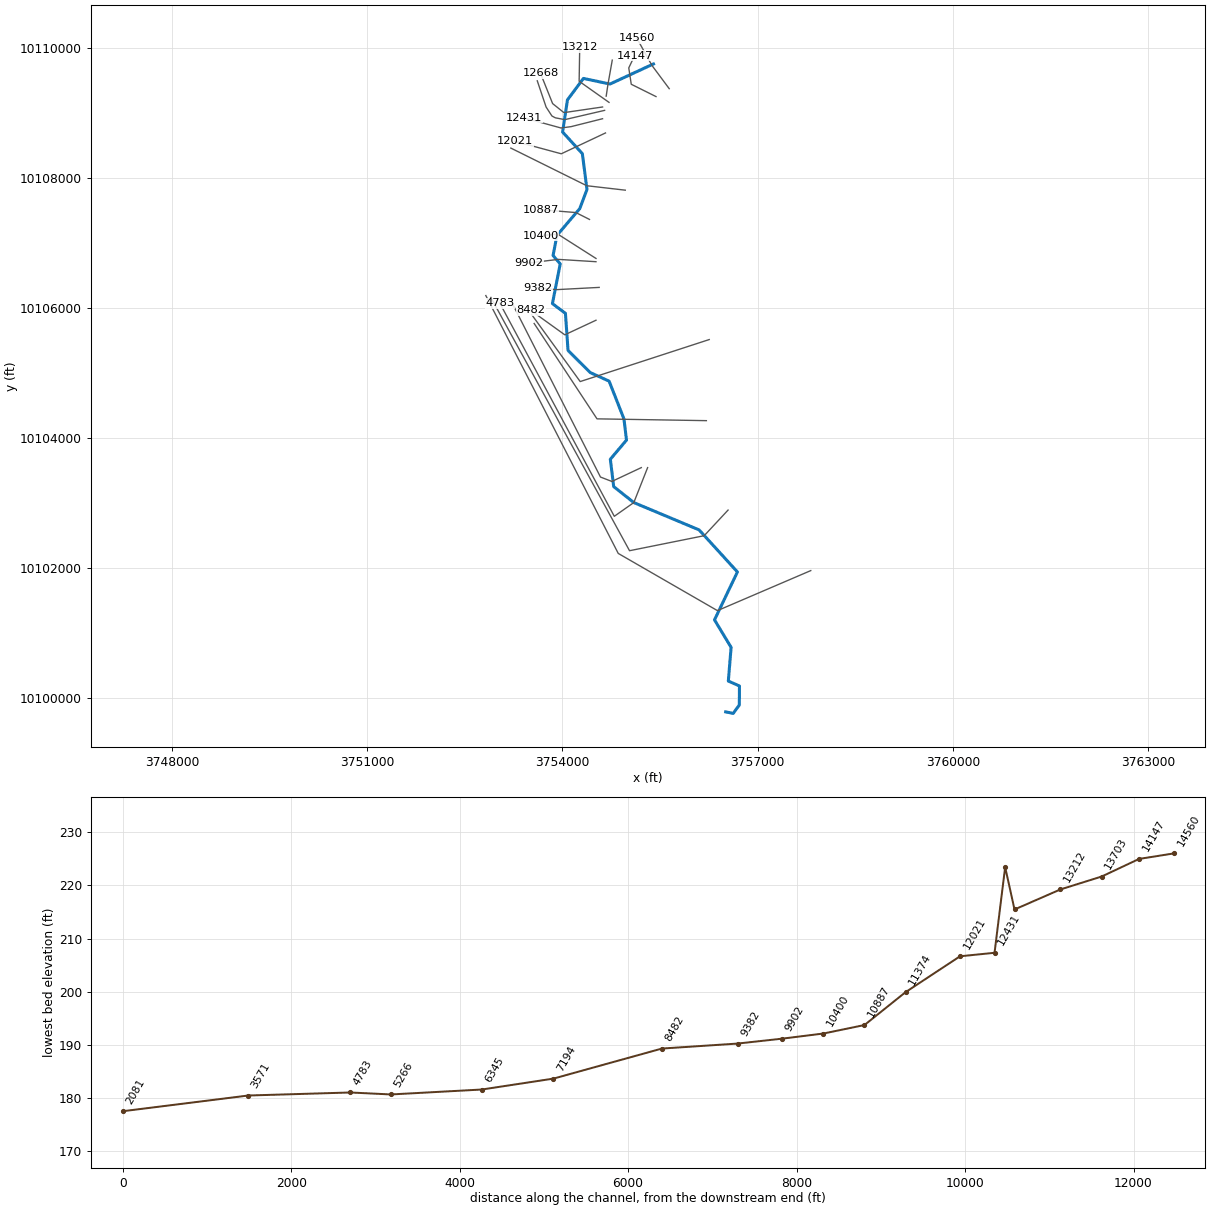
--- LAKE CREEK TRIBUTARY NO 17.prj (project) ---

Proj Title=LAKE CREEK TRIBUTARY NO 17 Base Level Engineering
Current Plan=p01
Default Exp/Contr=0.3,0.1
English Units
Geom File=g01
Flow File=f01
Flow File=f02
Plan File=p01
Y Axis Title=Elevation
X Axis Title(PF)=Main Channel Distance
X Axis Title(XS)=Station
BEGIN DESCRIPTION:
LAKE CREEK TRIBUTARY NO 17
END DESCRIPTION:
DSS Export Rating Curves= 0
DSS Export Rating Curve Sorted= 0
DSS Export Volume Flow Curves= 0
DXF OffsetX= 0
DXF OffsetY= 0
DXF ScaleX= 1
DXF ScaleY= 10

--- LAKE CREEK TRIBUTARY NO 17.p01 (plan) ---

Plan Title=Multiple Run
Short Identifier=Multiple
Geom File=g01
Flow File=f01
Subcritical Flow
K Sum by GR= 0
Std Step Tol= 0.01
Critical Tol= 0.01
Num of Std Step Trials= 20
Max Error Tol= 0.3
Flow Tol Ratio= 0.001
Split Flow NTrial= 30
Split Flow Tol= 0.02
Split Flow Ratio= 0.02
Log Output Level= 0
Friction Slope Method= 1
Unsteady Friction Slope Method= 2
Unsteady Bridges Friction Slope Method= 1
Parabolic Critical Depth
Global Vel Dist=  1 , 1 , 1
Global Log Level= 0
CheckData=True
Encroach Param= -1, 0, 0, 0
BEGIN DESCRIPTION:
Multiple Run
END DESCRIPTION:

--- LAKE CREEK TRIBUTARY NO 17.f01 (steady flow) ---

Flow Title=Multiple
Program Version=4.10
Number of Profiles= 7
Profile Names=10-year,25-year,50-year,1pct_min,100-year,1pct_plu,500-year
River Rch & RM=LAKE CREEK TRIBU,Reach-1         ,14560
     398     523     693     303     914    2760    1641
River Rch & RM=LAKE CREEK TRIBU,Reach-1         ,12557
     748    1018    1380     616    1859    5614    3485
River Rch & RM=LAKE CREEK TRIBU,Reach-1         ,7194
    1102    1526    2093     942    2846    8595    5440
River Rch & RM=LAKE CREEK TRIBU,Reach-1         ,2081
    1269    1771    2441    1104    3333   10065    6433
Boundary for River Rch & Prof#=LAKE CREEK TRIBU,Reach-1         , 1
Up Type= 0
Dn Type= 3
Dn Slope=0.005
Boundary for River Rch & Prof#=LAKE CREEK TRIBU,Reach-1         , 2
Up Type= 0
Dn Type= 3
Dn Slope=0.005
Boundary for River Rch & Prof#=LAKE CREEK TRIBU,Reach-1         , 3
Up Type= 0
Dn Type= 3
Dn Slope=0.005
Boundary for River Rch & Prof#=LAKE CREEK TRIBU,Reach-1         , 4
Up Type= 0
Dn Type= 3
Dn Slope=0.005
Boundary for River Rch & Prof#=LAKE CREEK TRIBU,Reach-1         , 5
Up Type= 0
Dn Type= 3
Dn Slope=0.005
Boundary for River Rch & Prof#=LAKE CREEK TRIBU,Reach-1         , 6
Up Type= 0
Dn Type= 3
Dn Slope=0.005
Boundary for River Rch & Prof#=LAKE CREEK TRIBU,Reach-1         , 7
Up Type= 0
Dn Type= 3
Dn Slope=0.005
DSS Import GetInterval= 0
DSS Import GetPeak= 0
DSS Import FillOption= 0

--- LAKE CREEK TRIBUTARY NO 17.f02 (steady flow) ---

Flow Title=Orig_BLE_Flows
Program Version=4.10
Number of Profiles= 7
Profile Names=10-year,25-year,50-year,1pct_min,100-year,1pct_plu,500-year
River Rch & RM=LAKE CREEK TRIBU,Reach-1         ,14560
     398     513     603     233     703    2123     954
River Rch & RM=LAKE CREEK TRIBU,Reach-1         ,12557
     748     998    1200     473    1430    4318    2026
River Rch & RM=LAKE CREEK TRIBU,Reach-1         ,7194
    1102    1496    1820     725    2189    6610    3163
River Rch & RM=LAKE CREEK TRIBU,Reach-1         ,2081
    1269    1736    2123     849    2564    7744    3740
Boundary for River Rch & Prof#=LAKE CREEK TRIBU,Reach-1         , 1
Up Type= 0
Dn Type= 3
Dn Slope=0.005
Boundary for River Rch & Prof#=LAKE CREEK TRIBU,Reach-1         , 2
Up Type= 0
Dn Type= 3
Dn Slope=0.005
Boundary for River Rch & Prof#=LAKE CREEK TRIBU,Reach-1         , 3
Up Type= 0
Dn Type= 3
Dn Slope=0.005
Boundary for River Rch & Prof#=LAKE CREEK TRIBU,Reach-1         , 4
Up Type= 0
Dn Type= 3
Dn Slope=0.005
Boundary for River Rch & Prof#=LAKE CREEK TRIBU,Reach-1         , 5
Up Type= 0
Dn Type= 3
Dn Slope=0.005
Boundary for River Rch & Prof#=LAKE CREEK TRIBU,Reach-1         , 6
Up Type= 0
Dn Type= 3
Dn Slope=0.005
Boundary for River Rch & Prof#=LAKE CREEK TRIBU,Reach-1         , 7
Up Type= 0
Dn Type= 3
Dn Slope=0.005
DSS Import GetInterval= 0
DSS Import GetPeak= 0
DSS Import FillOption= 0

--- LAKE CREEK TRIBUTARY NO 17.g01 (geometry) ---

Geom Title=Existing Conditions
Program Version=4.10

River Reach=LAKE CREEK TRIBU,Reach-1
Reach XY= 30
      3755401.04     10109752.14      3754732.64     10109443.11
      3754324.91     10109529.35      3754079.69     10109200.57
      3754004.43     10108705.62      3754308.25     10108372.51
       3754379.2     10107821.63      3754268.23     10107526.84
      3753918.23     10107116.84      3753858.23     10106806.84
      3753968.23     10106676.84      3753848.23     10106066.84
      3754048.23     10105916.84      3754088.23     10105346.84
      3754428.23     10105006.84      3754719.51     10104874.22
      3754947.37     10104294.32      3754986.48      10103967.7
      3754738.09     10103673.35      3754789.92     10103252.85
      3755098.94     10103007.39      3756102.27     10102586.89
      3756690.97      10101940.5      3756338.93     10101203.16
      3756594.16      10100780.7      3756551.13     10100262.41
      3756722.27     10100187.11      3756720.31     10099894.72
      3756626.43     10099765.63      3756510.61     10099788.72

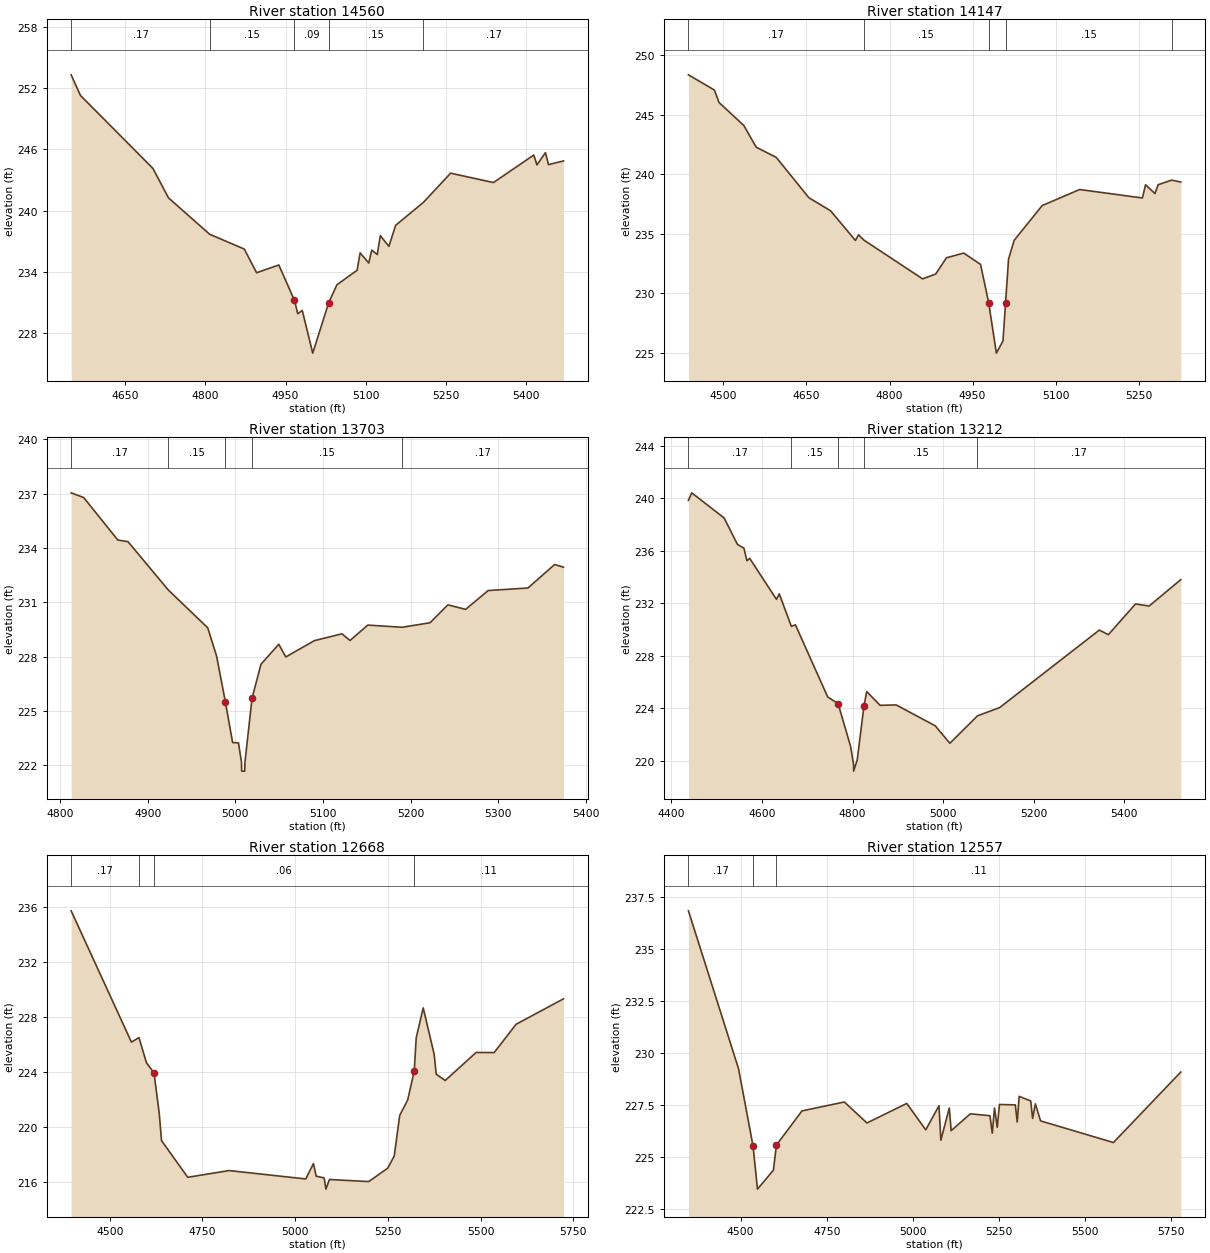
Type RM Length L Ch R = 1 ,14560   ,413,413,413
BEGIN DESCRIPTION:
LAKE CREEK TRIBUTARY NO. 17 21.0
END DESCRIPTION:
XS GIS Cut Line= 3
      3755642.99     10109371.79      3755377.35     10109729.45
      3755146.58     10110145.86
#Sta/Elev= 30
  4548.6   253.3    4566  251.28  4701.6  244.13  4730.8  241.24  4807.9  237.67
  4872.7  236.22  4895.7   233.9  4937.3  234.66  4966.6  231.19  4972.8  229.88
  4981.2   230.2  5000.8  226.02  5030.3   230.9    5046  232.72  5083.8  234.14
  5089.5  235.85  5105.6  234.85  5111.3  236.12  5121.6  235.69  5127.3  237.54
  5143.3  236.48    5156  238.55    5208   240.8  5258.9  243.66  5339.1  242.74
  5414.6  245.44  5420.4  244.47  5436.4  245.67  5442.1   244.5  5470.2  244.86
#Mann= 5 ,-1 , 0
  4548.6     .17       0  4807.9     .15       0  4966.6     .09       0
  5030.3     .15       0    5208     .17       0
Bank Sta=4966.6,5030.3
XS Rating Curve= 0 ,0
Exp/Cntr=0.3,0.1

Type RM Length L Ch R = 1 ,14147   ,444,444,444
BEGIN DESCRIPTION:
Mapping XS e247ed9f
END DESCRIPTION:
XS GIS Cut Line= 4
      3755439.83     10109250.29      3755059.64     10109439.52
      3755021.45     10109691.26      3755111.74     10109880.53
#Sta/Elev= 30
  4436.9  248.37  4483.8  247.09  4492.1  246.05  4536.9  244.11  4559.2  242.29
  4595.5  241.43  4654.4  238.04  4693.6  236.94  4738.4  234.45    4744  234.92
  4753.7  234.48  4859.8  231.22  4883.4  231.63  4902.7  232.99  4933.9  233.39
  4964.3  232.44 4979.05 229.214  4992.9  224.98  5004.8     226  5009.5229.2017
  5014.9  232.88    5025  234.46  5075.6  237.38  5143.2  238.73  5256.6  238.02
  5262.2  239.13  5279.3  238.39  5284.9  239.13  5309.3  239.52  5325.9  239.36
#Mann= 5 ,-1 , 0
  4436.9     .17       0  4753.7     .15       0 4979.05     .09       0
  5009.5     .15       0  5309.3     .17       0
Bank Sta=4979.05,5009.5
XS Rating Curve= 0 ,0
Exp/Cntr=0.3,0.1

Type RM Length L Ch R = 1 ,13703   ,491,491,491
BEGIN DESCRIPTION:
LAKE CREEK TRIBUTARY NO. 17 20.0
END DESCRIPTION:
XS GIS Cut Line= 3
      3754674.37     10109256.93      3754702.26     10109442.24
      3754767.85     10109811.05
#Sta/Elev= 30
  4812.6  237.05  4826.9  236.79  4865.9  234.44  4877.5  234.35  4923.5  231.68
  4968.5  229.59  4978.6  228.03  4988.7  225.48  4996.9  223.25  5003.6  223.23
    5007  222.17  5007.2  221.67  5010.7  221.67    5011  222.17  5019.1   225.7
  5029.3  227.58  5049.6  228.68  5057.6  227.98  5090.2  228.88  5121.7  229.26
  5130.9  228.89  5151.2  229.74  5190.5  229.62  5222.3  229.87  5242.6  230.86
  5262.9  230.61  5288.6  231.65    5334  231.79  5364.5  233.09  5374.6  232.94
#Mann= 5 ,-1 , 0
  4812.6     .17       0  4923.5     .15       0  4988.7     .09       0
  5019.1     .15       0  5190.5     .17       0
Bank Sta=4988.7,5019.1
XS Rating Curve= 0 ,0
Exp/Cntr=0.3,0.1

Type RM Length L Ch R = 1 ,13212   ,544,544,544
BEGIN DESCRIPTION:
LAKE CREEK TRIBUTARY NO. 17 19.0
END DESCRIPTION:
XS GIS Cut Line= 3
      3754717.82      10109161.1      3754258.73     10109485.95
      3754267.85     10110011.07
#Sta/Elev= 30
  4437.6  239.85  4444.9  240.42  4516.3  238.51  4545.9  236.49  4560.1  236.21
  4566.8  235.25  4572.9  235.43    4632  232.31  4638.2  232.73    4665  230.25
  4673.9  230.37  4745.2  224.88  4768.3  224.36  4795.7  221.12  4802.4  219.73
  4802.6  219.23  4810.5   220.1  4825.3  224.18  4831.4  225.29    4861  224.24
  4896.6  224.27  4982.8  222.68  5015.1  221.35  5076.1  223.44  5125.1  224.07
  5345.2  229.97  5365.2  229.62  5425.2  231.96  5455.2   231.8  5525.2  233.81
#Mann= 5 ,-1 , 0
  4437.6     .17       0    4665     .15       0  4768.3     .09       0
  4825.3     .15       0  5076.1     .17       0
Bank Sta=4768.3,4825.3
XS Rating Curve= 0 ,0
Exp/Cntr=0.3,0.1

Type RM Length L Ch R = 1 ,12668   ,111,111,111
BEGIN DESCRIPTION:
LAKE CREEK TRIBUTARY NO. 17 18.0
END DESCRIPTION:
XS GIS Cut Line= 4
      3754618.85     10109090.28      3754025.07     10109003.47
      3753851.45     10109142.35      3753663.95     10109611.12
#Sta/Elev= 30
    4396   235.7  4558.5  226.15  4578.8  226.48  4599.1  224.64  4619.3  223.92
  4633.5  220.96  4639.6  218.99  4710.3  216.32  4821.5  216.81  5028.4   216.2
  5049.2  217.32  5056.6   216.4    5078  216.28  5082.7  215.46  5092.4  216.16
  5198.1  216.01  5249.4  216.98    5267  217.87  5281.7  220.82  5303.2  221.94
  5320.9  224.05  5326.2  226.46  5345.1  228.64  5374.7  225.25  5380.1  223.82
  5404.3  223.36  5487.8   225.4  5536.3  225.39  5595.5  227.45  5723.3   229.3
#Mann= 4 ,-1 , 0
    4396     .17       0  4578.8     .11       0  4619.3     .06       0
  5320.9     .11       0
Bank Sta=4619.3,5320.9
XS Rating Curve= 0 ,0
Exp/Cntr=0.3,0.1

Type RM Length L Ch R = 1 ,12557   ,126,126,126
BEGIN DESCRIPTION:
Mapping XS 80c80c89
END DESCRIPTION:
XS GIS Cut Line= 6
      3754650.09     10109038.19      3754038.95     10108895.83
      3753893.12      10108923.6      3753841.04     10108951.38
      3753750.76     10109090.27      3753615.35     10109493.04
#Sta/Elev= 30
  4348.7  236.82  4494.1  229.23 4536.13225.5272  4549.1  223.44  4595.3  224.35
  4604.1225.5571  4678.2   227.2  4801.3  227.63  4866.9  226.62  4982.4  227.56
  5037.6  226.29    5076  227.45  5081.4  225.79  5105.9  227.34  5111.3  226.25
  5166.9  227.06  5223.9  226.97  5230.7  226.13  5237.1  227.34  5245.1  226.41
  5251.5  227.51  5297.5  227.49  5303.1  226.67  5308.7   227.9  5342.2  227.68
  5347.8  226.84  5355.7  227.54  5370.9  226.72  5582.3  225.68  5777.9  229.07
#Mann= 3 , 0 , 0
  4348.7     .17       0 4536.13     .06       0  4604.1     .11       0
Bank Sta=4536.13,4604.1
XS Rating Curve= 0 ,0
Exp/Cntr=0.3,0.1

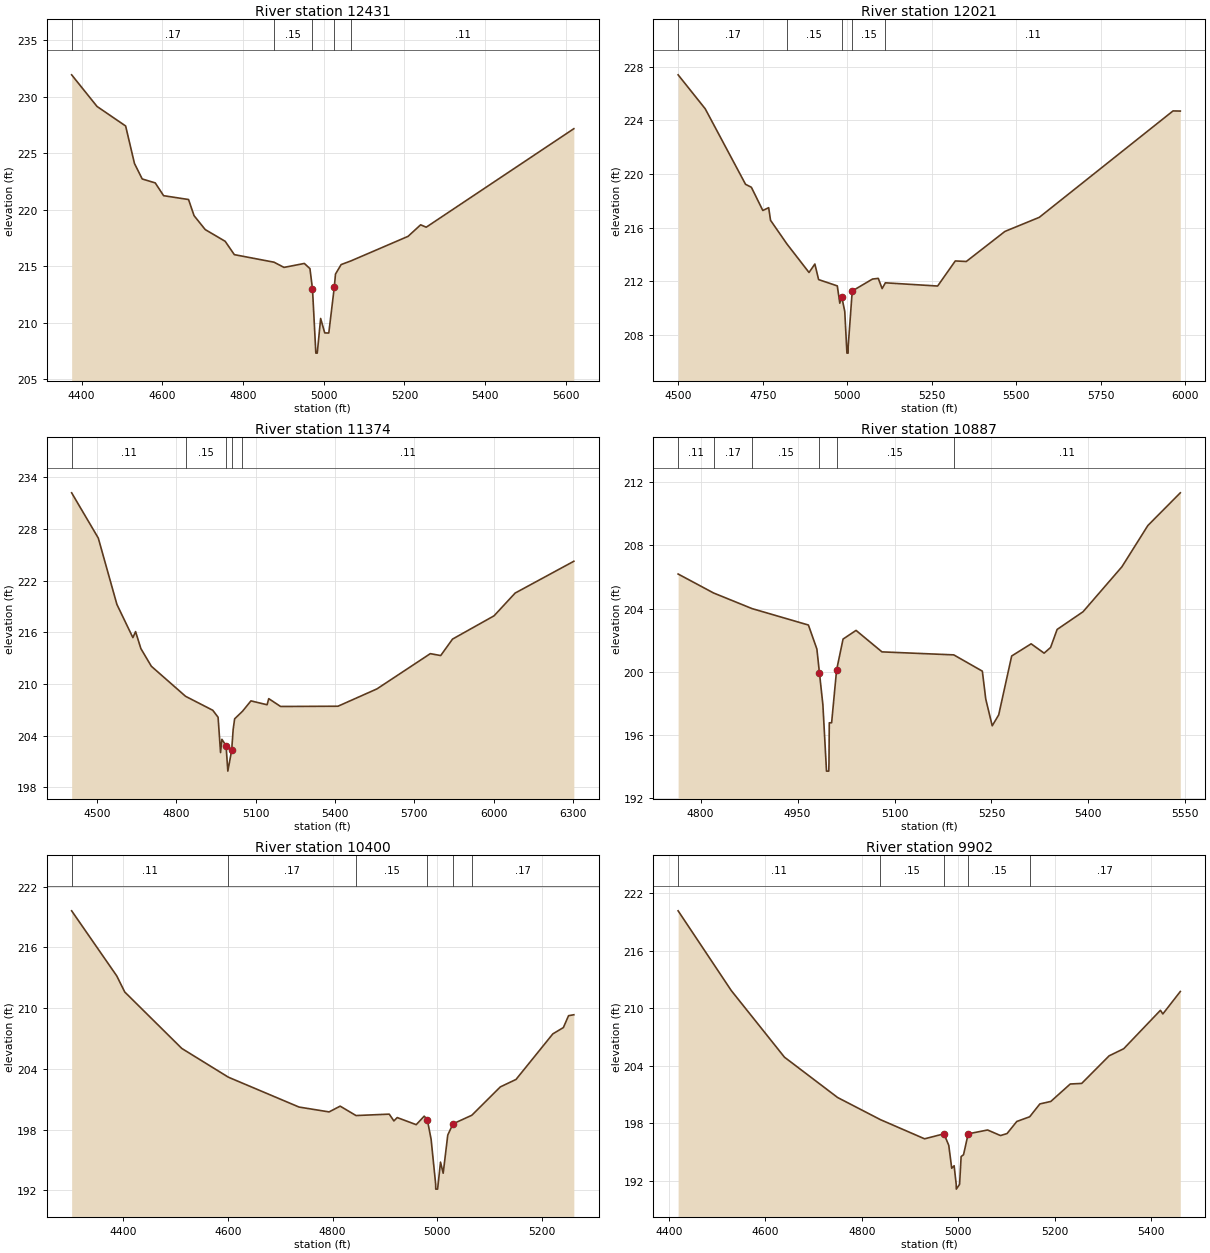
Type RM Length L Ch R = 1 ,12431   ,410,410,410
BEGIN DESCRIPTION:
Mapping XS a4eec251
END DESCRIPTION:
XS GIS Cut Line= 4
      3754618.82     10108909.72      3754136.18     10108788.19
      3753979.93     10108767.35      3753411.67     10108923.28
#Sta/Elev= 30
  4375.3  231.95  4438.2  229.15  4509.1  227.42    4531   224.1  4550.2  222.73
  4582.5  222.38  4603.2  221.25    4665  220.91  4678.7  219.48  4706.3  218.25
  4755.8  217.21  4778.5  216.03  4876.9  215.36  4901.6   214.9    4952  215.25
  4965.9  214.79  4972.2  212.99  4980.5  207.31    4984  207.31  4992.4  210.38
  5002.5   209.1  5012.6  209.09 5026.27213.1557  5029.2  214.31  5043.2  215.15
  5067.8  215.48  5209.1  217.65  5240.2  218.67  5254.1  218.46  5619.9  227.18
#Mann= 5 ,-1 , 0
  4375.3     .17       0  4876.9     .15       0  4972.2     .09       0
 5026.27     .15       0  5067.8     .11       0
Bank Sta=4972.2,5026.27
XS Rating Curve= 0 ,0
Exp/Cntr=0.3,0.1

Type RM Length L Ch R = 1 ,12021   ,647,647,647
BEGIN DESCRIPTION:
LAKE CREEK TRIBUTARY NO. 17 17.0
END DESCRIPTION:
XS GIS Cut Line= 3
      3754663.96     10108690.97      3753984.32     10108370.52
      3753275.04      10108562.5
#Sta/Elev= 30
  4499.2  227.39  4579.4  224.86  4698.8  219.23    4716  219.01  4749.9  217.28
  4767.2  217.49  4772.7  216.55  4821.1  214.79  4886.6  212.66  4903.9  213.29
    4915  212.13  4970.3  211.66  4977.7  210.37  4983.3  210.86  4992.4  209.76
  4998.8  206.65  5002.3  206.65  5002.5  207.15  5014.5  211.28  5074.4  212.17
  5091.6  212.22    5103  211.46  5112.6  211.89  5267.2  211.65  5319.5  213.52
  5352.1  213.48  5466.4  215.72  5568.1  216.77  5963.9   224.7  5985.4  224.69
#Mann= 5 ,-1 , 0
  4499.2     .17       0  4821.1     .15       0  4983.3     .09       0
  5014.5     .15       0  5112.6     .11       0
Bank Sta=4983.3,5014.5
XS Rating Curve= 0 ,0
Exp/Cntr=0.3,0.1

Type RM Length L Ch R = 1 ,11374   ,487,487,487
BEGIN DESCRIPTION:
LAKE CREEK TRIBUTARY NO. 17 16.0
END DESCRIPTION:
XS GIS Cut Line= 3
      3754967.84     10107811.07      3754376.27     10107879.32
      3753209.09     10108458.33
#Sta/Elev= 30
  4404.5  232.18  4505.2  226.93  4575.6  219.23    4636  215.38  4646.1  216.08
  4666.2  214.11  4705.7  212.06  4835.2  208.57    4938  206.95  4958.1  206.14
  4967.4  202.04  4972.4  203.58  4988.3  202.84  4994.9  199.89  5009.4   202.3
  5015.1  204.74  5020.7  205.96  5050.2  206.83  5082.3  208.04  5143.3  207.59
  5149.6   208.3  5194.4  207.39  5411.3  207.42  5558.6  209.43  5760.3  213.52
  5799.6   213.3  5844.4  215.21  6001.3  217.91    6081  220.55  6302.9  224.24
#Mann= 5 ,-1 , 0
  4404.5     .11       0  4835.2     .15       0  4988.3     .09       0
  5009.4     .15       0  5050.2     .11       0
Bank Sta=4988.3,5009.4
XS Rating Curve= 0 ,0
Exp/Cntr=0.3,0.1

Type RM Length L Ch R = 1 ,10887   ,487,487,487
BEGIN DESCRIPTION:
LAKE CREEK TRIBUTARY NO. 17 15.0
END DESCRIPTION:
XS GIS Cut Line= 3
      3754417.86     10107361.07      3754208.23     10107466.84
      3753667.84     10107511.07
#Sta/Elev= 30
  4765.2  206.19    4820  204.99  4879.6     204  4966.8  202.96  4979.9  201.44
 4983.93199.9103  4989.2  197.91  4994.8  193.71  4998.3  193.71  4998.6  194.21
  4999.1  196.77  5002.7  196.77  5010.4  200.11  5020.4  202.07  5040.5  202.62
  5080.6  201.26  5191.7  201.07  5235.9  200.04  5241.2  198.27  5251.2  196.58
  5261.2  197.27  5281.3     201  5311.4  201.77  5331.5  201.18  5341.5  201.54
  5351.6  202.68  5391.7   203.8  5451.9  206.65    5492  209.26  5542.2  211.33
#Mann= 6 ,-1 , 0
  4765.2     .11       0    4820     .17       0  4879.6     .15       0
 4983.93     .09       0  5010.4     .15       0  5191.7     .11       0
Bank Sta=4983.93,5010.4
XS Rating Curve= 0 ,0
Exp/Cntr=0.3,0.1

Type RM Length L Ch R = 1 ,10400   ,498,498,498
BEGIN DESCRIPTION:
LAKE CREEK TRIBUTARY NO. 17 14.0
END DESCRIPTION:
XS GIS Cut Line= 3
      3754517.86     10106761.06      3753928.23     10107136.84
       3753667.8     10107111.07
#Sta/Elev= 30
  4300.8  219.61  4387.1  213.18  4402.4  211.59  4511.6  206.01  4600.7  203.17
  4735.9  200.22  4793.4  199.74  4814.6  200.31  4844.9  199.38  4908.5  199.52
  4917.4  198.85  4923.8  199.18  4960.1  198.48  4975.4  199.32  4981.3  198.98
  4988.6  197.04  4997.3  192.61  4997.5  192.11    5001  192.11  5006.6  194.78
  5011.7  193.68  5020.5  197.46  5030.5  198.56  5066.5  199.41    5121  202.21
  5151.1  202.95  5221.5  207.45  5241.6  208.07  5251.6  209.25  5261.7  209.34
#Mann= 6 ,-1 , 0
  4300.8     .11       0  4600.7     .17       0  4844.9     .15       0
  4981.3     .09       0  5030.5     .15       0  5066.5     .17       0
Bank Sta=4981.3,5030.5
XS Rating Curve= 0 ,0
Exp/Cntr=0.3,0.1

Type RM Length L Ch R = 1 ,9902    ,520,520,520
BEGIN DESCRIPTION:
LAKE CREEK TRIBUTARY NO. 17 13.0
END DESCRIPTION:
XS GIS Cut Line= 3
      3754517.83     10106711.07      3753938.23     10106746.84
      3753481.41     10106691.15
#Sta/Elev= 30
  4419.3  220.17  4529.5  211.85  4639.7   204.9  4749.9  200.69  4838.6  198.38
  4930.2  196.38  4970.3   196.9  4980.3   195.7  4986.4  193.31  4991.4  193.57
  4995.7  191.63  4995.9  191.13  5002.7  191.63  5005.9  194.53  5010.9  194.72
  5020.5   196.9  5060.8   197.3  5087.5  196.72  5101.1  196.93  5121.3  198.19
    5148  198.68  5169.1  200.02  5191.8  200.28  5232.1   202.1  5255.8  202.16
  5312.7  205.04  5342.9  205.78    5419  209.79    5424  209.41  5460.2  211.75
#Mann= 5 ,-1 , 0
  4419.3     .11       0  4838.6     .15       0  4970.3     .09       0
  5020.5     .15       0    5148     .17       0
Bank Sta=4970.3,5020.5
XS Rating Curve= 0 ,0
Exp/Cntr=0.3,0.1

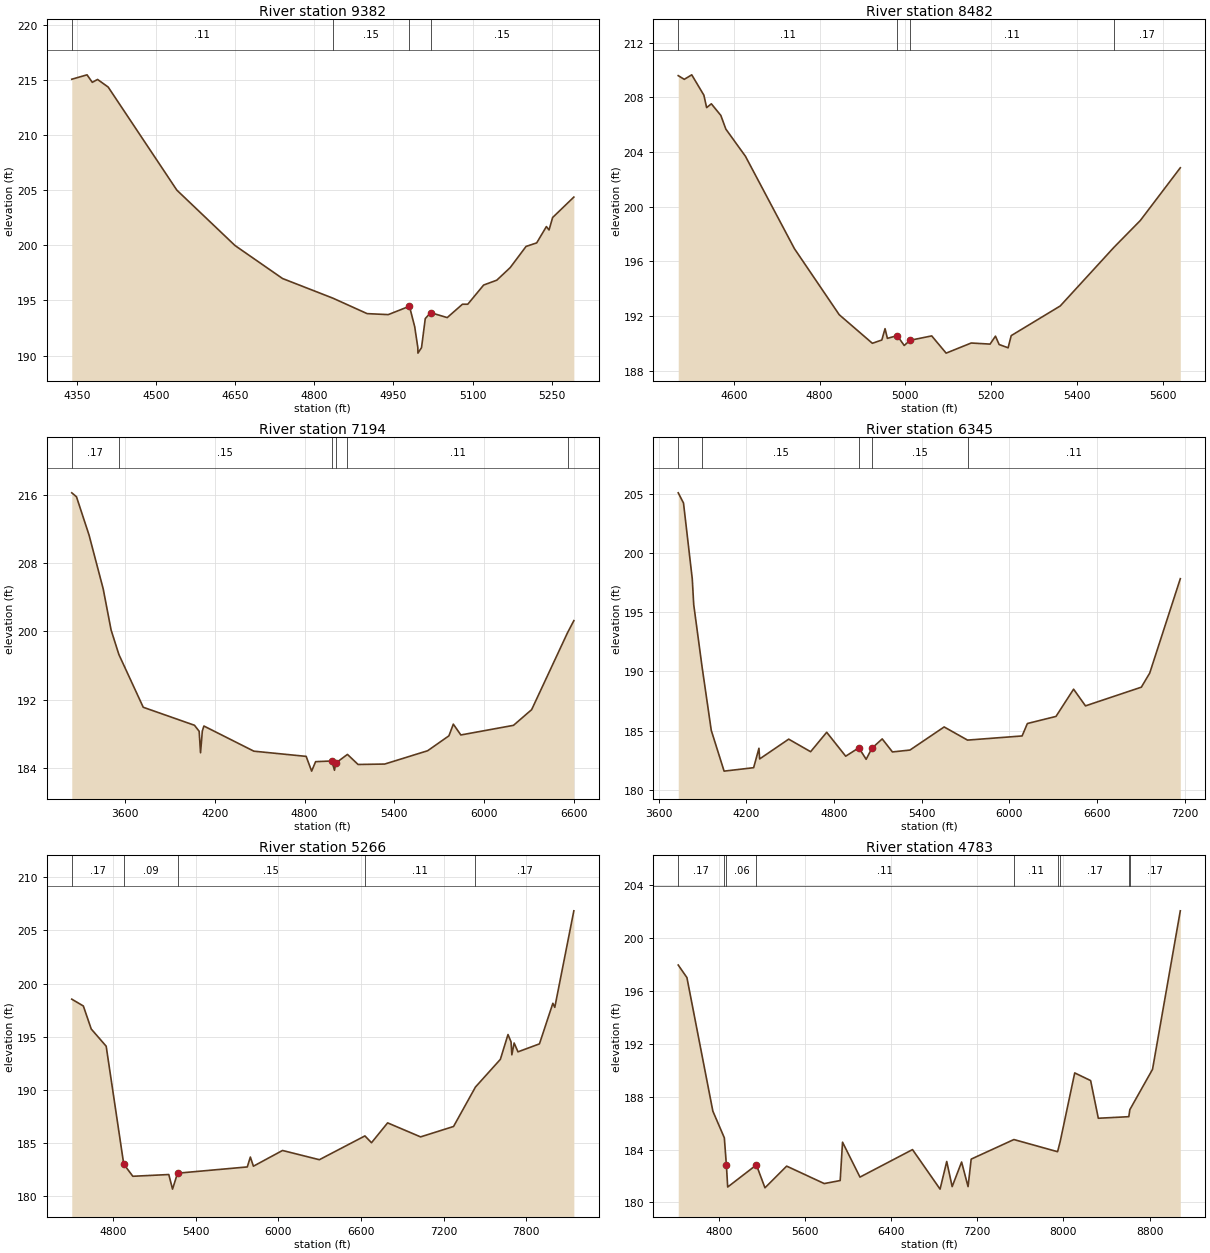
Type RM Length L Ch R = 1 ,9382    ,900,900,900
BEGIN DESCRIPTION:
LAKE CREEK TRIBUTARY NO. 17 12.0
END DESCRIPTION:
XS GIS Cut Line= 3
      3754566.72     10106315.97      3753907.01     10106281.24
      3753617.87     10106311.07
#Sta/Elev= 30
  4340.6  215.04  4369.5  215.44  4379.5  214.76  4389.5  215.02  4409.6  214.33
  4539.7  204.99  4649.9  199.97    4740  196.98  4835.4   195.2  4900.2   193.8
  4940.3  193.71  4980.4  194.47  4990.4  192.61  4996.3  190.72  4996.5  190.22
  5003.3  190.72  5010.4  193.35  5020.5  193.89    5052  193.44  5080.8  194.65
  5090.9  194.65    5121  196.39  5145.9  196.83  5171.3  197.97  5201.4  199.89
  5221.5  200.21  5239.9  201.69  5244.9  201.38  5251.7  202.51  5291.9  204.36
#Mann= 4 ,-1 , 0
  4340.6     .11       0  4835.4     .15       0  4980.4     .09       0
  5020.5     .15       0
Bank Sta=4980.4,5020.5
XS Rating Curve= 0 ,0
Exp/Cntr=0.3,0.1

Type RM Length L Ch R = 1 ,8482    ,1288,1288,1288
BEGIN DESCRIPTION:
LAKE CREEK TRIBUTARY NO. 17 11.0
END DESCRIPTION:
XS GIS Cut Line= 3
      3754517.81     10105811.05      3754038.23     10105586.84
      3753517.83     10105961.09
#Sta/Elev= 30
  4470.6  209.58  4484.7  209.31  4502.1  209.64  4530.4  208.15  4536.8  207.24
  4547.8  207.52  4569.9  206.67  4581.6  205.67  4627.3  203.68  4741.5  196.92
  4845.9  192.09  4923.1     190  4945.2  190.24  4952.7  191.07  4958.2  190.36
    4981  190.56  4997.4  189.84  5011.2  190.22  5061.5  190.54  5095.1  189.28
  5153.6  190.02  5197.5  189.94  5210.1  190.52  5218.7  189.91  5239.6  189.67
  5246.8  190.56  5361.1  192.73  5486.3  197.02  5547.7  198.98    5641  202.84
#Mann= 4 ,-1 , 0
  4470.6     .11       0    4981     .06       0  5011.2     .11       0
  5486.3     .17       0
Bank Sta=4981,5011.2
XS Rating Curve= 0 ,0
Exp/Cntr=0.3,0.1

Type RM Length L Ch R = 1 ,7194    ,849,849,849
BEGIN DESCRIPTION:
Mapping XS 2eed1c25
END DESCRIPTION:
XS GIS Cut Line= 3
      3756257.69     10105513.88      3754275.07     10104868.05
      3753529.69     10105897.71
#Sta/Elev= 30
  3244.2  216.26  3275.6   215.8  3359.7  211.31  3454.4  204.99    3507  200.18
  3558.9  197.31    3722  191.11  4064.4     189  4095.9  188.29    4105  185.77
    4117  188.33  4127.5  188.91  4461.4  185.96  4811.1  185.35  4847.6  183.62
  4874.2  184.73  4982.6  184.81  5000.4  183.72  5009.3  184.57  5087.1  185.58
  5158.2   184.4  5336.2  184.45  5623.1  186.01  5765.4  187.76  5794.8  189.13
  5845.1  187.86    6197  188.99  6318.4  190.83  6558.5  199.86  6600.5  201.27
#Mann= 6 ,-1 , 0
  3244.2     .17       0  3558.9     .15       0  4982.6     .09       0
  5009.3     .15       0  5087.1     .11       0  6558.5     .17       0
Bank Sta=4982.6,5009.3
XS Rating Curve= 0 ,0
Exp/Cntr=0.3,0.1

Type RM Length L Ch R = 1 ,6345    ,1079,1079,1079
BEGIN DESCRIPTION:
LAKE CREEK TRIBUTARY NO. 17 10.0
END DESCRIPTION:
XS GIS Cut Line= 3
      3756213.87     10104266.92      3754533.31      10104294.7
      3753567.83     10105761.11
#Sta/Elev= 30
  3734.7  205.07  3770.7  204.21  3830.7  197.81  3840.7  195.63  3897.8  190.38
  3960.8  185.01  4048.6  181.57  4250.8  181.86  4287.1   183.5  4292.1   182.6
  4490.8  184.27  4640.8  183.21  4750.9  184.85  4880.9  182.83  4970.9  183.54
  5020.9  182.57  5060.9  183.51  5130.9  184.29  5200.9  183.19  5320.9  183.35
  5554.8   185.3  5714.9  184.19  6088.4  184.54  6124.5  185.59  6320.3  186.19
  6440.8  188.49  6522.1  187.08  6904.6  188.66  6961.8  189.85  7171.2  197.82
#Mann= 5 ,-1 , 0
  3734.7     .17       0  3897.8     .15       0  4970.9     .09       0
  5060.9     .15       0  5714.9     .11       0
Bank Sta=4970.9,5060.9
XS Rating Curve= 0 ,0
Exp/Cntr=0.3,0.1

Type RM Length L Ch R = 1 ,5266    ,483,483,483
BEGIN DESCRIPTION:
LAKE CREEK TRIBUTARY NO. 17 9.0
END DESCRIPTION:
XS GIS Cut Line= 4
      3755213.87      10103544.7      3754761.56     10103332.06
      3754586.57     10103399.89      3753249.03     10106036.89
#Sta/Elev= 30
  4500.2  198.53  4584.2  197.89  4641.5  195.72    4750   194.1 4877.36     183
  4943.4  181.85 5204.51 182.014  5231.7  180.64  5267.7  182.14  5774.2  182.73
  5796.4  183.66  5818.7   182.8    6030  184.28  6297.3  183.41    6628  185.65
  6675.9  185.01  6792.8  186.88  7032.1  185.56  7271.4  186.54  7430.1  190.25
    7611  192.86  7666.6   195.2  7688.9   194.5  7694.5  193.29  7711.2   194.4
    7739  193.57  7894.9  194.32  7992.2  198.14  8006.2  197.76  8144.5  206.85
#Mann= 5 ,-1 , 0
  4500.2     .17       0 4877.36     .09       0  5267.7     .15       0
    6628     .11       0  7430.1     .17       0
Bank Sta=4877.36,5267.7
XS Rating Curve= 0 ,0
Exp/Cntr=0.3,0.1

Type RM Length L Ch R = 1 ,4783    ,1212,1212,1212
BEGIN DESCRIPTION:
LAKE CREEK TRIBUTARY NO. 17 8.0
END DESCRIPTION:
XS GIS Cut Line= 4
       3755311.1     10103544.72      3755098.94     10103007.39
      3754799.09     10102796.05      3753040.26     10106072.47
#Sta/Elev= 30
  4422.3  197.96    4503  197.01  4743.8  186.91  4850.5  184.89 4869.27  182.85
  4881.8  181.17  5148.1  182.84  5227.8  181.11  5429.3  182.75  5778.6  181.43
  5926.4  181.66  5948.3  184.56  6110.3  181.92  6598.3     184  6854.2  181.01
  6916.1   183.1  6966.5   181.2  7054.1  183.06  7114.2   181.2  7143.1  183.28
  7539.8  184.76  7945.6  183.84  7969.8  184.61  8104.8   189.8  8252.6  189.22
    8324  186.37  8607.1  186.49  8616.7  187.02  8827.4  190.07  9085.5  202.06
#Mann= 9 ,-1 , 0
  4422.3     .17       0  4850.5     .11       0 4869.27     .06       0
  5148.1     .11       0  7539.8     .11       0  7945.6     .15       0
  7969.8     .17       0  8607.1     .15       0  8616.7     .17       0
Bank Sta=4869.27,5148.1
XS Rating Curve= 0 ,0
Exp/Cntr=0.3,0.1

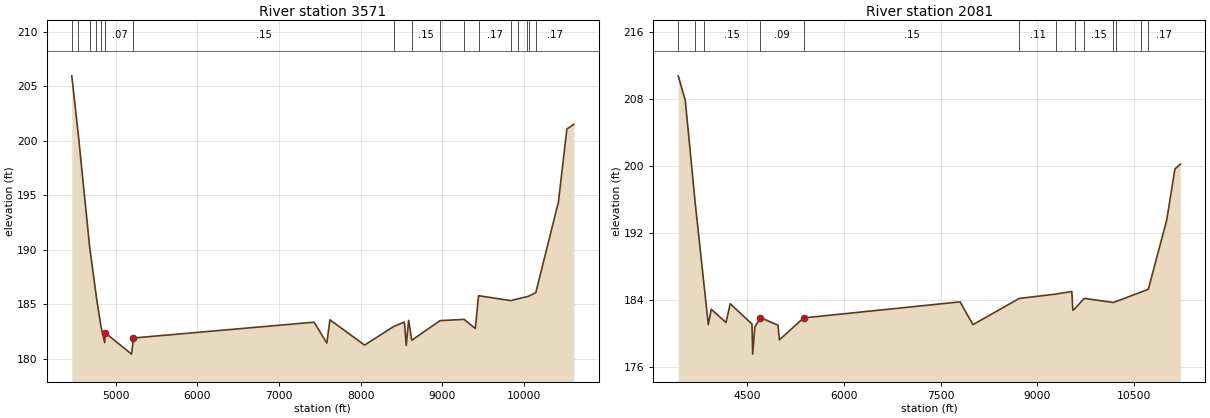
Type RM Length L Ch R = 1 ,3571    ,1490,1490,1490
BEGIN DESCRIPTION:
LAKE CREEK TRIBUTARY NO. 17 6.0
END DESCRIPTION:
XS GIS Cut Line= 4
      3756547.23     10102891.96      3756180.51      10102497.9
      3755033.31     10102266.92      3752902.11      10106161.4
#Sta/Elev= 30
  4461.7  205.97  4540.6  200.67  4679.9  190.33  4764.2  185.61  4819.3  182.97
  4865.2   181.5  4872.5  182.39    5194  180.44    5217  181.92  7428.9  183.37
  7585.2  181.46  7622.7  183.59  8048.1  181.27  8404.4  182.98  8534.6  183.38
  8557.4  181.24  8586.7  183.54  8624.8  181.71  8970.9  183.51  9265.1  183.63
  9403.3  182.79  9442.7   185.8  9837.2  185.35  9924.1  185.51 10033.8  185.71
 10058.2  185.76 10143.6  186.08   10421   194.4 10524.3   201.1 10609.7  201.51
#Mann= 18 ,-1 , 0
  4461.7     .17       0  4540.6     .11       0  4679.9     .15       0
  4764.2     .11       0  4819.3     .15       0  4865.2     .11       0
  4872.5     .07       0    5217     .15       0  8404.4     .11       0
  8624.8     .15       0  8970.9     .11       0  9265.1     .15       0
  9442.7     .17       0  9837.2     .11       0  9924.1     .15       0
 10033.8     .17       0 10058.2     .15       0 10143.6     .17       0
Bank Sta=4872.5,5217
XS Rating Curve= 0 ,0
Exp/Cntr=0.3,0.1

Type RM Length L Ch R = 1 ,2081    ,0,0,0
BEGIN DESCRIPTION:
LAKE CREEK TRIBUTARY NO. 17 3.0
END DESCRIPTION:
XS GIS Cut Line= 4
      3757817.82     10101961.06      3756383.71      10101345.7
       3754859.7     10102225.25      3752824.98     10106190.52
#Sta/Elev= 30
  3436.8  210.76  3545.5  207.84  3700.8  195.48  3830.1  186.21  3902.6  181.01
  3948.2  182.85  4176.7  181.26    4242  183.51  4579.3  181.08  4589.7  177.48
  4622.9   180.7  4709.9  181.85    4982  180.94  5004.1  179.19  5378.8  181.81
  7802.3  183.73    8002     181  8718.2  184.14  9287.5  184.66    9533  184.97
  9549.5  182.73  9587.1  182.96  9724.6  184.15 10176.4  183.65 10217.4  183.77
   10605   184.9 10718.3  185.24   11003   193.5 11130.5  199.62 11213.8  200.19
#Mann= 13 ,-1 , 0
  3436.8     .11       0  3700.8     .17       0  3830.1     .15       0
  4709.9     .09       0  5378.8     .15       0  8718.2     .11       0
  9287.5     .15       0  9587.1     .11       0  9724.6     .15       0
 10176.4     .17       0 10217.4     .11       0   10605     .15       0
 10718.3     .17       0
Bank Sta=4709.9,5378.8
XS Rating Curve= 0 ,0
Exp/Cntr=0.3,0.1

Chan Stop Cuts=-1
Use User Specified Reach Order=0
Composite Channel Slope=5