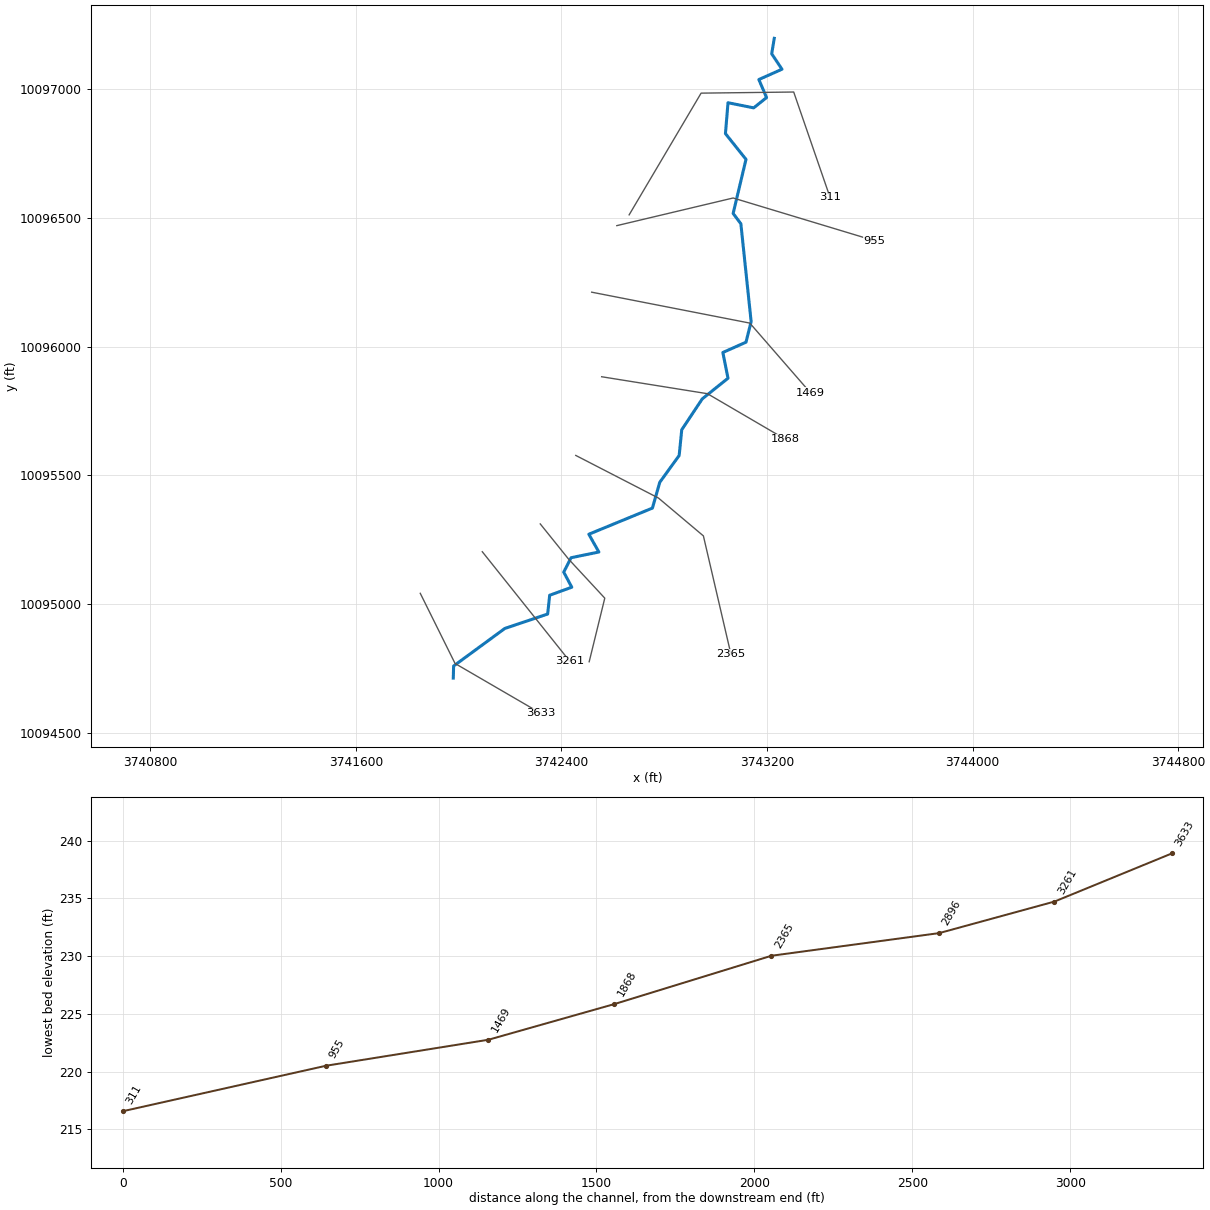
--- LAKE CREEK TRIBUTARY NO 18 5.prj (project) ---

Proj Title=LAKE CREEK TRIBUTARY NO 18 5 Base Level Engineering
Current Plan=p01
Default Exp/Contr=0.3,0.1
English Units
Geom File=g01
Flow File=f01
Flow File=f02
Plan File=p01
Y Axis Title=Elevation
X Axis Title(PF)=Main Channel Distance
X Axis Title(XS)=Station
BEGIN DESCRIPTION:
LAKE CREEK TRIBUTARY NO 18 5
END DESCRIPTION:
DSS Export Rating Curves= 0
DSS Export Rating Curve Sorted= 0
DSS Export Volume Flow Curves= 0
DXF OffsetX= 0
DXF OffsetY= 0
DXF ScaleX= 1
DXF ScaleY= 10

--- LAKE CREEK TRIBUTARY NO 18 5.p01 (plan) ---

Plan Title=Multiple Run
Short Identifier=Multiple
Geom File=g01
Flow File=f01
Subcritical Flow
K Sum by GR= 0
Std Step Tol= 0.01
Critical Tol= 0.01
Num of Std Step Trials= 20
Max Error Tol= 0.3
Flow Tol Ratio= 0.001
Split Flow NTrial= 30
Split Flow Tol= 0.02
Split Flow Ratio= 0.02
Log Output Level= 0
Friction Slope Method= 1
Unsteady Friction Slope Method= 2
Unsteady Bridges Friction Slope Method= 1
Parabolic Critical Depth
Global Vel Dist=  1 , 1 , 1
Global Log Level= 0
CheckData=True
Encroach Param= -1, 0, 0, 0
BEGIN DESCRIPTION:
Multiple Run
END DESCRIPTION:

--- LAKE CREEK TRIBUTARY NO 18 5.f01 (steady flow) ---

Flow Title=Multiple
Program Version=4.10
Number of Profiles= 7
Profile Names=10-year,25-year,50-year,1pct_min,100-year,1pct_plu,500-year
River Rch & RM=LAKE CREEK TRIBU,Reach-1         ,3633
     575     775    1044     464    1400    4228    2599
River Rch & RM=LAKE CREEK TRIBU,Reach-1         ,1469
     862    1191    1633     736    2224    6716    4266
Boundary for River Rch & Prof#=LAKE CREEK TRIBU,Reach-1         , 1
Up Type= 0
Dn Type= 3
Dn Slope=0.005
Boundary for River Rch & Prof#=LAKE CREEK TRIBU,Reach-1         , 2
Up Type= 0
Dn Type= 3
Dn Slope=0.005
Boundary for River Rch & Prof#=LAKE CREEK TRIBU,Reach-1         , 3
Up Type= 0
Dn Type= 3
Dn Slope=0.005
Boundary for River Rch & Prof#=LAKE CREEK TRIBU,Reach-1         , 4
Up Type= 0
Dn Type= 3
Dn Slope=0.005
Boundary for River Rch & Prof#=LAKE CREEK TRIBU,Reach-1         , 5
Up Type= 0
Dn Type= 3
Dn Slope=0.005
Boundary for River Rch & Prof#=LAKE CREEK TRIBU,Reach-1         , 6
Up Type= 0
Dn Type= 3
Dn Slope=0.005
Boundary for River Rch & Prof#=LAKE CREEK TRIBU,Reach-1         , 7
Up Type= 0
Dn Type= 3
Dn Slope=0.005
DSS Import GetInterval= 0
DSS Import GetPeak= 0
DSS Import FillOption= 0

--- LAKE CREEK TRIBUTARY NO 18 5.f02 (steady flow) ---

Flow Title=Orig_BLE_Flows
Program Version=4.10
Number of Profiles= 7
Profile Names=10-year,25-year,50-year,1pct_min,100-year,1pct_plu,500-year
River Rch & RM=LAKE CREEK TRIBU,Reach-1         ,3633
     575     760     908     357    1077    3253    1511
River Rch & RM=LAKE CREEK TRIBU,Reach-1         ,1469
     862    1168    1420     567    1711    5168    2480
Boundary for River Rch & Prof#=LAKE CREEK TRIBU,Reach-1         , 1
Up Type= 0
Dn Type= 3
Dn Slope=0.005
Boundary for River Rch & Prof#=LAKE CREEK TRIBU,Reach-1         , 2
Up Type= 0
Dn Type= 3
Dn Slope=0.005
Boundary for River Rch & Prof#=LAKE CREEK TRIBU,Reach-1         , 3
Up Type= 0
Dn Type= 3
Dn Slope=0.005
Boundary for River Rch & Prof#=LAKE CREEK TRIBU,Reach-1         , 4
Up Type= 0
Dn Type= 3
Dn Slope=0.005
Boundary for River Rch & Prof#=LAKE CREEK TRIBU,Reach-1         , 5
Up Type= 0
Dn Type= 3
Dn Slope=0.005
Boundary for River Rch & Prof#=LAKE CREEK TRIBU,Reach-1         , 6
Up Type= 0
Dn Type= 3
Dn Slope=0.005
Boundary for River Rch & Prof#=LAKE CREEK TRIBU,Reach-1         , 7
Up Type= 0
Dn Type= 3
Dn Slope=0.005
DSS Import GetInterval= 0
DSS Import GetPeak= 0
DSS Import FillOption= 0

--- LAKE CREEK TRIBUTARY NO 18 5.g01 (geometry) ---

Geom Title=Existing Conditions
Program Version=4.10

River Reach=LAKE CREEK TRIBU,Reach-1
Reach XY= 30
      3741979.44     10094712.44      3741980.74     10094759.32
      3742179.96     10094905.15      3742346.62     10094961.14
      3742354.44     10095034.06      3742440.37     10095065.31
      3742409.12      10095123.9      3742437.77     10095179.89
      3742545.84     10095202.03      3742506.78     10095271.04
      3742754.17      10095372.6      3742782.82     10095472.86
      3742858.23     10095576.84      3742868.23     10095676.84
      3742948.23     10095796.84      3743048.23     10095876.84
      3743028.23     10095976.84      3743118.23     10096016.84
      3743138.23     10096096.84      3743098.23     10096476.84
      3743068.23     10096516.84      3743118.23     10096726.84
      3743038.23     10096826.84      3743048.23     10096946.84
      3743148.23     10096926.84      3743198.23     10096966.84
      3743168.23     10097036.84      3743258.23     10097076.84
      3743218.23     10097136.84      3743228.23     10097196.84

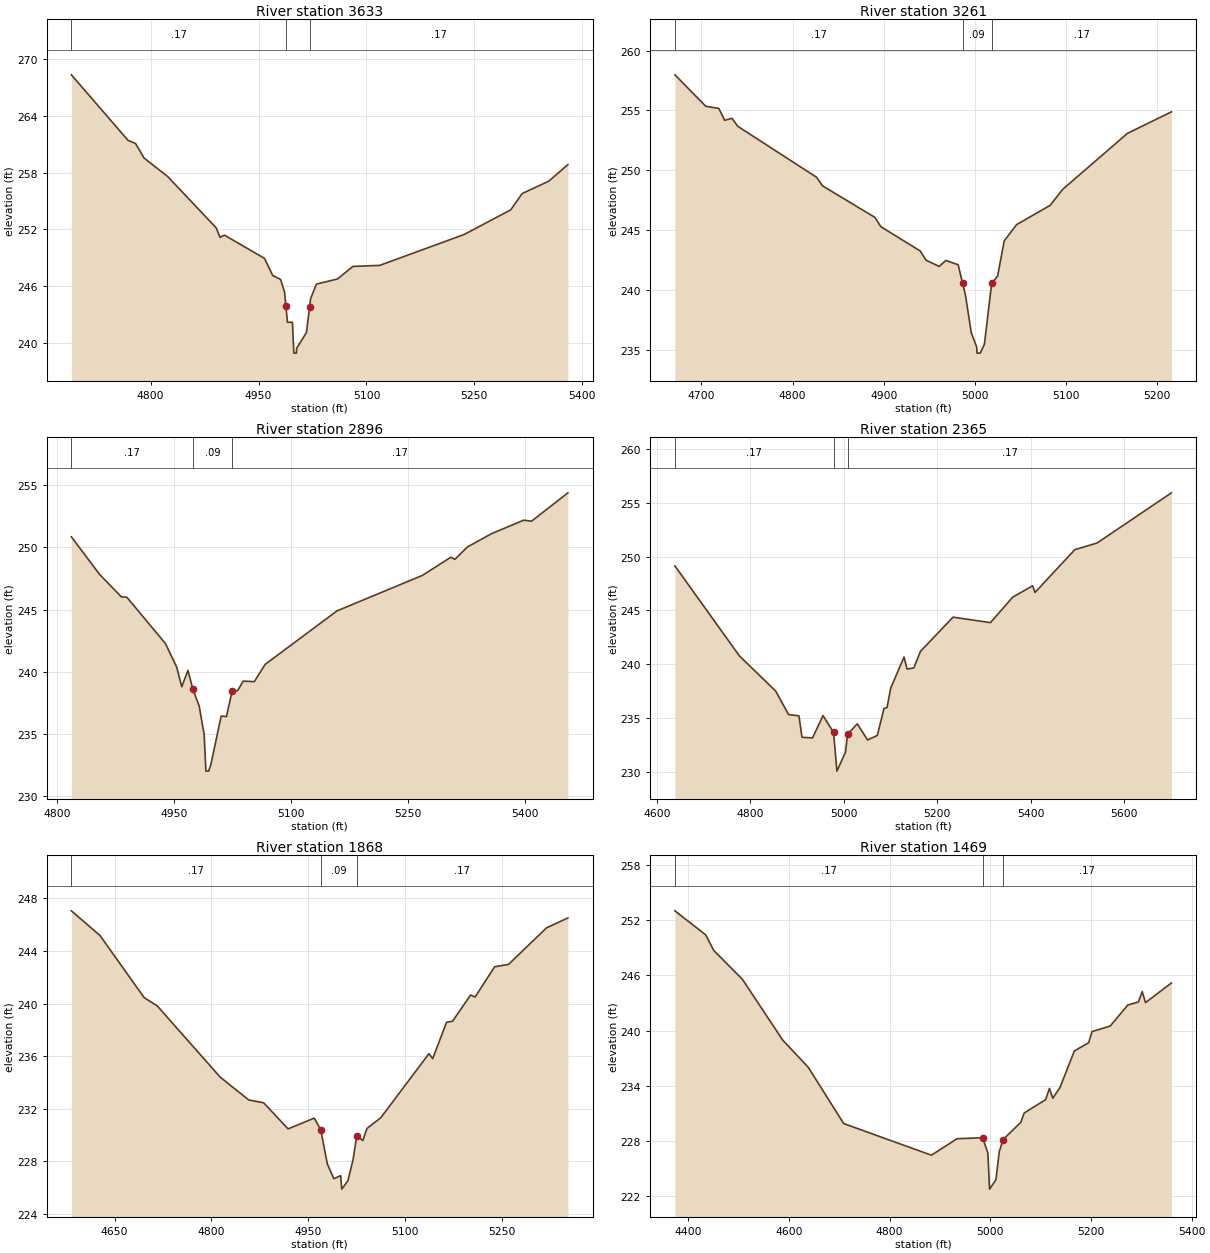
Type RM Length L Ch R = 1 ,3633    ,372,372,372
BEGIN DESCRIPTION:
LAKE CREEK TRIBUTARY NO. 18. 5 6.0
END DESCRIPTION:
XS GIS Cut Line= 3
      3741850.99     10095041.64      3741986.38     10094769.11
      3742320.23     10094575.38
#Sta/Elev= 30
  4689.8  268.33  4768.6   261.4    4779  261.07  4790.9  259.53  4823.8  257.57
  4891.1  252.15  4896.6  251.14  4902.6  251.38  4958.3  248.92  4969.6  247.12
  4980.7  246.69  4986.3  245.31  4988.1243.8561  4990.2  242.16  4997.1  242.16
  4999.1   238.9  5002.6   238.9  5002.9   239.4  5016.6  241.08 5021.04243.8206
  5022.4  244.66  5030.5   246.2  5059.7  246.74  5081.2  248.07  5118.5  248.18
    5236  251.45  5300.6  254.05  5316.4  255.77  5353.6  257.09  5380.1  258.84
#Mann= 3 , 0 , 0
  4689.8     .17       0  4988.1     .09       0 5021.04     .17       0
Bank Sta=4988.1,5021.04
XS Rating Curve= 0 ,0
Exp/Cntr=0.3,0.1

Type RM Length L Ch R = 1 ,3261    ,365,365,365
BEGIN DESCRIPTION:
Mapping XS 0680ade4
END DESCRIPTION:
XS GIS Cut Line= 2
      3742092.29     10095203.14      3742432.56      10094777.8
#Sta/Elev= 30
  4670.9  257.97  4704.7  255.35  4719.1  255.16  4725.5  254.17  4733.5  254.34
  4739.9  253.67  4826.4  249.41  4832.8   248.7  4890.4  246.06  4896.8  245.29
    4940  243.26  4946.4  242.49  4960.8  241.97  4968.1  242.47  4981.6  242.11
 4986.41240.5948  4989.6  239.59    4996  236.44    5002  235.23  5002.3  234.73
  5005.8  234.73  5010.4  235.47  5018.4  240.55  5024.9  241.16  5032.1   244.1
  5045.7  245.46  5082.5  247.07  5096.2   248.4  5167.3  253.08  5215.6  254.88
#Mann= 3 , 0 , 0
  4670.9     .17       0 4986.41     .09       0  5018.4     .17       0
Bank Sta=4986.41,5018.4
XS Rating Curve= 0 ,0
Exp/Cntr=0.3,0.1

Type RM Length L Ch R = 1 ,2896    ,531,531,531
BEGIN DESCRIPTION:
LAKE CREEK TRIBUTARY NO. 18. 5 5.0
END DESCRIPTION:
XS GIS Cut Line= 4
      3742317.86     10095311.06      3742427.77     10095174.76
      3742568.83     10095022.85      3742508.15     10094775.79
#Sta/Elev= 30
  4818.4  250.85  4854.4  247.84  4882.6  246.02  4889.6  245.99  4939.1  242.26
  4953.5  240.36    4960  238.79  4967.9   240.1  4974.3  238.58  4982.3  237.24
  4988.7  234.95  4990.9     232  4994.4     232  4997.2   232.5  5010.5  236.43
  5017.3  236.39  5024.7  238.47  5031.5  238.46  5038.8  239.24    5053   239.2
  5066.8  240.58    5159  244.89  5268.7  247.75  5305.1  249.21  5310.2  249.04
  5326.2  250.03  5357.1   251.1  5398.5  252.19  5408.6  252.11  5455.2  254.39
#Mann= 3 , 0 , 0
  4818.4     .17       0  4974.3     .09       0  5024.7     .17       0
Bank Sta=4974.3,5024.7
XS Rating Curve= 0 ,0
Exp/Cntr=0.3,0.1

Type RM Length L Ch R = 1 ,2365    ,497,497,497
BEGIN DESCRIPTION:
LAKE CREEK TRIBUTARY NO. 18. 5 4.0
END DESCRIPTION:
XS GIS Cut Line= 4
      3742455.97     10095577.11      3742777.61     10095411.66
      3742952.51     10095264.61      3743059.77     10094804.45
#Sta/Elev= 30
  4638.3  249.14  4776.4  240.76  4853.8   237.5  4881.6  235.31  4903.8  235.18
  4910.3  233.19  4932.8  233.13  4955.3  235.21  4977.8  233.65  4985.1  230.04
  5003.4  231.81  5007.8  233.47  5028.6  234.44  5050.7  232.94  5071.5  233.36
  5085.8  235.87  5092.3  235.95  5100.1  237.76  5128.7  240.66  5135.2  239.54
  5149.5  239.64  5163.9  241.19  5233.6  244.37  5313.6  243.86  5361.3  246.23
  5403.9  247.29    5409  246.67  5494.1  250.65  5541.8  251.27    5701  255.94
#Mann= 3 , 0 , 0
  4638.3     .17       0  4977.8     .09       0  5007.8     .17       0
Bank Sta=4977.8,5007.8
XS Rating Curve= 0 ,0
Exp/Cntr=0.3,0.1

Type RM Length L Ch R = 1 ,1868    ,399,399,399
BEGIN DESCRIPTION:
LAKE CREEK TRIBUTARY NO. 18. 5 3.0
END DESCRIPTION:
XS GIS Cut Line= 3
      3742556.66     10095882.66      3742968.23     10095816.84
      3743271.99     10095639.58
#Sta/Elev= 30
  4583.2  247.06  4627.5  245.18  4695.8  240.45  4716.1  239.82  4813.6  234.39
  4857.8  232.65  4880.7  232.44  4918.6  230.45  4959.1  231.27  4969.2  230.38
  4979.4  227.77  4989.5  226.65    5000  226.89  5001.7  225.86  5011.1  226.49
  5019.2  228.11  5024.9  229.93  5034.3  229.56  5040.7  230.48  5062.1   231.3
  5136.6  236.18  5142.4   235.8  5163.9  238.57  5173.2  238.65  5201.1  240.65
    5208  240.49  5238.3   242.8  5259.8  242.98  5318.5  245.76  5351.7  246.52
#Mann= 3 , 0 , 0
  4583.2     .17       0  4969.2     .09       0  5024.9     .17       0
Bank Sta=4969.2,5024.9
XS Rating Curve= 0 ,0
Exp/Cntr=0.3,0.1

Type RM Length L Ch R = 1 ,1469    ,514,514,514
BEGIN DESCRIPTION:
LAKE CREEK TRIBUTARY NO. 18. 5 2.0
END DESCRIPTION:
XS GIS Cut Line= 3
      3742517.89     10096211.06      3743133.07       10096091.
      3743369.19     10095820.15
#Sta/Elev= 30
  4373.8  253.03  4434.9  250.42  4451.1  248.71  4507.8  245.59  4587.7  238.99
  4638.7  236.01    4709   229.9  4883.2  226.46  4934.1  228.25  4985.1  228.36
  4995.3  226.69  4998.7  222.77  5011.3  223.78  5017.9  226.83  5025.5  228.16
  5060.7  230.03  5067.3  231.04    5110   232.5  5117.6  233.72  5124.3  232.66
  5138.5  233.81    5167  237.79  5195.5  238.69  5202.1   239.9  5238.2   240.5
  5273.3  242.79  5294.2  243.12  5301.8  244.24  5308.4  243.05  5359.9  245.19
#Mann= 3 , 0 , 0
  4373.8     .17       0  4985.1     .09       0  5025.5     .17       0
Bank Sta=4985.1,5025.5
XS Rating Curve= 0 ,0
Exp/Cntr=0.3,0.1

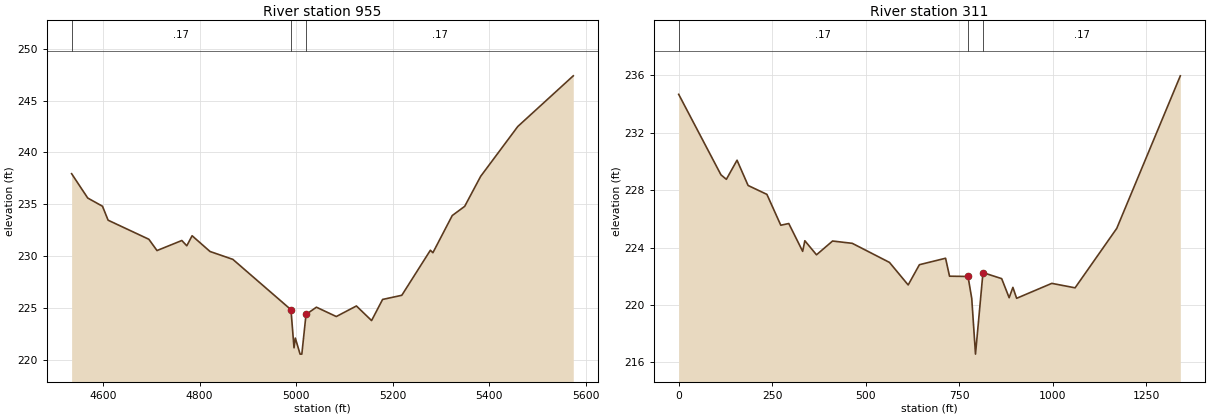
Type RM Length L Ch R = 1 ,955     ,644,644,644
BEGIN DESCRIPTION:
LAKE CREEK TRIBUTARY NO. 18. 5 1.0
END DESCRIPTION:
XS GIS Cut Line= 3
       3742615.7     10096469.46      3743068.23     10096576.84
      3743617.87     10096411.06
#Sta/Elev= 30
  4534.9  237.94  4568.3  235.59  4598.8   234.8  4610.5  233.45  4694.9  231.61
  4711.8  230.52  4763.2  231.49  4773.5  230.98  4784.5  231.95  4821.6  230.43
  4868.9  229.67  4989.3  224.81  4995.6  221.13  4998.3  222.07  5008.2  220.52
  5011.8  220.52  5020.5  224.35    5042  225.05  5083.2  224.15  5124.9  225.17
  5156.3  223.76  5179.1   225.8  5218.9   226.2  5278.1  230.55  5283.3  230.31
  5323.4   233.9  5349.2  234.79  5382.2  237.68  5459.2   242.5  5574.1  247.39
#Mann= 3 , 0 , 0
  4534.9     .17       0  4989.3     .09       0  5020.5     .17       0
Bank Sta=4989.3,5020.5
XS Rating Curve= 0 ,0
Exp/Cntr=0.3,0.1

Type RM Length L Ch R = 1 ,311     ,0,0,0
BEGIN DESCRIPTION:
LAKE CREEK TRIBUTARY NO. 18. 5 0.5
END DESCRIPTION:
XS GIS Cut Line= 4
      3742663.63     10096511.36      3742943.58     10096984.02
      3743303.82     10096988.36      3743444.88     10096580.37
#Sta/Elev= 30
       0  234.68   113.1  229.07   127.5  228.76     156  230.09   185.6  228.33
   235.9  227.71     273  225.56   294.4  225.68   331.5  223.74   337.3  224.48
   368.5   223.5   411.4  224.46   464.1   224.3   563.6  222.97   613.6   221.4
   643.6  222.81   713.6  223.26   724.2  222.01   773.6  221.99   783.6  220.46
   793.6  216.58   813.6  222.26   863.6  221.84   883.6  220.51   893.6  221.23
   903.6  220.47   997.6  221.51  1059.9   221.2  1171.3  225.34  1341.3  235.97
#Mann= 3 , 0 , 0
       0     .17       0   773.6     .06       0   813.6     .17       0
Bank Sta=773.6,813.6
XS Rating Curve= 0 ,0
Exp/Cntr=0.3,0.1

Chan Stop Cuts=-1
Use User Specified Reach Order=0
Composite Channel Slope=5