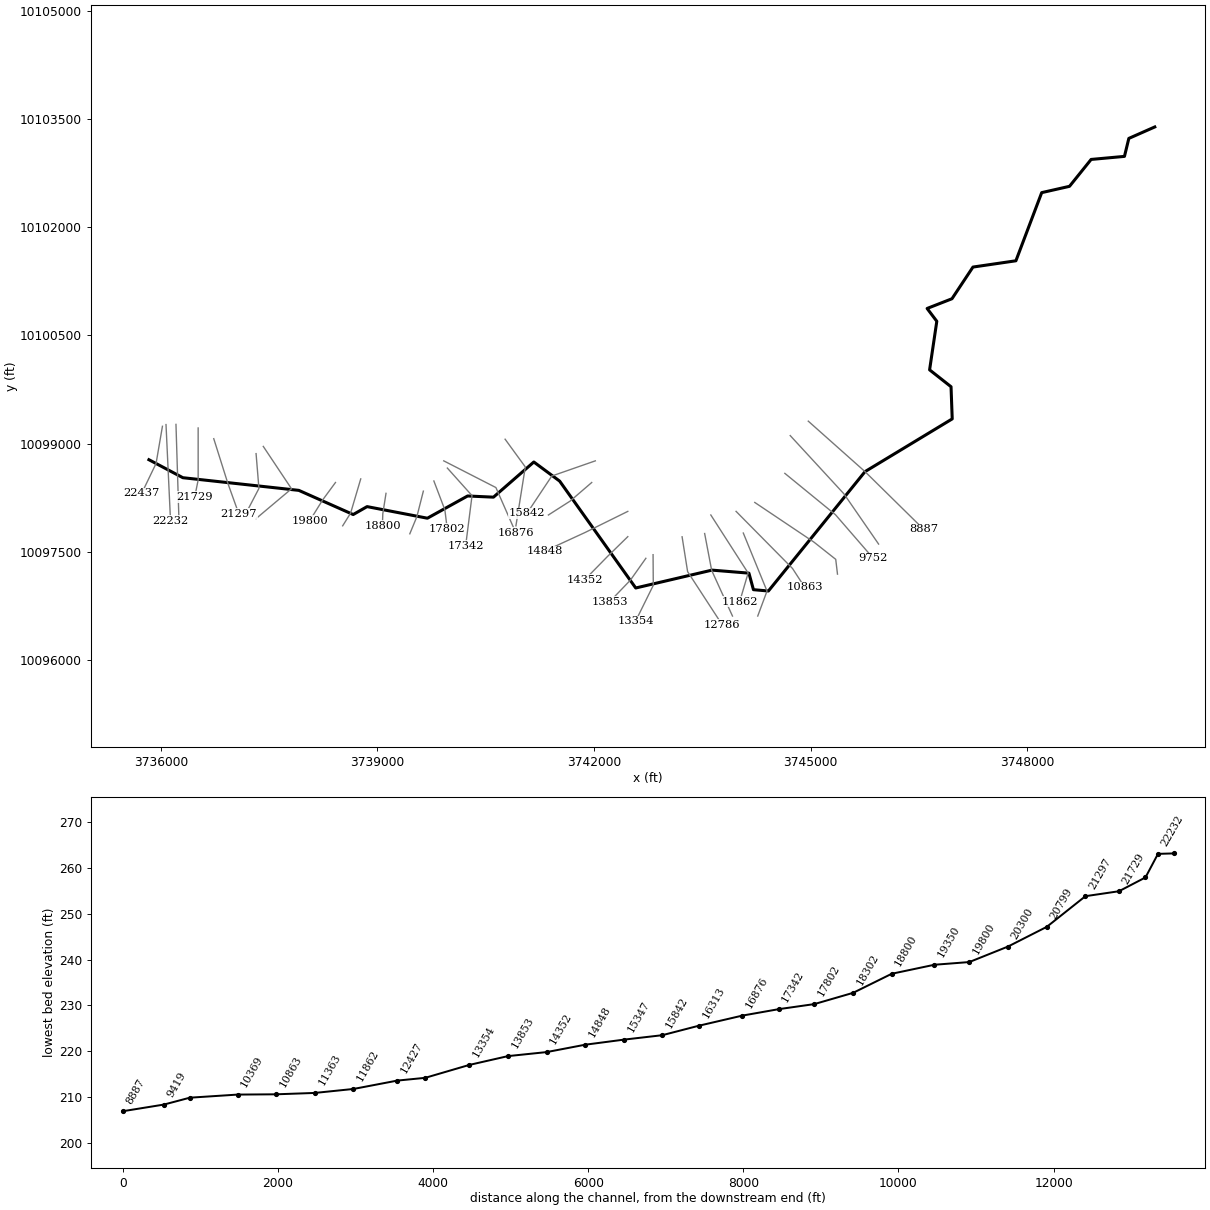
--- LAKE CREEK TRIBUTARY NO 18.prj (project) ---

Proj Title=LAKE CREEK TRIBUTARY NO 18 Base Level Engineering
Current Plan=p01
Default Exp/Contr=0.3,0.1
English Units
Geom File=g01
Flow File=f01
Flow File=f02
Plan File=p01
Y Axis Title=Elevation
X Axis Title(PF)=Main Channel Distance
X Axis Title(XS)=Station
BEGIN DESCRIPTION:
LAKE CREEK TRIBUTARY NO 18
END DESCRIPTION:
DSS Export Rating Curves= 0
DSS Export Rating Curve Sorted= 0
DSS Export Volume Flow Curves= 0
DXF OffsetX= 0
DXF OffsetY= 0
DXF ScaleX= 1
DXF ScaleY= 10

--- LAKE CREEK TRIBUTARY NO 18.p01 (plan) ---

Plan Title=Multiple Run
Short Identifier=Multiple
Geom File=g01
Flow File=f01
Subcritical Flow
K Sum by GR= 0
Std Step Tol= 0.01
Critical Tol= 0.01
Num of Std Step Trials= 20
Max Error Tol= 0.3
Flow Tol Ratio= 0.001
Split Flow NTrial= 30
Split Flow Tol= 0.02
Split Flow Ratio= 0.02
Log Output Level= 0
Friction Slope Method= 1
Unsteady Friction Slope Method= 2
Unsteady Bridges Friction Slope Method= 1
Parabolic Critical Depth
Global Vel Dist=  1 , 1 , 1
Global Log Level= 0
CheckData=True
Encroach Param= -1, 0, 0, 0
BEGIN DESCRIPTION:
Multiple Run
END DESCRIPTION:

--- LAKE CREEK TRIBUTARY NO 18.f01 (steady flow) ---

Flow Title=Multiple
Program Version=4.10
Number of Profiles= 7
Profile Names=10-year,25-year,50-year,1pct_min,100-year,1pct_plu,500-year
River Rch & RM=LAKE CREEK TRIBU,Reach-1         ,22437
     887    1229    1688     762    2302    6952    4429
River Rch & RM=LAKE CREEK TRIBU,Reach-1         ,17802
    1043    1439    1970     885    2672    8069    5088
River Rch & RM=LAKE CREEK TRIBU,Reach-1         ,12786
    1511    2108    2905    1311    3959   11956    7614
River Rch & RM=LAKE CREEK TRIBU,Reach-1         ,4841
    1693    2378    3289    1491    4502   13596    8727
Boundary for River Rch & Prof#=LAKE CREEK TRIBU,Reach-1         , 1
Up Type= 0
Dn Type= 3
Dn Slope=0.005
Boundary for River Rch & Prof#=LAKE CREEK TRIBU,Reach-1         , 2
Up Type= 0
Dn Type= 3
Dn Slope=0.005
Boundary for River Rch & Prof#=LAKE CREEK TRIBU,Reach-1         , 3
Up Type= 0
Dn Type= 3
Dn Slope=0.005
Boundary for River Rch & Prof#=LAKE CREEK TRIBU,Reach-1         , 4
Up Type= 0
Dn Type= 3
Dn Slope=0.005
Boundary for River Rch & Prof#=LAKE CREEK TRIBU,Reach-1         , 5
Up Type= 0
Dn Type= 3
Dn Slope=0.005
Boundary for River Rch & Prof#=LAKE CREEK TRIBU,Reach-1         , 6
Up Type= 0
Dn Type= 3
Dn Slope=0.005
Boundary for River Rch & Prof#=LAKE CREEK TRIBU,Reach-1         , 7
Up Type= 0
Dn Type= 3
Dn Slope=0.005
DSS Import GetInterval= 0
DSS Import GetPeak= 0
DSS Import FillOption= 0

--- LAKE CREEK TRIBUTARY NO 18.f02 (steady flow) ---

Flow Title=Orig_BLE_Flows
Program Version=4.10
Number of Profiles= 7
Profile Names=10-year,25-year,50-year,1pct_min,100-year,1pct_plu,500-year
River Rch & RM=LAKE CREEK TRIBU,Reach-1         ,22437
     887    1205    1468     587    1771    5349    2575
River Rch & RM=LAKE CREEK TRIBU,Reach-1         ,17802
    1043    1411    1713     681    2055    6207    2958
River Rch & RM=LAKE CREEK TRIBU,Reach-1         ,12786
    1511    2067    2526    1008    3045    9197    4427
River Rch & RM=LAKE CREEK TRIBU,Reach-1         ,4841
    1693    2331    2860    1147    3463   10457    5074
Boundary for River Rch & Prof#=LAKE CREEK TRIBU,Reach-1         , 1
Up Type= 0
Dn Type= 3
Dn Slope=0.005
Boundary for River Rch & Prof#=LAKE CREEK TRIBU,Reach-1         , 2
Up Type= 0
Dn Type= 3
Dn Slope=0.005
Boundary for River Rch & Prof#=LAKE CREEK TRIBU,Reach-1         , 3
Up Type= 0
Dn Type= 3
Dn Slope=0.005
Boundary for River Rch & Prof#=LAKE CREEK TRIBU,Reach-1         , 4
Up Type= 0
Dn Type= 3
Dn Slope=0.005
Boundary for River Rch & Prof#=LAKE CREEK TRIBU,Reach-1         , 5
Up Type= 0
Dn Type= 3
Dn Slope=0.005
Boundary for River Rch & Prof#=LAKE CREEK TRIBU,Reach-1         , 6
Up Type= 0
Dn Type= 3
Dn Slope=0.005
Boundary for River Rch & Prof#=LAKE CREEK TRIBU,Reach-1         , 7
Up Type= 0
Dn Type= 3
Dn Slope=0.005
DSS Import GetInterval= 0
DSS Import GetPeak= 0
DSS Import FillOption= 0

--- LAKE CREEK TRIBUTARY NO 18.g01 (geometry) ---

Geom Title=Existing Conditions
Program Version=4.10

River Reach=LAKE CREEK TRIBU,Reach-1
Reach XY= 30
      3735833.23     10098776.84      3736303.47     10098527.56
      3737910.12     10098352.18      3738663.39     10098017.33
      3738855.55     10098127.11      3739691.28     10097966.41
      3740248.21     10098274.42      3740606.71     10098258.06
      3741165.84     10098745.23      3741523.66     10098480.36
      3742577.54      10096999.7      3743633.83     10097247.19
      3744145.73     10097205.39      3744208.24     10096976.31
      3744415.75     10096958.01      3745754.18      10098611.8
      3746962.12     10099342.27      3746945.72     10099787.91
      3746648.79     10100021.87      3746748.55     10100694.56
      3746614.49      10100872.2      3746958.85     10101006.98
      3747249.53     10101445.79      3747844.44     10101532.78
       3748201.8     10102476.93      3748586.99     10102564.27
       3748886.5     10102936.77      3749348.23     10102979.06
      3749408.93     10103228.14      3749768.23     10103386.84

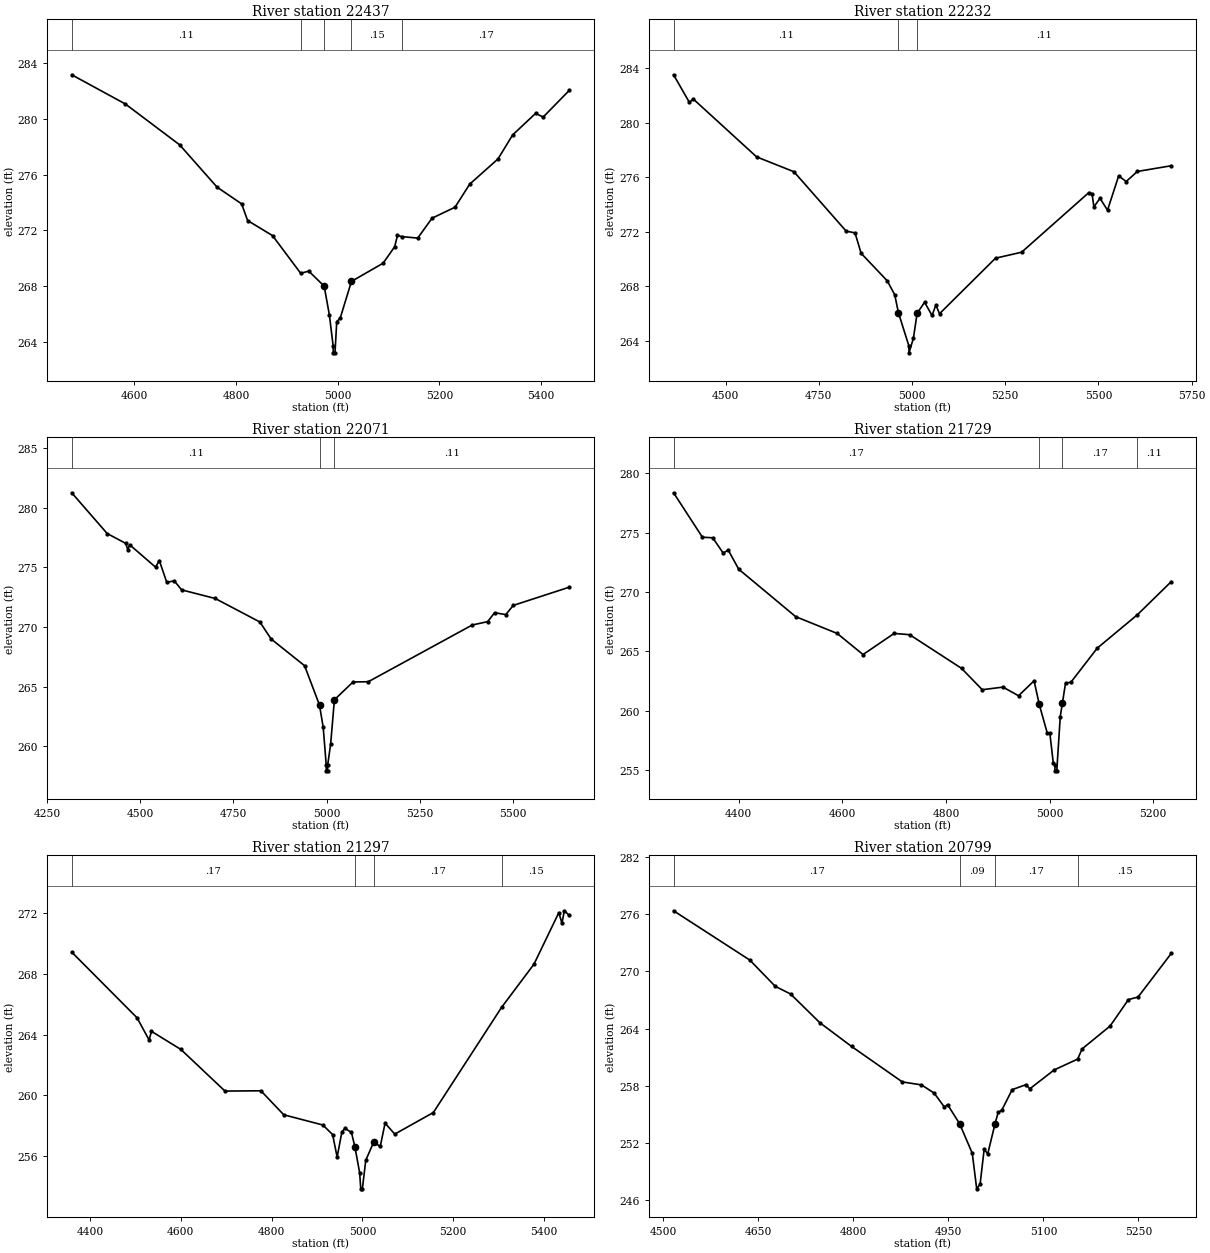
Type RM Length L Ch R = 1 ,22437   ,205,205,205
BEGIN DESCRIPTION:
LAKE CREEK TRIBUTARY NO. 18 45.0
END DESCRIPTION:
XS GIS Cut Line= 3
      3736020.65     10099240.06      3735932.43     10098724.96
      3735734.92      10098314.5
#Sta/Elev= 30
  4477.4  283.18  4582.9  281.08  4689.4  278.15    4763  275.11  4811.2  273.91
  4823.1  272.71    4872  271.63  4927.4  268.92  4943.2  269.08  4973.5     268
  4983.7  265.94  4991.1  263.71  4991.3  263.21  4994.8  263.21  4998.2  265.45
  5004.9  265.69  5027.1  268.34  5089.4  269.65    5112  270.83  5117.6  271.64
  5125.8  271.56  5157.3  271.45  5185.5  272.88  5230.7  273.67  5259.6  275.33
    5315  277.13  5343.9  278.86  5389.1  280.41  5403.8  280.14  5455.5  282.07
#Mann= 5 ,-1 , 0
  4477.4     .11       0  4927.4     .15       0  4973.5     .09       0
  5027.1     .15       0  5125.8     .17       0
Bank Sta=4973.5,5027.1
XS Rating Curve= 0 ,0
Exp/Cntr=0.3,0.1

Type RM Length L Ch R = 1 ,22232   ,161,161,161
BEGIN DESCRIPTION:
Mapping XS 07bd58a4
END DESCRIPTION:
XS GIS Cut Line= 2
      3736070.13     10099263.56      3736132.63     10097930.22
#Sta/Elev= 30
  4360.5   283.5    4403  281.47    4413  281.73  4583.2  277.48  4683.3  276.39
  4823.5  272.03  4847.1  271.91  4863.5  270.41  4933.6  268.39  4953.6  267.37
  4963.6  266.05  4991.7  263.61  4991.9  263.11  5003.7  264.18  5013.7  266.01
  5033.7  266.82  5053.7  265.85    5064  266.61  5073.8  265.98  5223.9  270.05
    5294  270.49  5474.2  274.86  5482.8  274.77  5487.8  273.82  5504.2  274.44
  5524.3  273.57  5554.3  276.09  5574.3  275.67  5604.3  276.41  5695.3  276.83
#Mann= 3 ,-1 , 0
  4360.5     .11       0  4963.6     .07       0  5013.7     .11       0
Bank Sta=4963.6,5013.7
XS Rating Curve= 0 ,0
Exp/Cntr=0.3,0.1

Type RM Length L Ch R = 1 ,22071   ,342,342,342
BEGIN DESCRIPTION:
Mapping XS 1fcb4089
END DESCRIPTION:
XS GIS Cut Line= 2
      3736208.15     10099266.17      3736249.82     10097930.22
#Sta/Elev= 30
  4315.8  281.24  4410.9  277.83    4461     277  4466.3  276.47  4471.3  276.89
    4541  275.01    4551  275.57    4571  273.74    4591  273.87    4611  273.11
  4701.1  272.39  4821.1  270.42  4851.2     269  4941.2  266.76  4981.2  263.46
  4991.2  261.59  4999.2  258.46  4999.5  257.96    5003  257.96  5003.2  258.46
  5011.2  260.22  5021.2  263.91  5071.3   265.4  5112.2  265.42  5391.4  270.17
  5432.7  270.45  5451.5   271.2  5481.5  271.04  5501.5  271.81  5652.4  273.34
#Mann= 3 ,-1 , 0
  4315.8     .11       0  4981.2     .07       0  5021.2     .11       0
Bank Sta=4981.2,5021.2
XS Rating Curve= 0 ,0
Exp/Cntr=0.3,0.1

Type RM Length L Ch R = 1 ,21729   ,432,432,432
BEGIN DESCRIPTION:
LAKE CREEK TRIBUTARY NO. 18 44.0
END DESCRIPTION:
XS GIS Cut Line= 3
      3736515.45     10099216.63      3736515.45     10098495.29
      3736467.86     10098261.12
#Sta/Elev= 30
  4274.5  278.35  4330.1  274.61  4350.1  274.56  4370.1  273.28  4380.1  273.52
  4400.1  271.92  4510.1  267.92  4590.1  266.51  4640.1  264.73  4700.1  266.51
  4730.1   266.4  4830.1  263.57  4870.1  261.77  4910.1  261.99  4940.1  261.26
  4970.1  262.52  4980.1  260.53  4995.5  258.12  5000.5  258.12  5007.1  255.62
  5010.2  255.44  5010.4  254.94  5013.9  254.94  5020.6   259.5  5024.8260.6653
  5030.8  262.33    5041  262.39    5092  265.27  5169.4  268.08  5234.8  270.87
#Mann= 4 ,-1 , 0
  4274.5     .17       0  4980.1     .09       0  5024.8     .17       0
  5169.4     .11       0
Bank Sta=4980.1,5024.8
XS Rating Curve= 0 ,0
Exp/Cntr=0.3,0.1

Type RM Length L Ch R = 1 ,21297   ,498,498,498
BEGIN DESCRIPTION:
LAKE CREEK TRIBUTARY NO. 18 43.0
END DESCRIPTION:
XS GIS Cut Line= 3
      3736731.58     10099068.23      3736923.98     10098458.05
      3737077.95     10098029.14
#Sta/Elev= 30
  4360.2  269.43    4504  265.11  4530.5  263.65  4535.7  264.22  4600.4  263.03
  4697.5  260.29  4776.6  260.31  4826.9  258.73  4912.9  258.06  4934.4  257.43
  4944.4  255.95  4954.9  257.61  4961.6  257.84  4975.9  257.57  4983.6256.6075
  4993.9  254.92  4996.4  253.86  4999.9  253.86  5007.4  255.74  5024.8  256.93
  5039.3  256.65  5049.9  258.18  5071.2  257.46  5156.2  258.88  5306.2  265.79
  5377.7  268.64  5432.4  272.03  5439.2  271.33  5444.5  272.15  5455.7  271.84
#Mann= 4 ,-1 , 0
  4360.2     .17       0  4983.6     .09       0  5024.8     .17       0
  5306.2     .15       0
Bank Sta=4983.6,5024.8
XS Rating Curve= 0 ,0
Exp/Cntr=0.3,0.1

Type RM Length L Ch R = 1 ,20799   ,499,499,499
BEGIN DESCRIPTION:
LAKE CREEK TRIBUTARY NO. 18 42.0
END DESCRIPTION:
XS GIS Cut Line= 3
      3737317.85     10098861.11      3737357.37     10098378.73
      3737217.87     10098111.11
#Sta/Elev= 30
    4516  276.37  4636.4  271.19  4676.6  268.43  4700.7  267.63  4746.8  264.62
    4797  262.12  4877.2  258.39  4907.4  258.08  4927.4  257.22  4943.6  255.75
  4948.6  256.01  4967.6     254  4987.6   250.9  4994.6  247.16    5000  247.66
  5006.4  251.33    5012  250.82 5023.36253.9468  5028.5  255.19  5034.1  255.41
  5050.6  257.58  5072.7  258.11  5078.3  257.66  5116.9  259.65    5154  260.79
    5161  261.86  5205.2  264.26  5234.2  267.04  5249.4  267.31  5301.8  271.89
#Mann= 4 ,-1 , 0
    4516     .17       0  4967.6     .09       0 5023.36     .17       0
    5154     .15       0
Bank Sta=4967.6,5023.36
XS Rating Curve= 0 ,0
Exp/Cntr=0.3,0.1

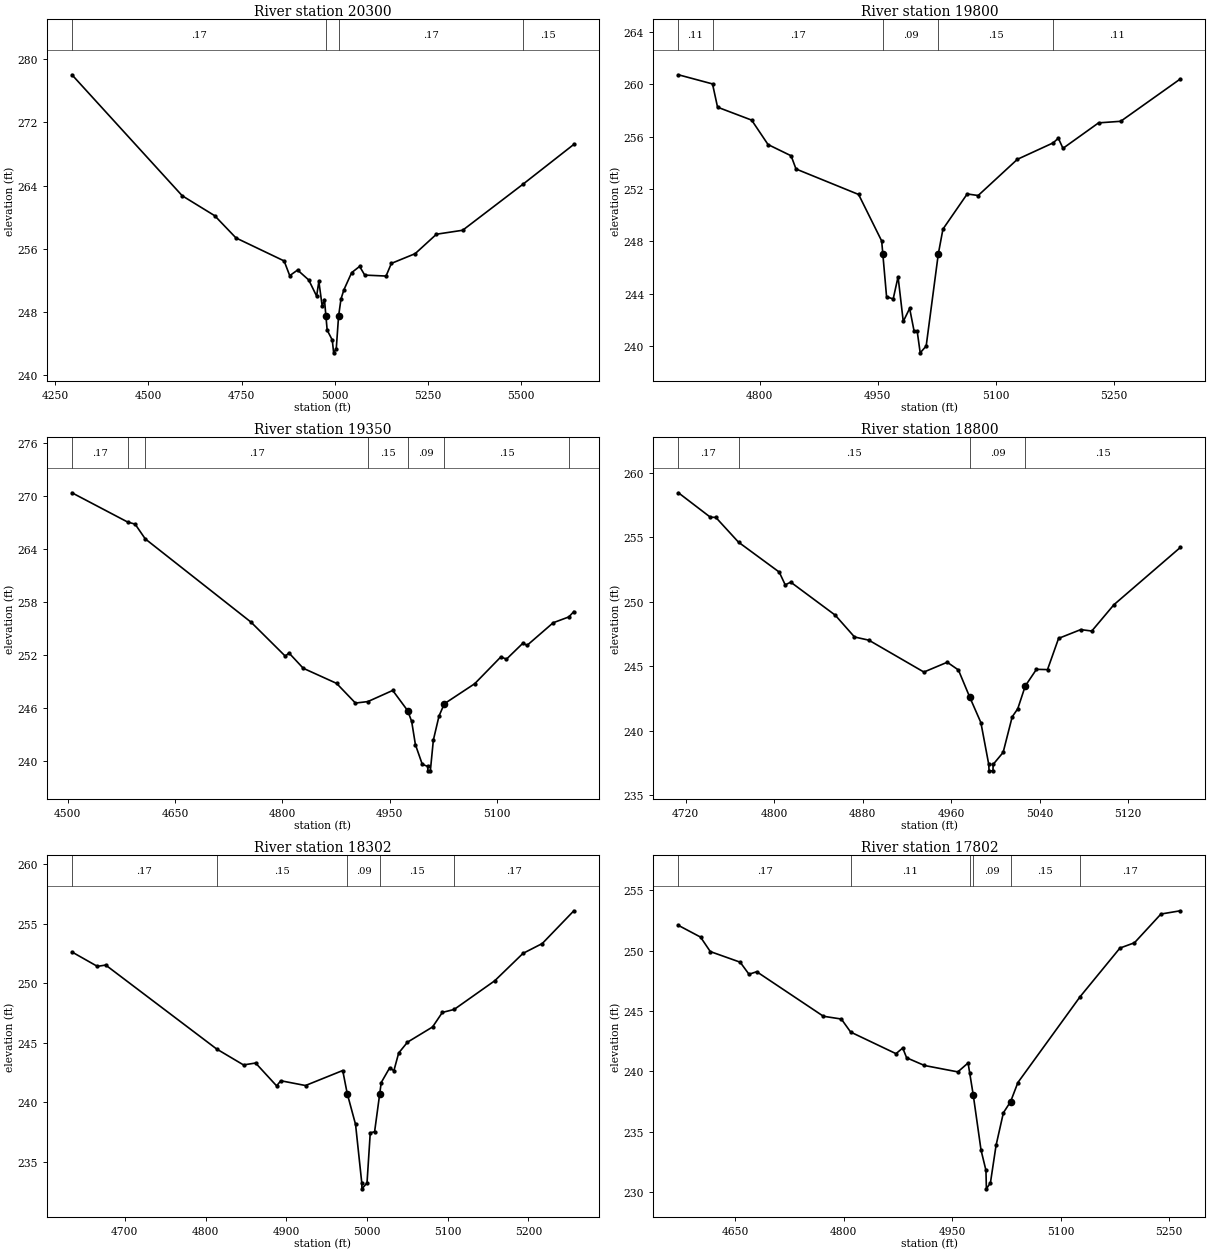
Type RM Length L Ch R = 1 ,20300   ,500,500,500
BEGIN DESCRIPTION:
LAKE CREEK TRIBUTARY NO. 18 41.0
END DESCRIPTION:
XS GIS Cut Line= 3
      3737417.88     10098961.03      3737808.91     10098374.05
      3737317.88     10097961.09
#Sta/Elev= 30
  4294.7  278.02  4590.7  262.72  4677.8   260.2  4734.9  257.39  4864.1  254.48
  4879.1  252.62  4900.2  253.33  4930.2  252.07  4951.3  250.03  4957.3  251.89
  4966.3  248.75  4972.3   249.6  4976.3247.4795  4979.6  245.73  4993.3  244.48
    4997  242.86    5004  243.36  5010.2  247.49  5016.7  249.67  5024.5  250.83
  5045.3     253  5066.7  253.79  5080.4  252.69  5137.6  252.57  5151.9  254.17
  5215.7   255.4  5272.9  257.86  5343.2  258.36  5504.2  264.15  5641.6  269.22
#Mann= 4 ,-1 , 0
  4294.7     .17       0  4976.3     .09       0  5010.2     .17       0
  5504.2     .15       0
Bank Sta=4976.3,5010.2
XS Rating Curve= 0 ,0
Exp/Cntr=0.3,0.1

Type RM Length L Ch R = 1 ,19800   ,450,450,450
BEGIN DESCRIPTION:
LAKE CREEK TRIBUTARY NO. 18 40.0
END DESCRIPTION:
XS GIS Cut Line= 3
      3738417.87      10098461.1      3738238.23     10098216.84
      3738062.33      10097932.8
#Sta/Elev= 30
  4696.8  260.74  4740.1  260.04  4746.5  258.26  4789.8  257.27  4810.6   255.4
  4839.9  254.54  4846.1  253.53  4925.6  251.58  4954.9  248.02  4956.3247.0582
  4961.1  243.76  4969.5  243.58  4975.7  245.28  4982.3  241.86  4990.4  242.86
  4996.1  241.11    5000  241.11  5003.8  239.46  5011.4  239.98  5026.8  247.03
  5032.7  248.93  5063.5  251.62  5077.4   251.5  5127.2  254.27  5172.7  255.53
  5179.2  255.89  5185.1  255.11  5230.3  257.06  5258.4  257.18  5334.1  260.42
#Mann= 5 ,-1 , 0
  4696.8     .11       0  4740.1     .17       0  4956.3     .09       0
  5026.8     .15       0  5172.7     .11       0
Bank Sta=4956.3,5026.8
XS Rating Curve= 0 ,0
Exp/Cntr=0.3,0.1

Type RM Length L Ch R = 1 ,19350   ,550,550,550
BEGIN DESCRIPTION:
LAKE CREEK TRIBUTARY NO. 18 39.0
END DESCRIPTION:
XS GIS Cut Line= 3
      3738767.84     10098511.02      3738627.42     10098036.96
      3738517.88     10097861.11
#Sta/Elev= 30
  4506.1  270.34  4583.9  267.03  4594.4  266.79  4608.6  265.12  4756.4   255.7
  4804.3  251.85  4809.5  252.21  4829.4  250.48    4876  248.77  4902.4  246.54
  4919.8  246.71  4954.5  247.97  4975.4  245.68    4981  244.46  4986.2  241.84
  4995.8  239.61  5003.4  239.37  5003.6  238.87  5007.1  238.87  5011.3  242.35
  5019.2  245.07  5026.6  246.46  5069.1  248.73  5105.7  251.77  5113.5  251.51
  5136.4  253.31  5142.3  253.07  5178.8  255.63  5200.7  256.29  5207.7   256.9
#Mann= 7 ,-1 , 0
  4506.1     .17       0  4583.9     .11       0  4608.6     .17       0
  4919.8     .15       0  4975.4     .09       0  5026.6     .15       0
  5200.7     .17       0
Bank Sta=4975.4,5026.6
XS Rating Curve= 0 ,0
Exp/Cntr=0.3,0.1

Type RM Length L Ch R = 1 ,18800   ,498,498,498
BEGIN DESCRIPTION:
LAKE CREEK TRIBUTARY NO. 18 38.0
END DESCRIPTION:
XS GIS Cut Line= 3
      3739117.85     10098311.05      3739073.47       10098028.
      3739067.85      10097861.1
#Sta/Elev= 30
  4713.5  258.46  4742.3  256.57  4747.3  256.55  4767.8  254.63  4804.6  252.31
    4810  251.32    4815  251.53  4855.2  248.97  4872.6  247.28  4885.6  247.03
  4935.3  244.56  4956.4  245.32  4966.5  244.72  4976.7  242.62  4986.8  240.64
  4993.9   237.4  4994.2   236.9  4997.7   236.9  4997.9   237.4  5006.9  238.33
  5015.1  241.09  5020.1  241.71  5026.9  243.48    5037  244.77    5047  244.75
    5057  247.17    5077  247.85    5087  247.74    5107  249.78    5167  254.22
#Mann= 4 ,-1 , 0
  4713.5     .17       0  4767.8     .15       0  4976.7     .09       0
  5026.9     .15       0
Bank Sta=4976.7,5026.9
XS Rating Curve= 0 ,0
Exp/Cntr=0.3,0.1

Type RM Length L Ch R = 1 ,18302   ,500,500,500
BEGIN DESCRIPTION:
LAKE CREEK TRIBUTARY NO. 18 37.0
END DESCRIPTION:
XS GIS Cut Line= 3
      3739635.23     10098341.62      3739545.35     10097987.35
      3739447.73     10097750.47
#Sta/Elev= 30
  4634.5  252.63    4666  251.42  4676.3  251.53  4813.7  244.48    4847  243.14
    4862   243.3    4888  241.38  4893.2  241.81  4923.8  241.41  4969.9  242.67
  4975.5  240.73  4985.8  238.14  4993.5  233.23  4993.7  232.73    5000  233.23
    5004  237.43  5009.4  237.53 5015.61240.6576  5017.6  241.66  5027.9  242.88
  5033.3  242.66  5039.2  244.14  5050.1  245.05  5081.2  246.33  5093.3  247.55
  5107.9   247.8  5158.2  250.21  5193.2  252.51  5217.1  253.34  5256.2  256.09
#Mann= 5 ,-1 , 0
  4634.5     .17       0  4813.7     .15       0  4975.5     .09       0
 5015.61     .15       0  5107.9     .17       0
Bank Sta=4975.5,5015.61
XS Rating Curve= 0 ,0
Exp/Cntr=0.3,0.1

Type RM Length L Ch R = 1 ,17802   ,460,460,460
BEGIN DESCRIPTION:
LAKE CREEK TRIBUTARY NO. 18 36.0
END DESCRIPTION:
XS GIS Cut Line= 3
      3739781.08     10098482.25      3739933.55     10098081.58
      3739965.97     10097818.17
#Sta/Elev= 30
  4571.3   252.1  4601.9  251.13  4615.4  249.93  4656.7  249.05  4668.9  248.05
  4679.6  248.26  4771.8  244.57  4796.6  244.34  4809.5  243.26  4872.2  241.47
  4881.5  241.94  4886.9  241.13  4911.6  240.49  4957.7  239.96  4971.9   240.7
  4974.1  239.88  4979.1  238.02  4989.8  233.48  4996.6   231.8  4997.2  230.27
  5002.8  230.77  5010.6  233.88  5020.7  236.57  5030.7   237.5  5040.8  239.08
  5126.8  246.19  5181.9  250.22    5202  250.66  5238.6  253.04  5265.4  253.31
#Mann= 6 ,-1 , 0
  4571.3     .17       0  4809.5     .11       0  4974.1     .15       0
  4979.1     .09       0  5030.7     .15       0  5126.8     .17       0
Bank Sta=4979.1,5030.7
XS Rating Curve= 0 ,0
Exp/Cntr=0.3,0.1

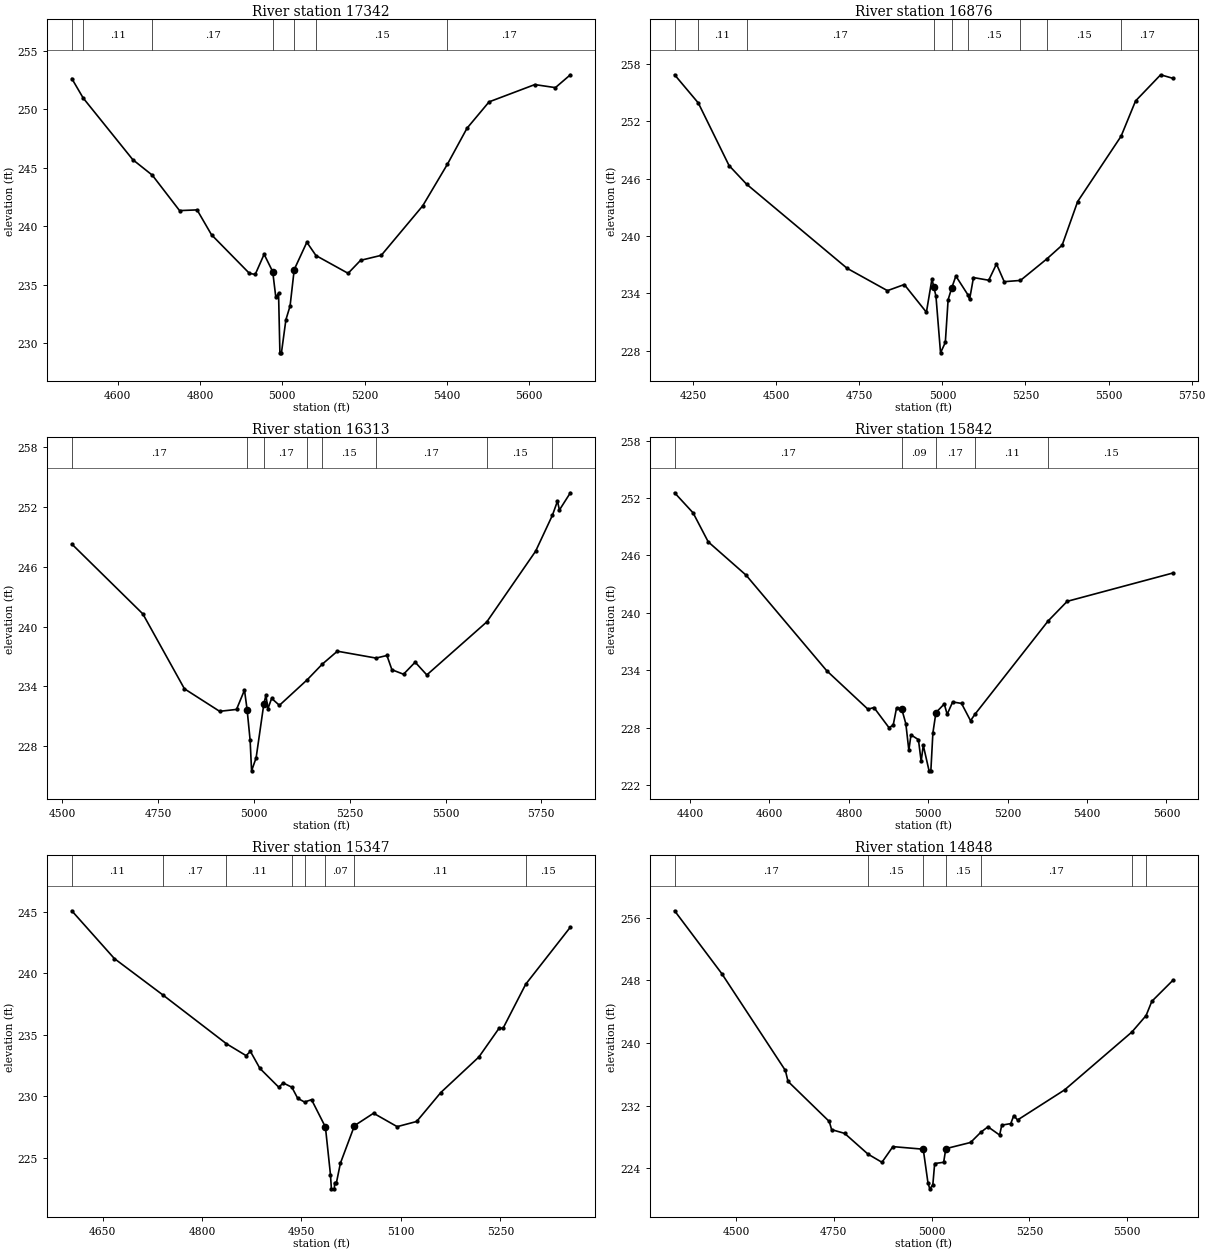
Type RM Length L Ch R = 1 ,17342   ,466,466,466
BEGIN DESCRIPTION:
LAKE CREEK TRIBUTARY NO. 18 35.0
END DESCRIPTION:
XS GIS Cut Line= 3
      3739967.84     10098661.08      3740309.72     10098279.15
      3740221.32     10097584.95
#Sta/Elev= 30
  4488.1  252.65  4515.8  250.98  4636.5   245.7    4684  244.37  4750.2  241.34
  4792.8   241.4  4827.9  239.27  4919.9  235.97  4934.1  235.87  4955.8   237.6
  4976.7  236.11  4984.2  233.93  4990.9  234.26  4994.2  229.16  4997.9  229.16
  5008.8     232  5018.9  233.17    5029  236.29  5059.7  238.63  5081.9  237.49
    5160  235.97  5190.3  237.08  5240.7  237.51  5341.5  241.75  5401.5  245.31
  5449.1  248.39  5502.8  250.65    5614  252.13  5664.1  251.87  5700.5  252.97
#Mann= 7 ,-1 , 0
  4488.1     .17       0  4515.8     .11       0    4684     .17       0
  4976.7     .09       0    5029     .17       0  5081.9     .15       0
  5401.5     .17       0
Bank Sta=4976.7,5029
XS Rating Curve= 0 ,0
Exp/Cntr=0.3,0.1

Type RM Length L Ch R = 1 ,16876   ,563,563,563
BEGIN DESCRIPTION:
LAKE CREEK TRIBUTARY NO. 18 34.0
END DESCRIPTION:
XS GIS Cut Line= 3
      3739917.84     10098761.08      3740640.45     10098391.13
      3740917.84     10097761.09
#Sta/Elev= 30
  4194.2  256.87  4265.5  253.92    4358  247.37  4410.7  245.42  4713.3  236.61
  4834.6  234.27  4885.3  234.91  4951.9  232.01  4968.5  235.48  4974.1  234.68
  4980.6  233.69  4994.4  227.76  5008.8  228.85  5017.2  233.32  5027.9  234.54
  5040.5   235.8  5076.8  233.83  5081.8  233.35  5093.5  235.64  5139.4  235.36
  5162.7  237.06    5186  235.21  5234.8  235.34  5313.8  237.58  5360.3  239.03
    5407   243.6  5537.7  250.44  5581.2  254.13  5656.7  256.87  5694.4  256.49
#Mann= 9 ,-1 , 0
  4194.2     .17       0  4265.5     .11       0  4410.7     .17       0
  4974.1     .09       0  5027.9     .17       0  5076.8     .15       0
  5234.8     .17       0  5313.8     .15       0  5537.7     .17       0
Bank Sta=4974.1,5027.9
XS Rating Curve= 0 ,0
Exp/Cntr=0.3,0.1

Type RM Length L Ch R = 1 ,16313   ,471,471,471
BEGIN DESCRIPTION:
LAKE CREEK TRIBUTARY NO. 18 33.0
END DESCRIPTION:
XS GIS Cut Line= 3
      3740767.87     10099061.05       3741047.8     10098676.56
      3740917.85     10097861.05
#Sta/Elev= 30
  4524.4  248.29  4709.9  241.28  4818.4  233.77  4910.3  231.51  4954.4   231.7
  4975.2  233.64    4982  231.69  4989.9  228.62  4993.7  225.54  5005.6  226.85
  5025.8  232.28  5031.2  233.12  5036.2  231.76  5046.1  232.81  5066.3  232.11
  5138.8  234.67  5177.9  236.23  5217.6  237.54  5318.5  236.85    5347  237.11
    5360  235.68  5390.3  235.23  5420.7  236.44  5451.1  235.16  5607.7  240.48
  5735.1  247.57    5779  251.18  5792.2   252.6  5797.2   251.7  5825.8  253.43
#Mann= 8 ,-1 , 0
  4524.4     .17       0    4982     .09       0  5025.8     .17       0
  5138.8     .11       0  5177.9     .15       0  5318.5     .17       0
  5607.7     .15       0    5779     .17       0
Bank Sta=4982,5025.8
XS Rating Curve= 0 ,0
Exp/Cntr=0.3,0.1

Type RM Length L Ch R = 1 ,15842   ,495,495,495
BEGIN DESCRIPTION:
LAKE CREEK TRIBUTARY NO. 18 32.0
END DESCRIPTION:
XS GIS Cut Line= 3
      3742017.85     10098761.07      3741414.46     10098550.73
      3741072.81     10098037.07
#Sta/Elev= 30
    4361  252.54  4407.6  250.44  4445.7  247.41    4541  243.93  4744.1  233.94
  4848.1  229.91  4863.1  230.09  4901.1  227.98  4911.7  228.26    4920  230.03
  4932.9  229.98  4943.5  228.39  4951.1  225.61  4956.4  227.23  4975.2  226.73
  4982.1  224.46  4987.4  226.14    5002  223.47  5006.5  223.47  5011.6  227.42
  5019.3  229.56  5040.3  230.46  5047.6  229.38  5061.4  230.67  5083.7  230.52
  5106.5  228.71  5117.3  229.37  5302.1  239.15  5349.9  241.19  5616.9  244.16
#Mann= 5 ,-1 , 0
    4361     .17       0  4932.9     .09       0  5019.3     .17       0
  5117.3     .11       0  5302.1     .15       0
Bank Sta=4932.9,5019.3
XS Rating Curve= 0 ,0
Exp/Cntr=0.3,0.1

Type RM Length L Ch R = 1 ,15347   ,499,499,499
BEGIN DESCRIPTION:
LAKE CREEK TRIBUTARY NO. 18 31.0
END DESCRIPTION:
XS GIS Cut Line= 3
      3741967.86     10098461.08      3741667.32      10098202.6
      3741367.83     10098011.06
#Sta/Elev= 30
  4603.6  245.08  4667.8   241.2  4740.6  238.26  4836.9  234.28  4866.4  233.32
    4873  233.66  4887.3  232.28  4915.8  230.75  4922.4   231.1  4935.5  230.75
  4944.3  229.85  4954.6  229.55  4965.2  229.74  4986.1  227.52  4993.7  223.66
  4995.1   222.5  4999.6   222.5    5000     223  5002.7     223  5008.7  224.58
  5029.9  227.63  5058.7  228.64  5094.3  227.55  5123.7  227.97  5160.1  230.32
  5217.6  233.21  5248.1  235.55    5254  235.54  5288.2  239.12  5355.5  243.75
#Mann= 8 ,-1 , 0
  4603.6     .11       0  4740.6     .17       0  4836.9     .11       0
  4935.5     .17       0  4954.6     .11       0  4986.1     .07       0
  5029.9     .11       0  5288.2     .15       0
Bank Sta=4986.1,5029.9
XS Rating Curve= 0 ,0
Exp/Cntr=0.3,0.1

Type RM Length L Ch R = 1 ,14848   ,496,496,496
BEGIN DESCRIPTION:
LAKE CREEK TRIBUTARY NO. 18 30.0
END DESCRIPTION:
XS GIS Cut Line= 3
      3742467.85     10098061.07      3741878.74     10097769.99
      3741317.82     10097511.06
#Sta/Elev= 30
  4342.9  256.89  4463.5  248.87  4626.2   236.5  4632.9  235.11  4738.4  229.99
  4744.4  228.95  4777.7  228.47  4837.5  225.82  4873.1  224.78  4901.1  226.78
  4978.7  226.45  4990.8  222.15  4995.4  221.39  5003.2  221.89  5007.9  224.62
  5030.9  224.78  5036.4  226.52  5099.7  227.31  5126.3  228.63  5144.2  229.31
    5174  228.26  5179.5  229.52  5202.5  229.72  5210.2  230.74  5219.9  230.18
  5340.1  234.02  5512.2  241.41  5548.5  243.51  5563.2  245.33  5617.8  248.05
#Mann= 7 ,-1 , 0
  4342.9     .17       0  4837.5     .15       0  4978.7     .09       0
  5036.4     .15       0  5126.3     .17       0  5512.2     .11       0
  5548.5     .17       0
Bank Sta=4978.7,5036.4
XS Rating Curve= 0 ,0
Exp/Cntr=0.3,0.1

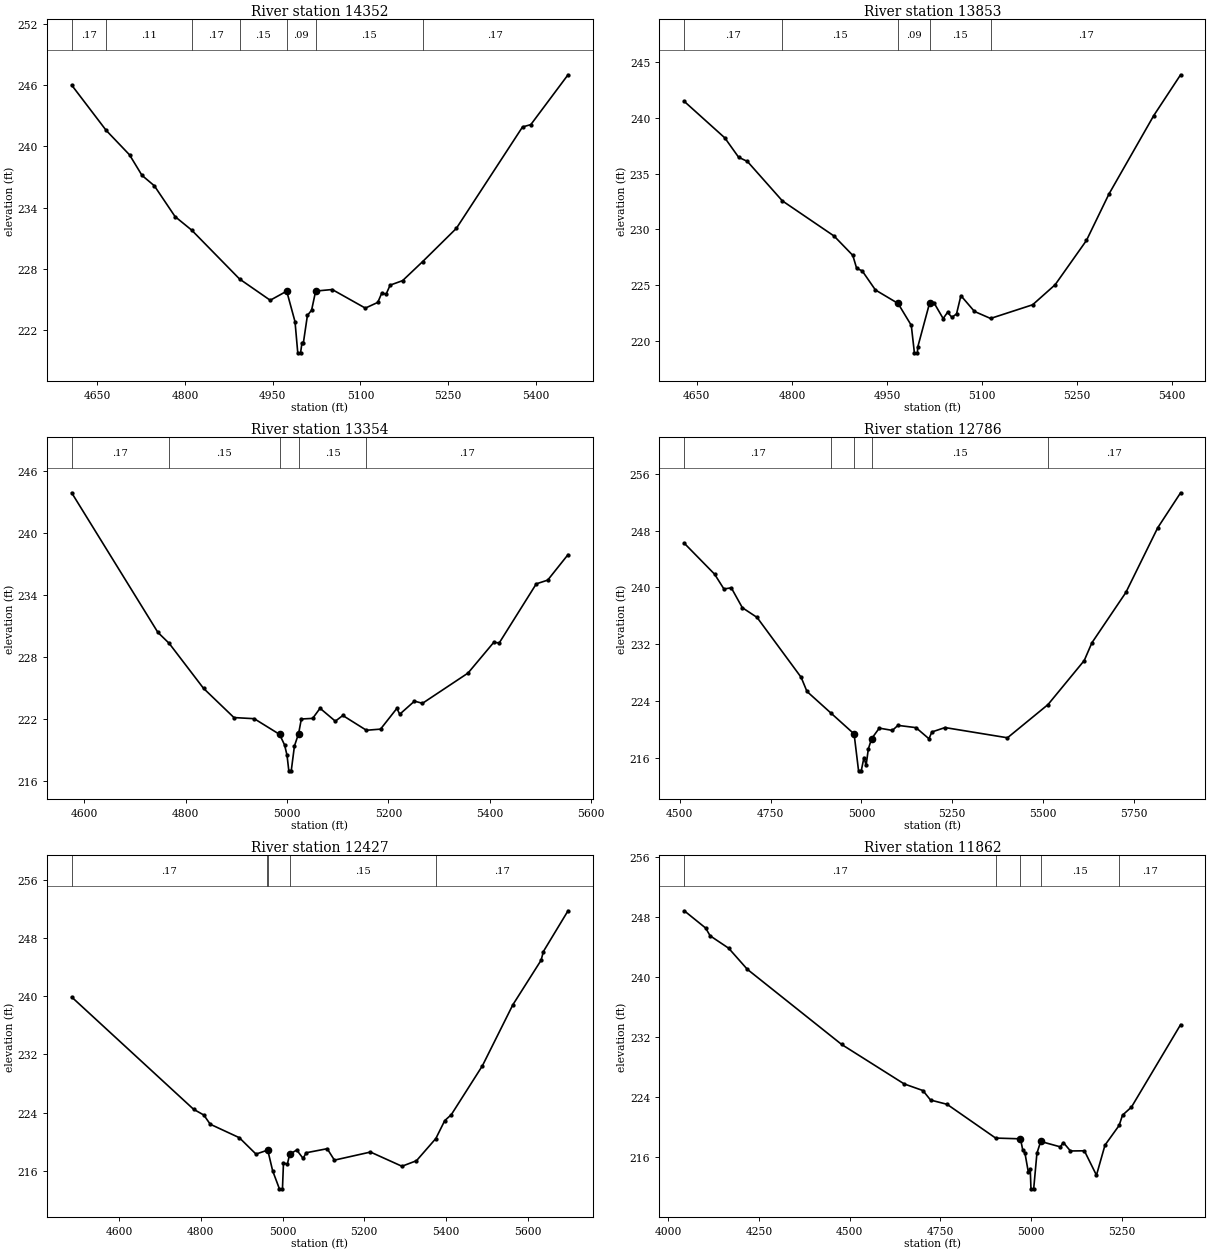
Type RM Length L Ch R = 1 ,14352   ,499,499,499
BEGIN DESCRIPTION:
LAKE CREEK TRIBUTARY NO. 18 29.0
END DESCRIPTION:
XS GIS Cut Line= 3
      3742467.82     10097711.04      3742186.12       10097436.
      3741867.88      10097111.1
#Sta/Elev= 30
  4606.3     246  4665.2  241.57  4705.2  239.17  4726.5  237.16  4747.6  236.14
  4783.1  233.12  4811.4   231.8  4893.3  227.01  4945.7  224.93  4973.9  225.82
  4988.1  222.83  4992.8  219.78  4997.6  219.78  4999.9  220.72  5002.3  220.72
  5009.3  223.45  5016.4  223.95  5023.4  225.83  5051.7  225.98  5108.3  224.16
  5129.6  224.72  5136.6  225.66  5143.7  225.51  5150.7  226.41    5172  226.85
  5206.2  228.71  5263.9  231.97    5377   241.9  5391.2  242.13  5454.8  247.01
#Mann= 7 ,-1 , 0
  4606.3     .17       0  4665.2     .11       0  4811.4     .17       0
  4893.3     .15       0  4973.9     .09       0  5023.4     .15       0
  5206.2     .17       0
Bank Sta=4973.9,5023.4
XS Rating Curve= 0 ,0
Exp/Cntr=0.3,0.1

Type RM Length L Ch R = 1 ,13853   ,499,499,499
BEGIN DESCRIPTION:
LAKE CREEK TRIBUTARY NO. 18 28.0
END DESCRIPTION:
XS GIS Cut Line= 3
      3742717.88     10097411.11      3742504.42     10097109.02
      3742217.85     10096811.07
#Sta/Elev= 30
  4630.1   241.5  4694.1  238.22  4715.9  236.48  4729.8   236.1  4784.9  232.56
  4866.5   229.4  4896.1  227.66  4902.2  226.49  4910.9  226.27  4931.8  224.55
  4967.5  223.34  4988.4  221.37  4993.3   218.9  4998.1   218.9  4998.5   219.4
  5017.3  223.38  5024.5  223.37  5038.7  221.98  5045.6  222.54  5052.6  222.09
  5059.8   222.4  5066.7  224.04  5088.1  222.62  5113.5  221.99  5179.9  223.22
  5215.4  225.02  5264.8     229  5300.3  233.17  5371.1  240.23  5413.4  243.89
#Mann= 5 ,-1 , 0
  4630.1     .17       0  4784.9     .15       0  4967.5     .09       0
  5017.3     .15       0  5113.5     .17       0
Bank Sta=4967.5,5017.3
XS Rating Curve= 0 ,0
Exp/Cntr=0.3,0.1

Type RM Length L Ch R = 1 ,13354   ,568,568,568
BEGIN DESCRIPTION:
LAKE CREEK TRIBUTARY NO. 18 27.0
END DESCRIPTION:
XS GIS Cut Line= 3
      3742817.85     10097461.08      3742820.72     10097036.39
      3742575.35     10096539.58
#Sta/Elev= 30
  4575.3   243.9  4745.3  230.38  4767.5  229.32  4835.3  224.96  4895.3  222.13
  4935.3  222.02  4985.3   220.5  4995.2  219.47    5000  218.47  5003.5  216.97
  5008.3  216.97  5014.6  219.38  5022.8220.5791  5028.2  221.99  5050.5  222.05
  5065.1  223.03  5095.2  221.78    5110  222.33  5156.5   220.9  5184.4  221.01
  5216.6  223.02  5222.2  222.45  5251.3  223.72  5267.1  223.51  5356.9  226.44
  5407.4   229.4  5418.6  229.37  5491.5  235.08    5514  235.44  5554.1  237.91
#Mann= 5 ,-1 , 0
  4575.3     .17       0  4767.5     .15       0  4985.3     .09       0
  5022.8     .15       0  5156.5     .17       0
Bank Sta=4985.3,5022.8
XS Rating Curve= 0 ,0
Exp/Cntr=0.3,0.1

Type RM Length L Ch R = 1 ,12786   ,359,359,359
BEGIN DESCRIPTION:
LAKE CREEK TRIBUTARY NO. 18 26.0
END DESCRIPTION:
XS GIS Cut Line= 3
      3743219.87     10097709.07      3743296.26     10097226.41
      3743775.43      10096490.3
#Sta/Elev= 30
  4512.1  246.24  4595.6  241.88  4621.4  239.79  4641.7  239.95  4672.1  237.15
  4712.6  235.78  4834.1  227.33  4850.1  225.34  4916.2  222.29  4979.9  219.35
  4992.2  214.15  4999.6  214.15    5007  216.02    5013  214.94  5019.1  217.23
  5028.1  218.68  5049.2  220.17  5085.4  219.85  5100.6  220.56  5150.3  220.24
  5186.1  218.67  5194.1  219.63  5230.3  220.25  5402.3  218.81  5513.9  223.49
  5613.7   229.7  5634.8   232.2  5728.4   239.3    5816  248.41  5879.1  253.35
#Mann= 5 ,-1 , 0
  4512.1     .17       0  4916.2     .15       0  4979.9     .09       0
  5028.1     .15       0  5513.9     .17       0
Bank Sta=4979.9,5028.1
XS Rating Curve= 0 ,0
Exp/Cntr=0.3,0.1

Type RM Length L Ch R = 1 ,12427   ,565,565,565
BEGIN DESCRIPTION:
LAKE CREEK TRIBUTARY NO. 18 25.0
END DESCRIPTION:
XS GIS Cut Line= 3
      3743532.38     10097754.17      3743629.59     10097243.77
      3743917.83     10096611.12
#Sta/Elev= 30
    4484  239.88  4782.4  224.47  4807.5  223.68  4823.1  222.42  4894.3  220.57
  4935.1  218.32  4961.2  218.82    4964  218.84  4975.8  216.04  4992.4  213.55
  4999.9  213.55  5002.4  217.14  5011.7   216.9  5017.5   218.3  5034.8  218.88
  5050.5  217.72  5057.8   218.5  5109.4  219.06    5127  217.49  5215.3   218.6
  5292.3  216.65  5327.9  217.41  5375.3  220.46    5397  222.91  5413.1  223.73
  5489.2  230.44  5563.8  238.82  5632.9  244.93  5638.5  246.13  5698.8  251.72
#Mann= 5 ,-1 , 0
    4484     .17       0  4961.2     .15       0    4964     .09       0
  5017.5     .15       0  5375.3     .17       0
Bank Sta=4964,5017.5
XS Rating Curve= 0 ,0
Exp/Cntr=0.3,0.1

Type RM Length L Ch R = 1 ,11862   ,499,499,499
BEGIN DESCRIPTION:
LAKE CREEK TRIBUTARY NO. 18 24.0
END DESCRIPTION:
XS GIS Cut Line= 3
      3743617.87     10098011.04       3744134.8     10097206.97
      3744017.85     10096811.08
#Sta/Elev= 30
  4044.1  248.86  4103.2  246.55  4115.4  245.52  4166.6  243.86  4218.1  241.04
  4478.3     231  4650.7  225.73  4702.2  224.85  4723.3  223.58  4768.9  223.01
  4902.8   218.5  4971.3   218.4  4977.6  216.89  4983.5  216.51  4992.8  213.99
  4998.2  214.35  5000.2  211.72  5007.7  211.72  5016.6  216.47    5027  218.05
  5080.9  217.33  5089.6   217.9    5109  216.78  5147.5   216.8  5180.8  213.54
  5204.3  217.56  5243.3  220.19  5252.6  221.56  5277.3  222.64  5412.8  233.65
#Mann= 5 ,-1 , 0
  4044.1     .17       0  4902.8     .15       0  4971.3     .09       0
    5027     .15       0  5243.3     .17       0
Bank Sta=4971.3,5027
XS Rating Curve= 0 ,0
Exp/Cntr=0.3,0.1

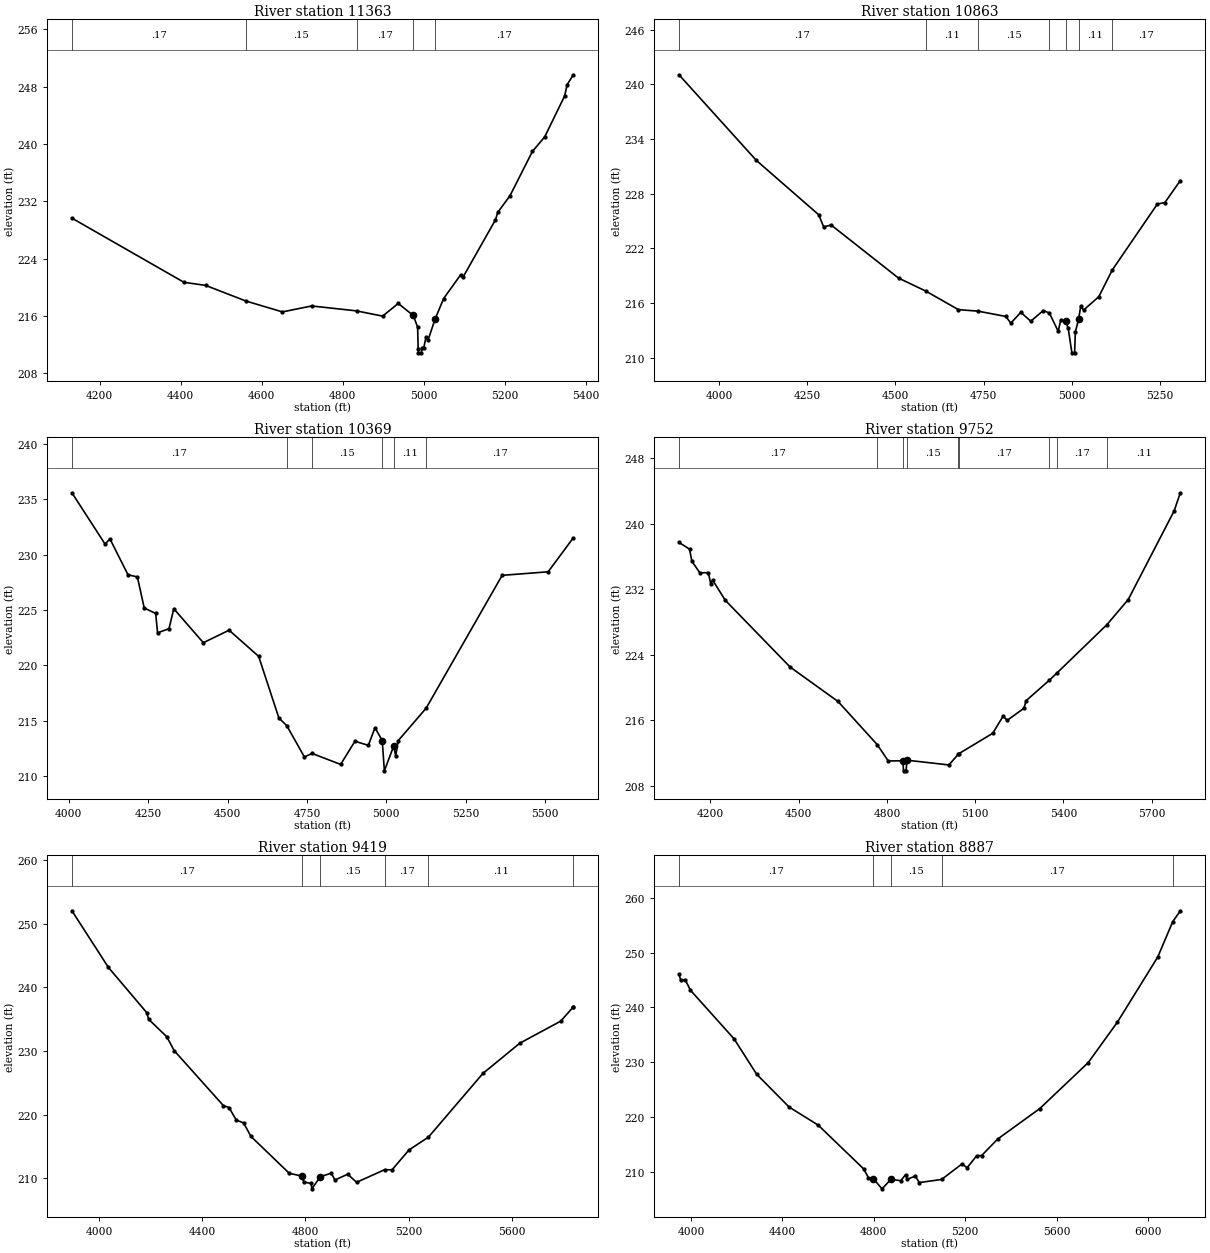
Type RM Length L Ch R = 1 ,11363   ,500,500,500
BEGIN DESCRIPTION:
LAKE CREEK TRIBUTARY NO. 18 23.0
END DESCRIPTION:
XS GIS Cut Line= 3
      3744067.87     10097761.03      3744396.41     10096956.96
      3744267.85     10096611.08
#Sta/Elev= 30
  4131.4  229.64  4407.9  220.69  4461.3  220.26  4561.3  218.07  4651.1  216.56
  4723.1  217.39  4834.4   216.7  4898.3  215.97  4936.9  217.74    4974  216.06
  4984.8  214.43  4986.1  211.35  4986.6  210.85  4994.2  210.85  4995.3  211.56
    5000  211.56  5005.6  213.07  5010.9  212.69  5027.6  215.52    5049  218.43
  5091.3  221.76  5096.6  221.39    5177  229.41  5182.4  230.43  5212.7  232.76
  5268.1  238.94  5298.5  240.98  5347.7  246.69  5353.8  248.25    5369  249.64
#Mann= 5 ,-1 , 0
  4131.4     .17       0  4561.3     .15       0  4834.4     .17       0
    4974     .09       0  5027.6     .17       0
Bank Sta=4974,5027.6
XS Rating Curve= 0 ,0
Exp/Cntr=0.3,0.1

Type RM Length L Ch R = 1 ,10863   ,494,494,494
BEGIN DESCRIPTION:
LAKE CREEK TRIBUTARY NO. 18 22.0
END DESCRIPTION:
XS GIS Cut Line= 3
      3743967.86     10098061.06      3744750.37     10097269.16
      3744917.87     10097011.04
#Sta/Elev= 30
  3886.7  241.05  4105.9  231.66  4282.6   225.7  4296.8  224.36    4318  224.57
  4508.9  218.75  4585.4  217.34  4678.6  215.29  4734.9  215.12    4813  214.54
  4827.2  213.81  4855.5  214.99  4883.8  214.02  4919.1  215.19  4936.5  214.92
  4961.5  212.91  4968.6  214.13  4982.8  214.03  4989.8  213.24  5000.3  210.55
    5008  210.55  5010.1  212.85  5019.3  214.22  5025.2  215.65  5033.5  215.24
  5076.6  216.71  5114.8  219.64  5242.7  226.88  5263.8  227.03  5307.7  229.45
#Mann= 7 ,-1 , 0
  3886.7     .17       0  4585.4     .11       0  4734.9     .15       0
  4936.5     .11       0  4982.8     .07       0  5019.3     .11       0
  5114.8     .17       0
Bank Sta=4982.8,5019.3
XS Rating Curve= 0 ,0
Exp/Cntr=0.3,0.1

Type RM Length L Ch R = 1 ,10369   ,617,617,617
BEGIN DESCRIPTION:
LAKE CREEK TRIBUTARY NO. 18 21.0
END DESCRIPTION:
XS GIS Cut Line= 4
      3744226.78     10098184.77      3745048.76     10097633.54
      3745348.34     10097396.55      3745372.65     10097191.67
#Sta/Elev= 30
  4010.3  235.58  4114.8  230.94  4129.8  231.43  4186.8  228.18  4216.3  227.99
  4237.9  225.18  4273.9  224.69  4279.9  222.94  4315.9  223.32  4330.9  225.12
  4423.9  222.05    4505  223.18    4598  220.82  4661.8  215.25  4686.2  214.58
  4742.1  211.74    4766  212.06  4856.1  211.07  4901.1  213.16  4943.2  212.79
  4964.2  214.38    4987  213.22  4993.7  210.49  5023.1  212.73  5029.4  211.83
  5037.1  213.21  5125.1  216.14  5364.4  228.13  5509.3  228.45  5588.3  231.51
#Mann= 6 ,-1 , 0
  4010.3     .17       0  4686.2     .11       0    4766     .15       0
    4987     .07       0  5023.1     .11       0  5125.1     .17       0
Bank Sta=4987,5023.1
XS Rating Curve= 0 ,0
Exp/Cntr=0.3,0.1

Type RM Length L Ch R = 1 ,9752    ,333,333,333
BEGIN DESCRIPTION:
LAKE CREEK TRIBUTARY NO. 18 20.0
END DESCRIPTION:
XS GIS Cut Line= 3
      3744643.46     10098587.54      3745344.87     10098014.61
      3745867.87     10097411.05
#Sta/Elev= 30
  4093.1  237.73    4129  236.91  4136.9  235.43  4164.2  234.01  4192.9  234.04
  4200.8  232.69  4207.3  233.14  4250.4  230.66  4470.8   222.5  4633.7  218.29
  4766.8  213.02  4804.6  211.01  4854.2  211.05  4856.4  209.81  4864.8  209.81
  4868.5  211.11  5010.5  210.53  5042.3  211.83  5043.7  211.89  5159.6   214.4
  5194.8  216.49    5209  215.98    5266  217.47  5272.6  218.37  5351.5  220.87
  5378.4  221.79  5547.3  227.66  5620.2  230.75    5776  241.56  5797.4   243.8
#Mann= 9 ,-1 , 0
  4093.1     .17       0  4766.8     .15       0  4854.2     .09       0
  4868.5     .15       0  5042.3     .11       0  5043.7     .17       0
  5351.5     .11       0  5378.4     .17       0  5547.3     .11       0
Bank Sta=4854.2,4868.5
XS Rating Curve= 0 ,0
Exp/Cntr=0.3,0.1

Type RM Length L Ch R = 1 ,9419    ,532,532,532
BEGIN DESCRIPTION:
LAKE CREEK TRIBUTARY NO. 18 19.0
END DESCRIPTION:
XS GIS Cut Line= 3
      3744717.87     10099111.05      3745462.93      10098302.8
      3745942.11     10097608.34
#Sta/Elev= 30
  3895.4  252.07  4036.9  243.15  4185.4  236.04  4192.8  234.98  4263.1  232.25
  4291.5  230.07  4482.6   221.4  4504.1  221.11  4532.5  219.13  4560.8  218.68
    4589  216.57  4737.8  210.75  4787.1  210.32  4793.9  209.37  4822.3  209.17
  4825.4  208.31    4858  210.23  4900.5  210.77  4914.7   209.7    4964  210.61
  4998.8  209.34  5107.2  211.32  5135.9   211.3  5201.5  214.42  5277.1  216.45
  5488.2  226.47  5631.5  231.24  5789.7   234.7  5837.4  236.88  5838.4  236.88
#Mann= 6 ,-1 , 0
  3895.4     .17       0  4787.1     .09       0    4858     .15       0
  5107.2     .17       0  5277.1     .11       0  5837.4     .17       0
Bank Sta=4787.1,4858
XS Rating Curve= 0 ,0
Exp/Cntr=0.3,0.1

Type RM Length L Ch R = 1 ,8887    ,499,499,499
BEGIN DESCRIPTION:
LAKE CREEK TRIBUTARY NO. 18 18.0
END DESCRIPTION:
XS GIS Cut Line= 3
      3744967.84     10099311.08      3745754.18      10098611.8
      3746567.86     10097811.06
#Sta/Elev= 30
  3947.7  246.11  3954.8  245.01  3975.7     245  3997.5  243.16  4188.6  234.26
  4287.6  227.79  4429.5   221.8  4556.9  218.49  4755.1  210.52  4776.8  208.89
  4797.7  208.72  4836.1  206.85  4875.5   208.6  4918.1  208.33    4939  209.42
  4946.6   208.6  4981.7  209.18  4999.1     208  5096.8  208.56    5187  211.43
  5208.2  210.68  5250.6  212.91  5271.8  212.92  5342.5  215.96  5526.3  221.51
  5738.5  229.92  5865.8  237.29  6042.6   249.2  6108.1  255.65  6141.6  257.66
#Mann= 5 ,-1 , 0
  3947.7     .17       0  4797.7     .09       0  4875.5     .15       0
  5096.8     .17       0  6108.1     .11       0
Bank Sta=4797.7,4875.5
XS Rating Curve= 0 ,0
Exp/Cntr=0.3,0.1