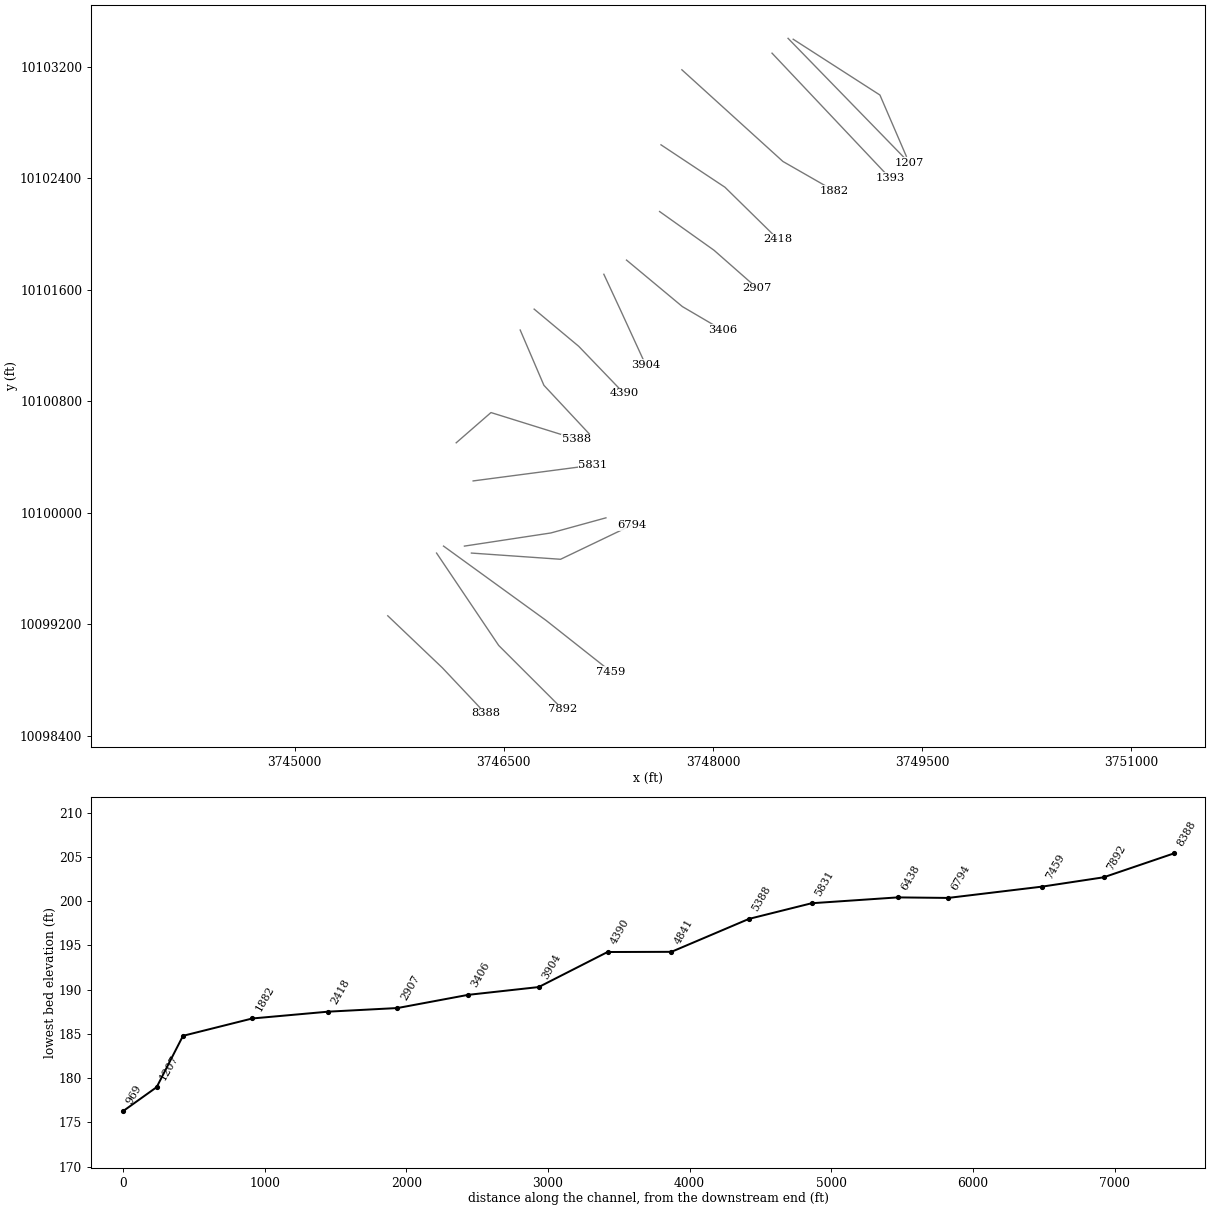
HEC-RAS study LAKE CREEK TRIBUTARY NO 18.prj: LAKE CREEK TRIBUTARY NO 18 Base Level Engineering

--- LAKE CREEK TRIBUTARY NO 18.g01 (geometry) --- (continued)

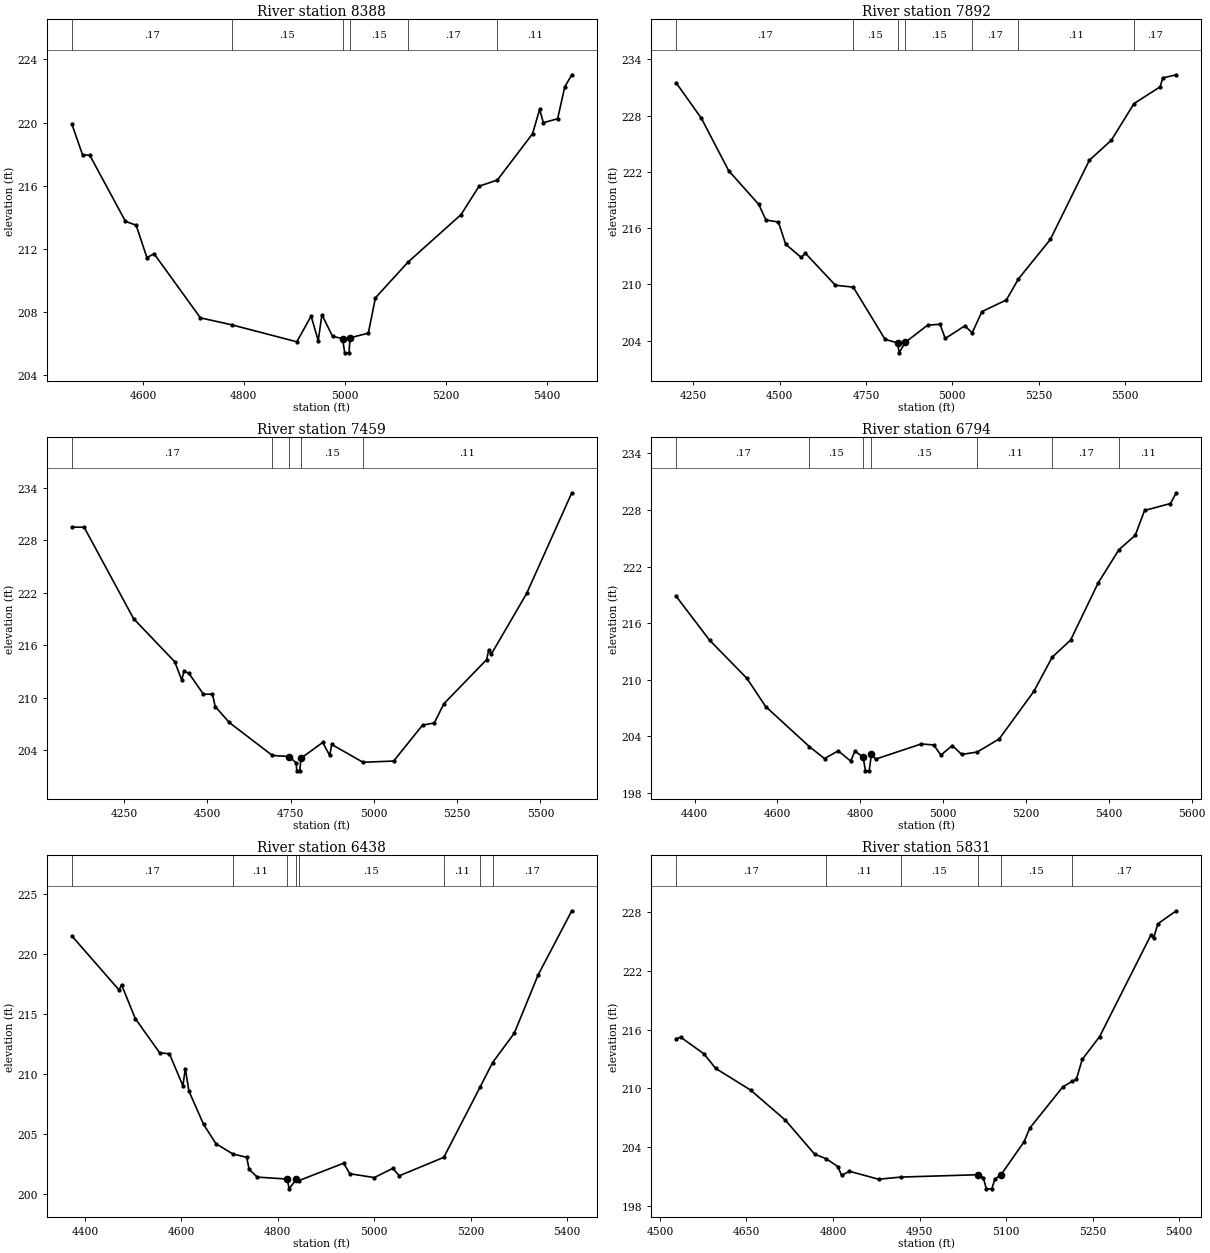
Type RM Length L Ch R = 1 ,8388    ,496,496,496
BEGIN DESCRIPTION:
LAKE CREEK TRIBUTARY NO. 18 17.0
END DESCRIPTION:
XS GIS Cut Line= 3
      3745667.83      10099261.1      3746059.28      10098888.1
      3746367.83     10098561.09
#Sta/Elev= 30
  4459.3  219.91  4480.6  217.94  4494.7  217.93  4565.5  213.73  4586.6  213.49
    4608  211.43  4622.1  211.68  4713.9  207.61  4775.8  207.17  4904.9  206.09
  4933.2  207.72  4947.3  206.16  4954.6  207.81  4975.6  206.44  4995.6  206.29
  4999.7  205.39  5008.3  205.39 5010.41206.3424  5046.5  206.64  5060.6  208.88
  5125.3  211.15  5230.2  214.16  5265.8  215.96  5302.1  216.35  5371.8  219.29
  5385.9  220.84  5393.2  219.99  5421.5  220.24  5435.7  222.27  5449.6  223.03
#Mann= 6 ,-1 , 0
  4459.3     .17       0  4775.8     .15       0  4995.6     .09       0
 5010.41     .15       0  5125.3     .17       0  5302.1     .11       0
Bank Sta=4995.6,5010.41
XS Rating Curve= 0 ,0
Exp/Cntr=0.3,0.1

Type RM Length L Ch R = 1 ,7892    ,433,433,433
BEGIN DESCRIPTION:
LAKE CREEK TRIBUTARY NO. 18 16.0
END DESCRIPTION:
XS GIS Cut Line= 3
      3746017.83     10099711.11      3746463.86     10099048.07
      3746922.59      10098590.1
#Sta/Elev= 30
  4200.9  231.47  4273.3  227.72  4352.4  222.12  4439.4  218.53  4460.4  216.86
  4496.4  216.64  4517.4  214.28  4562.3  212.87  4574.6  213.31  4661.4   209.9
  4713.1   209.7  4805.3  204.12  4841.3  203.76    4846  202.69  4863.8  203.81
  4928.3  205.64  4964.3  205.74  4979.3  204.22  5036.1  205.57  5057.4  204.82
  5085.6  207.09  5156.3  208.33  5191.4  210.58  5283.5  214.78  5396.7  223.24
  5460.3  225.37  5525.9  229.28  5601.7  231.07  5608.8  232.01  5648.2  232.35
#Mann= 7 ,-1 , 0
  4200.9     .17       0  4713.1     .15       0  4841.3     .09       0
  4863.8     .15       0  5057.4     .17       0  5191.4     .11       0
  5525.9     .17       0
Bank Sta=4841.3,4863.8
XS Rating Curve= 0 ,0
Exp/Cntr=0.3,0.1

Type RM Length L Ch R = 1 ,7459    ,665,665,665
BEGIN DESCRIPTION:
LAKE CREEK TRIBUTARY NO. 18 15.0
END DESCRIPTION:
XS GIS Cut Line= 3
      3746067.83     10099761.09      3746803.21     10099228.15
      3747267.82      10098861.1
#Sta/Elev= 30
  4093.8  229.53  4130.6  229.52  4279.1  219.05  4402.6  214.12  4423.6  212.02
  4429.8  213.01  4444.5  212.83  4488.6  210.41  4515.6  210.41  4524.1     209
  4565.9  207.18  4695.6   203.4  4746.1  203.28  4766.9  202.55  4768.8  201.64
  4777.5  201.64  4781.6  203.09  4846.6  204.89  4867.5   203.4  4873.6  204.66
  4967.4  202.62  5059.5  202.76  5146.1  206.87  5181.4  207.12  5210.2  209.32
  5338.5  214.37  5344.9  215.51    5352  214.96  5458.7  221.95  5594.1  233.46
#Mann= 5 ,-1 , 0
  4093.8     .17       0  4695.6     .15       0  4746.1     .07       0
  4781.6     .15       0  4967.4     .11       0
Bank Sta=4746.1,4781.6
XS Rating Curve= 0 ,0
Exp/Cntr=0.3,0.1

Type RM Length L Ch R = 1 ,6794    ,356,356,356
BEGIN DESCRIPTION:
LAKE CREEK TRIBUTARY NO. 18 14.0
END DESCRIPTION:
XS GIS Cut Line= 3
      3746267.83     10099711.07      3746907.37     10099666.52
      3747417.83     10099911.06
#Sta/Elev= 30
  4355.8  218.83    4436   214.2  4526.2  210.16  4571.5  207.17  4677.2  202.92
  4713.6  201.66  4746.8  202.48  4776.8  201.39  4786.9  202.44  4806.9  201.81
  4812.4  200.36  4821.5  200.36    4827  202.16    4837   201.6  4947.3  203.21
  4977.3   203.1  4994.6  202.03  5022.1  203.04  5044.7   202.1  5082.1  202.35
  5135.4  203.74  5219.2  208.79  5263.2  212.39  5307.9  214.22  5374.4  220.27
  5424.4  223.78  5463.7   225.3  5486.4  227.94  5548.8  228.67  5562.9  229.81
#Mann= 7 ,-1 , 0
  4355.8     .17       0  4677.2     .15       0  4806.9     .09       0
    4827     .15       0  5082.1     .11       0  5263.2     .17       0
  5424.4     .11       0
Bank Sta=4806.9,4827
XS Rating Curve= 0 ,0
Exp/Cntr=0.3,0.1

Type RM Length L Ch R = 1 ,6438    ,607,607,607
BEGIN DESCRIPTION:
LAKE CREEK TRIBUTARY NO. 18 13.0
END DESCRIPTION:
XS GIS Cut Line= 3
      3746217.82     10099761.07      3746837.93     10099855.32
      3747232.86     10099963.82
#Sta/Elev= 30
  4372.8  221.54  4470.8  217.02  4475.8  217.47  4504.3  214.64  4554.9  211.78
  4575.1   211.7  4603.1  209.03  4608.1  210.46  4615.6  208.58  4645.9  205.81
  4671.8  204.18  4706.9  203.33  4735.4  203.05  4740.4  202.05  4757.2   201.4
 4819.56201.2374  4823.3  200.42  4838.1  201.21  4843.6  201.11  4936.4  202.56
  4949.4  201.68    5000  201.36  5038.4  202.13  5051.8  201.51  5144.1  203.05
  5219.8  208.95  5245.4  210.97  5290.3  213.42  5339.8  218.29  5409.6  223.64
#Mann= 8 ,-1 , 0
  4372.8     .17       0  4706.9     .11       0 4819.56     .09       0
  4838.1     .11       0  4843.6     .15       0  5144.1     .11       0
  5219.8     .15       0  5245.4     .17       0
Bank Sta=4819.56,4838.1
XS Rating Curve= 0 ,0
Exp/Cntr=0.3,0.1

Type RM Length L Ch R = 1 ,5831    ,443,443,443
BEGIN DESCRIPTION:
LAKE CREEK TRIBUTARY NO. 18 12.0
END DESCRIPTION:
XS GIS Cut Line= 2
      3746280.24     10100228.59      3747139.56     10100341.43
#Sta/Elev= 30
  4528.4  215.09  4536.1  215.23  4576.4  213.53  4596.6  212.05  4657.1  209.84
  4717.6  206.76  4768.1   203.3  4788.3  202.83  4808.4  202.03  4814.9  201.14
  4828.6  201.55    4879  200.74  4917.5  200.96  5051.1   201.2  5060.5   200.9
  5065.9  199.76  5075.3  199.76  5080.7  200.76  5090.8  201.16  5131.1  204.55
  5141.2  205.96  5198.5  210.17  5214.5  210.72  5221.9  210.93    5232  212.96
  5262.3   215.3    5351  225.64    5356  225.38  5363.1   226.8  5395.1  228.13
#Mann= 6 ,-1 , 0
  4528.4     .17       0  4788.3     .11       0  4917.5     .15       0
  5051.1     .09       0  5090.8     .15       0  5214.5     .17       0
Bank Sta=5051.1,5090.8
XS Rating Curve= 0 ,0
Exp/Cntr=0.3,0.1

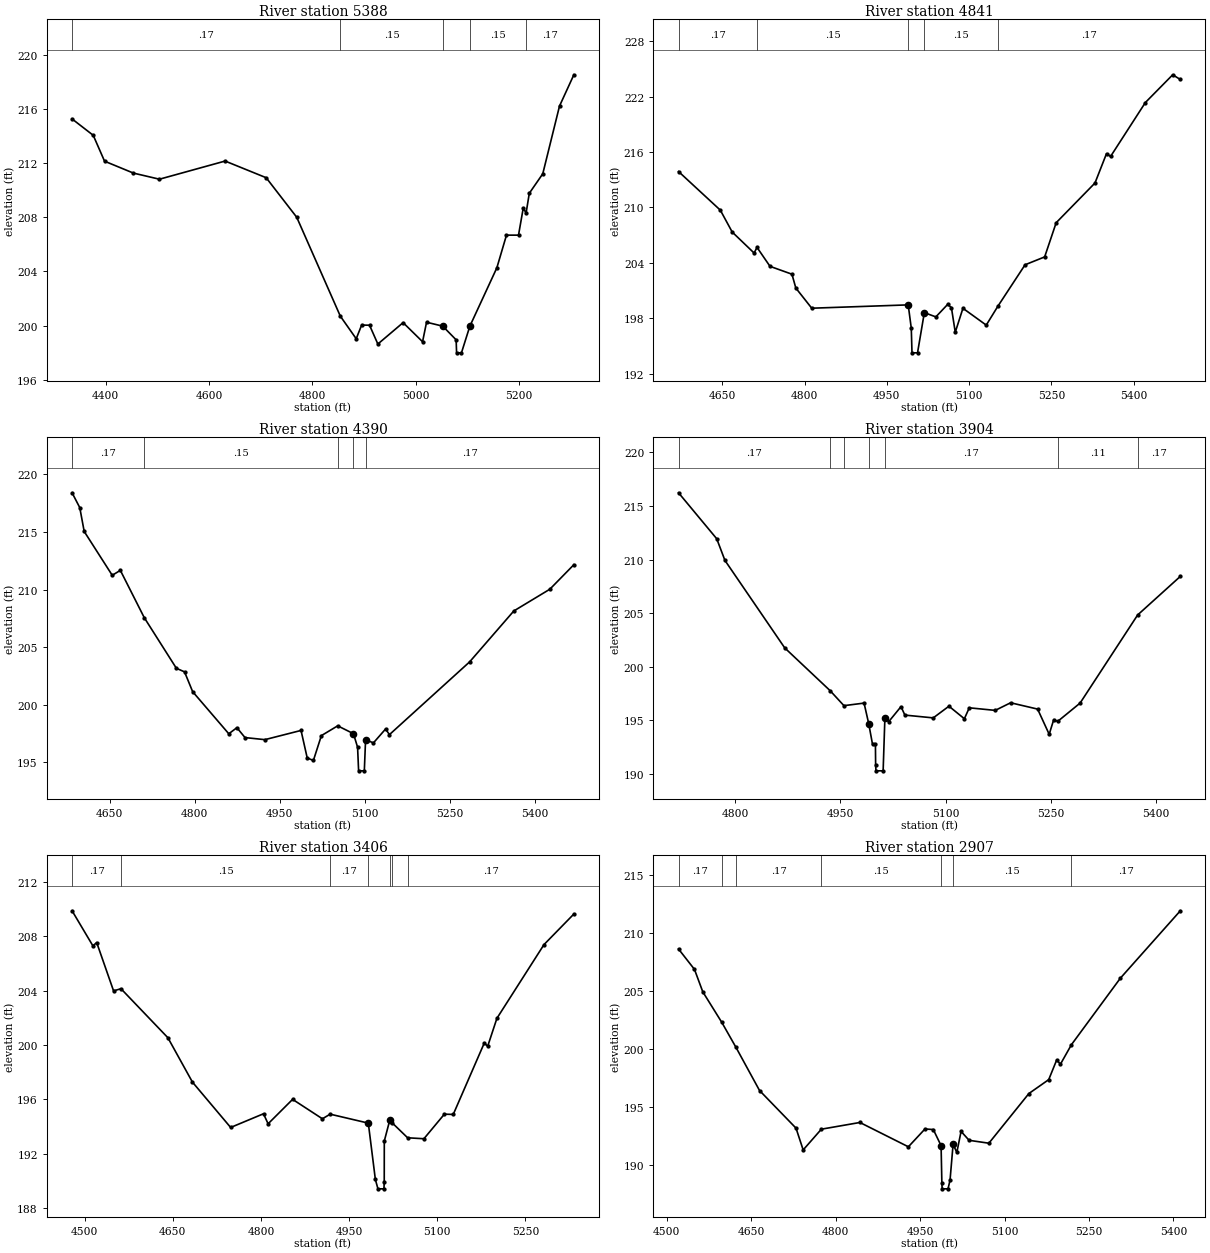
Type RM Length L Ch R = 1 ,5388    ,547,547,547
BEGIN DESCRIPTION:
LAKE CREEK TRIBUTARY NO. 18 11.0
END DESCRIPTION:
XS GIS Cut Line= 3
      3746158.66       10100502.      3746408.24     10100719.03
      3747020.19     10100528.07
#Sta/Elev= 30
  4334.8  215.26  4375.8  214.05  4397.7  212.14  4453.7  211.26    4504  210.81
  4631.2  212.15  4710.7  210.92  4769.9     208  4854.3   200.7  4885.1  199.03
  4895.6  200.04  4910.9  200.03    4927  198.64  4975.9  200.22  5013.6  198.81
  5021.3  200.25  5052.7  199.96  5078.6  198.95  5079.5  197.99  5088.9  197.99
  5105.1  199.95  5157.5  204.27  5176.1  206.68  5199.4  206.68  5208.6  208.68
  5214.1  208.31  5220.3  209.77  5246.4  211.21  5278.8  216.21  5306.6  218.52
#Mann= 5 ,-1 , 0
  4334.8     .17       0  4854.3     .15       0  5052.7     .09       0
  5105.1     .15       0  5214.1     .17       0
Bank Sta=5052.7,5105.1
XS Rating Curve= 0 ,0
Exp/Cntr=0.3,0.1

Type RM Length L Ch R = 1 ,4841    ,451,451,451
BEGIN DESCRIPTION:
LAKE CREEK TRIBUTARY NO. 18 10.0
END DESCRIPTION:
XS GIS Cut Line= 3
      3746617.84     10101311.09      3746788.01     10100914.35
      3747117.84     10100561.08
#Sta/Elev= 30
  4570.2  213.89  4646.4  209.71  4668.1  207.34    4708  205.07  4713.3  205.68
    4737  203.63    4777  202.78  4784.1  201.28  4813.1   199.1    4989  199.46
  4994.6  196.94  4995.9  194.27    5006  194.27  5018.4  198.62  5039.4  198.16
  5060.9  199.51  5067.8  199.16  5074.8   196.5  5088.8  199.09  5131.3  197.27
  5152.8  199.34  5202.1   203.8  5237.8  204.65  5258.8  208.35  5329.6  212.65
  5350.6  215.83    5358  215.52  5421.5  221.36  5471.3  224.36  5485.2  223.85
#Mann= 5 ,-1 , 0
  4570.2     .17       0  4713.3     .15       0    4989     .09       0
  5018.4     .15       0  5152.8     .17       0
Bank Sta=4989,5018.4
XS Rating Curve= 0 ,0
Exp/Cntr=0.3,0.1

Type RM Length L Ch R = 1 ,4390    ,486,486,486
BEGIN DESCRIPTION:
LAKE CREEK TRIBUTARY NO. 18 9.0
END DESCRIPTION:
XS GIS Cut Line= 3
      3746717.87     10101461.06      3747037.58     10101194.29
      3747362.84     10100856.11
#Sta/Elev= 30
  4583.4  218.41    4597  217.12  4604.8  215.05  4654.3  211.24  4668.6  211.67
  4710.8  207.56  4767.5  203.16  4781.9  202.85  4796.2  201.13    4860  197.47
  4874.3     198  4888.6  197.14  4923.7  196.96  4987.5  197.76  4998.4  195.37
  5009.3  195.15  5023.4  197.31  5052.2  198.16    5080  197.48  5087.3   196.3
  5089.1  194.25  5099.2  194.25  5101.4  196.95  5115.3  196.68  5136.6  197.88
  5143.6   197.4  5285.1  203.72    5363  208.14  5426.6  210.03    5469  212.16
#Mann= 5 ,-1 , 0
  4583.4     .17       0  4710.8     .15       0  5052.2     .17       0
    5080     .09       0  5101.4     .17       0
Bank Sta=5080,5101.4
XS Rating Curve= 0 ,0
Exp/Cntr=0.3,0.1

Type RM Length L Ch R = 1 ,3904    ,498,498,498
BEGIN DESCRIPTION:
LAKE CREEK TRIBUTARY NO. 18 8.0
END DESCRIPTION:
XS GIS Cut Line= 3
      3747217.84     10101711.09      3747336.32     10101456.39
      3747517.85     10101061.08
#Sta/Elev= 30
  4719.1  216.23  4773.6  211.94  4785.3  209.92  4870.6  201.76  4935.2  197.78
  4955.1  196.37  4983.8  196.61  4990.5  194.67  4995.9  192.75    5000  192.75
  5000.3  190.79  5000.8  190.29    5011  190.29  5013.5  195.21    5019  194.88
  5036.5  196.28    5042  195.49  5082.5  195.23  5104.9  196.32  5126.9  195.15
  5133.9  196.17  5170.9  195.93  5192.9  196.64  5231.4  196.05  5247.9   193.7
  5254.4  195.07    5260   194.9    5292  196.61  5374.1  204.83    5435  208.43
#Mann= 7 ,-1 , 0
  4719.1     .17       0  4935.2     .15       0  4955.1     .17       0
  4990.5     .09       0  5013.5     .17       0    5260     .11       0
  5374.1     .17       0
Bank Sta=4990.5,5013.5
XS Rating Curve= 0 ,0
Exp/Cntr=0.3,0.1

Type RM Length L Ch R = 1 ,3406    ,499,499,499
BEGIN DESCRIPTION:
LAKE CREEK TRIBUTARY NO. 18 7.0
END DESCRIPTION:
XS GIS Cut Line= 3
      3747380.48     10101812.77      3747781.23     10101479.22
      3748067.85     10101311.07
#Sta/Elev= 30
  4478.6  209.89    4514  207.31  4520.5  207.55  4549.2  203.99  4561.8  204.15
  4641.6  200.54  4683.4  197.27  4748.4  193.93  4804.3  194.94  4812.1   194.2
  4853.8     196  4904.5  194.57  4917.7  194.91  4982.6  194.25  4994.6   190.1
    4999  189.41  5009.2  189.41  5009.7  189.91  5009.8  192.93  5019.3   194.5
  5023.2  194.27  5049.5  193.17  5077.2   193.1    5112  194.91  5127.1  194.89
  5179.9  200.15  5185.7  199.91  5201.4  201.97  5281.5   207.4  5332.3  209.65
#Mann= 7 ,-1 , 0
  4478.6     .17       0  4561.8     .15       0  4917.7     .17       0
  4982.6     .09       0  5019.3     .17       0  5023.2     .11       0
  5049.5     .17       0
Bank Sta=4982.6,5019.3
XS Rating Curve= 0 ,0
Exp/Cntr=0.3,0.1

Type RM Length L Ch R = 1 ,2907    ,489,489,489
BEGIN DESCRIPTION:
LAKE CREEK TRIBUTARY NO. 18 6.0
END DESCRIPTION:
XS GIS Cut Line= 3
      3747617.81      10102161.1      3748008.25     10101883.27
      3748317.82      10101611.1
#Sta/Elev= 30
  4520.8  208.63  4549.1  206.87  4563.9  204.93  4597.7  202.29  4622.9  200.13
  4664.7  196.41  4729.5  193.16  4742.2  191.28  4774.5  193.07    4843  193.65
  4929.1  191.55  4958.6  193.09  4973.4  193.04  4987.2  191.65  4988.6  188.42
  4989.1  187.92  4999.5  187.92  5003.1  188.66  5008.5  191.75  5015.2  191.07
  5022.7  192.88    5037  192.11  5072.1  191.86  5143.2  196.15  5178.4  197.35
  5192.6  199.05  5199.2  198.68  5218.8  200.37  5305.7  206.11  5412.2  211.93
#Mann= 7 ,-1 , 0
  4520.8     .17       0  4597.7     .11       0  4622.9     .17       0
  4774.5     .15       0  4987.2     .09       0  5008.5     .15       0
  5218.8     .17       0
Bank Sta=4987.2,5008.5
XS Rating Curve= 0 ,0
Exp/Cntr=0.3,0.1

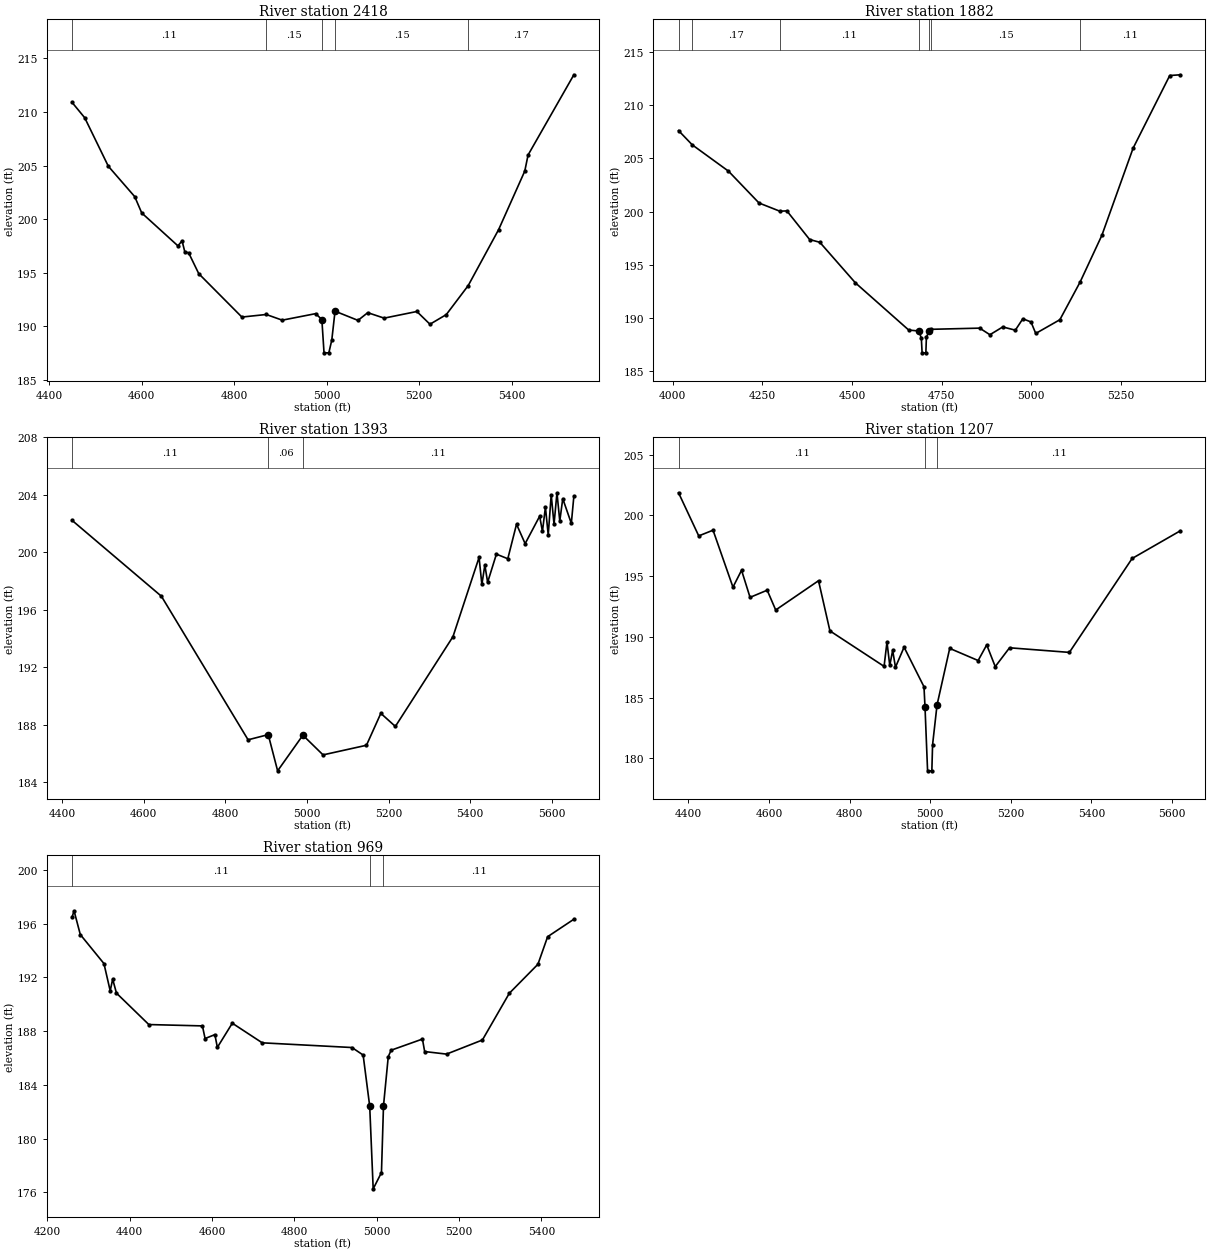
Type RM Length L Ch R = 1 ,2418    ,536,536,536
BEGIN DESCRIPTION:
LAKE CREEK TRIBUTARY NO. 18 5.0
END DESCRIPTION:
XS GIS Cut Line= 3
      3747627.84     10102639.62      3748086.61     10102335.36
      3748467.88     10101961.04
#Sta/Elev= 30
  4449.5  210.89  4476.8  209.46  4527.9  204.93    4585  202.09  4600.1  200.57
  4678.3   197.5  4687.3  197.96  4693.3  196.93  4701.5  196.85  4723.4   194.9
  4816.6  190.85  4869.3  191.09  4903.9  190.56  4976.1  191.17  4989.5  190.62
  4994.2  187.51  5004.6  187.51    5011  188.71    5018   191.4  5067.6  190.54
  5088.7  191.26  5124.2  190.75  5194.9  191.37  5223.2  190.18  5258.5  191.08
  5305.9  193.79  5371.6  199.01  5428.2  204.48  5435.3  205.98  5534.3  213.47
#Mann= 5 ,-1 , 0
  4449.5     .11       0  4869.3     .15       0  4989.5     .09       0
    5018     .15       0  5305.9     .17       0
Bank Sta=4989.5,5018
XS Rating Curve= 0 ,0
Exp/Cntr=0.3,0.1

Type RM Length L Ch R = 1 ,1882    ,489,489,489
BEGIN DESCRIPTION:
LAKE CREEK TRIBUTARY NO. 18 4.0
END DESCRIPTION:
XS GIS Cut Line= 3
       3747777.6      10103177.8      3748502.42     10102520.25
      3748867.84     10102311.08
#Sta/Elev= 30
    4016  207.61  4054.3  206.27  4155.3   203.8  4240.5  200.81  4298.5  200.04
  4318.2  200.07  4381.7  197.38  4410.1  197.12  4509.4  193.31  4658.1  188.88
  4686.5  188.79  4693.3  188.11  4695.4  186.74  4705.9  186.74  4707.4  188.21
  4714.9  188.76  4721.2  188.95  4856.1  189.06  4884.5  188.44  4920.3  189.17
  4955.5  188.87  4976.4  189.94  4999.1  189.64  5012.4  188.56  5079.7  189.85
  5136.2  193.39  5196.8  197.77    5284  205.96  5386.2  212.78  5415.7  212.85
#Mann= 7 ,-1 , 0
    4016     .11       0  4054.3     .17       0  4298.5     .11       0
  4686.5     .09       0  4714.9     .11       0  4721.2     .15       0
  5136.2     .11       0
Bank Sta=4686.5,4714.9
XS Rating Curve= 0 ,0
Exp/Cntr=0.3,0.1

Type RM Length L Ch R = 1 ,1393    ,186,186,186
BEGIN DESCRIPTION:
LAKE CREEK TRIBUTARY NO. 18 3.0
END DESCRIPTION:
XS GIS Cut Line= 2
      3748424.33     10103297.13      3749268.48     10102403.07
#Sta/Elev= 30
  4424.3  202.21  4643.2  196.93  4855.6  186.94    4905   187.3    4928  184.78
  4989.9  187.26  5039.3  185.89  5145.7  186.56  5180.9  188.78  5216.5  187.87
  5357.7  194.12  5421.6  199.63  5428.5  197.75  5435.8   199.1  5442.6   197.9
  5464.1  199.86    5492  199.54  5513.4  201.94  5534.5  200.59  5570.1   202.5
  5576.9  201.44  5584.2  203.13  5591.1   201.2  5598.4  203.99  5605.3  201.94
  5612.5  204.13  5619.4  202.16  5626.7  203.72  5647.7     202  5653.9  203.89
#Mann= 3 , 0 , 0
  4424.3     .11       0    4905     .06       0  4989.9     .11       0
Bank Sta=4905,4989.9
XS Rating Curve= 0 ,0
Exp/Cntr=0.3,0.1

Type RM Length L Ch R = 1 ,1207    ,238,238,238
BEGIN DESCRIPTION:
Mapping XS e2d6e757
END DESCRIPTION:
XS GIS Cut Line= 2
      3748539.33     10103403.48      3749407.38     10102511.56
#Sta/Elev= 30
  4375.9  201.87    4426  198.32  4461.5  198.79  4510.9   194.1  4532.2  195.49
  4553.3  193.26  4595.8  193.85  4616.9  192.22  4723.1  194.63  4751.4   190.5
  4885.7  187.58  4892.9  189.58  4899.8  187.66    4907  188.89    4914  187.51
  4935.3  189.16  4984.7   185.9 4987.21184.2477  4993.6  178.98  5004.2  178.98
    5006  181.13  5017.1 184.411  5048.5  189.06    5119  188.06  5140.3  189.35
  5161.4  187.56  5196.9  189.11  5345.3  188.73  5500.9  196.46  5620.5  198.74
#Mann= 3 , 0 , 0
  4375.9     .11       0 4987.21     .06       0  5017.1     .11       0
Bank Sta=4987.21,5017.1
XS Rating Curve= 0 ,0
Exp/Cntr=0.3,0.1

Type RM Length L Ch R = 1 ,969     ,0,0,0
BEGIN DESCRIPTION:
LAKE CREEK TRIBUTARY NO. 18 2.0
END DESCRIPTION:
XS GIS Cut Line= 3
       3748576.2     10103396.99      3749198.37     10102996.74
      3749387.84     10102557.13
#Sta/Elev= 30
  4260.2  196.48    4265  196.96  4280.2  195.19  4337.6  193.03  4352.8     191
  4358.8  191.87    4368  190.83  4446.6  188.49  4576.7  188.39  4583.2  187.45
    4607  187.74    4613  186.79  4649.3  188.59    4722  187.13  4939.9  186.78
    4967  186.22 4982.96182.4134  4991.4  176.26  5011.5  177.47 5016.44182.4363
    5028   186.1    5035  186.58    5111  187.41  5116.4  186.48  5169.5  186.29
  5256.6  187.34    5322  190.82  5391.5  192.98    5415  195.03  5478.7  196.33
#Mann= 3 , 0 , 0
  4260.2     .11       0 4982.96     .06       0 5016.44     .11       0
Bank Sta=4982.96,5016.44
XS Rating Curve= 0 ,0
Exp/Cntr=0.3,0.1

Chan Stop Cuts=-1
Use User Specified Reach Order=0
Composite Channel Slope=5