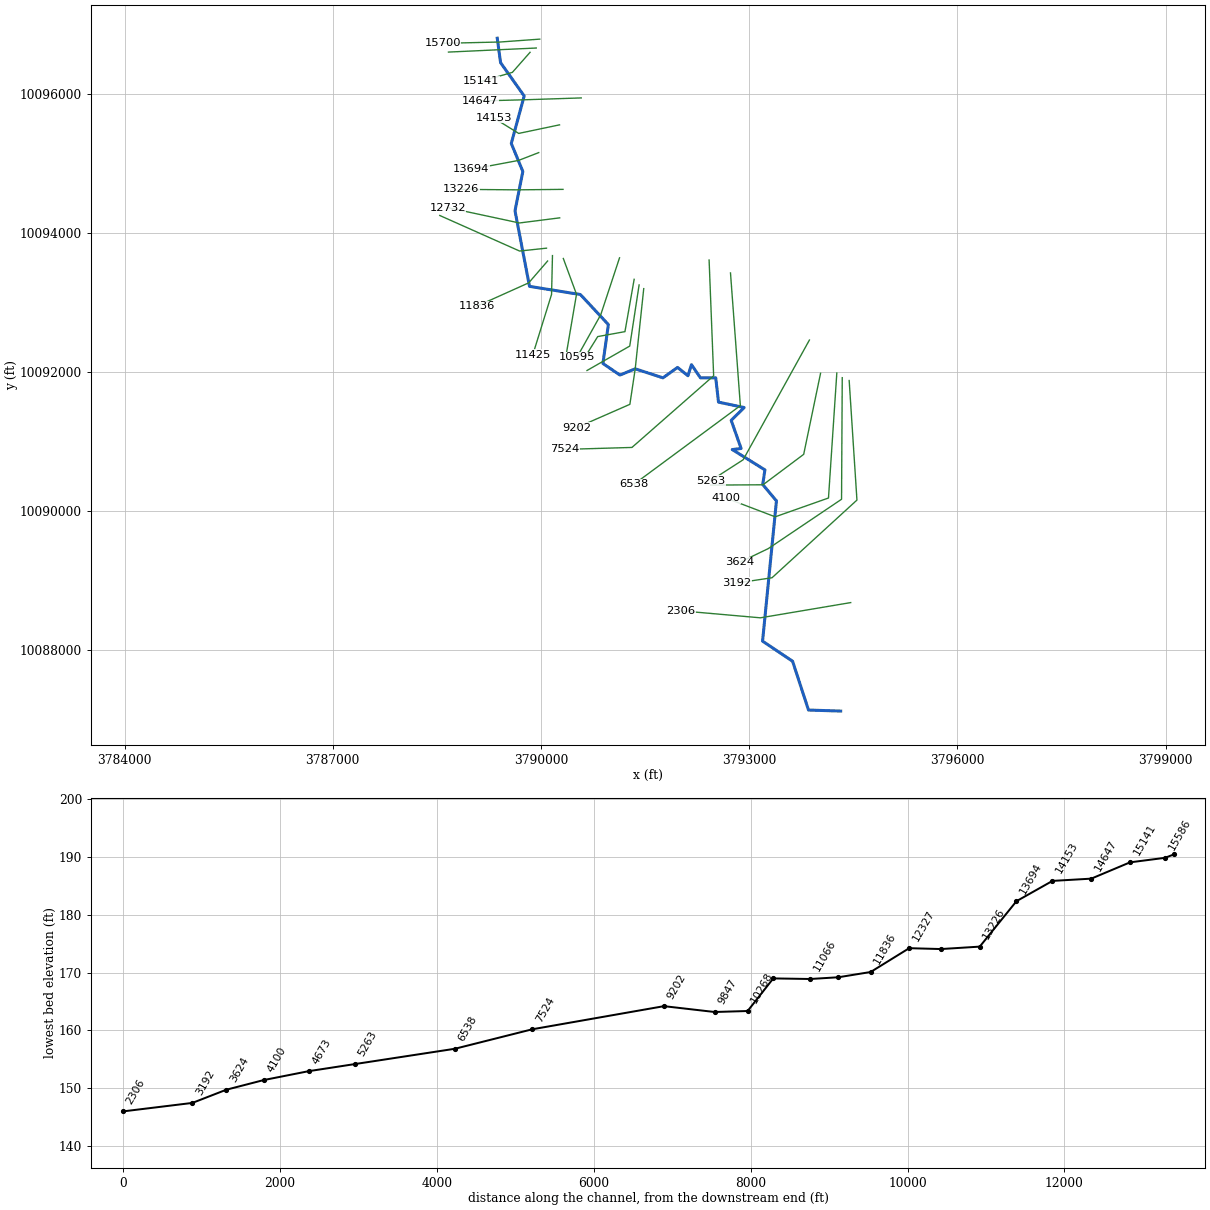
--- LAKE CREEK TRIBUTARY NO 2.prj (project) ---

Proj Title=LAKE CREEK TRIBUTARY NO 2 Base Level Engineering
Current Plan=p01
Default Exp/Contr=0.3,0.1
English Units
Geom File=g01
Flow File=f01
Flow File=f02
Plan File=p01
Y Axis Title=Elevation
X Axis Title(PF)=Main Channel Distance
X Axis Title(XS)=Station
BEGIN DESCRIPTION:
LAKE CREEK TRIBUTARY NO 2
END DESCRIPTION:
DSS Export Rating Curves= 0
DSS Export Rating Curve Sorted= 0
DSS Export Volume Flow Curves= 0
DXF OffsetX= 0
DXF OffsetY= 0
DXF ScaleX= 1
DXF ScaleY= 10

--- LAKE CREEK TRIBUTARY NO 2.p01 (plan) ---

Plan Title=Multiple Run
Short Identifier=Multiple
Geom File=g01
Flow File=f01
Subcritical Flow
K Sum by GR= 0
Std Step Tol= 0.01
Critical Tol= 0.01
Num of Std Step Trials= 20
Max Error Tol= 0.3
Flow Tol Ratio= 0.001
Split Flow NTrial= 30
Split Flow Tol= 0.02
Split Flow Ratio= 0.02
Log Output Level= 0
Friction Slope Method= 1
Unsteady Friction Slope Method= 2
Unsteady Bridges Friction Slope Method= 1
Parabolic Critical Depth
Global Vel Dist=  1 , 1 , 1
Global Log Level= 0
CheckData=True
Encroach Param= -1, 0, 0, 0
BEGIN DESCRIPTION:
Multiple Run
END DESCRIPTION:

--- LAKE CREEK TRIBUTARY NO 2.f01 (steady flow) ---

Flow Title=Multiple
Program Version=4.10
Number of Profiles= 7
Profile Names=10-year,25-year,50-year,1pct_min,100-year,1pct_plu,500-year
River Rch & RM=LAKE CREEK TRIBU,Reach-1         ,15700
     709     962    1301     579    1749    5282    3263
River Rch & RM=LAKE CREEK TRIBU,Reach-1         ,7524
     776    1044    1405     621    1876    5665    3455
Boundary for River Rch & Prof#=LAKE CREEK TRIBU,Reach-1         , 1
Up Type= 0
Dn Type= 3
Dn Slope=0.005
Boundary for River Rch & Prof#=LAKE CREEK TRIBU,Reach-1         , 2
Up Type= 0
Dn Type= 3
Dn Slope=0.005
Boundary for River Rch & Prof#=LAKE CREEK TRIBU,Reach-1         , 3
Up Type= 0
Dn Type= 3
Dn Slope=0.005
Boundary for River Rch & Prof#=LAKE CREEK TRIBU,Reach-1         , 4
Up Type= 0
Dn Type= 3
Dn Slope=0.005
Boundary for River Rch & Prof#=LAKE CREEK TRIBU,Reach-1         , 5
Up Type= 0
Dn Type= 3
Dn Slope=0.005
Boundary for River Rch & Prof#=LAKE CREEK TRIBU,Reach-1         , 6
Up Type= 0
Dn Type= 3
Dn Slope=0.005
Boundary for River Rch & Prof#=LAKE CREEK TRIBU,Reach-1         , 7
Up Type= 0
Dn Type= 3
Dn Slope=0.005
DSS Import GetInterval= 0
DSS Import GetPeak= 0
DSS Import FillOption= 0

--- LAKE CREEK TRIBUTARY NO 2.f02 (steady flow) ---

Flow Title=Orig_BLE_Flows
Program Version=4.10
Number of Profiles= 7
Profile Names=10-year,25-year,50-year,1pct_min,100-year,1pct_plu,500-year
River Rch & RM=LAKE CREEK TRIBU,Reach-1         ,15700
     709     943    1131     445    1345    4061    1897
River Rch & RM=LAKE CREEK TRIBU,Reach-1         ,7524
     776    1024    1222     478    1443    4359    2009
Boundary for River Rch & Prof#=LAKE CREEK TRIBU,Reach-1         , 1
Up Type= 0
Dn Type= 3
Dn Slope=0.005
Boundary for River Rch & Prof#=LAKE CREEK TRIBU,Reach-1         , 2
Up Type= 0
Dn Type= 3
Dn Slope=0.005
Boundary for River Rch & Prof#=LAKE CREEK TRIBU,Reach-1         , 3
Up Type= 0
Dn Type= 3
Dn Slope=0.005
Boundary for River Rch & Prof#=LAKE CREEK TRIBU,Reach-1         , 4
Up Type= 0
Dn Type= 3
Dn Slope=0.005
Boundary for River Rch & Prof#=LAKE CREEK TRIBU,Reach-1         , 5
Up Type= 0
Dn Type= 3
Dn Slope=0.005
Boundary for River Rch & Prof#=LAKE CREEK TRIBU,Reach-1         , 6
Up Type= 0
Dn Type= 3
Dn Slope=0.005
Boundary for River Rch & Prof#=LAKE CREEK TRIBU,Reach-1         , 7
Up Type= 0
Dn Type= 3
Dn Slope=0.005
DSS Import GetInterval= 0
DSS Import GetPeak= 0
DSS Import FillOption= 0

--- LAKE CREEK TRIBUTARY NO 2.g01 (geometry) ---

Geom Title=Existing Conditions
Program Version=4.10

River Reach=LAKE CREEK TRIBU,Reach-1
Reach XY= 30
      3789370.21     10096808.73      3789418.23     10096456.84
      3789758.23     10095976.84      3789572.41     10095293.19
      3789738.82     10094888.86      3789626.05     10094322.24
      3789835.09      10093234.4      3790568.23     10093116.84
      3790971.08     10092684.28      3790892.68     10092123.17
      3791138.23     10091956.84      3791358.23     10092046.84
      3791758.23     10091916.84      3791968.23     10092066.84
      3792118.23     10091946.84      3792168.23     10092106.84
      3792298.23     10091916.84      3792518.23     10091916.84
      3792558.23     10091566.84       3792928.1     10091489.16
      3792741.06     10091304.87      3792884.09     10090899.17
      3792756.19     10090884.04      3793227.06     10090590.71
      3793195.11     10090380.29      3793393.03     10090144.87
      3793193.03     10088124.04      3793625.67     10087834.46
      3793854.83     10087131.68      3794318.23     10087116.77

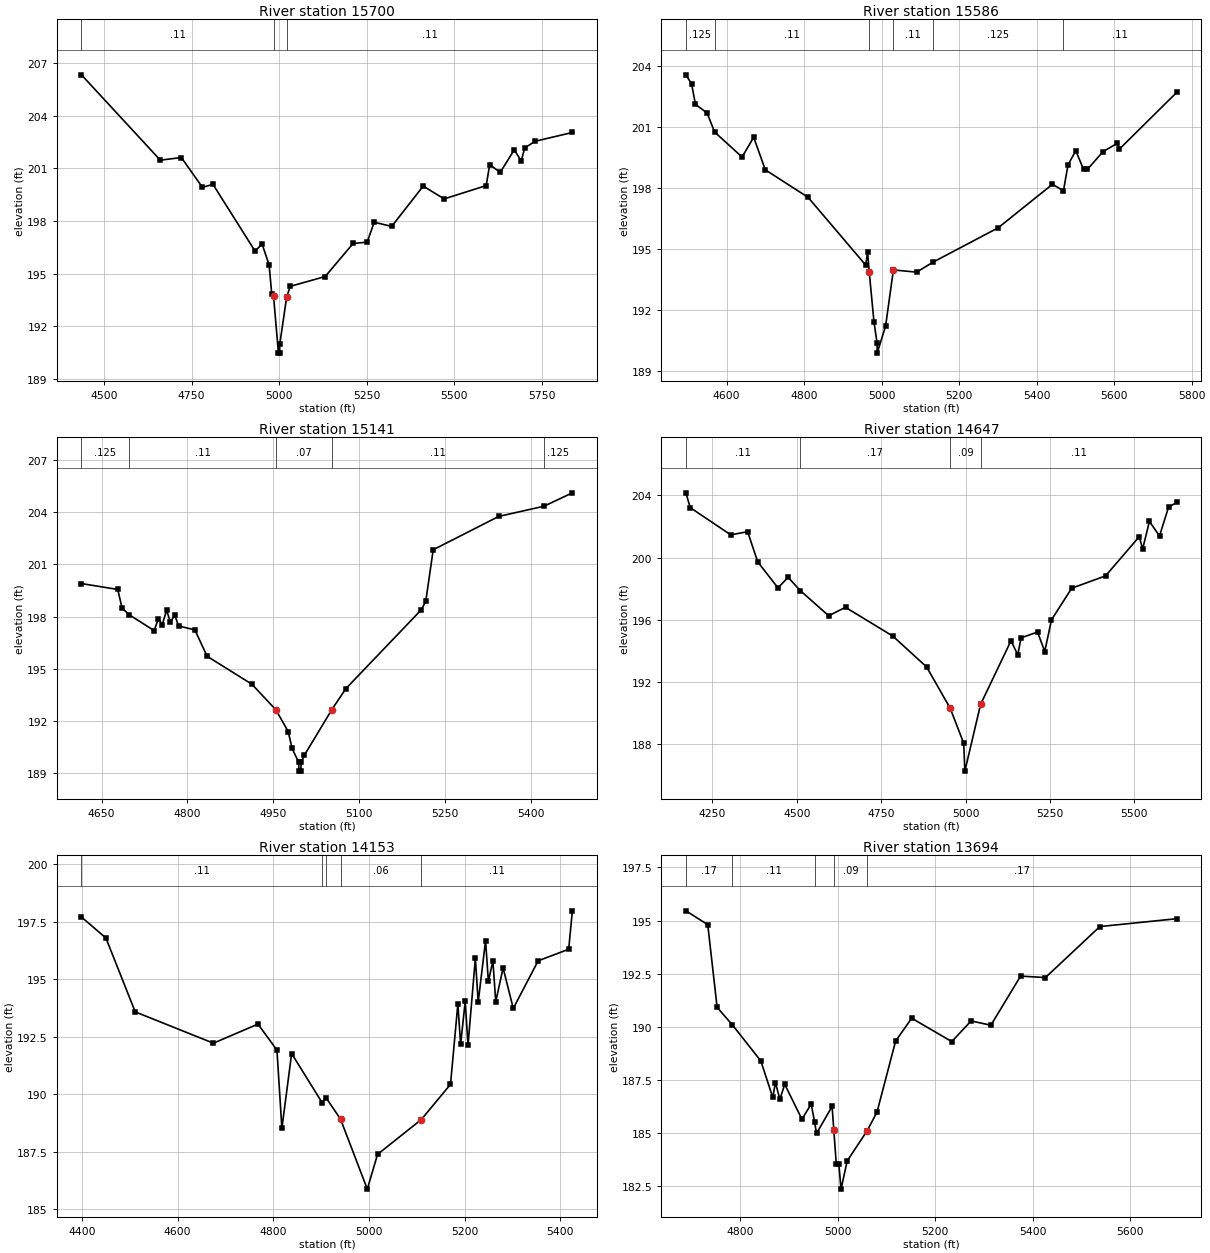
Type RM Length L Ch R = 1 ,15700   ,114,114,114
BEGIN DESCRIPTION:
LAKE CREEK TRIBUTARY NO. 2 25.0
END DESCRIPTION:
XS GIS Cut Line= 3
      3789982.53     10096795.74      3789416.12      10096754.5
      3788581.76       10096735.
#Sta/Elev= 30
  4435.6  206.34  4660.9  201.47    4721  201.62  4781.2  199.92  4811.3  200.09
  4931.6  196.28  4951.6  196.69  4971.7  195.49  4979.3  193.82  4984.3  193.72
  4998.4  190.46  5001.9  190.46  5002.1  190.96  5021.8  193.65  5031.8  194.27
  5131.8  194.83  5211.8  196.72  5251.8  196.79  5271.9  197.93  5321.9  197.69
  5411.9  199.99  5471.9  199.26  5591.9  200.02  5601.9  201.22  5631.9  200.77
    5672  202.06    5692  201.43    5702  202.17    5732  202.55  5838.1  203.05
#Mann= 3 , 0 , 0
  4435.6     .11       0  4984.3     .06       0  5021.8     .11       0
Bank Sta=4984.3,5021.8
XS Rating Curve= 0 ,0
Exp/Cntr=0.3,0.1

Type RM Length L Ch R = 1 ,15586   ,445,445,445
BEGIN DESCRIPTION:
Mapping XS c8d06062
END DESCRIPTION:
XS GIS Cut Line= 2
      3789932.57      10096667.7      3788667.42     10096609.11
#Sta/Elev= 30
  4495.2  203.55  4509.9   203.1  4519.9   202.1    4550  201.67  4569.2  200.74
  4640.1  199.51  4670.1  200.48  4700.1  198.88  4810.3  197.53    4959   194.2
    4964  194.82  4968.1193.8783  4980.4  191.41  4988.4  190.37  4988.7  189.87
  5010.5  191.21  5030.5  193.96  5090.6  193.85  5132.6  194.34  5300.8  196.03
  5440.9  198.17  5469.3  197.85    5481  199.12    5501  199.82    5521  198.91
    5531   198.9  5571.1  199.77  5608.6  200.19  5613.6   199.9  5761.7  202.69
#Mann= 6 ,-1 , 0
  4495.2    .125       0  4569.2     .11       0  4968.1     .07       0
  5030.5     .11       0  5132.6    .125       0  5469.3     .11       0
Bank Sta=4968.1,5030.5
XS Rating Curve= 0 ,0
Exp/Cntr=0.3,0.1

Type RM Length L Ch R = 1 ,15141   ,494,494,494
BEGIN DESCRIPTION:
LAKE CREEK TRIBUTARY NO. 2 24.0
END DESCRIPTION:
XS GIS Cut Line= 3
      3789842.85     10096605.76      3789588.23     10096316.84
      3789134.28     10096185.75
#Sta/Elev= 30
  4614.9   199.9  4678.3  199.56  4685.8  198.49  4698.4   198.1  4741.8  197.19
  4749.4  197.88  4756.1  197.54  4763.6  198.36  4770.3  197.67  4777.8   198.1
  4784.5  197.46    4813  197.23  4834.4  195.71  4912.6   194.1  4954.4  192.63
  4976.1  191.37  4982.8   190.4  4994.5  189.59  4994.8  189.09  4998.3  189.09
  4998.5  189.59  5004.2     190  5052.4  192.64  5076.7  193.84  5208.6  198.39
  5216.4  198.88  5229.4  201.85  5343.9  203.77  5423.1  204.36  5472.5  205.13
#Mann= 5 ,-1 , 0
  4614.9    .125       0  4698.4     .11       0  4954.4     .07       0
  5052.4     .11       0  5423.1    .125       0
Bank Sta=4954.4,5052.4
XS Rating Curve= 0 ,0
Exp/Cntr=0.3,0.1

Type RM Length L Ch R = 1 ,14647   ,494,494,494
BEGIN DESCRIPTION:
LAKE CREEK TRIBUTARY NO. 2 23.0
END DESCRIPTION:
XS GIS Cut Line= 3
      3790580.63     10095948.89      3789752.58      10095921.7
      3789126.69     10095905.49
#Sta/Elev= 30
  4171.5  204.16  4184.3  203.21  4304.3  201.46  4354.4  201.66  4384.4  199.72
  4444.4  198.05  4474.4  198.73  4510.2  197.88  4594.5  196.26  4644.5   196.8
  4784.6  194.95  4884.7  192.97  4954.7  190.31  4994.7  188.06  4998.1  186.27
  5044.7  190.56  5134.8  194.65  5154.8  193.75  5164.8  194.84  5213.5  195.21
  5234.8  193.96  5254.8     196  5314.8  198.03  5414.9  198.82  5514.9  201.34
  5524.9  200.55  5544.9  202.32  5574.9  201.39  5601.8  203.25  5626.1  203.54
#Mann= 4 ,-1 , 0
  4171.5     .11       0  4510.2     .17       0  4954.7     .09       0
  5044.7     .11       0
Bank Sta=4954.7,5044.7
XS Rating Curve= 0 ,0
Exp/Cntr=0.3,0.1

Type RM Length L Ch R = 1 ,14153   ,459,459,459
BEGIN DESCRIPTION:
LAKE CREEK TRIBUTARY NO. 2 22.0
END DESCRIPTION:
XS GIS Cut Line= 3
      3790267.86     10095561.07      3789679.69      10095437.6
      3789317.84     10095661.08
#Sta/Elev= 30
    4399   197.7  4450.1  196.79  4511.4  193.58  4674.9  192.22    4768  193.05
  4807.7  191.92    4818  188.52  4838.4  191.77    4902  189.64  4910.4  189.85
  4940.6  188.92  4996.6  185.88    5018  187.39 5109.26188.8987  5170.5  190.43
  5185.9  193.92  5191.7  192.17  5201.3  194.04  5207.1  192.13  5222.5  195.91
  5228.4     194  5243.8  196.68  5249.7  194.91  5259.2  195.79  5265.1  194.02
  5280.5  195.49  5301.7  193.73  5353.8   195.8  5417.6   196.3  5425.3  197.97
#Mann= 5 ,-1 , 0
    4399     .11       0    4902     .17       0  4910.4     .11       0
  4940.6     .06       0 5109.26     .11       0
Bank Sta=4940.6,5109.26
XS Rating Curve= 0 ,0
Exp/Cntr=0.3,0.1

Type RM Length L Ch R = 1 ,13694   ,468,468,468
BEGIN DESCRIPTION:
LAKE CREEK TRIBUTARY NO. 2 21.0
END DESCRIPTION:
XS GIS Cut Line= 3
      3789967.87     10095161.08      3789676.94     10095048.39
      3788992.52     10094920.32
#Sta/Elev= 30
    4688  195.46  4732.9  194.81  4752.1  190.92  4783.7  190.09  4841.9   188.4
  4866.5  186.68  4871.8  187.38  4881.1   186.6    4891   187.3  4926.3  185.66
  4945.4  186.37  4952.4  185.52  4956.3  184.99  4988.3  186.26 4991.82 185.146
  4996.8  183.57  5002.1  183.57  5006.6  182.37  5019.4   183.7  5060.1  185.11
  5080.5  185.99  5118.7  189.33  5151.7  190.41  5234.1  189.31  5273.8  190.28
  5314.4  190.08  5375.5  192.39  5426.4  192.32  5538.3  194.72  5696.3  195.09
#Mann= 5 ,-1 , 0
    4688     .17       0  4783.7     .11       0  4952.4     .17       0
 4991.82     .09       0  5060.1     .17       0
Bank Sta=4991.82,5060.1
XS Rating Curve= 0 ,0
Exp/Cntr=0.3,0.1

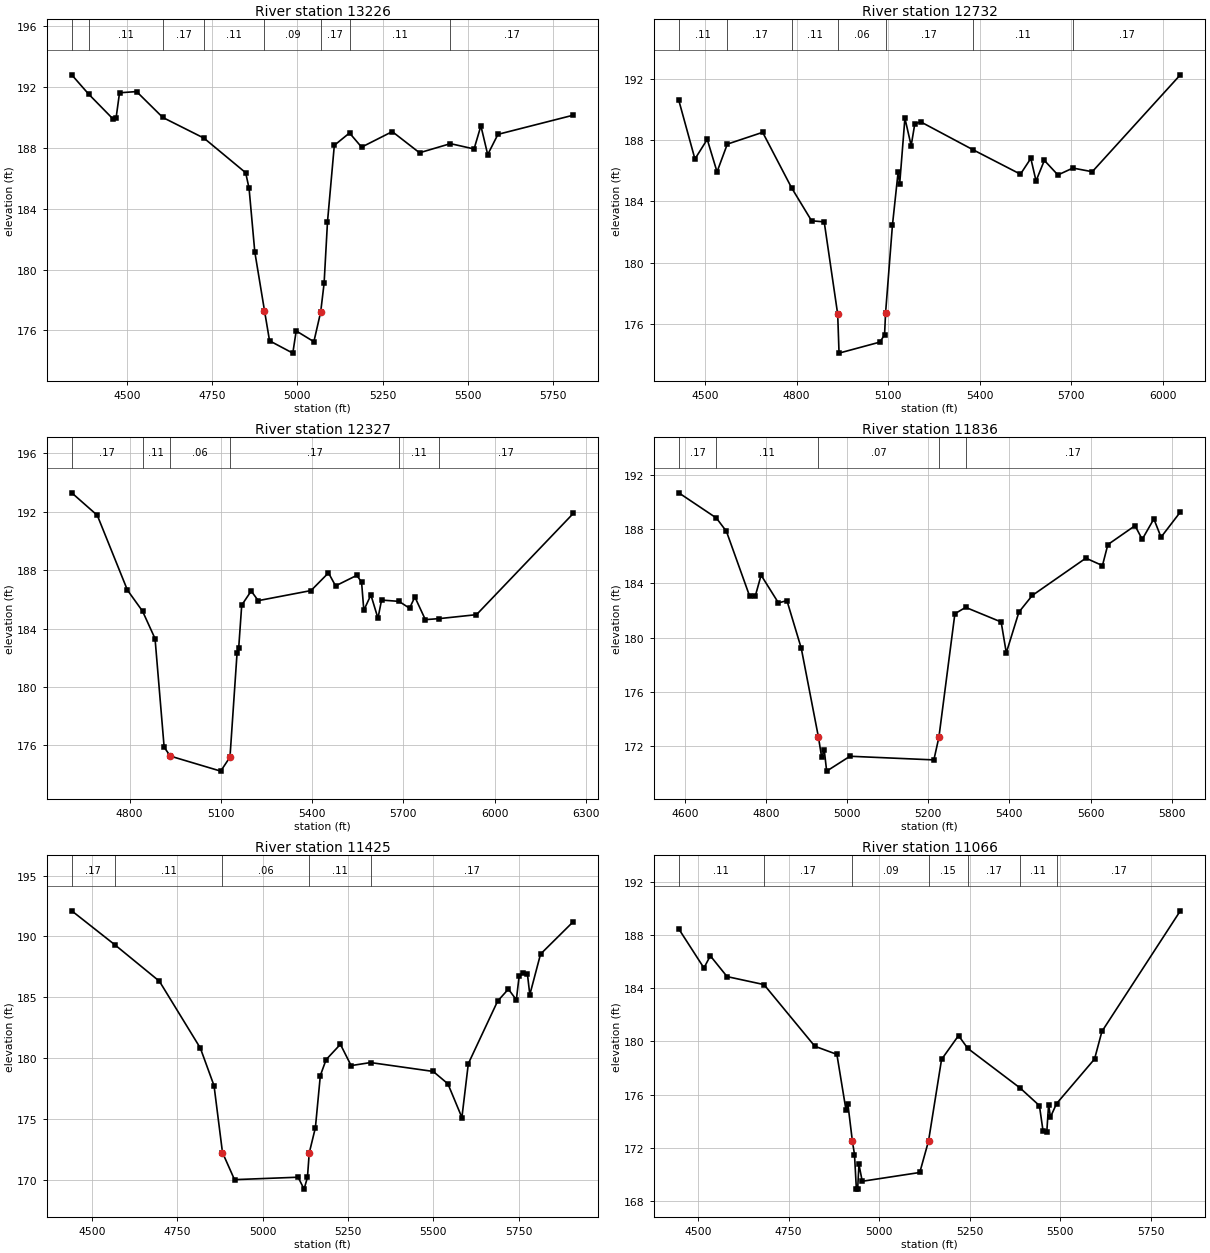
Type RM Length L Ch R = 1 ,13226   ,494,494,494
BEGIN DESCRIPTION:
LAKE CREEK TRIBUTARY NO. 2 20.0
END DESCRIPTION:
XS GIS Cut Line= 3
      3790318.07     10094631.62      3789656.31      10094624.8
      3788846.74     10094631.62
#Sta/Elev= 30
  4338.2  192.79  4387.5  191.53  4458.4  189.91  4468.4  189.98  4478.4  191.61
  4528.4  191.69  4605.3  189.99  4726.2  188.63  4848.4  186.36  4858.4  185.34
  4875.2  181.16 4903.66177.2989  4918.5  175.32  4986.7  174.51  4996.7  175.97
  5048.5  175.26  5068.5  177.21  5078.5  179.09  5088.5  183.14  5108.5  188.16
  5153.1  188.97  5188.5  188.04  5278.5  189.06  5358.5  187.67  5449.2  188.27
  5518.5  187.92  5538.5  189.44  5558.5  187.55  5588.5  188.88  5809.6  190.14
#Mann= 8 ,-1 , 0
  4338.2     .17       0  4387.5     .11       0  4605.3     .17       0
  4726.2     .11       0 4903.66     .09       0  5068.5     .17       0
  5153.1     .11       0  5449.2     .17       0
Bank Sta=4903.66,5068.5
XS Rating Curve= 0 ,0
Exp/Cntr=0.3,0.1

Type RM Length L Ch R = 1 ,12732   ,405,405,405
BEGIN DESCRIPTION:
LAKE CREEK TRIBUTARY NO. 2 19.0
END DESCRIPTION:
XS GIS Cut Line= 3
      3790270.33     10094221.46      3789689.31     10094147.58
      3788655.77     10094369.03
#Sta/Elev= 30
  4414.3  190.58  4467.2  186.75  4507.5  188.03  4539.6  185.91  4573.2  187.72
    4689  188.49  4783.8  184.87  4849.3  182.72  4890.6  182.65 4934.76176.6288
  4939.2  174.09  5073.1  174.81  5088.3  175.29 5091.51176.6912    5114  182.42
  5132.7  185.91  5137.8  185.13  5154.9  189.41  5175.4  187.62  5187.2  189.03
    5206  189.18  5376.4  187.37  5533.3  185.76  5567.3  186.79  5584.4  185.32
  5611.6  186.66    5656  185.71  5705.1  186.16  5768.5  185.92    6057  192.24
#Mann= 7 ,-1 , 0
  4414.3     .11       0  4573.2     .17       0  4783.8     .11       0
 4934.76     .06       0 5091.51     .17       0  5376.4     .11       0
  5705.1     .17       0
Bank Sta=4934.76,5091.51
XS Rating Curve= 0 ,0
Exp/Cntr=0.3,0.1

Type RM Length L Ch R = 1 ,12327   ,491,491,491
BEGIN DESCRIPTION:
LAKE CREEK TRIBUTARY NO. 2 18.0
END DESCRIPTION:
XS GIS Cut Line= 3
      3790079.97     10093784.58      3789692.06     10093743.25
      3788541.87     10094255.49
#Sta/Elev= 30
  4609.9  193.29  4693.9  191.75    4793  186.63  4842.7  185.19  4883.8  183.31
  4913.7  175.88  4933.8  175.27  5099.7  174.24  5130.2   175.2  5153.4   182.3
  5158.9  182.68  5168.8   185.6  5199.9  186.57  5223.1  185.91  5396.7   186.6
  5454.1  187.81  5477.4  186.92  5547.1  187.64  5562.9  187.18  5570.3  185.25
  5593.6   186.3  5616.8   184.7  5628.6  185.95    5686  185.86  5720.7  185.39
  5738.1  186.16  5772.6  184.61  5818.6  184.68  5940.8  184.95  6259.1  191.88
#Mann= 6 ,-1 , 0
  4609.9     .17       0  4842.7     .11       0  4933.8     .06       0
  5130.2     .17       0    5686     .11       0  5818.6     .17       0
Bank Sta=4933.8,5130.2
XS Rating Curve= 0 ,0
Exp/Cntr=0.3,0.1

Type RM Length L Ch R = 1 ,11836   ,411,411,411
BEGIN DESCRIPTION:
LAKE CREEK TRIBUTARY NO. 2 17.0
END DESCRIPTION:
XS GIS Cut Line= 3
      3790095.58     10093599.69      3789824.09     10093285.28
      3789074.73     10092948.64
#Sta/Elev= 30
  4584.6   190.7  4677.2  188.84  4702.1  187.85  4759.1  183.08  4773.4  183.08
  4787.6  184.61  4830.4  182.56  4851.3  182.73  4886.7   179.2  4929.1  172.62
  4936.8  171.17  4943.4  171.66  4949.3  170.12  5006.8  171.22  5213.7  170.95
  5226.1  172.63  5265.5  181.76  5292.1  182.23  5379.6  181.15  5392.3  178.87
  5423.4  181.88  5456.3  183.11  5588.5  185.87  5629.4  185.32  5642.7  186.87
  5709.8  188.27  5727.5  187.26  5756.2  188.77  5773.9  187.42  5821.5  189.28
#Mann= 5 ,-1 , 0
  4584.6     .17       0  4677.2     .11       0  4929.1     .07       0
  5226.1     .11       0  5292.1     .17       0
Bank Sta=4929.1,5226.1
XS Rating Curve= 0 ,0
Exp/Cntr=0.3,0.1

Type RM Length L Ch R = 1 ,11425   ,359,359,359
BEGIN DESCRIPTION:
LAKE CREEK TRIBUTARY NO. 2 16.0
END DESCRIPTION:
XS GIS Cut Line= 3
      3790165.89     10093677.82      3790152.78     10093118.87
      3789882.44     10092249.43
#Sta/Elev= 30
  4440.9   192.1  4567.5   189.3  4697.7  186.31  4817.7  180.81  4857.8  177.72
  4882.6172.2183  4917.8  169.99  5104.2  170.19  5121.6  169.21  5131.5  170.17
  5136.8  172.19  5154.8  174.26  5169.3  178.55  5186.2  179.86  5228.1  181.12
  5259.5  179.37  5316.3  179.62    5500  178.89  5543.1  177.87  5584.1   175.1
  5602.9  179.53  5688.9  184.68  5720.3  185.66  5743.6  184.78  5751.7   186.7
  5762.2  186.97  5776.1  186.89  5783.1   185.2  5814.5  188.54  5910.5  191.21
#Mann= 5 ,-1 , 0
  4440.9     .17       0  4567.5     .11       0  4882.6     .06       0
  5136.8     .11       0  5316.3     .17       0
Bank Sta=4882.6,5136.8
XS Rating Curve= 0 ,0
Exp/Cntr=0.3,0.1

Type RM Length L Ch R = 1 ,11066   ,471,471,471
BEGIN DESCRIPTION:
LAKE CREEK TRIBUTARY NO. 2 15.0
END DESCRIPTION:
XS GIS Cut Line= 3
      3790322.13     10093636.16      3790512.24     10093120.52
      3790371.62     10092297.62
#Sta/Elev= 30
  4446.7  188.45  4516.1  185.52  4533.8  186.43    4580  184.87  4681.9  184.27
  4822.2  179.64  4883.1  179.03  4908.2  174.86  4913.5  175.29 4925.81172.5269
  4931.7  171.51  4936.9  168.91  4940.4  168.91    4944  170.76  4953.1   169.5
  5111.9  170.16  5136.1 172.529    5172  178.65  5218.9  180.44  5244.3  179.48
    5389   176.5  5442.1  175.18  5452.2  173.27  5462.4  173.18  5467.5  175.25
  5472.6  174.32  5489.4  175.33  5594.3  178.68  5614.6  180.75  5831.1  189.81
#Mann= 7 ,-1 , 0
  4446.7     .11       0  4681.9     .17       0 4925.81     .09       0
  5136.1     .15       0  5244.3     .17       0    5389     .11       0
  5489.4     .17       0
Bank Sta=4925.81,5136.1
XS Rating Curve= 0 ,0
Exp/Cntr=0.3,0.1

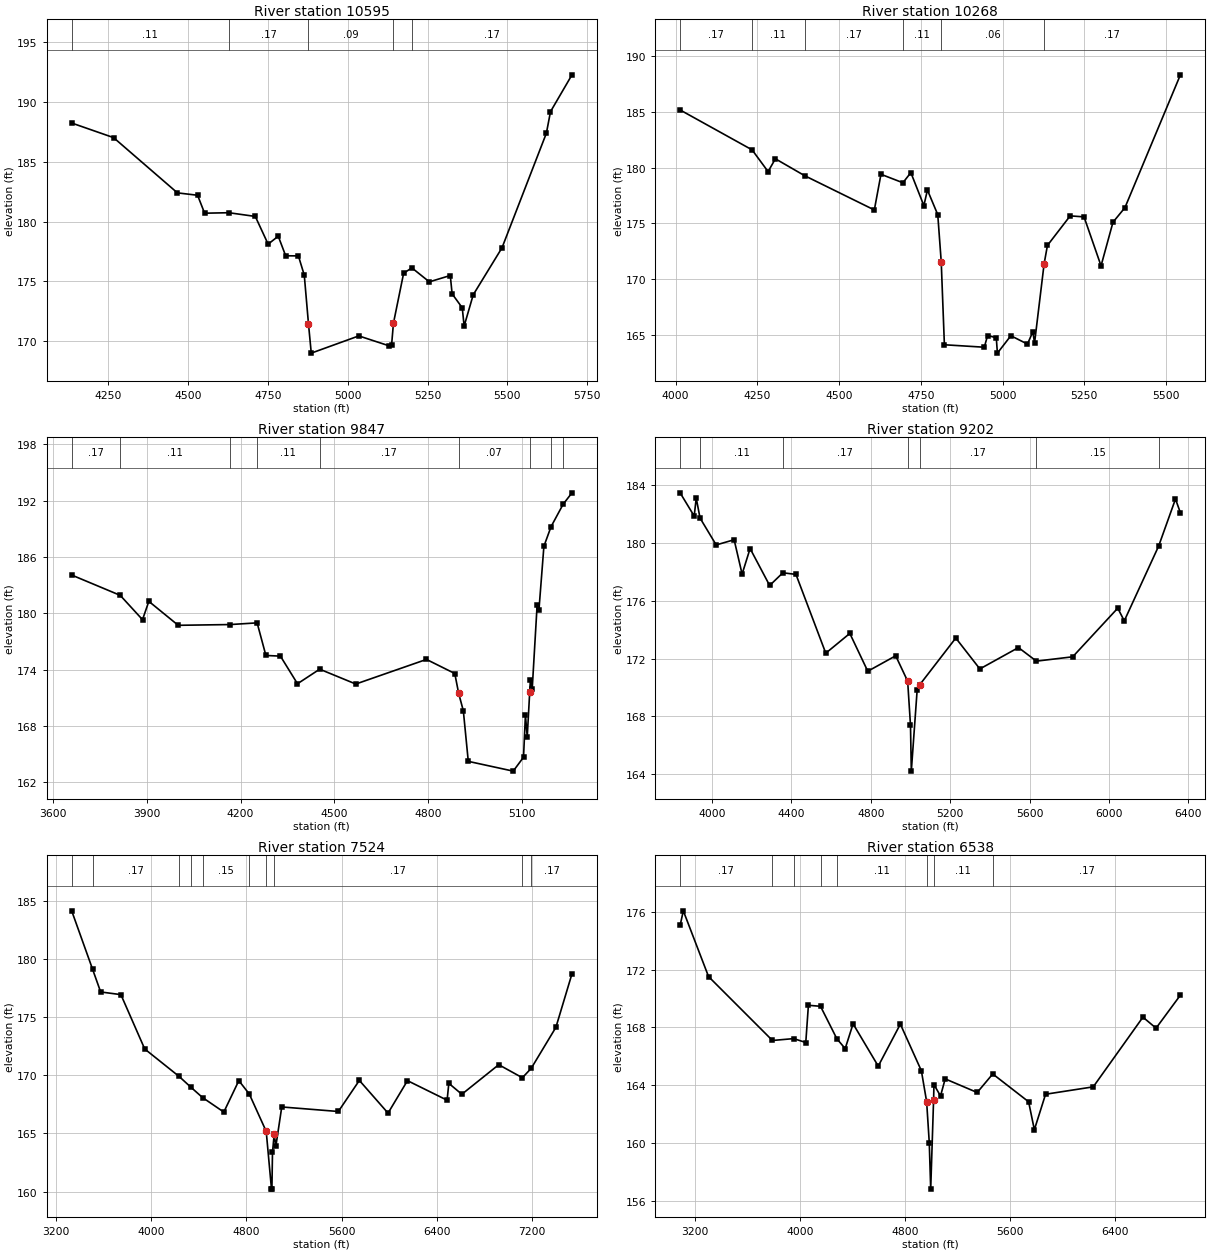
Type RM Length L Ch R = 1 ,10595   ,327,327,327
BEGIN DESCRIPTION:
LAKE CREEK TRIBUTARY NO. 2 14.0
END DESCRIPTION:
XS GIS Cut Line= 3
      3791132.02     10093645.66      3790860.95     10092824.12
      3790517.87      10092211.1
#Sta/Elev= 30
  4134.9  188.25  4266.1  187.03  4466.2  182.41  4529.4  182.21  4551.4  180.71
  4627.5  180.75  4710.2  180.44  4750.5  178.12  4782.1  178.79  4805.4  177.15
  4845.3  177.14  4863.7  175.53  4876.9  171.45  4885.6  169.01  5034.6  170.45
  5129.6  169.62  5137.4  169.73  5143.1  171.51    5175  175.69  5200.8  176.14
  5255.6  174.97  5321.2   175.5  5326.9  173.97  5358.7   172.8  5364.6  171.27
  5393.1  173.89  5483.3  177.82  5622.3   187.4  5635.2   189.2  5702.5  192.28
#Mann= 5 ,-1 , 0
  4134.9     .11       0  4627.5     .17       0  4876.9     .09       0
  5143.1     .15       0  5200.8     .17       0
Bank Sta=4876.9,5143.1
XS Rating Curve= 0 ,0
Exp/Cntr=0.3,0.1

Type RM Length L Ch R = 1 ,10268   ,421,421,421
BEGIN DESCRIPTION:
LAKE CREEK TRIBUTARY NO. 2 13.0
END DESCRIPTION:
XS GIS Cut Line= 4
      3791342.85     10093336.06      3791210.16     10092582.32
      3790817.85     10092511.07      3790624.24     10092200.41
#Sta/Elev= 30
  4013.7  185.18  4233.9   181.6  4282.8  179.65  4305.1   180.8  4394.9  179.28
  4607.7  176.21    4628  179.41  4695.1  178.65  4719.4  179.56  4759.2   176.6
  4770.1     178  4801.7  175.79 4812.31 171.567    4822  164.12    4944   163.9
  4954.2  164.95  4980.7  164.75  4984.1  163.37  5025.3  164.93  5076.1  164.18
  5092.6   165.3  5097.7  164.27  5126.9  171.36  5137.1  173.03  5206.7  175.68
  5249.1  175.59  5301.1   171.2  5337.6  175.11  5374.2  176.42  5543.8  188.33
#Mann= 6 ,-1 , 0
  4013.7     .17       0  4233.9     .11       0  4394.9     .17       0
  4695.1     .11       0 4812.31     .06       0  5126.9     .17       0
Bank Sta=4812.31,5126.9
XS Rating Curve= 0 ,0
Exp/Cntr=0.3,0.1

Type RM Length L Ch R = 1 ,9847    ,645,645,645
BEGIN DESCRIPTION:
LAKE CREEK TRIBUTARY NO. 2 12.0
END DESCRIPTION:
XS GIS Cut Line= 3
      3791414.15     10093255.07      3791279.22     10092374.58
      3790663.25     10092022.41
#Sta/Elev= 30
  3659.7  184.07  3814.9  181.91  3886.3  179.32  3906.5  181.27  4000.5  178.72
  4166.6   178.8  4252.9  178.98  4280.9  175.51  4327.4  175.44    4382   172.5
    4453  174.05  4568.5  172.47  4794.5  175.09  4885.1  173.59  4897.6  171.47
  4912.5  169.62  4928.3  164.24    5072   163.2    5105  164.68  5111.1  169.17
  5116.9  166.85 5124.81171.6274    5127  172.95  5132.7  171.89  5148.6  180.92
  5154.3  180.34  5170.2  187.13  5193.1  189.22  5231.8  191.61    5260  192.82
#Mann= 9 ,-1 , 0
  3659.7     .17       0  3814.9     .11       0  4166.6     .17       0
  4252.9     .11       0    4453     .17       0  4897.6     .07       0
 5124.81     .17       0  5193.1     .11       0  5231.8     .17       0
Bank Sta=4897.6,5124.81
XS Rating Curve= 0 ,0
Exp/Cntr=0.3,0.1

Type RM Length L Ch R = 1 ,9202    ,1678,1678,1678
BEGIN DESCRIPTION:
LAKE CREEK TRIBUTARY NO. 2 11.0
END DESCRIPTION:
XS GIS Cut Line= 4
      3791480.84     10093201.96      3791358.23     10092046.84
      3791281.18     10091535.27      3790508.64     10091196.74
#Sta/Elev= 30
  3838.4  183.49  3909.4  181.88  3919.7  183.12    3939  181.74  4020.3  179.88
  4110.8  180.24    4151  177.86  4191.3  179.63  4289.9  177.07  4356.4  177.95
  4422.5  177.84  4572.8  172.38  4694.1  173.75  4784.6  171.13  4925.4   172.2
  4985.7  170.44    5000  167.38  5004.1  164.21  5033.6  169.84  5046.3  170.19
  5228.3  173.43  5349.7  171.29  5544.3  172.77  5634.8  171.83  5817.8  172.13
    6045   175.5  6077.8  174.62  6251.1   179.8    6336  183.06  6360.8  182.11
#Mann= 7 ,-1 , 0
  3838.4     .17       0    3939     .11       0  4356.4     .17       0
  4985.7     .09       0  5046.3     .17       0  5634.8     .15       0
  6251.1     .17       0
Bank Sta=4985.7,5046.3
XS Rating Curve= 0 ,0
Exp/Cntr=0.3,0.1

Type RM Length L Ch R = 1 ,7524    ,986,986,986
BEGIN DESCRIPTION:
LAKE CREEK TRIBUTARY NO. 2 10.0
END DESCRIPTION:
XS GIS Cut Line= 4
      3792422.68     10093614.26      3792488.23     10091946.84
      3791311.16     10090914.29      3790342.85     10090886.07
#Sta/Elev= 30
  3331.3  184.12  3506.6  179.11  3574.7  177.15  3744.8  176.92    3945  172.25
    4234  169.89  4332.3  168.97  4430.5  168.08  4609.5  166.83  4735.6  169.53
  4823.6  168.38  4965.7  165.17    5010  160.21  5013.5  160.21  5018.4  163.37
  5032.6  164.91  5046.9  163.91  5096.2  167.27  5571.6  166.88  5748.1  169.55
  5989.2  166.74  6152.4  169.53  6485.5  167.85  6499.7   169.3  6609.1  168.36
  6919.2   170.9  7117.7  169.78  7192.2  170.59  7399.4  174.11  7534.5  178.71
#Mann= 10 ,-1 , 0
  3331.3     .11       0  3506.6     .17       0    4234     .11       0
  4332.3     .17       0  4430.5     .15       0  4823.6     .17       0
  4965.7     .09       0  5032.6     .17       0  7117.7     .15       0
  7192.2     .17       0
Bank Sta=4965.7,5032.6
XS Rating Curve= 0 ,0
Exp/Cntr=0.3,0.1

Type RM Length L Ch R = 1 ,6538    ,1275,1275,1275
BEGIN DESCRIPTION:
LAKE CREEK TRIBUTARY NO. 2 9.0
END DESCRIPTION:
XS GIS Cut Line= 3
      3792730.83     10093427.68      3792873.09     10091516.67
      3791342.85     10090386.07
#Sta/Elev= 30
  3083.7  175.04  3108.1  176.05  3300.9  171.51  3788.6   167.1  3950.8  167.23
    4043  166.96    4063  169.53  4155.5  169.46  4280.2  167.22  4343.8  166.54
    4404  168.25  4596.1  165.33  4764.9  168.23  4925.4  165.01  4965.5  162.88
  4985.6  160.05  4996.6  156.84 5018.47 162.975  5021.5  164.05  5071.6  163.27
  5107.1  164.45  5351.4  163.51  5470.2  164.79  5743.9  162.87  5787.8  160.94
  5873.4  163.39  6237.4   163.9  6616.6  168.71  6716.8  167.95  6902.6  170.23
#Mann= 8 ,-1 , 0
  3083.7     .17       0  3788.6     .11       0  3950.8     .17       0
  4155.5     .15       0  4280.2     .11       0  4965.5     .06       0
 5018.47     .11       0  5470.2     .17       0
Bank Sta=4965.5,5018.47
XS Rating Curve= 0 ,0
Exp/Cntr=0.3,0.1

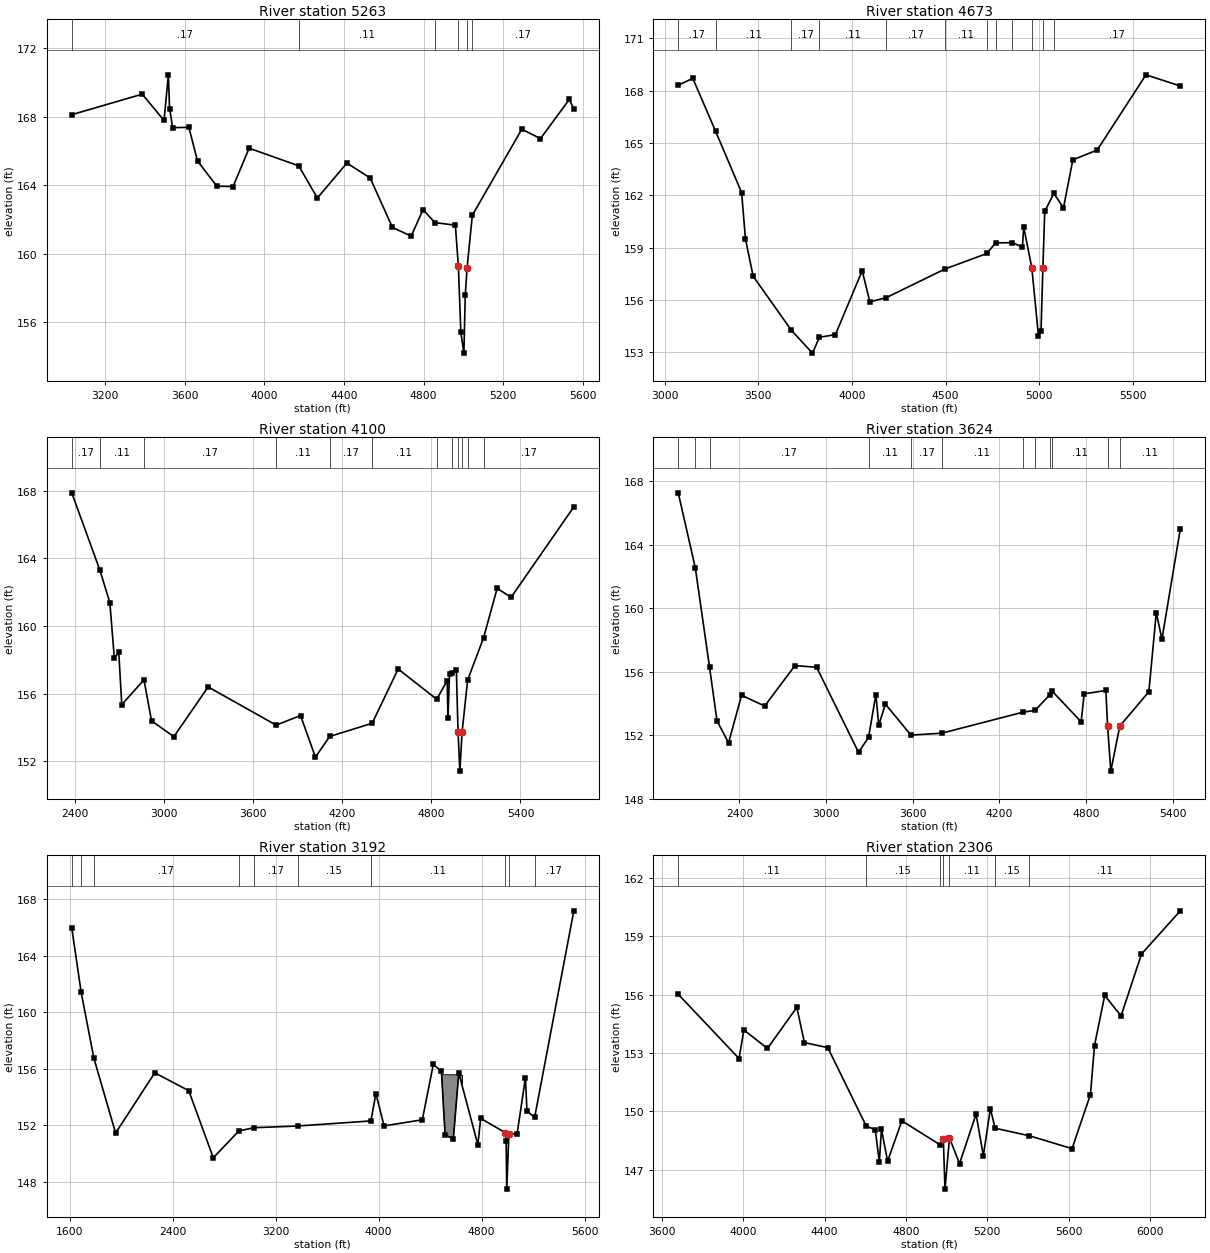
Type RM Length L Ch R = 1 ,5263    ,590,590,590
BEGIN DESCRIPTION:
LAKE CREEK TRIBUTARY NO. 2 8.0
END DESCRIPTION:
XS GIS Cut Line= 3
      3793867.87      10092461.1      3792913.13     10090736.66
      3792448.71     10090437.18
#Sta/Elev= 30
  3031.6  168.13    3386  169.33  3495.4  167.79  3517.1  170.46  3523.1  168.49
  3538.9  167.37  3620.2  167.39  3663.7  165.42    3761  163.95  3842.3  163.93
  3923.2  166.17  4172.4  165.14  4266.1  163.26  4414.7   165.3  4531.6  164.43
  4643.3  161.54  4737.7  161.03  4797.2  162.58  4857.1  161.82  4959.8  161.67
  4974.8  159.27  4987.3   155.4  5002.7  154.19  5009.4  157.56  5018.6  159.17
    5045  162.25  5293.8  167.28  5387.5  166.73  5532.5  169.02  5555.3  168.46
#Mann= 6 ,-1 , 0
  3031.6     .17       0  4172.4     .11       0  4857.1     .15       0
  4974.8     .09       0  5018.6     .15       0    5045     .17       0
Bank Sta=4974.8,5018.6
XS Rating Curve= 0 ,0
Exp/Cntr=0.3,0.1

Type RM Length L Ch R = 1 ,4673    ,573,573,573
BEGIN DESCRIPTION:
LAKE CREEK TRIBUTARY NO. 2 7.0
END DESCRIPTION:
XS GIS Cut Line= 4
      3794028.57     10091982.28      3793785.52     10090814.79
      3793199.58     10090376.42       3792444.4     10090372.08
#Sta/Elev= 30
  3072.7  168.31  3150.2  168.71  3271.6  165.69    3411  162.16  3431.4  159.51
  3472.3  157.37  3676.6  154.27    3789  152.96  3826.3  153.87  3911.5  154.02
  4054.5  157.68  4095.4   155.9  4182.8  156.14  4495.9  157.78  4719.8  158.67
  4766.4  159.28  4855.3  159.29  4909.8  159.04  4916.1  160.21  4959.8  157.84
    4995  153.96  5008.7  154.25  5018.7  157.82  5028.7  161.09  5077.5  162.11
  5128.7  161.29  5178.7  164.04  5308.7   164.6  5568.7  168.91  5752.2  168.27
#Mann= 12 ,-1 , 0
  3072.7     .17       0  3271.6     .11       0  3676.6     .17       0
  3826.3     .11       0  4182.8     .17       0  4495.9     .11       0
  4719.8     .17       0  4766.4     .11       0  4855.3     .17       0
  4959.8     .09       0  5018.7     .15       0  5077.5     .17       0
Bank Sta=4959.8,5018.7
XS Rating Curve= 0 ,0
Exp/Cntr=0.3,0.1

Type RM Length L Ch R = 1 ,4100    ,476,476,476
BEGIN DESCRIPTION:
LAKE CREEK TRIBUTARY NO. 2 6.0
END DESCRIPTION:
XS GIS Cut Line= 4
      3794262.95     10091986.66      3794142.85     10090186.07
      3793374.97     10089915.01      3792665.69     10090185.46
#Sta/Elev= 30
  2381.1  167.88  2570.5   163.3  2637.3  161.38  2667.3  158.12  2697.4  158.44
  2717.4  155.35  2866.9  156.82  2917.9  154.39  3068.2  153.46  3298.7   156.4
  3756.2  154.14  3920.1  154.71  4020.3  152.25  4116.2  153.47  4402.2  154.25
  4577.1  157.46  4836.4  155.67  4906.8  156.77  4912.1  154.55  4922.7  157.18
  4939.6  157.23  4968.6  157.38 4980.11153.7253  4992.3  151.42 5006.87153.7099
  5044.5  156.81  5151.6   159.3  5243.1  162.23  5336.9   161.7  5759.1  167.05
#Mann= 12 ,-1 , 0
  2381.1     .17       0  2570.5     .11       0  2866.9     .17       0
  3756.2     .11       0  4116.2     .17       0  4402.2     .11       0
  4836.4     .17       0  4939.6     .15       0 4980.11     .09       0
 5006.87     .15       0  5044.5     .11       0  5151.6     .17       0
Bank Sta=4980.11,5006.87
XS Rating Curve= 0 ,0
Exp/Cntr=0.3,0.1

Type RM Length L Ch R = 1 ,3624    ,432,432,432
BEGIN DESCRIPTION:
LAKE CREEK TRIBUTARY NO. 2 5.0
END DESCRIPTION:
XS GIS Cut Line= 4
      3794341.07     10091919.43      3794331.04     10090167.96
      3793275.67     10089457.37      3792867.85     10089261.07
#Sta/Elev= 30
  1976.2  167.28  2094.5  162.55  2192.9   156.3  2244.6  152.92  2324.6  151.53
  2414.6  154.53  2574.6  153.85  2784.6   156.4  2934.6  156.29  3224.6  150.93
    3294  151.88  3344.6  154.57  3364.6  152.64  3410.6  153.97  3587.6  152.02
  3801.6  152.14  4361.7  153.46  4447.1  153.58  4548.4  154.55    4563  154.81
  4765.9  152.86  4786.9  154.62  4937.1  154.83 4948.81152.6167  4971.4  149.75
 5033.61152.5893  5234.9  154.75  5286.1  159.73  5325.4  158.06  5452.6     165
#Mann= 12 ,-1 , 0
  1976.2     .17       0  2094.5     .11       0  2192.9     .17       0
    3294     .11       0  3587.6     .17       0  3801.6     .11       0
  4361.7     .17       0  4447.1     .11       0  4548.4     .17       0
    4563     .11       0 4948.81     .07       0 5033.61     .11       0
Bank Sta=4948.81,5033.61
XS Rating Curve= 0 ,0
Exp/Cntr=0.3,0.1

Type RM Length L Ch R = 1 ,3192    ,886,886,886
BEGIN DESCRIPTION:
LAKE CREEK TRIBUTARY NO. 2 4.0
END DESCRIPTION:
XS GIS Cut Line= 4
       3794440.9     10091878.18      3794552.91     10090155.99
      3793329.14     10089037.24      3792817.88     10088961.08
#Sta/Elev= 30
  1616.1  165.96  1689.3   161.4  1787.6  156.75  1956.6  151.44    2261  155.71
  2525.1  154.44  2715.5  149.69  2914.6  151.59    3031  151.82  3370.4  151.94
  3940.1   152.3  3978.9  154.24  4042.5  151.95  4339.7  152.38  4424.8   156.3
  4488.3  155.81  4516.7  151.29  4580.8  151.04  4622.8  155.69  4771.4  150.61
    4793  152.48  4984.2  151.47  4990.9  150.91  4995.5  147.47  5012.2  151.37
  5076.4   151.4  5140.7  155.35    5153  152.97  5212.4  152.56  5516.9  167.18
#Mann= 10 ,-1 , 0
  1616.1     .17       0  1689.3     .11       0  1787.6     .17       0
  2914.6     .11       0    3031     .17       0  3370.4     .15       0
  3940.1     .11       0  4984.2     .06       0  5012.2     .11       0
  5212.4     .17       0
#Block Obstruct= 1 ,-1
  4453.5 4645.55  155.57
Bank Sta=4984.2,5012.2
XS Rating Curve= 0 ,0
Exp/Cntr=0.3,0.1

Type RM Length L Ch R = 1 ,2306    ,0,0,0
BEGIN DESCRIPTION:
LAKE CREEK TRIBUTARY NO. 2 3.0
END DESCRIPTION:
XS GIS Cut Line= 3
      3794462.64     10088679.38      3793161.78     10088460.15
      3792017.82     10088561.07
#Sta/Elev= 30
  3680.8  156.01  3979.7  152.71  4003.3  154.18  4119.3  153.23  4263.7  155.34
  4300.8  153.53  4415.8  153.27  4605.2  149.23    4649  149.06  4669.3  147.39
  4679.5  149.08  4709.9  147.44  4779.8  149.51  4969.1  148.27  4983.7  148.56
  4991.8     146    5014  148.63  5063.3  147.31  5144.5  149.85  5180.4  147.72
  5214.8  150.14  5237.9  149.13  5407.1  148.74  5616.3  148.08  5706.7  150.86
  5726.7  153.38  5776.9  155.95  5857.2   154.9  5957.6  158.08  6148.4   160.3
#Mann= 7 ,-1 , 0
  3680.8     .11       0  4605.2     .15       0  4969.1     .11       0
  4983.7     .07       0    5014     .11       0  5237.9     .15       0
  5407.1     .11       0
Bank Sta=4983.7,5014
XS Rating Curve= 0 ,0
Exp/Cntr=0.3,0.1

Chan Stop Cuts=-1
Use User Specified Reach Order=0
Composite Channel Slope=5