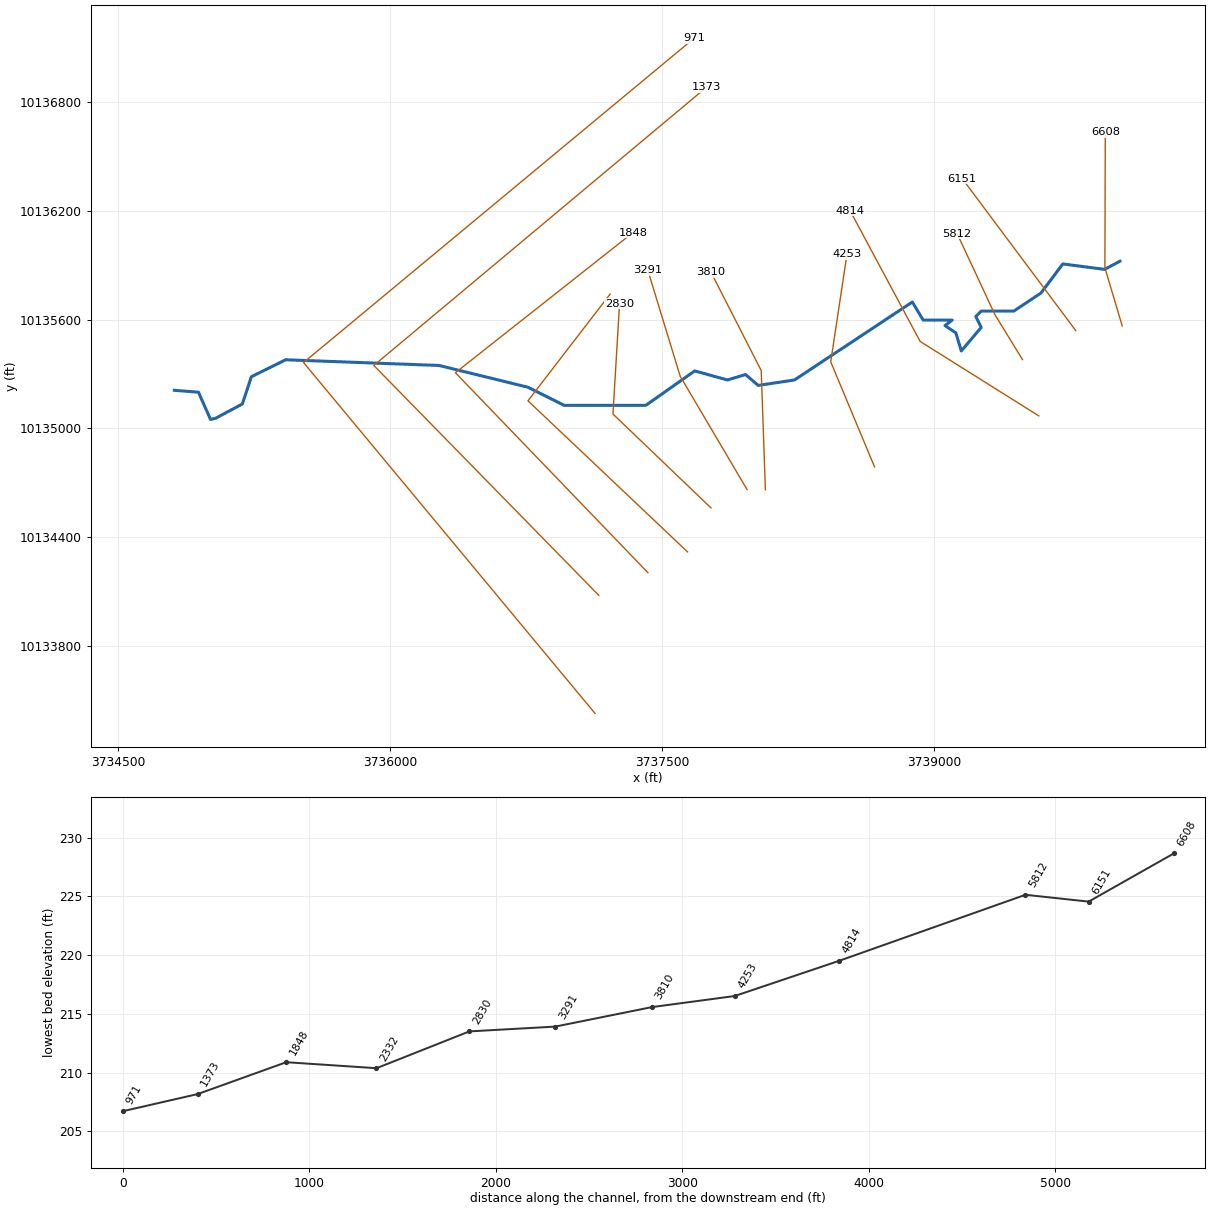
--- LAKE CREEK TRIBUTARY NO 20.prj (project) ---

Proj Title=LAKE CREEK TRIBUTARY NO 20 Base Level Engineering
Current Plan=p01
Default Exp/Contr=0.3,0.1
English Units
Geom File=g01
Flow File=f01
Flow File=f02
Plan File=p01
Y Axis Title=Elevation
X Axis Title(PF)=Main Channel Distance
X Axis Title(XS)=Station
BEGIN DESCRIPTION:
LAKE CREEK TRIBUTARY NO 20
END DESCRIPTION:
DSS Export Rating Curves= 0
DSS Export Rating Curve Sorted= 0
DSS Export Volume Flow Curves= 0
DXF OffsetX= 0
DXF OffsetY= 0
DXF ScaleX= 1
DXF ScaleY= 10

--- LAKE CREEK TRIBUTARY NO 20.p01 (plan) ---

Plan Title=Multiple Run
Short Identifier=Multiple
Geom File=g01
Flow File=f01
Subcritical Flow
K Sum by GR= 0
Std Step Tol= 0.01
Critical Tol= 0.01
Num of Std Step Trials= 20
Max Error Tol= 0.3
Flow Tol Ratio= 0.001
Split Flow NTrial= 30
Split Flow Tol= 0.02
Split Flow Ratio= 0.02
Log Output Level= 0
Friction Slope Method= 1
Unsteady Friction Slope Method= 2
Unsteady Bridges Friction Slope Method= 1
Parabolic Critical Depth
Global Vel Dist=  1 , 1 , 1
Global Log Level= 0
CheckData=True
Encroach Param= -1, 0, 0, 0
BEGIN DESCRIPTION:
Multiple Run
END DESCRIPTION:

--- LAKE CREEK TRIBUTARY NO 20.f01 (steady flow) ---

Flow Title=Multiple
Program Version=4.10
Number of Profiles= 7
Profile Names=10-year,25-year,50-year,1pct_min,100-year,1pct_plu,500-year
River Rch & RM=LAKE CREEK TRIBU,Reach-1         ,6608
     712     972    1320     590    1781    5379    3354
Boundary for River Rch & Prof#=LAKE CREEK TRIBU,Reach-1         , 1
Up Type= 0
Dn Type= 3
Dn Slope=0.005
Boundary for River Rch & Prof#=LAKE CREEK TRIBU,Reach-1         , 2
Up Type= 0
Dn Type= 3
Dn Slope=0.005
Boundary for River Rch & Prof#=LAKE CREEK TRIBU,Reach-1         , 3
Up Type= 0
Dn Type= 3
Dn Slope=0.005
Boundary for River Rch & Prof#=LAKE CREEK TRIBU,Reach-1         , 4
Up Type= 0
Dn Type= 3
Dn Slope=0.005
Boundary for River Rch & Prof#=LAKE CREEK TRIBU,Reach-1         , 5
Up Type= 0
Dn Type= 3
Dn Slope=0.005
Boundary for River Rch & Prof#=LAKE CREEK TRIBU,Reach-1         , 6
Up Type= 0
Dn Type= 3
Dn Slope=0.005
Boundary for River Rch & Prof#=LAKE CREEK TRIBU,Reach-1         , 7
Up Type= 0
Dn Type= 3
Dn Slope=0.005
DSS Import GetInterval= 0
DSS Import GetPeak= 0
DSS Import FillOption= 0

--- LAKE CREEK TRIBUTARY NO 20.f02 (steady flow) ---

Flow Title=Orig_BLE_Flows
Program Version=4.10
Number of Profiles= 7
Profile Names=10-year,25-year,50-year,1pct_min,100-year,1pct_plu,500-year
River Rch & RM=LAKE CREEK TRIBU,Reach-1         ,6608
     712     953    1148     454    1370    4138    1950
Boundary for River Rch & Prof#=LAKE CREEK TRIBU,Reach-1         , 1
Up Type= 0
Dn Type= 3
Dn Slope=0.005
Boundary for River Rch & Prof#=LAKE CREEK TRIBU,Reach-1         , 2
Up Type= 0
Dn Type= 3
Dn Slope=0.005
Boundary for River Rch & Prof#=LAKE CREEK TRIBU,Reach-1         , 3
Up Type= 0
Dn Type= 3
Dn Slope=0.005
Boundary for River Rch & Prof#=LAKE CREEK TRIBU,Reach-1         , 4
Up Type= 0
Dn Type= 3
Dn Slope=0.005
Boundary for River Rch & Prof#=LAKE CREEK TRIBU,Reach-1         , 5
Up Type= 0
Dn Type= 3
Dn Slope=0.005
Boundary for River Rch & Prof#=LAKE CREEK TRIBU,Reach-1         , 6
Up Type= 0
Dn Type= 3
Dn Slope=0.005
Boundary for River Rch & Prof#=LAKE CREEK TRIBU,Reach-1         , 7
Up Type= 0
Dn Type= 3
Dn Slope=0.005
DSS Import GetInterval= 0
DSS Import GetPeak= 0
DSS Import FillOption= 0

--- LAKE CREEK TRIBUTARY NO 20.g01 (geometry) ---

Geom Title=Existing Conditions
Program Version=4.10

River Reach=LAKE CREEK TRIBU,Reach-1
Reach XY= 30
      3740023.23     10135921.84      3739938.23     10135876.84
      3739708.23     10135906.84      3739588.23     10135746.84
      3739438.23     10135646.84      3739258.23     10135646.84
      3739228.23     10135616.84      3739258.23     10135556.84
      3739148.23     10135426.84      3739118.23     10135526.84
      3739058.23     10135566.84      3739098.23     10135596.84
      3738938.23     10135596.84      3738878.23     10135696.84
      3738228.23     10135266.84      3738028.23     10135236.84
      3737958.23     10135296.84      3737858.23     10135266.84
      3737678.23     10135316.84      3737408.23     10135126.84
      3736958.23     10135126.84      3736758.23     10135226.84
      3736268.23     10135346.84      3735421.86     10135378.31
      3735232.62     10135284.55      3735183.18     10135134.52
      3735036.56      10135056.1      3735007.58     10135049.28
      3734941.09      10135199.3      3734808.21     10135209.88

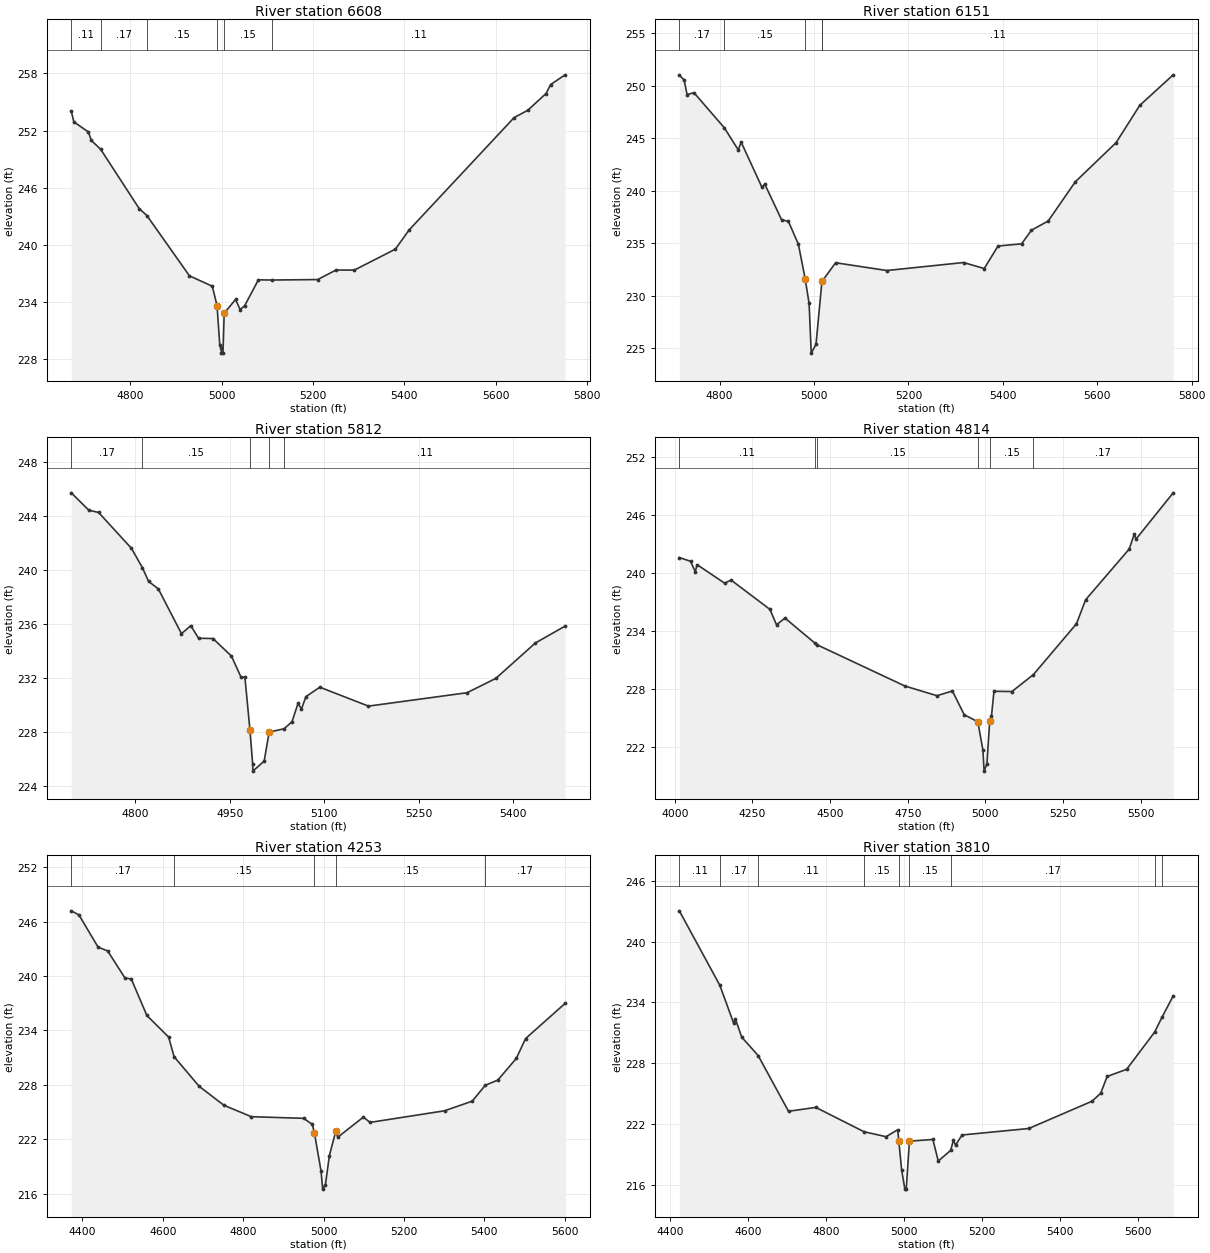
Type RM Length L Ch R = 1 ,6608    ,457,457,457
BEGIN DESCRIPTION:
LAKE CREEK TRIBUTARY NO. 20 11.0
END DESCRIPTION:
XS GIS Cut Line= 3
      3740035.77     10135565.03      3739940.29     10135886.21
      3739942.46     10136632.73
#Sta/Elev= 30
  4670.8  254.06  4676.5  252.92  4708.4  251.85  4714.9  250.96  4735.2  250.04
  4819.7  243.81  4836.6  243.08  4929.7  236.76  4979.7  235.67  4990.1  233.64
  4996.1  229.53  4999.3  229.15  4999.6  228.65  5003.1  228.65  5005.8  232.84
  5030.7  234.28  5040.7  233.22  5050.7  233.63  5080.7  236.34  5110.9  236.32
  5210.7  236.37  5250.7  237.37  5290.7  237.36  5380.7  239.56  5410.7  241.57
  5640.7  253.36  5670.7  254.13  5710.7  255.89  5720.7  256.83  5752.4  257.85
#Mann= 6 ,-1 , 0
  4670.8     .11       0  4735.2     .17       0  4836.6     .15       0
  4990.1     .09       0  5005.8     .15       0  5110.9     .11       0
Bank Sta=4990.1,5005.8
XS Rating Curve= 0 ,0
Exp/Cntr=0.3,0.1

Type RM Length L Ch R = 1 ,6151    ,339,339,339
BEGIN DESCRIPTION:
Mapping XS 964482b2
END DESCRIPTION:
XS GIS Cut Line= 2
      3739779.69       10135539.       3739153.7     10136377.26
#Sta/Elev= 30
  4714.7     251  4724.8  250.54  4731.1  249.15  4745.7  249.33    4810  245.99
  4839.5  243.89  4845.7  244.62  4889.5  240.35  4895.8  240.62  4931.2  237.25
  4945.8  237.08  4966.9  234.91  4981.2  231.64  4989.6  229.28  4994.1  224.55
  5004.2  225.38  5016.8  231.38  5017.3   231.4  5045.8  233.15  5154.1  232.41
  5316.8  233.17  5360.6   232.6  5389.8  234.74  5439.8  234.95  5460.7  236.25
  5496.1  237.12  5553.5  240.85    5640  244.58    5690  248.12  5760.9  251.03
#Mann= 5 ,-1 , 0
  4714.7     .17       0    4810     .15       0  4981.2     .09       0
  5016.8     .15       0  5017.3     .11       0
Bank Sta=4981.2,5016.8
XS Rating Curve= 0 ,0
Exp/Cntr=0.3,0.1

Type RM Length L Ch R = 1 ,5812    ,998,998,998
BEGIN DESCRIPTION:
LAKE CREEK TRIBUTARY NO. 20 10.0
END DESCRIPTION:
XS GIS Cut Line= 3
       3739485.8      10135379.4      3739333.89      10135626.8
      3739125.57     10136073.82
#Sta/Elev= 30
  4698.6  245.72  4726.6  244.43    4742  244.27  4794.2  241.61  4811.5  240.18
  4821.3  239.17  4836.8  238.61  4873.5   235.3  4888.3  235.89  4900.6  234.96
  4923.5  234.94  4952.8  233.64  4968.2  232.06  4974.1  232.09  4982.2  228.14
  4986.5  225.63  4986.7  225.13  5004.7  225.87  5012.6  228.02  5036.1  228.26
  5048.8  228.78  5058.4  230.14  5063.9  229.73  5070.9  230.64  5092.9  231.34
  5170.2  229.94  5326.5  230.93  5372.2  231.99  5434.9  234.61  5482.1  235.86
#Mann= 5 ,-1 , 0
  4698.6     .17       0  4811.5     .15       0  4982.2     .09       0
  5012.6     .15       0  5036.1     .11       0
Bank Sta=4982.2,5012.6
XS Rating Curve= 0 ,0
Exp/Cntr=0.3,0.1

Type RM Length L Ch R = 1 ,4814    ,561,561,561
BEGIN DESCRIPTION:
LAKE CREEK TRIBUTARY NO. 20 9.0
END DESCRIPTION:
XS GIS Cut Line= 3
      3739576.06     10135068.65      3738921.57     10135479.23
      3738535.29     10136199.69
#Sta/Elev= 30
  4014.5  241.64  4050.5  241.25  4065.8  240.18  4071.7   240.9  4160.1  238.99
  4181.3   239.3  4306.2  236.27  4327.4  234.68  4354.7  235.37  4450.8  232.78
  4458.8  232.59    4741  228.33  4844.1  227.33  4893.6  227.82  4931.8  225.36
  4975.6  224.63  4991.9  221.71  4995.8  219.52  5004.8  220.28  5013.8   224.7
  5019.5   225.2  5027.5  227.79  5085.3  227.76  5154.3  229.51  5293.2  234.78
  5322.5  237.26    5463  242.52  5479.2  244.06  5484.9  243.55  5604.6  248.34
#Mann= 6 ,-1 , 0
  4014.5     .11       0  4450.8     .17       0  4458.8     .15       0
  4975.6     .09       0  5013.8     .15       0  5154.3     .17       0
Bank Sta=4975.6,5013.8
XS Rating Curve= 0 ,0
Exp/Cntr=0.3,0.1

Type RM Length L Ch R = 1 ,4253    ,443,443,443
BEGIN DESCRIPTION:
LAKE CREEK TRIBUTARY NO. 20 8.0
END DESCRIPTION:
XS GIS Cut Line= 3
      3738669.83     10134787.39      3738428.23     10135366.84
      3738517.84     10135961.02
#Sta/Elev= 30
  4372.2  247.18  4391.4  246.73    4439  243.18  4462.9  242.76  4506.2  239.76
  4521.4  239.69  4560.4  235.65  4614.5  233.27  4628.1  231.11  4690.4  227.85
    4752  225.76  4820.4   224.5  4950.4  224.32  4972.1  223.65 4977.06222.7469
  4993.7  218.52  4997.8  216.52  5004.7  217.02  5014.4   220.2  5030.3   222.9
  5035.3  222.24  5099.2  224.46  5115.5  223.87  5300.9  225.15  5369.8  226.21
  5402.3  227.96  5433.7  228.54  5479.6  230.93  5502.6  233.11  5600.9  236.98
#Mann= 5 ,-1 , 0
  4372.2     .17       0  4628.1     .15       0 4977.06     .09       0
  5030.3     .15       0  5402.3     .17       0
Bank Sta=4977.06,5030.3
XS Rating Curve= 0 ,0
Exp/Cntr=0.3,0.1

Type RM Length L Ch R = 1 ,3810    ,519,519,519
BEGIN DESCRIPTION:
LAKE CREEK TRIBUTARY NO. 20 7.0
END DESCRIPTION:
XS GIS Cut Line= 3
      3738067.85      10134661.1      3738044.83     10135318.64
      3737767.85     10135861.07
#Sta/Elev= 30
  4423.9  243.03  4527.7  235.69  4562.9  231.99  4567.9  232.34    4584  230.57
    4626  228.76    4704  223.26  4774.1  223.64  4897.8  221.24  4954.2  220.75
  4984.2  221.44 4986.91220.3642  4994.2  217.47  5002.5  215.58    5006  215.58
  5014.2  220.31  5074.3  220.48  5088.2  218.35  5119.9   219.4    5127  220.39
  5132.6  219.92  5149.2  220.92  5320.4  221.56  5482.6  224.25  5504.8  225.03
  5521.4  226.69  5571.5   227.4  5643.3  231.07    5662  232.52  5690.9  234.64
#Mann= 9 ,-1 , 0
  4423.9     .11       0  4527.7     .17       0    4626     .11       0
  4897.8     .15       0 4986.91     .09       0  5014.2     .15       0
  5119.9     .17       0  5643.3     .11       0    5662     .17       0
Bank Sta=4986.91,5014.2
XS Rating Curve= 0 ,0
Exp/Cntr=0.3,0.1

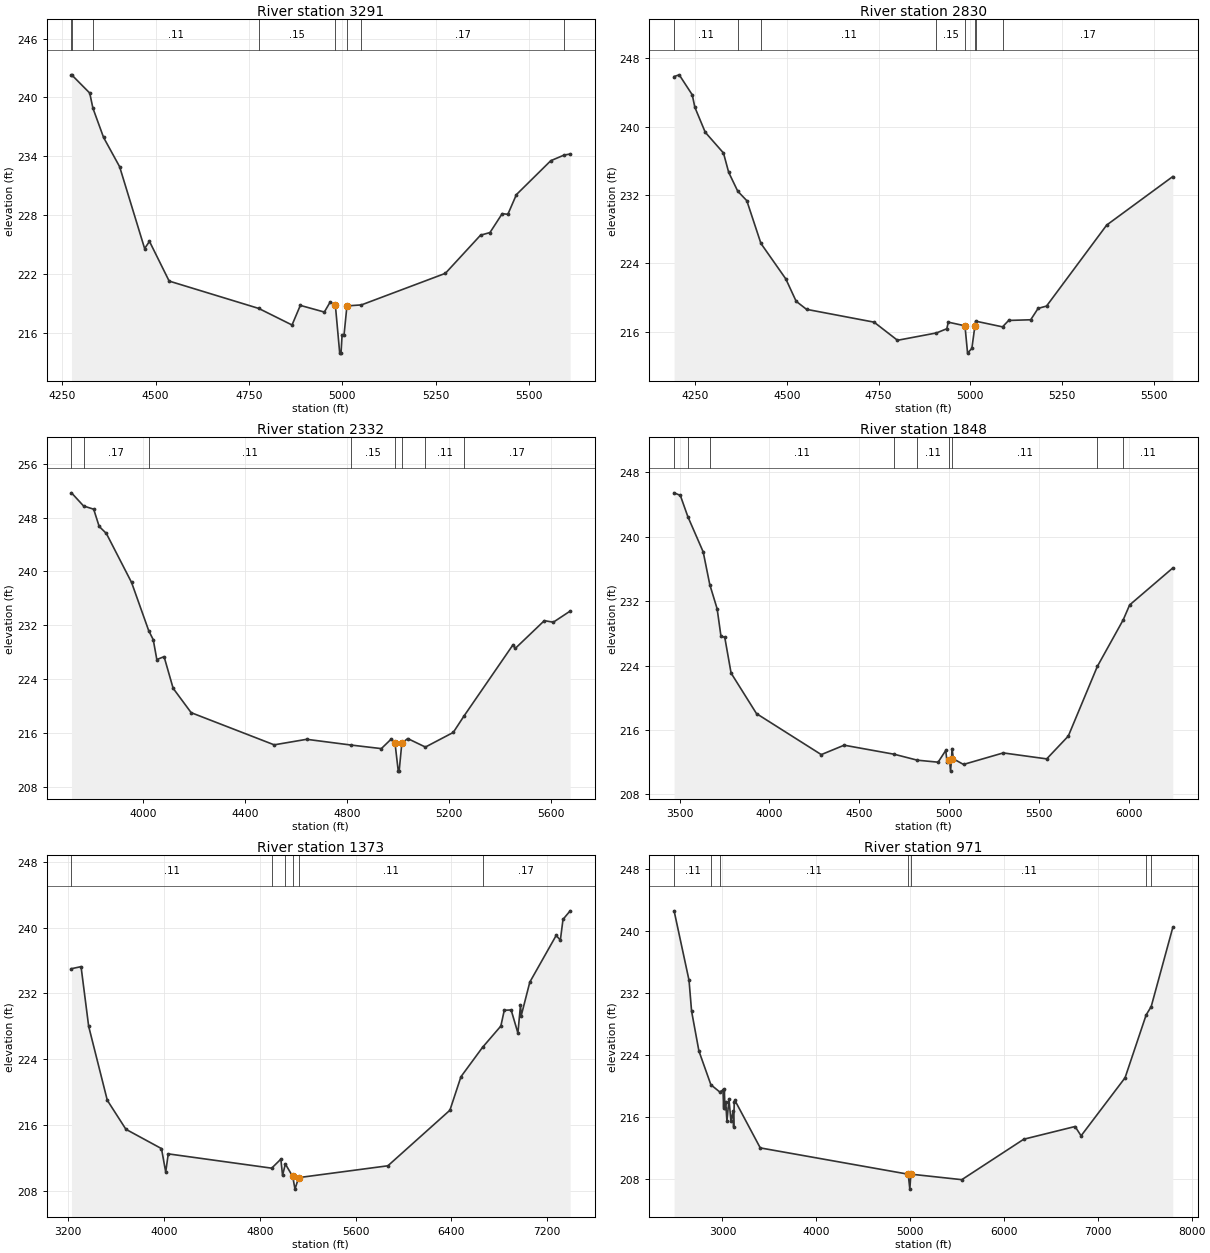
Type RM Length L Ch R = 1 ,3291    ,461,461,461
BEGIN DESCRIPTION:
LAKE CREEK TRIBUTARY NO. 20 6.0
END DESCRIPTION:
XS GIS Cut Line= 3
      3737966.72     10134662.36      3737598.23     10135286.84
      3737419.84      10135870.7
#Sta/Elev= 30
  4274.9  242.31  4275.4  242.31  4323.8  240.45  4332.3  238.91  4360.9  235.92
  4403.8  232.94  4470.8  224.59  4483.8  225.32  4536.5  221.27  4776.4  218.48
  4865.6  216.79  4887.8  218.79  4952.1  218.11  4967.7  219.13  4981.7  218.79
  4993.3  213.92  4996.8  213.92  4999.6  215.75  5004.8  215.75  5012.7218.7383
  5051.5  218.84  5276.3  222.06  5370.4  225.95  5395.7  226.22  5428.5  228.15
  5443.6  228.08  5466.5  230.09  5558.6  233.55  5594.6  234.13  5610.5  234.23
#Mann= 8 ,-1 , 0
  4274.9     .11       0  4275.4     .17       0  4332.3     .11       0
  4776.4     .15       0  4981.7     .09       0  5012.7     .15       0
  5051.5     .17       0  5594.6     .11       0
Bank Sta=4981.7,5012.7
XS Rating Curve= 0 ,0
Exp/Cntr=0.3,0.1

Type RM Length L Ch R = 1 ,2830    ,498,498,498
BEGIN DESCRIPTION:
LAKE CREEK TRIBUTARY NO. 20 5.0
END DESCRIPTION:
XS GIS Cut Line= 3
      3737767.86     10134561.06      3737227.12     10135079.05
      3737263.51     10135687.26
#Sta/Elev= 30
  4193.3  245.84  4207.3  246.04  4242.8   243.7  4249.8  242.25  4278.1  239.33
  4327.8   236.9  4341.9  234.65  4366.6  232.44  4391.3  231.33  4429.8  226.33
  4497.6  222.18  4525.7  219.57  4553.9  218.63  4737.9  217.13  4801.7  215.01
  4907.8  215.87    4936  216.36    4940  217.13 4985.45216.7016  4992.5  213.51
  5004.2  214.06 5012.46216.6689  5014.3  217.25  5087.7  216.58  5104.4  217.33
  5164.5  217.41  5184.6  218.74  5207.6  219.01  5371.4  228.48  5551.4  234.15
#Mann= 8 ,-1 , 0
  4193.3     .11       0  4366.6     .17       0  4429.8     .11       0
  4907.8     .15       0 4985.45     .09       0 5012.46     .12       0
  5014.3     .15       0  5087.7     .17       0
Bank Sta=4985.45,5012.46
XS Rating Curve= 0 ,0
Exp/Cntr=0.3,0.1

Type RM Length L Ch R = 1 ,2332    ,484,484,484
BEGIN DESCRIPTION:
LAKE CREEK TRIBUTARY NO. 20 4.0
END DESCRIPTION:
XS GIS Cut Line= 3
      3737638.61     10134318.61      3736758.37     10135151.97
      3737211.49      10135740.5
#Sta/Elev= 30
  3720.3  251.66  3767.7  249.71  3807.4  249.23  3828.8  246.68  3857.1  245.63
  3955.8  238.37  4023.2   231.2  4040.8  229.88  4054.9  226.93  4083.3  227.36
  4118.8  222.67  4189.5  219.05  4514.9  214.28  4642.3   215.1  4815.8  214.25
    4935  213.72    4974  215.15  4988.5  214.56  5001.3  210.38  5004.8  210.38
 5015.31214.5261  5038.4  215.21  5107.7  213.95  5216.9  216.12  5258.4  218.52
  5451.5  229.14  5459.7  228.57  5573.9   232.7  5609.2  232.47  5675.2  234.12
#Mann= 8 ,-1 , 0
  3720.3     .11       0  3767.7     .17       0  4023.2     .11       0
  4815.8     .15       0  4988.5     .09       0 5015.31     .15       0
  5107.7     .11       0  5258.4     .17       0
Bank Sta=4988.5,5015.31
XS Rating Curve= 0 ,0
Exp/Cntr=0.3,0.1

Type RM Length L Ch R = 1 ,1848    ,475,475,475
BEGIN DESCRIPTION:
LAKE CREEK TRIBUTARY NO. 20 3.0
END DESCRIPTION:
XS GIS Cut Line= 3
      3737419.81     10134204.08      3736358.23     10135306.84
      3737336.48     10136079.04
#Sta/Elev= 30
  3469.3  245.44    3504  245.12  3545.9  242.48  3631.3  238.11    3668  234.05
    3709  231.04  3730.1  227.67  3751.5  227.49  3786.7  223.06  3928.2  218.03
  4288.9  212.94  4416.3  214.11  4696.2  212.98  4823.3  212.25  4939.5     212
    4982  213.46  4989.2  212.05  5002.9  212.31  5008.6  210.89 5014.24 212.352
  5016.8  213.69  5024.8  212.41  5080.9  211.72  5302.2  213.15  5544.2  212.41
  5664.4  215.24  5826.2  223.89  5970.4  229.68    6006  231.52  6246.3  236.11
#Mann= 9 ,-1 , 0
  3469.3     .11       0  3545.9     .17       0    3668     .11       0
  4696.2     .15       0  4823.3     .11       0  5002.9     .06       0
 5014.24     .11       0  5826.2     .17       0  5970.4     .11       0
Bank Sta=5002.9,5014.24
XS Rating Curve= 0 ,0
Exp/Cntr=0.3,0.1

Type RM Length L Ch R = 1 ,1373    ,402,402,402
BEGIN DESCRIPTION:
LAKE CREEK TRIBUTARY NO. 20 2.0
END DESCRIPTION:
XS GIS Cut Line= 3
      3737148.98     10134079.07      3735908.23     10135346.84
      3737742.71     10136881.11
#Sta/Elev= 30
  3226.1     235  3306.1  235.25  3369.7  227.99  3525.3  218.99  3680.9  215.46
  3977.9  213.11  4013.2  210.26  4034.5  212.47  4898.4  210.73    4975  211.83
  4989.2  209.85  5012.5  211.24    5074  209.72    5093  208.18  5123.4  209.58
  5869.1  211.02    6387  217.78  6479.4  221.86  6659.5  225.43  6812.5  228.02
  6841.1  229.94  6898.4  229.98    6955  227.17  6976.5  230.55    6983   229.3
  7054.5  233.37  7274.4  239.04  7309.6  238.48  7331.7     241  7391.5  242.04
#Mann= 6 ,-1 , 0
  3226.1     .11       0  4898.4     .15       0  5012.5     .11       0
    5074     .09       0  5123.4     .11       0  6659.5     .17       0
Bank Sta=5074,5123.4
XS Rating Curve= 0 ,0
Exp/Cntr=0.3,0.1

Type RM Length L Ch R = 1 ,971     ,0,0,0
BEGIN DESCRIPTION:
LAKE CREEK TRIBUTARY NO. 20 1.0
END DESCRIPTION:
XS GIS Cut Line= 3
      3737128.15     10133428.03      3735520.74     10135362.97
      3737673.98     10137151.09
#Sta/Elev= 30
  2484.5  242.63  2643.6  233.67  2670.9  229.68  2749.1  224.54  2876.5  220.19
  2970.6  219.26  3005.6  219.49  3012.1  217.24  3019.9  219.58  3026.4  217.13
  3034.2     218  3047.5   215.5  3069.4  218.31  3090.2  215.53  3112.4  216.74
  3118.9  214.74  3125.5  217.91  3133.2  218.16  3402.7  212.04 4979.45208.6448
  4996.6  206.72 5007.74208.6516  5550.7  207.94  6210.9  213.16  6757.8   214.8
  6821.6   213.6  7290.3  221.09  7515.1   229.2  7568.7  230.27  7798.9  240.48
#Mann= 7 ,-1 , 0
  2484.5     .11       0  2876.5     .17       0  2970.6     .11       0
 4979.45     .06       0 5007.74     .11       0  7515.1     .17       0
  7568.7     .11       0
Bank Sta=4979.45,5007.74
XS Rating Curve= 0 ,0
Exp/Cntr=0.3,0.1

Chan Stop Cuts=-1
Use User Specified Reach Order=0
Composite Channel Slope=5