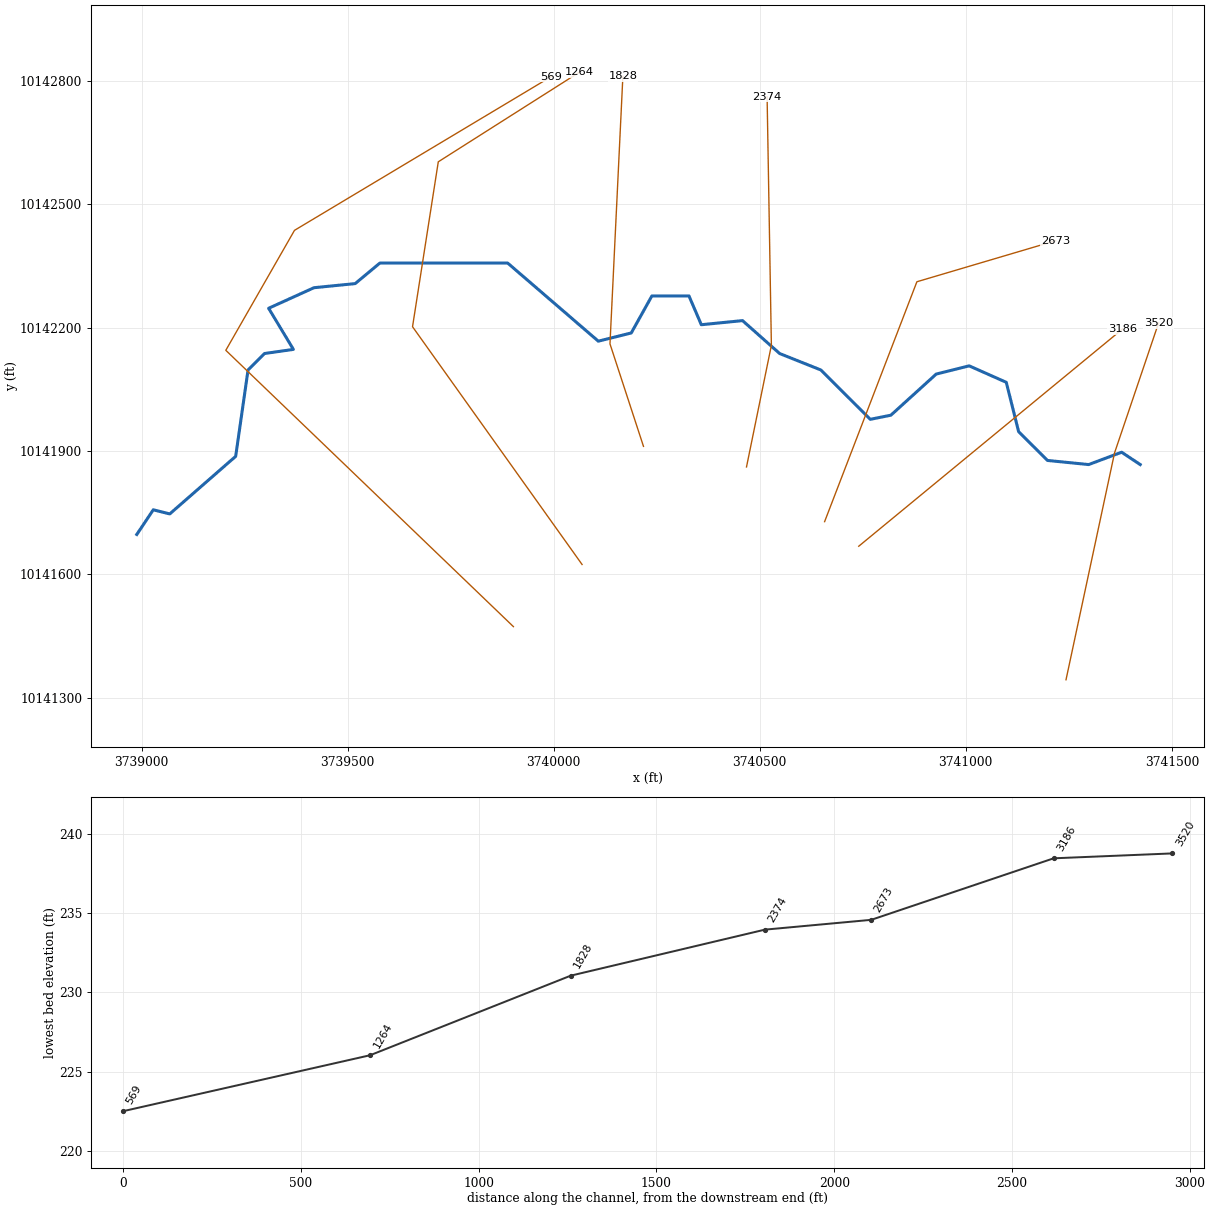
--- LAKE CREEK TRIBUTARY NO 21 1.prj (project) ---

Proj Title=LAKE CREEK TRIBUTARY NO 21 1 Base Level Engineering
Current Plan=p01
Default Exp/Contr=0.3,0.1
English Units
Geom File=g01
Flow File=f01
Flow File=f02
Plan File=p01
Y Axis Title=Elevation
X Axis Title(PF)=Main Channel Distance
X Axis Title(XS)=Station
BEGIN DESCRIPTION:
LAKE CREEK TRIBUTARY NO 21 1
END DESCRIPTION:
DSS Export Rating Curves= 0
DSS Export Rating Curve Sorted= 0
DSS Export Volume Flow Curves= 0
DXF OffsetX= 0
DXF OffsetY= 0
DXF ScaleX= 1
DXF ScaleY= 10

--- LAKE CREEK TRIBUTARY NO 21 1.p01 (plan) ---

Plan Title=Multiple Run
Short Identifier=Multiple
Geom File=g01
Flow File=f01
Subcritical Flow
K Sum by GR= 0
Std Step Tol= 0.01
Critical Tol= 0.01
Num of Std Step Trials= 20
Max Error Tol= 0.3
Flow Tol Ratio= 0.001
Split Flow NTrial= 30
Split Flow Tol= 0.02
Split Flow Ratio= 0.02
Log Output Level= 0
Friction Slope Method= 1
Unsteady Friction Slope Method= 2
Unsteady Bridges Friction Slope Method= 1
Parabolic Critical Depth
Global Vel Dist=  1 , 1 , 1
Global Log Level= 0
CheckData=True
Encroach Param= -1, 0, 0, 0
BEGIN DESCRIPTION:
Multiple Run
END DESCRIPTION:

--- LAKE CREEK TRIBUTARY NO 21 1.f01 (steady flow) ---

Flow Title=Multiple
Program Version=4.10
Number of Profiles= 7
Profile Names=10-year,25-year,50-year,1pct_min,100-year,1pct_plu,500-year
River Rch & RM=LAKE CREEK TRIBU,Reach-1         ,3520
     819    1136    1563     707    2136    6451    4126
Boundary for River Rch & Prof#=LAKE CREEK TRIBU,Reach-1         , 1
Up Type= 0
Dn Type= 3
Dn Slope=0.005
Boundary for River Rch & Prof#=LAKE CREEK TRIBU,Reach-1         , 2
Up Type= 0
Dn Type= 3
Dn Slope=0.005
Boundary for River Rch & Prof#=LAKE CREEK TRIBU,Reach-1         , 3
Up Type= 0
Dn Type= 3
Dn Slope=0.005
Boundary for River Rch & Prof#=LAKE CREEK TRIBU,Reach-1         , 4
Up Type= 0
Dn Type= 3
Dn Slope=0.005
Boundary for River Rch & Prof#=LAKE CREEK TRIBU,Reach-1         , 5
Up Type= 0
Dn Type= 3
Dn Slope=0.005
Boundary for River Rch & Prof#=LAKE CREEK TRIBU,Reach-1         , 6
Up Type= 0
Dn Type= 3
Dn Slope=0.005
Boundary for River Rch & Prof#=LAKE CREEK TRIBU,Reach-1         , 7
Up Type= 0
Dn Type= 3
Dn Slope=0.005
DSS Import GetInterval= 0
DSS Import GetPeak= 0
DSS Import FillOption= 0

--- LAKE CREEK TRIBUTARY NO 21 1.f02 (steady flow) ---

Flow Title=Orig_BLE_Flows
Program Version=4.10
Number of Profiles= 7
Profile Names=10-year,25-year,50-year,1pct_min,100-year,1pct_plu,500-year
River Rch & RM=LAKE CREEK TRIBU,Reach-1         ,3520
     819    1114    1359     544    1643    4962    2399
Boundary for River Rch & Prof#=LAKE CREEK TRIBU,Reach-1         , 1
Up Type= 0
Dn Type= 3
Dn Slope=0.005
Boundary for River Rch & Prof#=LAKE CREEK TRIBU,Reach-1         , 2
Up Type= 0
Dn Type= 3
Dn Slope=0.005
Boundary for River Rch & Prof#=LAKE CREEK TRIBU,Reach-1         , 3
Up Type= 0
Dn Type= 3
Dn Slope=0.005
Boundary for River Rch & Prof#=LAKE CREEK TRIBU,Reach-1         , 4
Up Type= 0
Dn Type= 3
Dn Slope=0.005
Boundary for River Rch & Prof#=LAKE CREEK TRIBU,Reach-1         , 5
Up Type= 0
Dn Type= 3
Dn Slope=0.005
Boundary for River Rch & Prof#=LAKE CREEK TRIBU,Reach-1         , 6
Up Type= 0
Dn Type= 3
Dn Slope=0.005
Boundary for River Rch & Prof#=LAKE CREEK TRIBU,Reach-1         , 7
Up Type= 0
Dn Type= 3
Dn Slope=0.005
DSS Import GetInterval= 0
DSS Import GetPeak= 0
DSS Import FillOption= 0

--- LAKE CREEK TRIBUTARY NO 21 1.g01 (geometry) ---

Geom Title=Existing Conditions
Program Version=4.10

River Reach=LAKE CREEK TRIBU,Reach-1
Reach XY= 30
      3741423.23     10141866.84      3741378.23     10141896.84
      3741298.23     10141866.84      3741198.23     10141876.84
      3741128.23     10141946.84      3741098.23     10142066.84
      3741008.23     10142106.84      3740928.23     10142086.84
      3740818.23     10141986.84      3740768.23     10141976.84
      3740648.23     10142096.84      3740548.23     10142136.84
      3740458.23     10142216.84      3740358.23     10142206.84
      3740328.23     10142276.84      3740238.23     10142276.84
      3740188.23     10142186.84      3740108.23     10142166.84
      3739888.23     10142356.84      3739578.23     10142356.84
      3739518.23     10142306.84      3739418.23     10142296.84
      3739308.23     10142246.84      3739368.23     10142146.84
      3739298.23     10142136.84      3739258.23     10142096.84
      3739228.23     10141886.84      3739068.23     10141746.84
      3739028.23     10141756.84      3738988.23     10141696.84

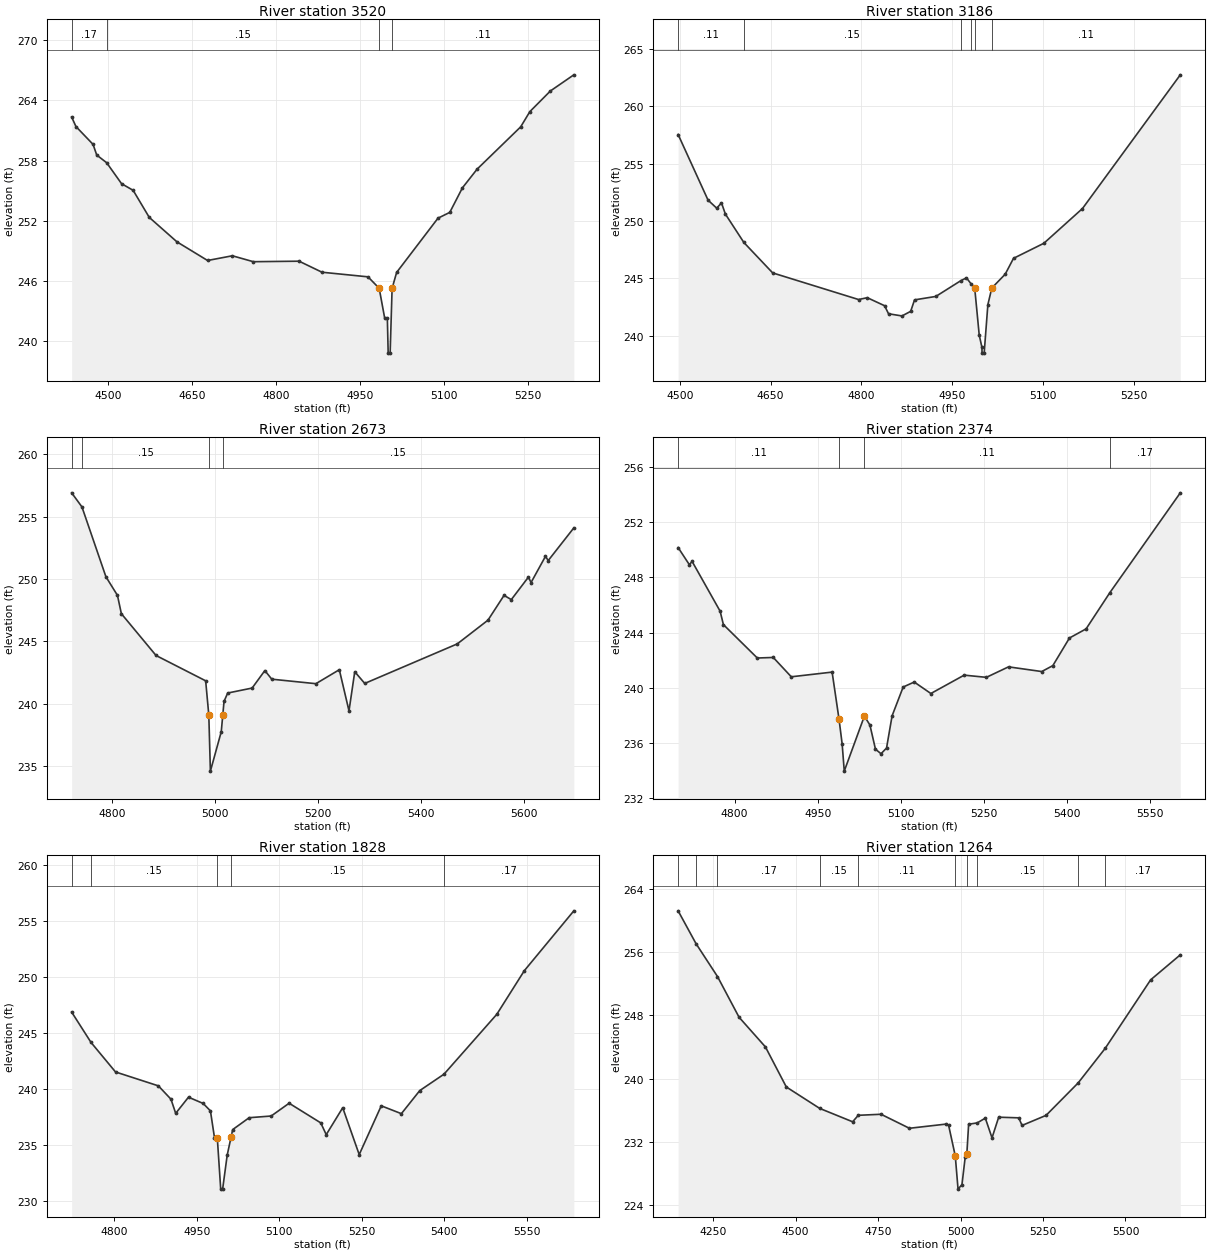
Type RM Length L Ch R = 1 ,3520    ,334,334,334
BEGIN DESCRIPTION:
LAKE CREEK TRIBUTARY NO. 21. 1 5.0
END DESCRIPTION:
XS GIS Cut Line= 3
      3741243.22     10141343.57      3741361.05     10141895.33
      3741467.85     10142211.06
#Sta/Elev= 30
  4434.2  262.34  4441.9  261.39  4472.5  259.61    4479  258.55  4496.8  257.78
  4523.4  255.69  4544.1  255.03  4572.9  252.33  4622.4  249.89  4677.1  248.03
  4721.4   248.5  4758.9  247.91  4840.7  247.96  4881.6  246.86  4963.8   246.4
  4983.8  245.26  4993.7  242.27  4998.4  242.27  4999.9  238.79  5003.4  238.79
  5006.9  245.25    5015  246.84  5088.9  252.25    5110  252.83  5132.6  255.28
  5158.8  257.14  5236.7  261.36  5253.1  262.88  5289.8  264.94  5331.7  266.55
#Mann= 4 ,-1 , 0
  4434.2     .17       0  4496.8     .15       0  4983.8     .07       0
  5006.9     .11       0
Bank Sta=4983.8,5006.9
XS Rating Curve= 0 ,0
Exp/Cntr=0.3,0.1

Type RM Length L Ch R = 1 ,3186    ,513,513,513
BEGIN DESCRIPTION:
Mapping XS b0249269
END DESCRIPTION:
XS GIS Cut Line= 2
      3740740.25     10141668.27      3741380.53     10142196.57
#Sta/Elev= 30
    4497  257.53  4546.5  251.81  4560.8  251.11  4568.7  251.57  4575.1   250.6
  4605.7  248.12  4653.3  245.47  4795.3  243.15  4809.7  243.31  4838.3  242.61
  4844.8  241.91    4867  241.72  4881.4  242.12  4887.8  243.12    4923  243.42
  4964.2  244.79  4973.6  245.04  4981.8  244.48  4987.2  244.18  4994.7  240.06
  4999.2  238.98  4999.4  238.48  5002.9  238.48    5009   242.7  5015.5  244.15
  5037.7  245.36  5051.4  246.74  5101.5  248.05  5165.4  251.08  5327.1  262.73
#Mann= 6 ,-1 , 0
    4497     .11       0  4605.7     .15       0  4964.2     .17       0
  4981.8     .11       0  4987.2     .07       0  5015.5     .11       0
Bank Sta=4987.2,5015.5
XS Rating Curve= 0 ,0
Exp/Cntr=0.3,0.1

Type RM Length L Ch R = 1 ,2673    ,299,299,299
BEGIN DESCRIPTION:
LAKE CREEK TRIBUTARY NO. 21. 1 4.0
END DESCRIPTION:
XS GIS Cut Line= 3
      3740657.39       10141728.      3740881.35     10142311.33
      3741217.83     10142411.07
#Sta/Elev= 30
  4721.6   256.9  4741.6  255.77  4788.2  250.17  4810.6  248.68  4818.2  247.21
  4885.6  243.86    4982  241.83 4988.11239.0853  4991.2  234.59  5012.3  237.75
 5015.23239.0685  5017.7  240.18  5024.8  240.85  5072.3  241.25    5097  242.65
  5110.5  241.96  5196.2   241.6  5241.7  242.72  5260.5  239.42  5271.7  242.56
  5291.1  241.62  5470.9  244.79  5530.5  246.69  5561.8  248.68  5575.9  248.34
  5609.1  250.14  5614.3  249.71  5642.3  251.81  5647.6  251.47  5697.4  254.09
#Mann= 4 ,-1 , 0
  4721.6     .11       0  4741.6     .15       0 4988.11     .09       0
 5015.23     .15       0
Bank Sta=4988.11,5015.23
XS Rating Curve= 0 ,0
Exp/Cntr=0.3,0.1

Type RM Length L Ch R = 1 ,2374    ,546,546,546
BEGIN DESCRIPTION:
LAKE CREEK TRIBUTARY NO. 21. 1 3.0
END DESCRIPTION:
XS GIS Cut Line= 3
      3740467.85     10141861.04      3740528.23     10142156.84
      3740517.85     10142761.06
#Sta/Elev= 30
  4698.1  250.16  4718.3  248.92  4723.4  249.15  4773.9  245.55  4779.8  244.58
    4841  242.16  4869.8   242.2  4902.3   240.8    4976  241.14  4988.5237.7188
  4994.1  235.94  4997.9  233.97  5034.2  237.95  5044.2  237.31  5054.2  235.56
  5064.2  235.23  5074.2  235.64  5084.2  237.97  5104.2  240.06  5124.2  240.42
  5154.2  239.59  5214.3  240.92  5254.3  240.76  5294.3  241.52  5354.3  241.18
  5374.3  241.61  5404.3  243.61  5434.3  244.27  5477.3   246.9  5604.3  254.12
#Mann= 4 ,-1 , 0
  4698.1     .11       0  4988.5     .06       0  5034.2     .11       0
  5477.3     .17       0
Bank Sta=4988.5,5034.2
XS Rating Curve= 0 ,0
Exp/Cntr=0.3,0.1

Type RM Length L Ch R = 1 ,1828    ,564,564,564
BEGIN DESCRIPTION:
LAKE CREEK TRIBUTARY NO. 21. 1 2.0
END DESCRIPTION:
XS GIS Cut Line= 3
      3740217.85     10141911.06      3740136.55     10142160.29
      3740167.85     10142811.09
#Sta/Elev= 30
  4722.2  246.85  4757.5  244.14    4802  241.51    4880  240.27  4902.9  239.08
  4911.5  237.82  4934.8  239.26  4961.5   238.7  4974.7  238.04  4982.1  235.64
  4987.2  235.64  4993.4  231.06  4996.9  231.06  5005.2  234.09 5012.14235.6723
  5015.2  236.37  5045.2  237.43  5085.2  237.58  5117.9  238.72  5175.4  236.97
  5185.4  235.92  5215.4  238.32  5245.4  234.14  5285.5  238.49  5322.1  237.79
  5355.6  239.85  5399.6  241.31  5495.7  246.65  5545.8  250.54  5635.9  255.88
#Mann= 5 ,-1 , 0
  4722.2     .17       0  4757.5     .15       0  4987.2     .09       0
 5012.14     .15       0  5399.6     .17       0
Bank Sta=4987.2,5012.14
XS Rating Curve= 0 ,0
Exp/Cntr=0.3,0.1

Type RM Length L Ch R = 1 ,1264    ,695,695,695
BEGIN DESCRIPTION:
Mapping XS 12226fe7
END DESCRIPTION:
XS GIS Cut Line= 4
      3740068.83     10141623.86      3739657.39     10142201.96
      3739719.89       10142603.      3740063.22     10142821.48
#Sta/Elev= 30
  4143.8   261.2    4198  257.06  4263.1   252.9  4328.6  247.75  4408.5     244
  4471.8  238.94  4573.1  236.23  4672.9  234.54  4689.9  235.36    4759  235.49
    4845  233.72  4956.3  234.25  4963.8   234.1    4984  230.23  4992.4  226.03
  5004.3   226.6    5014  230.04  5019.1   230.5  5024.5  234.23  5050.5   234.4
  5075.1     235  5095.4  232.51  5115.6  235.12  5176.3  235.04  5186.5  234.08
  5259.2  235.35  5356.5  239.45  5438.3  243.81  5576.3  252.48  5666.2  255.64
#Mann= 10 ,-1 , 0
  4143.8     .17       0    4198     .11       0  4263.1     .17       0
  4573.1     .15       0  4689.9     .11       0    4984     .07       0
  5019.1     .11       0  5050.5     .15       0  5356.5     .11       0
  5438.3     .17       0
Bank Sta=4984,5019.1
XS Rating Curve= 0 ,0
Exp/Cntr=0.3,0.1

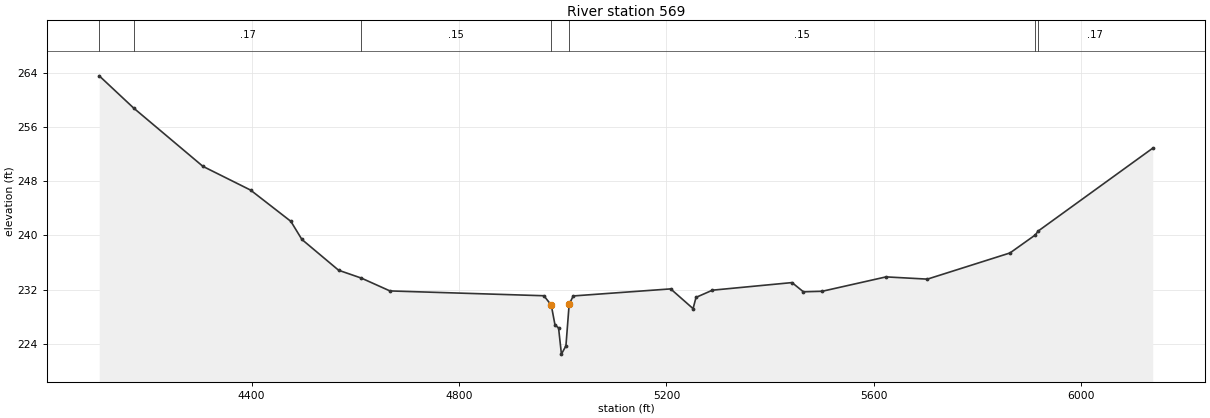
Type RM Length L Ch R = 1 ,569     ,0,0,0
BEGIN DESCRIPTION:
LAKE CREEK TRIBUTARY NO. 21. 1 1.0
END DESCRIPTION:
XS GIS Cut Line= 4
      3739902.21     10141472.76      3739204.26     10142144.66
      3739370.93     10142436.33      3739994.38      10142810.4
#Sta/Elev= 30
  4106.1  263.53  4172.5  258.78  4306.1  250.18    4398  246.68  4475.7  242.07
    4497   239.4  4567.8  234.86  4611.7   233.7  4666.8  231.81  4963.7   231.1
  4977.9  229.72  4985.1   226.8    4992  226.35  4997.5  222.49  5006.2  223.71
 5012.41 229.834  5020.3  231.07  5208.2  232.11  5251.4   229.2  5257.1  230.86
  5288.8  231.92  5442.2  233.04  5464.2  231.68  5500.5  231.76  5623.6  233.88
  5703.3  233.55  5862.6  237.41  5911.7  240.08  5916.6  240.62  6137.9  252.86
#Mann= 7 ,-1 , 0
  4106.1     .11       0  4172.5     .17       0  4611.7     .15       0
  4977.9     .06       0 5012.41     .15       0  5911.7     .11       0
  5916.6     .17       0
Bank Sta=4977.9,5012.41
XS Rating Curve= 0 ,0
Exp/Cntr=0.3,0.1

Chan Stop Cuts=-1
Use User Specified Reach Order=0
Composite Channel Slope=5