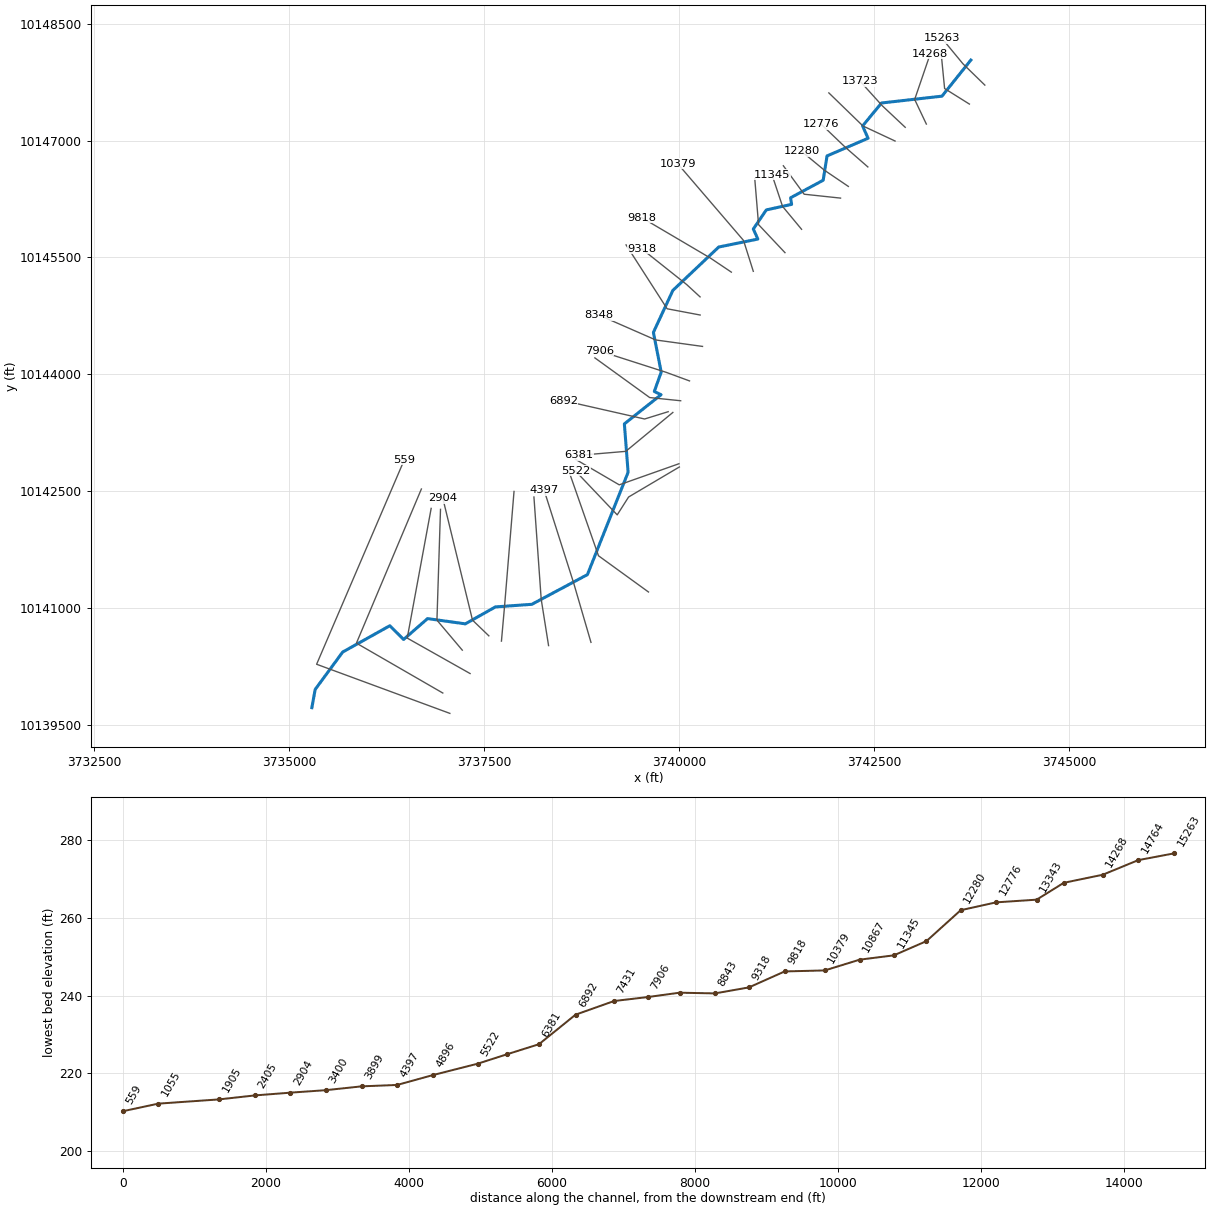
--- LAKE CREEK TRIBUTARY NO 21.prj (project) ---

Proj Title=LAKE CREEK TRIBUTARY NO 21 Base Level Engineering
Current Plan=p01
Default Exp/Contr=0.3,0.1
English Units
Geom File=g01
Flow File=f01
Flow File=f02
Plan File=p01
Y Axis Title=Elevation
X Axis Title(PF)=Main Channel Distance
X Axis Title(XS)=Station
BEGIN DESCRIPTION:
LAKE CREEK TRIBUTARY NO 21
END DESCRIPTION:
DSS Export Rating Curves= 0
DSS Export Rating Curve Sorted= 0
DSS Export Volume Flow Curves= 0
DXF OffsetX= 0
DXF OffsetY= 0
DXF ScaleX= 1
DXF ScaleY= 10

--- LAKE CREEK TRIBUTARY NO 21.p01 (plan) ---

Plan Title=Multiple Run
Short Identifier=Multiple
Geom File=g01
Flow File=f01
Subcritical Flow
K Sum by GR= 0
Std Step Tol= 0.01
Critical Tol= 0.01
Num of Std Step Trials= 20
Max Error Tol= 0.3
Flow Tol Ratio= 0.001
Split Flow NTrial= 30
Split Flow Tol= 0.02
Split Flow Ratio= 0.02
Log Output Level= 0
Friction Slope Method= 1
Unsteady Friction Slope Method= 2
Unsteady Bridges Friction Slope Method= 1
Parabolic Critical Depth
Global Vel Dist=  1 , 1 , 1
Global Log Level= 0
CheckData=True
Encroach Param= -1, 0, 0, 0
BEGIN DESCRIPTION:
Multiple Run
END DESCRIPTION:

--- LAKE CREEK TRIBUTARY NO 21.f01 (steady flow) ---

Flow Title=Multiple
Program Version=4.10
Number of Profiles= 7
Profile Names=10-year,25-year,50-year,1pct_min,100-year,1pct_plu,500-year
River Rch & RM=LAKE CREEK TRIBU,Reach-1         ,15263
     708     964    1309     584    1764    5327    3313
River Rch & RM=LAKE CREEK TRIBU,Reach-1         ,9318
     861    1181    1610     721    2176    6571    4113
River Rch & RM=LAKE CREEK TRIBU,Reach-1         ,4896
    1362    1910    2642    1198    3618   10926    7026
Boundary for River Rch & Prof#=LAKE CREEK TRIBU,Reach-1         , 1
Up Type= 0
Dn Type= 3
Dn Slope=0.005
Boundary for River Rch & Prof#=LAKE CREEK TRIBU,Reach-1         , 2
Up Type= 0
Dn Type= 3
Dn Slope=0.005
Boundary for River Rch & Prof#=LAKE CREEK TRIBU,Reach-1         , 3
Up Type= 0
Dn Type= 3
Dn Slope=0.005
Boundary for River Rch & Prof#=LAKE CREEK TRIBU,Reach-1         , 4
Up Type= 0
Dn Type= 3
Dn Slope=0.005
Boundary for River Rch & Prof#=LAKE CREEK TRIBU,Reach-1         , 5
Up Type= 0
Dn Type= 3
Dn Slope=0.005
Boundary for River Rch & Prof#=LAKE CREEK TRIBU,Reach-1         , 6
Up Type= 0
Dn Type= 3
Dn Slope=0.005
Boundary for River Rch & Prof#=LAKE CREEK TRIBU,Reach-1         , 7
Up Type= 0
Dn Type= 3
Dn Slope=0.005
DSS Import GetInterval= 0
DSS Import GetPeak= 0
DSS Import FillOption= 0

--- LAKE CREEK TRIBUTARY NO 21.f02 (steady flow) ---

Flow Title=Orig_BLE_Flows
Program Version=4.10
Number of Profiles= 7
Profile Names=10-year,25-year,50-year,1pct_min,100-year,1pct_plu,500-year
River Rch & RM=LAKE CREEK TRIBU,Reach-1         ,15263
     708     945    1138     449    1357    4097    1926
River Rch & RM=LAKE CREEK TRIBU,Reach-1         ,9318
     861    1158    1400     554    1674    5054    2391
River Rch & RM=LAKE CREEK TRIBU,Reach-1         ,4896
    1362    1873    2297     922    2783    8405    4085
Boundary for River Rch & Prof#=LAKE CREEK TRIBU,Reach-1         , 1
Up Type= 0
Dn Type= 3
Dn Slope=0.005
Boundary for River Rch & Prof#=LAKE CREEK TRIBU,Reach-1         , 2
Up Type= 0
Dn Type= 3
Dn Slope=0.005
Boundary for River Rch & Prof#=LAKE CREEK TRIBU,Reach-1         , 3
Up Type= 0
Dn Type= 3
Dn Slope=0.005
Boundary for River Rch & Prof#=LAKE CREEK TRIBU,Reach-1         , 4
Up Type= 0
Dn Type= 3
Dn Slope=0.005
Boundary for River Rch & Prof#=LAKE CREEK TRIBU,Reach-1         , 5
Up Type= 0
Dn Type= 3
Dn Slope=0.005
Boundary for River Rch & Prof#=LAKE CREEK TRIBU,Reach-1         , 6
Up Type= 0
Dn Type= 3
Dn Slope=0.005
Boundary for River Rch & Prof#=LAKE CREEK TRIBU,Reach-1         , 7
Up Type= 0
Dn Type= 3
Dn Slope=0.005
DSS Import GetInterval= 0
DSS Import GetPeak= 0
DSS Import FillOption= 0

--- LAKE CREEK TRIBUTARY NO 21.g01 (geometry) ---

Geom Title=Existing Conditions
Program Version=4.10

River Reach=LAKE CREEK TRIBU,Reach-1
Reach XY= 30
      3743738.23     10148031.84      3743368.29     10147569.07
       3742593.5     10147481.66      3742350.48     10147186.98
      3742420.52     10147028.91      3741894.57     10146802.35
      3741845.12     10146490.19      3741427.48     10146265.35
      3741440.31     10146180.71      3741115.91     10146109.73
      3740949.34     10145864.31      3741007.36     10145735.61
      3740505.94     10145633.45      3739917.68     10145076.78
      3739668.22     10144537.85      3739768.34     10144029.05
      3739679.53     10143779.93      3739766.62      10143738.7
      3739295.87     10143364.38      3739344.02     10142743.74
      3738822.19      10141430.1      3738109.52     10141049.17
      3737642.88     10141015.84      3737257.05     10140798.37
      3736772.99     10140866.03      3736465.32     10140598.35
      3736288.75     10140774.24      3735683.88     10140436.51
      3735331.69     10139956.77      3735289.25     10139722.95

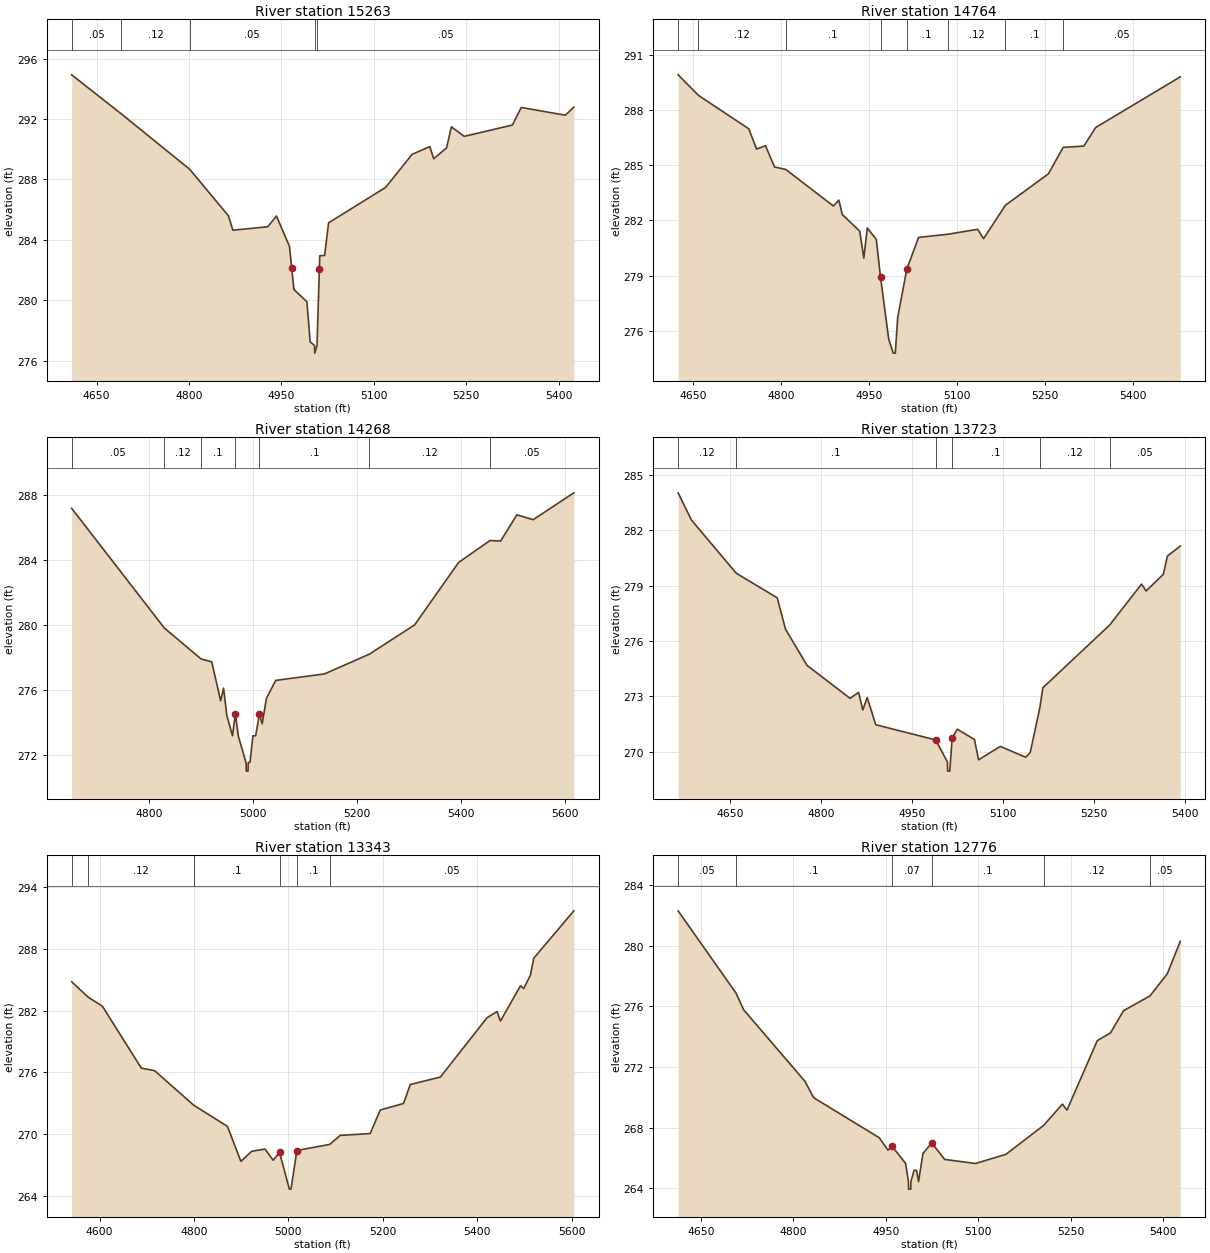
Type RM Length L Ch R = 1 ,15263   ,499,499,499
BEGIN DESCRIPTION:
LAKE CREEK TRIBUTARY NO. 21 29.0
END DESCRIPTION:
XS GIS Cut Line= 3
      3743917.88     10147711.05      3743638.08     10147983.45
      3743367.84     10148311.08
#Sta/Elev= 30
  4609.5  294.92  4689.7  292.35  4801.2  288.67  4864.1  285.59  4871.2  284.64
  4927.8  284.87    4942  285.58  4963.1  283.57  4966.7282.1449  4970.3  280.72
  4991.4  279.91  4996.7  277.26  5003.8  277.01  5004.1  276.51  5007.8  277.01
 5011.66282.1057  5012.3  282.95  5020.1  282.97  5026.6  285.13  5119.1  287.47
  5162.2  289.66  5190.8  290.17  5197.3  289.37  5218.1  290.09    5226  291.48
  5246.8  290.85    5325   291.6  5339.3  292.76    5411  292.25  5424.7  292.78
#Mann= 5 ,-1 , 0
  4609.5     .05       0  4689.7     .12       0  4801.2     .05       0
  5003.8     .05       0  5007.8     .05       0
Bank Sta=4966.7,5011.66
XS Rating Curve= 0 ,0
Exp/Cntr=0.3,0.1

Type RM Length L Ch R = 1 ,14764   ,496,496,496
BEGIN DESCRIPTION:
LAKE CREEK TRIBUTARY NO. 21 28.0
END DESCRIPTION:
XS GIS Cut Line= 3
      3743719.92     10147467.56      3743402.05     10147666.71
      3743355.31     10148144.63
#Sta/Elev= 30
  4624.9  289.93  4659.6  288.81  4745.3  286.99  4758.5  285.89  4773.8  286.07
  4789.1  284.91  4808.2  284.78  4889.3  282.79  4898.7  283.11  4904.6  282.32
  4934.2  281.42  4941.2  279.95  4947.1  281.59  4962.4  280.97  4969.6  278.92
  4983.6  275.54  4991.3  274.78  4994.8  274.78  4998.9  276.72  5014.4  279.35
  5034.5  281.08  5083.9  281.25    5135  281.52  5145.1  281.01  5182.3  282.83
  5255.6  284.54  5280.7  285.98  5315.9  286.05    5336  287.06  5480.2  289.82
#Mann= 8 ,-1 , 0
  4624.9     .05       0  4659.6     .12       0  4808.2      .1       0
  4969.6     .07       0  5014.4      .1       0  5083.9     .12       0
  5182.3      .1       0  5280.7     .05       0
Bank Sta=4969.6,5014.4
XS Rating Curve= 0 ,0
Exp/Cntr=0.3,0.1

Type RM Length L Ch R = 1 ,14268   ,545,545,545
BEGIN DESCRIPTION:
LAKE CREEK TRIBUTARY NO. 21 27.0
END DESCRIPTION:
XS GIS Cut Line= 3
      3743167.84      10147211.1      3743018.15      10147526.7
      3743217.87     10148111.12
#Sta/Elev= 30
  4650.7  287.17  4829.1  279.82  4899.8  277.92  4920.4  277.74  4937.6  275.35
  4943.2  276.13  4949.5  274.44  4960.4   273.2  4965.9  274.56  4971.6  273.18
  4986.6  271.53  4986.9  271.03  4990.4  271.03  4990.6  271.53  4994.2  271.59
  4999.7   273.2    5005   273.2  5012.2  274.54  5017.5  273.94  5025.8   275.5
  5043.5   276.6  5137.5     277  5223.8  278.21  5311.1  280.01  5395.6  283.84
  5456.1  285.19  5476.6  285.16    5508  286.77  5539.3  286.47  5617.6  288.12
#Mann= 7 ,-1 , 0
  4650.7     .05       0  4829.1     .12       0  4899.8      .1       0
  4965.9     .07       0  5012.2      .1       0  5223.8     .12       0
  5456.1     .05       0
Bank Sta=4965.9,5012.2
XS Rating Curve= 0 ,0
Exp/Cntr=0.3,0.1

Type RM Length L Ch R = 1 ,13723   ,380,380,380
BEGIN DESCRIPTION:
LAKE CREEK TRIBUTARY NO. 21 26.0
END DESCRIPTION:
XS GIS Cut Line= 3
      3742897.01     10147169.41       3742603.5     10147445.27
      3742317.86     10147761.06
#Sta/Elev= 30
  4563.7  284.02  4585.6  282.55  4659.6  279.67  4727.2  278.34  4740.9  276.64
  4776.5  274.68  4847.4   272.9  4861.5  273.22  4868.4  272.27  4875.7  272.94
  4889.8  271.47  4988.5  270.65  5008.1  269.46  5008.4  268.96  5011.9  268.96
  5015.9270.7536  5024.3  271.23  5052.7  270.67  5059.4  269.57  5095.3   270.3
  5137.2  269.71  5144.6  269.96  5160.5  272.38  5165.5  273.47  5275.6  276.86
  5328.4  279.08  5335.9  278.71  5364.3  279.61    5371   280.6  5392.3  281.14
#Mann= 6 ,-1 , 0
  4563.7     .12       0  4659.6      .1       0  4988.5     .07       0
  5015.9      .1       0  5160.5     .12       0  5275.6     .05       0
Bank Sta=4988.5,5015.9
XS Rating Curve= 0 ,0
Exp/Cntr=0.3,0.1

Type RM Length L Ch R = 1 ,13343   ,567,567,567
BEGIN DESCRIPTION:
LAKE CREEK TRIBUTARY NO. 21 25.0
END DESCRIPTION:
XS GIS Cut Line= 3
      3742766.78     10146993.62       3742355.3     10147186.33
      3741917.85     10147611.07
#Sta/Elev= 30
  4540.8  284.82    4576  283.31  4605.9  282.44  4688.4  276.41  4716.7  276.16
  4799.1  272.81  4870.9  270.74  4899.4  267.33  4922.2  268.31  4950.6  268.53
  4967.9  267.44  4981.3  268.21  5002.1  264.63  5005.6  264.63    5018  268.39
  5087.5  268.98  5109.9  269.86  5173.4  270.04  5194.7  272.33  5244.2  272.97
  5258.3  274.81  5322.1  275.54  5421.1  281.32  5442.2  281.91  5449.4  280.99
  5491.8  284.42  5498.8  284.16  5512.9  285.46  5520.1  287.11  5604.9  291.72
#Mann= 6 ,-1 , 0
  4540.8     .05       0    4576     .12       0  4799.1      .1       0
  4981.3     .07       0    5018      .1       0  5087.5     .05       0
Bank Sta=4981.3,5018
XS Rating Curve= 0 ,0
Exp/Cntr=0.3,0.1

Type RM Length L Ch R = 1 ,12776   ,496,496,496
BEGIN DESCRIPTION:
LAKE CREEK TRIBUTARY NO. 21 24.0
END DESCRIPTION:
XS GIS Cut Line= 3
      3742417.88     10146661.04      3742126.79     10146915.45
      3741817.84     10147211.08
#Sta/Elev= 30
  4613.4   282.3  4707.3  276.87  4719.7  275.77  4818.9  271.06  4833.2  269.97
  4939.5  267.33  4953.7  266.51  4960.4  266.76  4982.2  265.64  4986.8  264.44
  4987.1  263.94  4990.6  263.94  4990.8  264.44    4996  265.18    5000  265.18
  5003.2  264.44  5010.4  266.29  5024.6  266.99  5045.6   265.9  5095.3  265.63
  5144.7  266.23  5206.2  268.15  5236.5  269.55  5243.8  269.15  5293.1  273.74
  5314.5  274.25  5335.6  275.71  5378.5  276.69  5406.4  278.14  5427.6  280.29
#Mann= 6 ,-1 , 0
  4613.4     .05       0  4707.3      .1       0  4960.4     .07       0
  5024.6      .1       0  5206.2     .12       0  5378.5     .05       0
Bank Sta=4960.4,5024.6
XS Rating Curve= 0 ,0
Exp/Cntr=0.3,0.1

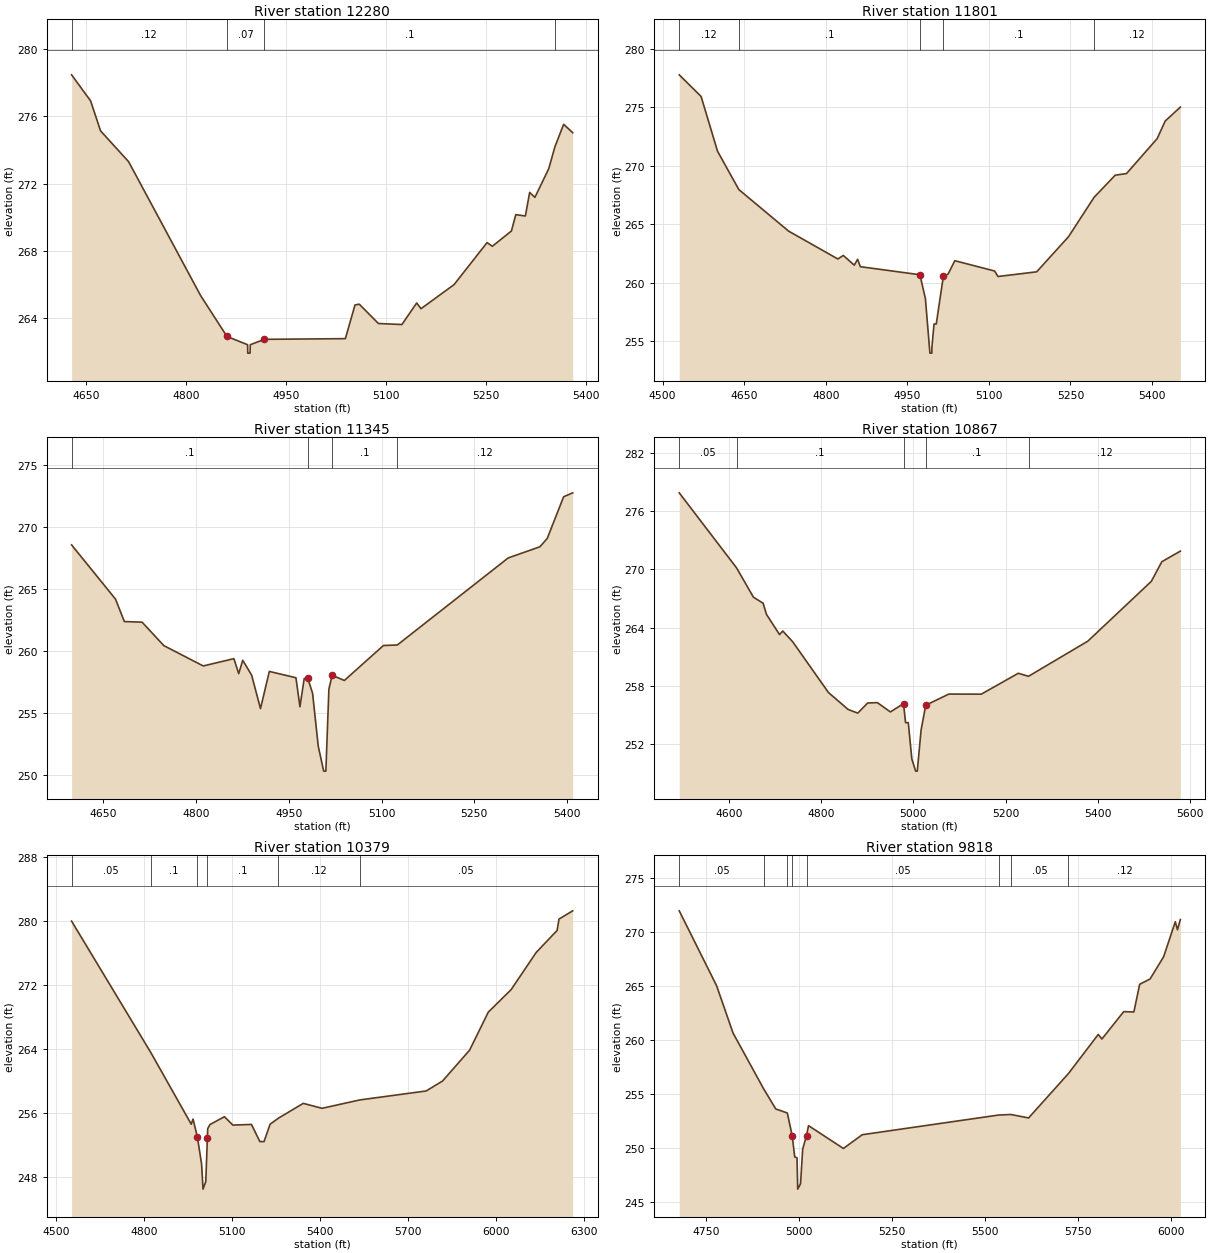
Type RM Length L Ch R = 1 ,12280   ,479,479,479
BEGIN DESCRIPTION:
LAKE CREEK TRIBUTARY NO. 21 23.0
END DESCRIPTION:
XS GIS Cut Line= 3
      3742167.84     10146411.08      3741860.45     10146619.16
      3741567.89     10146861.04
#Sta/Elev= 30
  4628.8  278.46  4657.3  276.91  4672.2  275.13  4714.2   273.3  4822.1  265.34
  4861.6  262.91  4892.5  262.42  4892.7  261.92  4896.2  261.92  4896.5  262.42
  4917.8  262.74    5039  262.78  5053.4  264.78  5059.8  264.83  5088.5  263.68
  5123.7  263.62  5145.8   264.9  5152.3  264.56  5201.8  265.99  5251.3  268.49
  5259.2  268.27  5287.8  269.18  5294.3  270.15  5308.7  270.07  5315.1  271.47
    5323  271.18  5343.8  272.89  5352.9  274.18    5366  275.52  5379.6  275.02
#Mann= 4 ,-1 , 0
  4628.8     .12       0  4861.6     .07       0  4917.8      .1       0
  5352.9     .05       0
Bank Sta=4861.6,4917.8
XS Rating Curve= 0 ,0
Exp/Cntr=0.3,0.1

Type RM Length L Ch R = 1 ,11801   ,456,456,456
BEGIN DESCRIPTION:
LAKE CREEK TRIBUTARY NO. 21 22.0
END DESCRIPTION:
XS GIS Cut Line= 3
      3742067.84     10146261.07       3741601.1     10146310.98
      3741334.45     10146675.95
#Sta/Elev= 30
  4530.6  277.77  4570.8  275.92    4601  271.24  4640.2  267.96  4731.7  264.41
  4822.2  262.03  4832.3  262.33  4852.4   261.5  4858.6     262  4863.6  261.37
  4973.1  260.68  4983.2  258.65  4991.5  253.98    4995  253.98  4995.2  254.48
  4999.1  256.47  5003.2  256.47  5016.3  260.57  5024.8  260.73  5037.3  261.88
  5110.5     261  5116.7  260.53  5187.8  260.93  5246.5  263.94  5293.4   267.3
  5332.2  269.19    5353  269.33  5409.4  272.32  5424.1  273.82    5452  275.01
#Mann= 5 ,-1 , 0
  4530.6     .12       0  4640.2      .1       0  4973.1     .07       0
  5016.3      .1       0  5293.4     .12       0
Bank Sta=4973.1,5016.3
XS Rating Curve= 0 ,0
Exp/Cntr=0.3,0.1

Type RM Length L Ch R = 1 ,11345   ,478,478,478
BEGIN DESCRIPTION:
LAKE CREEK TRIBUTARY NO. 21 21.0
END DESCRIPTION:
XS GIS Cut Line= 3
      3741567.85     10145861.07      3741324.05     10146155.08
      3741188.63     10146561.36
#Sta/Elev= 30
  4598.8  268.57  4669.8   264.2  4684.1  262.39  4712.8  262.34  4747.9  260.45
  4811.7  258.81  4861.2   259.4    4869  258.19  4875.5  259.27  4889.9  258.07
  4904.2  255.37  4918.5  258.37  4961.5  257.86    4968  255.52  4974.9   257.8
  4980.7   257.8  4988.4  256.62  4997.6  252.34  5006.4  250.33  5009.9  250.33
  5014.8  256.95  5020.1  258.06  5039.8  257.64    5103  260.46  5125.4   260.5
  5304.7  267.52    5356  268.42  5367.9   269.1  5394.3  272.45    5409  272.77
#Mann= 4 ,-1 , 0
  4598.8      .1       0  4980.7     .07       0  5020.1      .1       0
  5125.4     .12       0
Bank Sta=4980.7,5020.1
XS Rating Curve= 0 ,0
Exp/Cntr=0.3,0.1

Type RM Length L Ch R = 1 ,10867   ,488,488,488
BEGIN DESCRIPTION:
LAKE CREEK TRIBUTARY NO. 21 20.0
END DESCRIPTION:
XS GIS Cut Line= 3
      3741355.28     10145561.35      3741016.76     10145920.71
      3740967.85     10146511.09
#Sta/Elev= 30
  4492.7  277.86  4617.2  270.12  4653.5  267.12  4674.5   266.5  4681.8  265.35
  4710.1  263.27    4717  263.64  4738.5  262.54  4816.1  257.31  4858.6  255.57
  4879.6  255.19  4901.1  256.23  4922.1  256.27  4950.4  255.31  4978.8  256.17
  4983.2  254.21  4989.1  254.21  4996.8  250.47  5005.1  249.22  5008.6  249.22
  5016.9  253.45  5026.9     256  5077.1  257.15  5147.3  257.14  5227.6  259.29
  5249.7  258.98  5378.1  262.59  5515.9  268.75  5538.6  270.77  5578.8  271.86
#Mann= 5 ,-1 , 0
  4492.7     .05       0  4617.2      .1       0  4978.8     .07       0
  5026.9      .1       0  5249.7     .12       0
Bank Sta=4978.8,5026.9
XS Rating Curve= 0 ,0
Exp/Cntr=0.3,0.1

Type RM Length L Ch R = 1 ,10379   ,561,561,561
BEGIN DESCRIPTION:
LAKE CREEK TRIBUTARY NO. 21 19.0
END DESCRIPTION:
XS GIS Cut Line= 3
      3740949.04     10145321.79      3740824.05     10145717.58
      3739981.58     10146700.47
#Sta/Elev= 30
  4552.9  280.02  4823.7  263.53  4961.1  254.59  4967.2  255.24  4982.2  252.96
  4996.4   249.6  5001.3  246.46  5010.7  247.41 5016.17252.9049  5017.3  254.04
    5025  254.55  5074.4  255.53  5102.9  254.48  5166.6  254.56  5195.1  252.42
  5209.4  252.41  5230.2  254.59  5258.3  255.34  5343.3   257.2  5407.2  256.58
  5536.3  257.63  5762.5  258.75  5818.5     260  5910.7  263.86  5974.4  268.62
  6052.6  271.45  6137.9   276.1  6209.2  278.85  6215.8  280.28  6262.5  281.31
#Mann= 6 ,-1 , 0
  4552.9     .05       0  4823.7      .1       0  4982.2     .07       0
 5016.17      .1       0  5258.3     .12       0  5536.3     .05       0
Bank Sta=4982.2,5016.17
XS Rating Curve= 0 ,0
Exp/Cntr=0.3,0.1

Type RM Length L Ch R = 1 ,9818    ,500,500,500
BEGIN DESCRIPTION:
LAKE CREEK TRIBUTARY NO. 21 18.0
END DESCRIPTION:
XS GIS Cut Line= 3
      3740667.83     10145311.09      3740401.33     10145490.22
      3739517.84     10146011.08
#Sta/Elev= 30
  4678.9  271.93  4779.4     265  4823.5  260.63  4906.1  255.45  4938.4  253.61
  4969.3  253.24 4982.42251.1435  4989.3  249.18  4995.4   249.1  4997.3   246.2
  5004.9   246.7  5010.7  249.92 5020.97251.1455  5026.3  252.07  5120.1  249.96
  5170.7  251.23  5537.2  253.05  5570.4   253.1  5617.7  252.78  5724.7  256.88
    5805   260.5  5814.8  260.08  5873.4  262.61  5900.7  262.58  5916.3  265.14
  5944.3  265.63  5980.7  267.69    6012  270.92  6017.8  270.18  6025.6  271.12
#Mann= 8 ,-1 , 0
  4678.9     .05       0  4906.1      .1       0  4969.3     .05       0
 4982.42     .04       0 5020.97     .05       0  5537.2     .12       0
  5570.4     .05       0  5724.7     .12       0
Bank Sta=4982.42,5020.97
XS Rating Curve= 0 ,0
Exp/Cntr=0.3,0.1

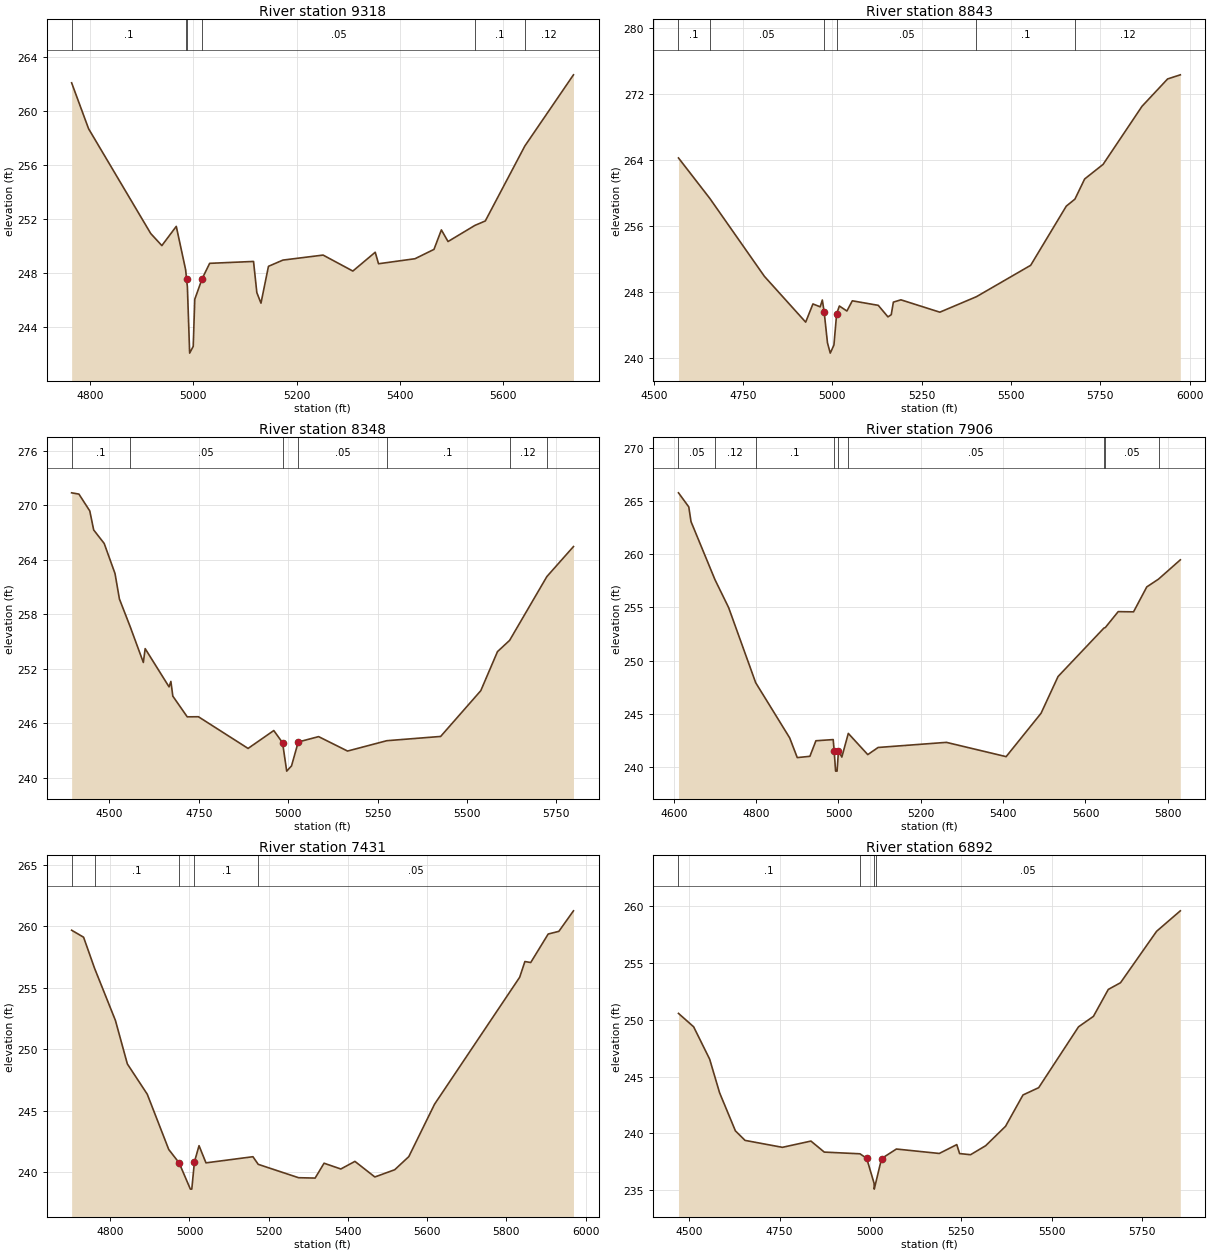
Type RM Length L Ch R = 1 ,9318    ,475,475,475
BEGIN DESCRIPTION:
LAKE CREEK TRIBUTARY NO. 21 17.0
END DESCRIPTION:
XS GIS Cut Line= 3
      3740266.78     10144993.61      3740093.69     10145153.01
      3739517.86     10145611.07
#Sta/Elev= 30
  4764.7  262.06  4797.5  258.67  4917.8  250.93  4939.3  250.04  4967.2  251.46
  4985.3  248.26  4987.2247.5558  4988.7     247  4993.1   242.1    5000   242.6
    5003  246.08  5017.4  247.61  5031.8  248.73  5116.7  248.87  5123.1  246.57
  5131.1  245.79  5145.6  248.51  5173.6  248.97  5251.3  249.34  5308.9  248.16
  5352.2  249.55  5358.6   248.7  5429.1  249.07  5465.9  249.76  5480.2   251.2
  5493.1  250.34    5545  251.53  5565.2  251.86  5641.8   257.4  5735.8  262.65
#Mann= 6 ,-1 , 0
  4764.7      .1       0  4985.3     .05       0  4987.2     .04       0
  5017.4     .05       0    5545      .1       0  5641.8     .12       0
Bank Sta=4987.2,5017.4
XS Rating Curve= 0 ,0
Exp/Cntr=0.3,0.1

Type RM Length L Ch R = 1 ,8843    ,495,495,495
BEGIN DESCRIPTION:
LAKE CREEK TRIBUTARY NO. 21 16.0
END DESCRIPTION:
XS GIS Cut Line= 3
      3740267.82     10144761.08      3739844.23     10144841.18
      3739317.86     10145661.05
#Sta/Elev= 30
  4568.9  264.25  4656.8  259.33  4809.5  249.88  4925.1  244.32  4945.4  246.53
  4965.8  246.18  4971.7  247.01  4976.8  245.59  4986.1  241.82  4993.9  240.56
  5004.2  241.54  5011.8  245.32  5019.4  246.28  5040.5  245.67  5055.7  246.91
  5128.4  246.36  5155.5  244.96  5164.7  245.22  5170.7  246.75  5191.8  247.03
  5300.8  245.53  5403.3  247.41  5555.2  251.22  5654.9   258.4  5679.1  259.25
  5706.4   261.7    5758  263.47    5867  270.52  5938.7  273.84  5974.3  274.34
#Mann= 6 ,-1 , 0
  4568.9      .1       0  4656.8     .05       0  4976.8     .04       0
  5011.8     .05       0  5403.3      .1       0  5679.1     .12       0
Bank Sta=4976.8,5011.8
XS Rating Curve= 0 ,0
Exp/Cntr=0.3,0.1

Type RM Length L Ch R = 1 ,8348    ,442,442,442
BEGIN DESCRIPTION:
LAKE CREEK TRIBUTARY NO. 21 15.0
END DESCRIPTION:
XS GIS Cut Line= 3
      3740298.06      10144358.2      3739698.44     10144440.91
      3738967.81     10144761.09
#Sta/Elev= 30
  4394.7  271.39  4415.1  271.25  4445.4   269.4  4456.4   267.3  4485.8  265.81
    4516   262.5  4528.3   259.7    4558  256.69  4595.2  252.71  4600.3  254.23
  4667.1  250.02  4672.2  250.62  4677.6     249  4717.9  246.72  4749.2  246.73
    4888  243.24  4959.9  245.21 4984.43243.8657    4996  240.74  5009.5  241.32
 5028.24243.9475  5085.1  244.54  5166.1  242.95  5275.7  244.09  5426.4  244.56
  5538.6   249.6  5585.3   253.9  5619.2  255.14  5723.4  262.17  5797.7  265.47
#Mann= 7 ,-1 , 0
  4394.7      .1       0    4558     .05       0 4984.43     .04       0
 5028.24     .05       0  5275.7      .1       0  5619.2     .12       0
  5723.4     .05       0
Bank Sta=4984.43,5028.24
XS Rating Curve= 0 ,0
Exp/Cntr=0.3,0.1

Type RM Length L Ch R = 1 ,7906    ,475,475,475
BEGIN DESCRIPTION:
LAKE CREEK TRIBUTARY NO. 21 14.0
END DESCRIPTION:
XS GIS Cut Line= 3
      3740131.32     10143915.51      3739834.47     10144024.87
      3738975.07     10144300.92
#Sta/Elev= 30
  4611.4  265.75  4636.4  264.43  4641.8  263.05    4700   257.6  4733.2  254.98
  4798.9  247.93  4881.5  242.75  4899.9   240.9  4930.6  241.02  4945.2  242.48
  4987.2  242.59 4989.57241.5301    4993  239.63  4996.6  239.63    5000  241.55
  5008.2  240.95  5023.9  243.17  5071.2  241.18  5096.3  241.85  5262.1  242.33
  5407.3  240.99  5492.1  245.06  5533.4  248.51  5644.9  253.06  5648.3  253.11
  5679.5   254.6  5716.8  254.58  5748.9  256.92  5777.4  257.65  5830.4  259.46
#Mann= 9 ,-1 , 0
  4611.4     .05       0    4700     .12       0  4798.9      .1       0
 4989.57     .07       0    5000      .1       0  5023.9     .05       0
  5644.9      .1       0  5648.3     .05       0  5777.4     .12       0
Bank Sta=4989.57,5000
XS Rating Curve= 0 ,0
Exp/Cntr=0.3,0.1

Type RM Length L Ch R = 1 ,7431    ,539,539,539
BEGIN DESCRIPTION:
LAKE CREEK TRIBUTARY NO. 21 13.0
END DESCRIPTION:
XS GIS Cut Line= 3
      3740017.86     10143661.07      3739620.93     10143701.96
      3738917.84     10144211.08
#Sta/Elev= 30
  4702.4  259.69  4732.6  259.12  4760.3  256.59    4813  252.34  4843.1   248.8
  4893.4  246.33  4947.6  241.83  4973.8  240.74  5002.2   238.6  5005.8   238.6
 5012.44240.8146  5024.1  242.14  5041.6  240.74  5160.2  241.24  5173.5  240.62
  5275.4  239.53  5317.2   239.5  5339.8  240.71  5382.1  240.24  5417.7  240.86
    5468  239.59  5518.2  240.18  5553.8  241.25  5618.8  245.52  5833.7  255.86
  5846.9  257.14  5861.6  257.06  5905.7  259.38  5932.7   259.6  5969.5  261.27
#Mann= 5 ,-1 , 0
  4702.4     .05       0  4760.3      .1       0  4973.8     .07       0
 5012.44      .1       0  5173.5     .05       0
Bank Sta=4973.8,5012.44
XS Rating Curve= 0 ,0
Exp/Cntr=0.3,0.1

Type RM Length L Ch R = 1 ,6892    ,511,511,511
BEGIN DESCRIPTION:
Mapping XS 3d650df3
END DESCRIPTION:
XS GIS Cut Line= 3
      3739857.81     10143520.66      3739555.68      10143426.9
      3738514.05       10143663.
#Sta/Elev= 30
  4470.9  250.56  4512.7  249.38  4556.9  246.53  4584.2  243.58  4627.9  240.22
  4654.6  239.38  4757.5  238.77  4836.3  239.32  4873.1  238.35  4971.6   238.2
  4990.1   237.8  5010.6  235.59  5010.9  235.09  5014.7  235.59  5031.1  237.78
  5072.1  238.62  5190.3  238.23  5238.6  239.01  5246.4  238.22  5276.6  238.12
  5318.2  238.91  5373.1  240.62  5421.3  243.38  5464.5  244.02  5574.5  249.38
  5615.6   250.3  5656.6  252.67  5690.3  253.26  5789.9  257.79  5855.3  259.59
#Mann= 4 ,-1 , 0
  4470.9      .1       0  4971.6     .05       0  5010.6     .05       0
  5014.7     .05       0
Bank Sta=4990.1,5031.1
XS Rating Curve= 0 ,0
Exp/Cntr=0.3,0.1

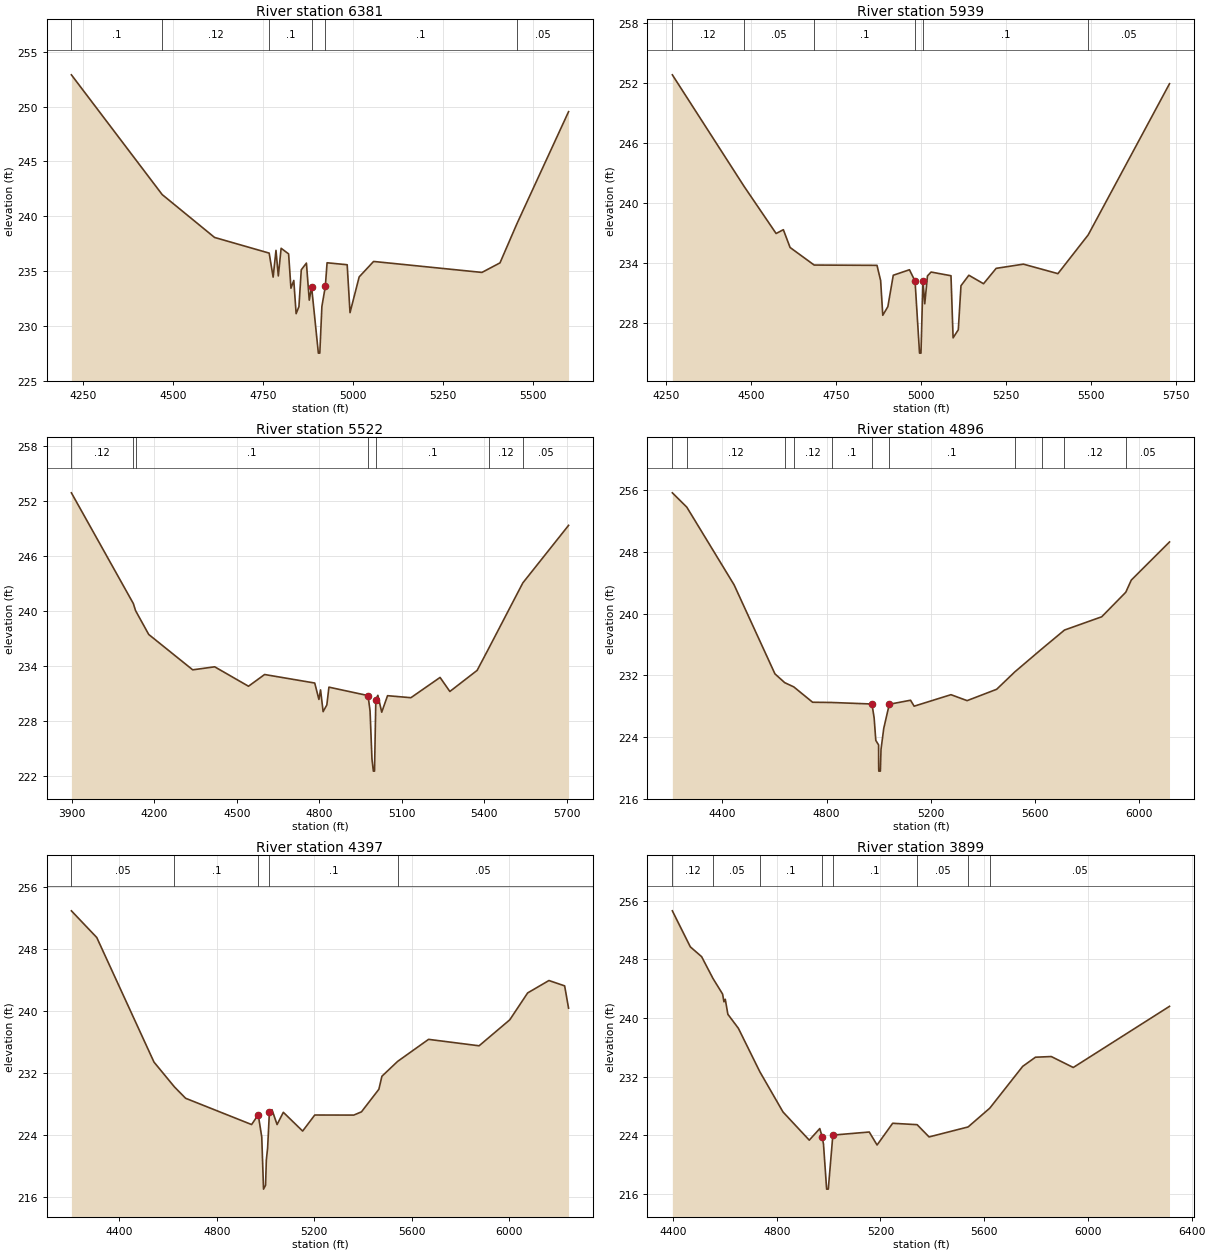
Type RM Length L Ch R = 1 ,6381    ,442,442,442
BEGIN DESCRIPTION:
LAKE CREEK TRIBUTARY NO. 21 12.0
END DESCRIPTION:
XS GIS Cut Line= 3
      3739917.83     10143511.05      3739314.14     10143011.77
       3738717.9     10142961.08
#Sta/Elev= 30
  4216.6  252.89  4468.9  241.97  4614.5  238.06  4766.3  236.63  4777.3  234.44
  4785.2  236.88  4791.7  234.55  4799.5  237.07  4820.3  236.56  4826.8  233.43
  4834.7  234.14  4841.2  231.11    4849  231.75  4855.5  235.11  4869.8  235.72
  4877.7  232.34  4884.2  233.55    4903  227.51    4907  227.51  4912.8  231.77
 4922.34233.5906  4927.2  235.75  4983.1  235.57    4991   231.2  5016.4  234.46
  5056.5  235.87  5357.6  234.87  5407.8  235.74  5454.7   239.3  5598.4  249.53
#Mann= 6 ,-1 , 0
  4216.6      .1       0  4468.9     .12       0  4766.3      .1       0
  4884.2     .07       0 4922.34      .1       0  5454.7     .05       0
Bank Sta=4884.2,4922.34
XS Rating Curve= 0 ,0
Exp/Cntr=0.3,0.1

Type RM Length L Ch R = 1 ,5939    ,417,417,417
BEGIN DESCRIPTION:
LAKE CREEK TRIBUTARY NO. 21 11.0
END DESCRIPTION:
XS GIS Cut Line= 3
       3739995.9     10142852.99       3739230.3     10142582.16
      3738667.89     10142911.05
#Sta/Elev= 30
  4267.7  252.83  4478.7  241.67  4573.2  236.94  4594.5  237.32  4614.3  235.54
  4685.2  233.78  4870.2  233.75  4880.9  232.22  4887.2  228.75  4902.1  229.61
  4918.1  232.76  4965.7  233.31 4982.22232.1679  4995.4  224.96  4999.6  224.96
  5005.5  232.22  5010.8   229.9  5018.7  232.69  5029.4  233.08    5088  232.71
  5094.2  226.49  5109.5   227.3  5117.4  231.71  5140.6  232.76  5183.8  231.91
    5221  233.45  5301.2  233.87  5402.8  232.92  5491.9   236.8  5731.3  251.94
#Mann= 6 ,-1 , 0
  4267.7     .12       0  4478.7     .05       0  4685.2      .1       0
 4982.22     .07       0  5005.5      .1       0  5491.9     .05       0
Bank Sta=4982.22,5005.5
XS Rating Curve= 0 ,0
Exp/Cntr=0.3,0.1

Type RM Length L Ch R = 1 ,5522    ,626,626,626
BEGIN DESCRIPTION:
LAKE CREEK TRIBUTARY NO. 21 10.0
END DESCRIPTION:
XS GIS Cut Line= 4
      3740001.13     10142811.33       3739350.1     10142425.91
      3739204.26     10142196.75      3738667.84     10142761.08
#Sta/Elev= 30
    3899  252.86  4124.1  240.78  4132.2  240.01    4180  237.41  4339.9  233.55
  4419.8  233.88  4542.6  231.76  4601.1  233.04  4783.3  232.11  4798.5  230.32
  4804.5  231.36  4813.8  228.99  4827.3  229.72  4834.9  231.66  4977.1  230.74
  4984.4  229.06  4991.3  223.82  4996.4   222.5  5000.6   222.5  5005.4   230.3
  5012.7  230.77  5026.8  228.93  5047.9  230.73  5132.8  230.51  5238.8  232.72
  5274.4  231.19  5373.5  233.49  5416.7  235.95  5539.5  243.03  5705.8  249.31
#Mann= 7 ,-1 , 0
    3899     .12       0  4124.1     .05       0  4132.2      .1       0
  4977.1     .07       0  5005.4      .1       0  5416.7     .12       0
  5539.5     .05       0
Bank Sta=4977.1,5005.4
XS Rating Curve= 0 ,0
Exp/Cntr=0.3,0.1

Type RM Length L Ch R = 1 ,4896    ,499,499,499
BEGIN DESCRIPTION:
LAKE CREEK TRIBUTARY NO. 21 9.0
END DESCRIPTION:
XS GIS Cut Line= 3
      3739605.33     10141207.15      3738964.04     10141672.26
      3738595.22     10142727.04
#Sta/Elev= 30
  4207.8  255.66  4263.2  253.81    4445  243.73  4601.9  232.19  4639.4  231.05
  4674.3   230.5  4746.5  228.51  4819.9  228.48  4974.6  228.28  4982.9  226.47
  4989.3  223.56    5000  222.98  5000.3  220.08  5000.8  219.58  5006.8  219.58
  5009.3   222.4  5019.9  225.14  5041.1  228.25  5122.7  228.77  5136.5     228
  5277.9  229.49    5340  228.72  5453.5  230.19    5523  232.44  5625.7  235.39
    5714  237.87    5857  239.59  5949.4  242.77  5970.6  244.35  6117.4  249.29
#Mann= 11 ,-1 , 0
  4207.8     .05       0  4263.2     .12       0  4639.4      .1       0
  4674.3     .12       0  4819.9      .1       0  4974.6     .07       0
  5041.1      .1       0    5523     .12       0  5625.7      .1       0
    5714     .12       0  5949.4     .05       0
Bank Sta=4974.6,5041.1
XS Rating Curve= 0 ,0
Exp/Cntr=0.3,0.1

Type RM Length L Ch R = 1 ,4397    ,498,498,498
BEGIN DESCRIPTION:
LAKE CREEK TRIBUTARY NO. 21 8.0
END DESCRIPTION:
XS GIS Cut Line= 3
      3738867.85     10140561.09       3738644.8     10141326.03
      3738267.86     10142511.03
#Sta/Elev= 30
  4203.2  252.95  4307.3  249.51  4542.1  233.44  4626.2  230.23  4671.9  228.77
  4942.7  225.38    4970  226.64  4984.4  223.77  4991.7  217.05    5000  217.55
  5003.2  220.81  5008.5  222.38  5015.8     227  5026.3   227.3  5047.3  225.38
  5072.9  226.96  5152.2  224.54  5201.9  226.61  5362.1   226.6  5393.6  227.02
    5465  229.93  5477.5  231.61  5542.1  233.53  5668.9  236.37  5876.3  235.54
  6002.2  238.89  6075.6  242.36    6163  243.96  6227.4  243.27  6243.5  240.39
#Mann= 5 ,-1 , 0
  4203.2     .05       0  4626.2      .1       0    4970     .07       0
  5015.8      .1       0  5542.1     .05       0
Bank Sta=4970,5015.8
XS Rating Curve= 0 ,0
Exp/Cntr=0.3,0.1

Type RM Length L Ch R = 1 ,3899    ,499,499,499
BEGIN DESCRIPTION:
LAKE CREEK TRIBUTARY NO. 21 7.0
END DESCRIPTION:
XS GIS Cut Line= 3
      3738324.06     10140519.62      3738229.64     10141114.58
      3738136.56     10142425.88
#Sta/Elev= 30
  4397.6   254.6    4467  249.69  4510.4  248.36  4554.4  245.38  4591.4  243.26
  4596.6  242.21  4601.7  242.55  4611.7  240.51  4652.2   238.6  4734.8  232.69
  4824.3   227.2  4925.6  223.36  4966.1  224.94  4975.3  223.82  4980.4  222.82
  4992.5  216.69  4998.9  216.69  5016.5  224.05  5156.9  224.47    5187   222.7
  5247.1  225.66  5341.4  225.47  5387.5   223.8    5538  225.16  5621.6  227.72
  5748.4  233.41  5797.7  234.66  5858.7  234.75  5943.5  233.26  6314.6  241.59
#Mann= 8 ,-1 , 0
  4397.6     .12       0  4554.4     .05       0  4734.8      .1       0
  4975.3     .07       0  5016.5      .1       0  5341.4     .05       0
    5538      .1       0  5621.6     .05       0
Bank Sta=4975.3,5016.5
XS Rating Curve= 0 ,0
Exp/Cntr=0.3,0.1

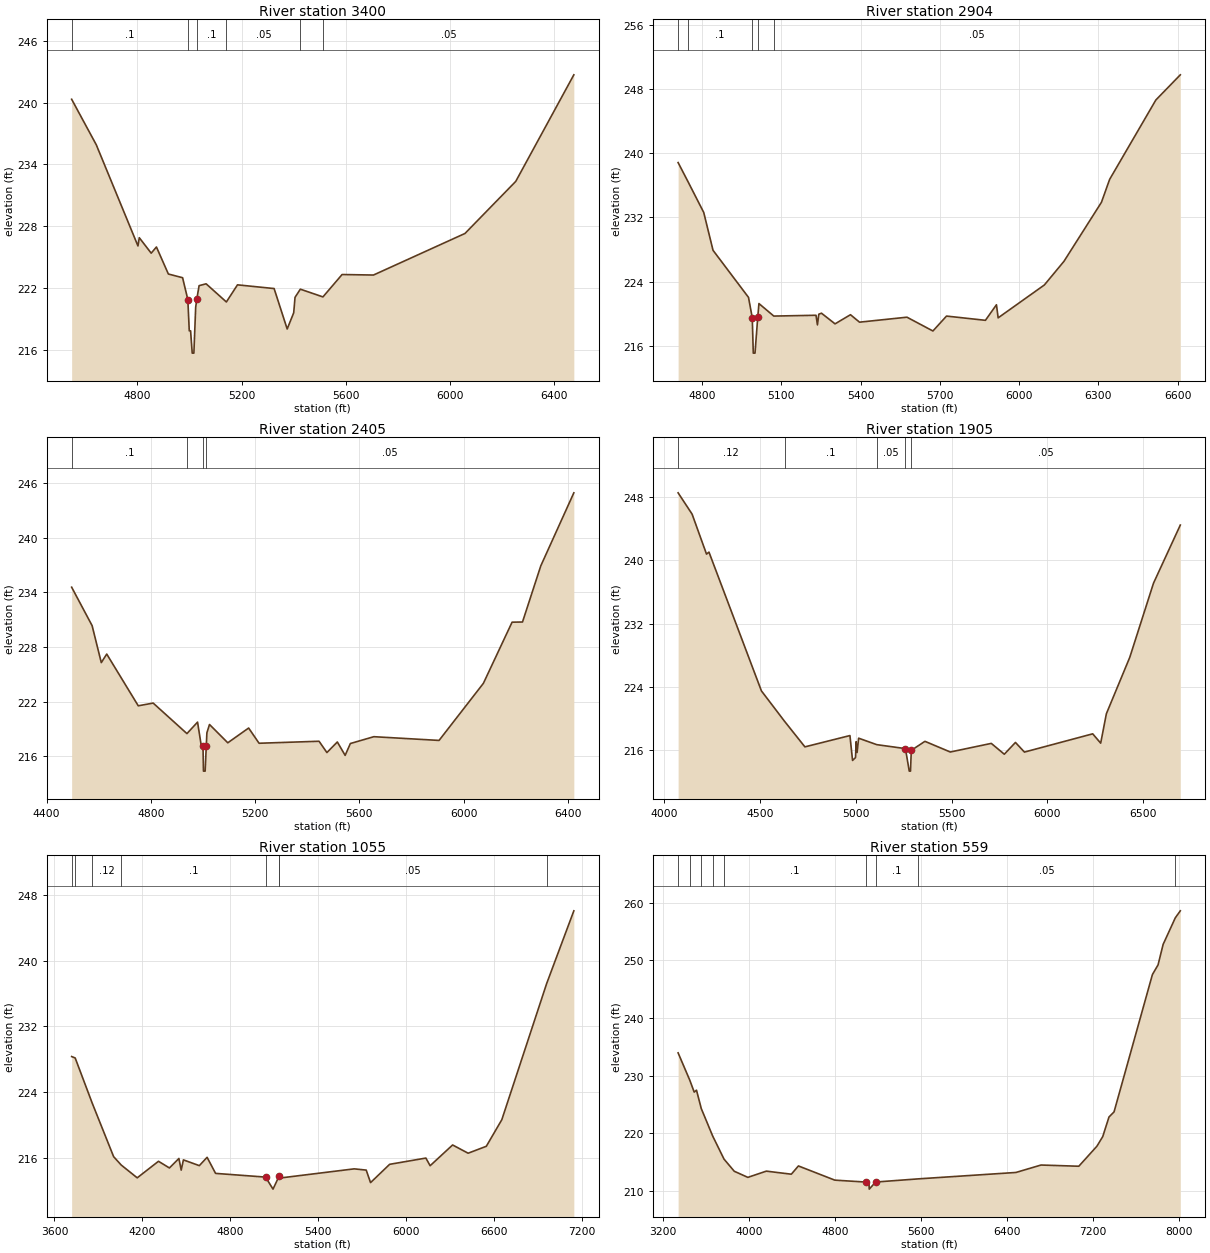
Type RM Length L Ch R = 1 ,3400    ,496,496,496
BEGIN DESCRIPTION:
LAKE CREEK TRIBUTARY NO. 21 6.0
END DESCRIPTION:
XS GIS Cut Line= 3
      3737719.89     10140576.97      3737759.97     10141027.19
      3737881.24      10142497.5
#Sta/Elev= 30
    4548  240.32  4642.5  235.91  4802.5   226.1  4807.6   226.9  4853.3   225.4
  4873.4     226  4919.2  223.38  4973.8  223.02  4993.9   220.9  4999.4  217.87
  5004.5  217.87  5010.7  215.71  5017.1  215.71    5024  220.15 5028.26 220.938
  5037.1  222.25  5064.1  222.43  5141.8  220.67  5184.5  222.33    5325  221.97
  5375.2  218.05  5400.2  219.62  5405.3  221.12  5425.7  221.91  5512.4  221.16
  5585.9  223.33  5706.3  223.28  6057.5  227.31  6252.4  232.36  6475.3  242.69
#Mann= 6 ,-1 , 0
    4548      .1       0  4993.9     .07       0 5028.26      .1       0
  5141.8     .05       0  5425.7      .1       0  5512.4     .05       0
Bank Sta=4993.9,5028.26
XS Rating Curve= 0 ,0
Exp/Cntr=0.3,0.1

Type RM Length L Ch R = 1 ,2904    ,499,499,499
BEGIN DESCRIPTION:
LAKE CREEK TRIBUTARY NO. 21 5.0
END DESCRIPTION:
XS GIS Cut Line= 3
      3737558.42     10140644.67      3737348.91      10140846.2
      3736967.85     10142411.07
#Sta/Elev= 30
  4709.3  238.83  4747.2  236.42  4806.3  232.61  4841.5  227.89  4975.8  222.02
    4990  219.49  4993.9  215.07  5000.4  215.07 5010.73219.5206  5015.3  221.25
  5071.6  219.69  5231.4  219.79  5236.8  218.59  5241.9  219.92    5252  220.05
  5303.5  218.72  5361.9  219.86  5396.1  218.93  5575.7  219.55    5674  217.83
  5725.5  219.69  5872.8  219.16  5914.5   221.1    5921  219.47    6096  223.57
    6170  226.51  6312.1  233.88    6343  236.73    6518  246.63  6610.6  249.77
#Mann= 5 ,-1 , 0
  4709.3     .12       0  4747.2      .1       0    4990     .07       0
 5010.73      .1       0  5071.6     .05       0
Bank Sta=4990,5010.73
XS Rating Curve= 0 ,0
Exp/Cntr=0.3,0.1

Type RM Length L Ch R = 1 ,2405    ,500,500,500
BEGIN DESCRIPTION:
LAKE CREEK TRIBUTARY NO. 21 4.0
END DESCRIPTION:
XS GIS Cut Line= 3
      3737217.84     10140461.08      3736892.88     10140846.06
      3736938.58     10142267.83
#Sta/Elev= 30
  4496.2  234.55  4574.7  230.33  4609.9  226.27  4630.8  227.21  4751.7  221.53
  4808.9  221.83  4938.4  218.48  4979.2  219.74  4993.5  217.13    5000  217.13
  5001.8  214.36  5008.3  214.36 5012.64217.1579    5015  218.57    5025  219.48
  5095.1  217.47  5175.1  219.09  5215.1  217.42  5445.2  217.64  5475.3   216.4
  5515.3  217.56  5545.3  216.09  5565.3  217.39  5655.3  218.14  5905.5  217.73
  6075.6     224  6185.6  230.71  6225.6  230.73  6295.7  236.89  6422.5  244.91
#Mann= 4 ,-1 , 0
  4496.2      .1       0  4938.4     .05       0    5000     .03       0
 5012.64     .05       0
Bank Sta=5000,5012.64
XS Rating Curve= 0 ,0
Exp/Cntr=0.3,0.1

Type RM Length L Ch R = 1 ,1905    ,850,850,850
BEGIN DESCRIPTION:
LAKE CREEK TRIBUTARY NO. 21 3.0
END DESCRIPTION:
XS GIS Cut Line= 3
      3737317.89     10140161.05        3736512.     10140615.72
      3736818.84     10142280.07
#Sta/Elev= 30
  4074.7  248.56  4147.7  245.86  4222.8   240.8  4235.5  241.06  4508.8   223.5
  4629.4  219.65  4735.6  216.41  4970.3  217.84    4984  214.69  4999.5  215.06
  5002.5  217.06  5007.6   215.7  5015.6  217.51  5110.2  216.69  5259.7  216.19
  5279.5  213.34    5286  213.34  5290.2  215.97  5361.3  217.11  5493.5  215.76
  5707.1  216.85    5775  215.48  5833.1  216.97  5879.9  215.75  6235.8  218.06
  6277.4  216.88    6307   220.6    6429  227.74  6552.6  237.12  6692.4  244.48
#Mann= 5 ,-1 , 0
  4074.7     .12       0  4629.4      .1       0  5110.2     .05       0
  5259.7     .07       0  5290.2     .05       0
Bank Sta=5259.7,5290.2
XS Rating Curve= 0 ,0
Exp/Cntr=0.3,0.1

Type RM Length L Ch R = 1 ,1055    ,496,496,496
BEGIN DESCRIPTION:
LAKE CREEK TRIBUTARY NO. 21 2.0
END DESCRIPTION:
XS GIS Cut Line= 3
      3736967.85     10139911.07      3735860.51     10140550.91
      3736693.36     10142528.92
#Sta/Elev= 30
  3717.4  228.34  3741.5  228.17  3858.1  222.67  4003.8  216.19  4055.1  215.18
  4164.6  213.62  4309.6  215.63  4384.2  214.82  4448.9  215.97  4464.6  214.56
  4479.7   215.8  4588.1   215.1  4641.2  216.11  4699.1  214.16  5039.9  213.71
  5090.8  212.25  5131.6   213.8  5134.8  213.59  5644.3  214.71  5726.4  214.56
    5756  213.04  5886.2  215.26  6133.3  216.02  6162.4  215.09  6315.7  217.61
  6421.5  216.61  6545.6  217.45  6651.4  220.68  6956.7  237.18  7142.5  246.03
#Mann= 8 ,-1 , 0
  3717.4     .12       0  3741.5      .1       0  3858.1     .12       0
  4055.1      .1       0  5039.9     .07       0  5131.6      .1       0
  5134.8     .05       0  6956.7     .12       0
Bank Sta=5039.9,5131.6
XS Rating Curve= 0 ,0
Exp/Cntr=0.3,0.1

Type RM Length L Ch R = 1 ,559     ,0,0,0
BEGIN DESCRIPTION:
LAKE CREEK TRIBUTARY NO. 21 1.0
END DESCRIPTION:
XS GIS Cut Line= 3
      3737058.42     10139649.88       3735350.1     10140280.08
       3736475.1      10142905.1
#Sta/Elev= 30
  3339.3  233.94  3448.4  229.18  3489.1  227.13  3510.4  227.47  3555.1  224.27
  3661.8  219.49  3766.7  215.51  3862.2   213.4  3988.8  212.34  4160.6  213.42
  4393.6  212.89  4459.8  214.32  4798.3  211.86    5092  211.52  5117.1  211.12
  5119.2   210.3 5178.63211.5296  5576.9  212.08  6485.2  213.19  6719.1  214.48
  7070.9  214.27  7239.3  217.74  7293.7  219.41  7351.9  222.81  7399.1   223.7
  7756.3  247.52  7808.9   249.2    7856  252.75  7969.4  257.36  8016.1  258.58
#Mann= 9 ,-1 , 0
  3339.3     .12       0  3448.4      .1       0  3555.1     .05       0
  3661.8     .12       0  3766.7      .1       0    5092     .07       0
 5178.63      .1       0  5576.9     .05       0  7969.4     .12       0
Bank Sta=5092,5178.63
XS Rating Curve= 0 ,0
Exp/Cntr=0.3,0.1

Chan Stop Cuts=-1
Use User Specified Reach Order=0
Composite Channel Slope=5