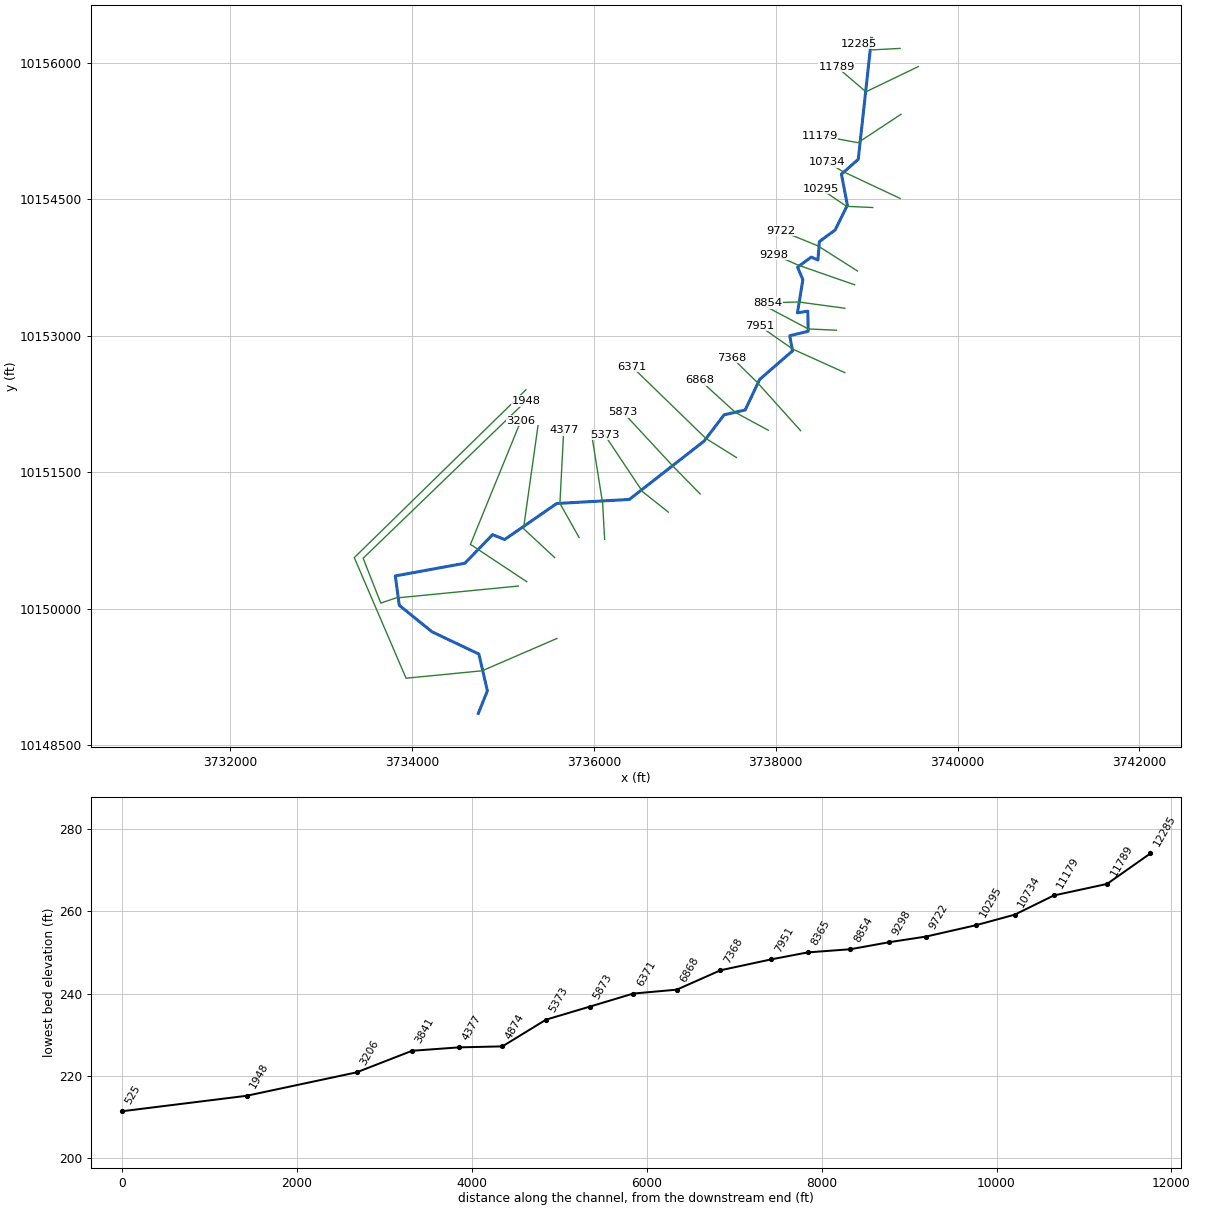
--- LAKE CREEK TRIBUTARY NO 22.prj (project) ---

Proj Title=LAKE CREEK TRIBUTARY NO 22 Base Level Engineering
Current Plan=p01
Default Exp/Contr=0.3,0.1
English Units
Geom File=g01
Flow File=f01
Flow File=f02
Plan File=p01
Y Axis Title=Elevation
X Axis Title(PF)=Main Channel Distance
X Axis Title(XS)=Station
BEGIN DESCRIPTION:
LAKE CREEK TRIBUTARY NO 22
END DESCRIPTION:
DSS Export Rating Curves= 0
DSS Export Rating Curve Sorted= 0
DSS Export Volume Flow Curves= 0
DXF OffsetX= 0
DXF OffsetY= 0
DXF ScaleX= 1
DXF ScaleY= 10

--- LAKE CREEK TRIBUTARY NO 22.p01 (plan) ---

Plan Title=Multiple Run
Short Identifier=Multiple
Geom File=g01
Flow File=f01
Subcritical Flow
K Sum by GR= 0
Std Step Tol= 0.01
Critical Tol= 0.01
Num of Std Step Trials= 20
Max Error Tol= 0.3
Flow Tol Ratio= 0.001
Split Flow NTrial= 30
Split Flow Tol= 0.02
Split Flow Ratio= 0.02
Log Output Level= 0
Friction Slope Method= 1
Unsteady Friction Slope Method= 2
Unsteady Bridges Friction Slope Method= 1
Parabolic Critical Depth
Global Vel Dist=  1 , 1 , 1
Global Log Level= 0
CheckData=True
Encroach Param= -1, 0, 0, 0
BEGIN DESCRIPTION:
Multiple Run
END DESCRIPTION:

--- LAKE CREEK TRIBUTARY NO 22.f01 (steady flow) ---

Flow Title=Multiple
Number of Profiles=7
Profile Names=10-year,25-year,50-year,1pct_min,100-year,1pct_plu,500-year
River Rch & RM= LAKE CREEK TRIBU,Reach-1,12285
     870    1186    1448     580    1752    5290    2560
River Rch & RM= LAKE CREEK TRIBU,Reach-1,6868
     908    1226    1486     590    1783    5384    2563
Boundary for River Rch & Prof#=LAKE CREEK TRIBU,Reach-1,1
Up Type=0
Dn Type=3
Dn Slope=0.005
Boundary for River Rch & Prof#=LAKE CREEK TRIBU,Reach-1,2
Up Type=0
Dn Type=3
Dn Slope=0.005
Boundary for River Rch & Prof#=LAKE CREEK TRIBU,Reach-1,3
Up Type=0
Dn Type=3
Dn Slope=0.005
Boundary for River Rch & Prof#=LAKE CREEK TRIBU,Reach-1,4
Up Type=0
Dn Type=3
Dn Slope=0.005
Boundary for River Rch & Prof#=LAKE CREEK TRIBU,Reach-1,5
Up Type=0
Dn Type=3
Dn Slope=0.005
Boundary for River Rch & Prof#=LAKE CREEK TRIBU,Reach-1,6
Up Type=0
Dn Type=3
Dn Slope=0.005
Boundary for River Rch & Prof#=LAKE CREEK TRIBU,Reach-1,7
Up Type=0
Dn Type=3
Dn Slope=0.005

--- LAKE CREEK TRIBUTARY NO 22.f02 (steady flow) ---

Flow Title=Orig_BLE_Flows
Program Version=4.10
Number of Profiles= 7
Profile Names=10-year,25-year,50-year,1pct_min,100-year,1pct_plu,500-year
River Rch & RM=LAKE CREEK TRIBU,Reach-1         ,12285
     870    1186    1448     580    1752    5290    2560
River Rch & RM=LAKE CREEK TRIBU,Reach-1         ,6868
     908    1226    1486     590    1783    5384    2563
Boundary for River Rch & Prof#=LAKE CREEK TRIBU,Reach-1         , 1
Up Type= 0
Dn Type= 3
Dn Slope=0.005
Boundary for River Rch & Prof#=LAKE CREEK TRIBU,Reach-1         , 2
Up Type= 0
Dn Type= 3
Dn Slope=0.005
Boundary for River Rch & Prof#=LAKE CREEK TRIBU,Reach-1         , 3
Up Type= 0
Dn Type= 3
Dn Slope=0.005
Boundary for River Rch & Prof#=LAKE CREEK TRIBU,Reach-1         , 4
Up Type= 0
Dn Type= 3
Dn Slope=0.005
Boundary for River Rch & Prof#=LAKE CREEK TRIBU,Reach-1         , 5
Up Type= 0
Dn Type= 3
Dn Slope=0.005
Boundary for River Rch & Prof#=LAKE CREEK TRIBU,Reach-1         , 6
Up Type= 0
Dn Type= 3
Dn Slope=0.005
Boundary for River Rch & Prof#=LAKE CREEK TRIBU,Reach-1         , 7
Up Type= 0
Dn Type= 3
Dn Slope=0.005
DSS Import GetInterval= 0
DSS Import GetPeak= 0
DSS Import FillOption= 0

--- LAKE CREEK TRIBUTARY NO 22.g01 (geometry) ---

Geom Title=Existing Conditions
Program Version=4.10

River Reach=LAKE CREEK TRIBU,Reach-1
Reach XY= 30
      3739053.23     10156271.84      3738907.55     10154941.18
      3738722.63     10154777.33      3738788.23     10154436.84
      3738654.59     10154164.82      3738479.89     10154036.11
      3738464.12     10153833.64      3738390.83     10153865.75
      3738239.87     10153755.29      3738298.48     10153616.85
      3738238.67     10153252.85      3738352.74     10153270.73
      3738357.04     10153049.19      3738154.09      10153000.9
      3738184.69     10152834.45       3737822.5     10152519.54
      3737664.26     10152183.94      3737431.98     10152130.56
       3737211.6     10151841.63      3736389.73     10151199.91
      3735590.73     10151155.37      3735018.21     10150759.03
      3734885.09      10150812.9      3734581.01      10150498.4
      3733815.52      10150358.6      3733859.07     10150035.44
      3734218.89     10149744.37      3734734.66     10149499.28
      3734828.36     10149094.41      3734728.23     10148846.84

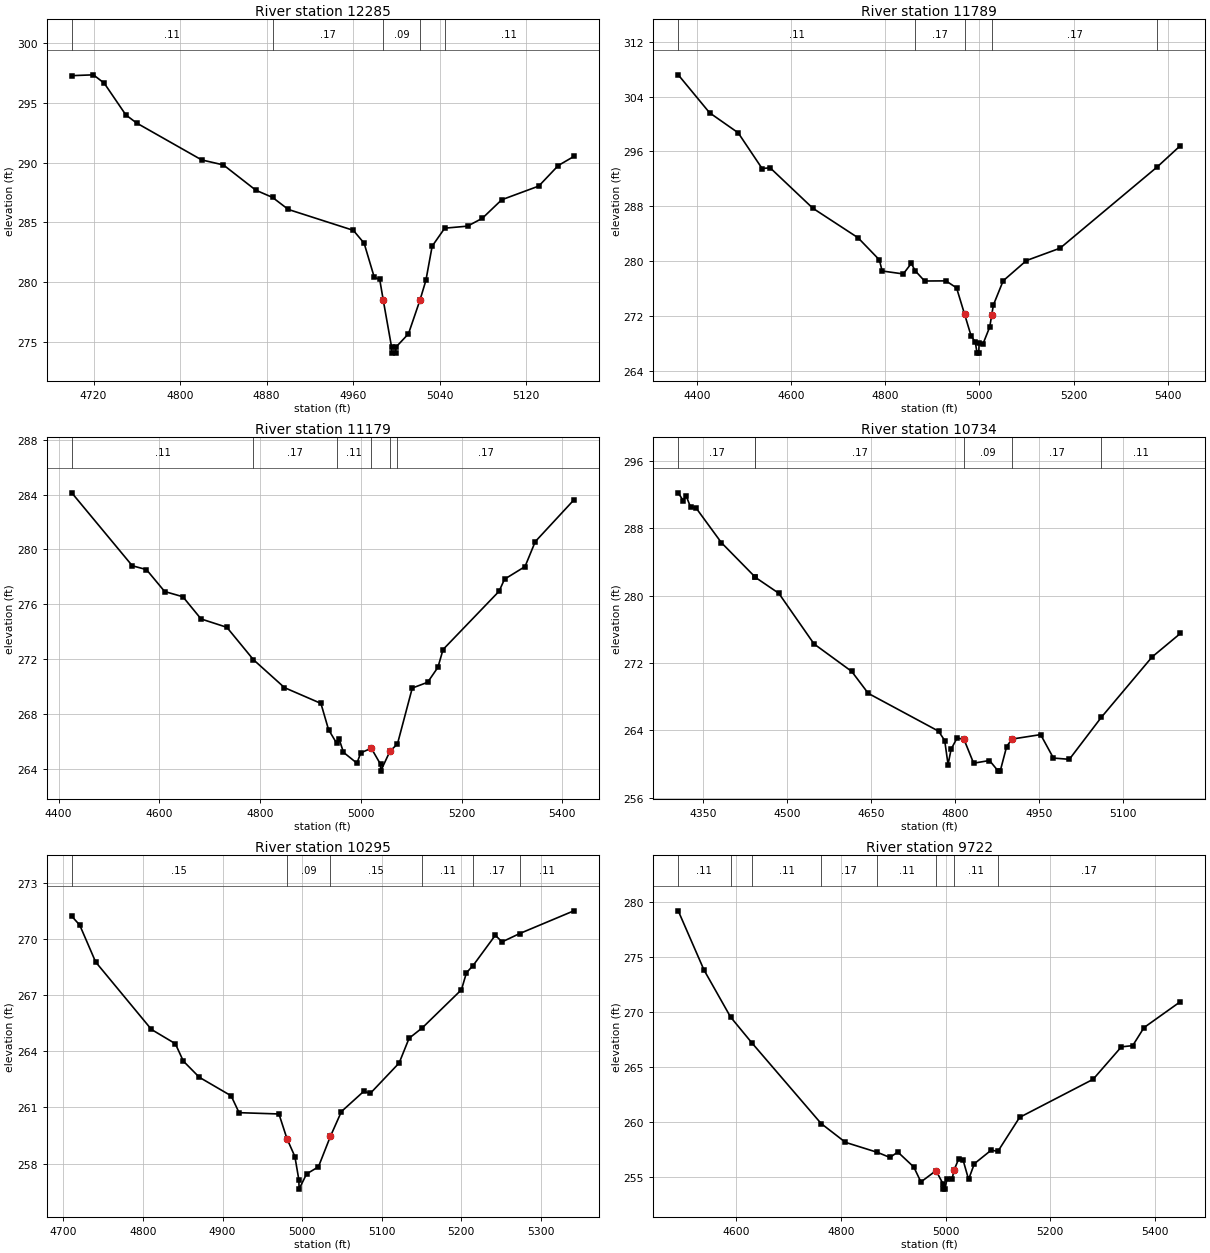
Type RM Length L Ch R = 1 ,12285   ,496,496,496
BEGIN DESCRIPTION:
LAKE CREEK TRIBUTARY NO. 22 22.0
END DESCRIPTION:
XS GIS Cut Line= 3
      3739367.82     10156161.07      3739068.14     10156145.23
      3738917.83     10156211.08
#Sta/Elev= 30
  4699.9   297.3  4719.9  297.37  4729.9  296.67  4749.9  294.01  4759.9  293.33
    4820  290.24  4840.1  289.82  4870.1   287.7  4885.5   287.1  4900.1  286.09
  4960.2  284.34  4970.2  283.26  4979.6   280.4  4984.6  280.23 4987.89278.4868
  4995.6  274.55  4995.9  274.05  4999.4  274.05  4999.6  274.55  5011.2  275.67
  5021.9  278.51  5027.3  280.14  5033.1  283.01  5044.7  284.52  5065.8  284.69
  5079.5  285.35  5097.4   286.9  5131.7  288.05  5149.7  289.77  5164.1  290.53
#Mann= 5 ,-1 , 0
  4699.9     .11       0  4885.5     .17       0 4987.89     .09       0
  5021.9     .17       0  5044.7     .11       0
Bank Sta=4987.89,5021.9
XS Rating Curve= 0 ,0
Exp/Cntr=0.3,0.1

Type RM Length L Ch R = 1 ,11789   ,610,610,610
BEGIN DESCRIPTION:
LAKE CREEK TRIBUTARY NO. 22 21.0
END DESCRIPTION:
XS GIS Cut Line= 3
      3739567.83     10155961.06       3738991.9     10155683.78
      3738667.85     10155961.07
#Sta/Elev= 30
  4360.8  307.16  4427.4  301.63    4488  298.72  4538.8  293.52  4555.9  293.62
  4646.4  287.74  4742.4  283.44  4787.7  280.22  4793.6   278.6  4838.5  278.17
  4855.5  279.71  4863.4  278.66  4883.7  277.14    4929  277.16  4951.6  276.14
  4968.7  272.28  4982.3  269.18  4991.3  268.24  4995.1  266.64  4998.6  266.64
  4999.5  268.07  5007.7  267.99    5022  270.45 5026.35272.2521  5029.7  273.64
  5050.5  277.17  5099.9  280.12  5171.3  281.92  5377.8  293.77  5426.5  296.84
#Mann= 5 ,-1 , 0
  4360.8     .11       0  4863.4     .17       0  4968.7     .09       0
 5026.35     .17       0  5377.8     .11       0
Bank Sta=4968.7,5026.35
XS Rating Curve= 0 ,0
Exp/Cntr=0.3,0.1

Type RM Length L Ch R = 1 ,11179   ,445,445,445
BEGIN DESCRIPTION:
LAKE CREEK TRIBUTARY NO. 22 20.0
END DESCRIPTION:
XS GIS Cut Line= 3
      3739378.13     10155436.67       3738904.2     10155124.19
      3738482.54     10155202.28
#Sta/Elev= 30
  4426.3  284.13  4546.4  278.81  4574.5  278.53  4610.7  276.93  4646.8  276.55
  4682.9  274.93  4734.1  274.32  4786.8  271.96  4848.5  269.92  4920.8  268.77
  4935.9  266.86  4952.1  265.86  4956.9  266.17  4965.6   265.2  4992.3  264.41
  4999.8  265.16  5020.8   265.5  5039.1  264.33  5039.4  263.83  5057.8  265.28
  5072.7  265.81  5102.1  269.89  5132.6  270.31    5153   271.4  5163.2   272.7
  5274.4  276.95  5285.2  277.83  5325.9  278.75  5346.2  280.57  5422.8  283.61
#Mann= 6 ,-1 , 0
  4426.3     .11       0  4786.8     .17       0  4952.1     .11       0
  5020.8     .06       0  5057.8     .11       0  5072.7     .17       0
Bank Sta=5020.8,5057.8
XS Rating Curve= 0 ,0
Exp/Cntr=0.3,0.1

Type RM Length L Ch R = 1 ,10734   ,439,439,439
BEGIN DESCRIPTION:
LAKE CREEK TRIBUTARY NO. 22 19.0
END DESCRIPTION:
XS GIS Cut Line= 3
      3739367.87     10154511.06      3738732.33     10154809.96
      3738567.84     10154911.08
#Sta/Elev= 30
  4306.3  292.18    4315  291.27  4320.5  291.81  4328.4  290.46  4337.8  290.41
  4383.4  286.26  4443.4   282.2    4444  282.15  4485.6  280.27  4548.5  274.26
  4615.7     271  4645.2   268.4  4770.5  263.92  4781.5  262.81  4787.5  259.96
    4793  261.79  4803.6  263.11  4815.8  262.96  4833.1  260.12  4861.4  260.44
    4877  259.18  4880.5  259.18    4892   262.1  4901.5  262.98  4952.6  263.51
  4975.4  260.73  5003.8  260.58  5060.7  265.55  5151.4  272.72  5201.7   275.5
#Mann= 6 ,-1 , 0
  4306.3     .17       0  4443.4     .11       0    4444     .17       0
  4815.8     .09       0  4901.5     .17       0  5060.7     .11       0
Bank Sta=4815.8,4901.5
XS Rating Curve= 0 ,0
Exp/Cntr=0.3,0.1

Type RM Length L Ch R = 1 ,10295   ,573,573,573
BEGIN DESCRIPTION:
LAKE CREEK TRIBUTARY NO. 22 18.0
END DESCRIPTION:
XS GIS Cut Line= 3
      3739067.87     10154411.07      3738778.75     10154423.79
      3738496.25     10154615.49
#Sta/Elev= 30
  4710.6   271.2  4720.6  270.73  4740.6  268.76  4810.7  265.16  4840.7   264.4
  4850.8  263.47  4870.8  262.61  4910.8  261.62  4920.8  260.72  4970.9  260.65
  4980.9  259.34  4990.9  258.38  4995.9  257.14  4996.2  256.64  5005.6  257.45
  5020.5  257.83  5035.5  259.45  5049.4  260.78  5077.5  261.86  5085.7  261.75
  5121.9  263.37  5134.4  264.69  5151.1  265.25  5200.2  267.28  5206.5  268.19
  5214.8  268.57  5242.8  270.19  5251.1  269.83  5273.5  270.28  5341.4  271.49
#Mann= 6 ,-1 , 0
  4710.6     .15       0  4980.9     .09       0  5035.5     .15       0
  5151.1     .11       0  5214.8     .17       0  5273.5     .11       0
Bank Sta=4980.9,5035.5
XS Rating Curve= 0 ,0
Exp/Cntr=0.3,0.1

Type RM Length L Ch R = 1 ,9722    ,424,424,424
BEGIN DESCRIPTION:
LAKE CREEK TRIBUTARY NO. 22 17.0
END DESCRIPTION:
XS GIS Cut Line= 3
      3738898.97     10153712.75       3738461.5     10153990.51
      3738053.65     10154156.42
#Sta/Elev= 30
  4489.6  279.16  4538.7  273.79  4589.5  269.51  4630.2  267.16  4762.4  259.83
  4808.9  258.12  4869.9  257.21  4893.7  256.75  4908.8  257.24  4939.3  255.88
  4952.9  254.52  4981.7  255.55  4994.9  254.37  4995.2  253.87  4998.7  253.87
  5002.9  254.83  5012.5  254.82  5016.4255.6267  5025.2  256.64  5033.3  256.53
  5043.9  254.75  5054.9  256.18  5087.3  257.42  5099.7  257.29  5141.3  260.39
  5281.6  263.85  5335.6   266.8  5357.2  266.91  5378.8  268.55  5448.1   270.9
#Mann= 8 ,-1 , 0
  4489.6     .11       0  4589.5     .17       0  4630.2     .11       0
  4762.4     .17       0  4869.9     .11       0  4981.7     .07       0
  5016.4     .11       0  5099.7     .17       0
Bank Sta=4981.7,5016.4
XS Rating Curve= 0 ,0
Exp/Cntr=0.3,0.1

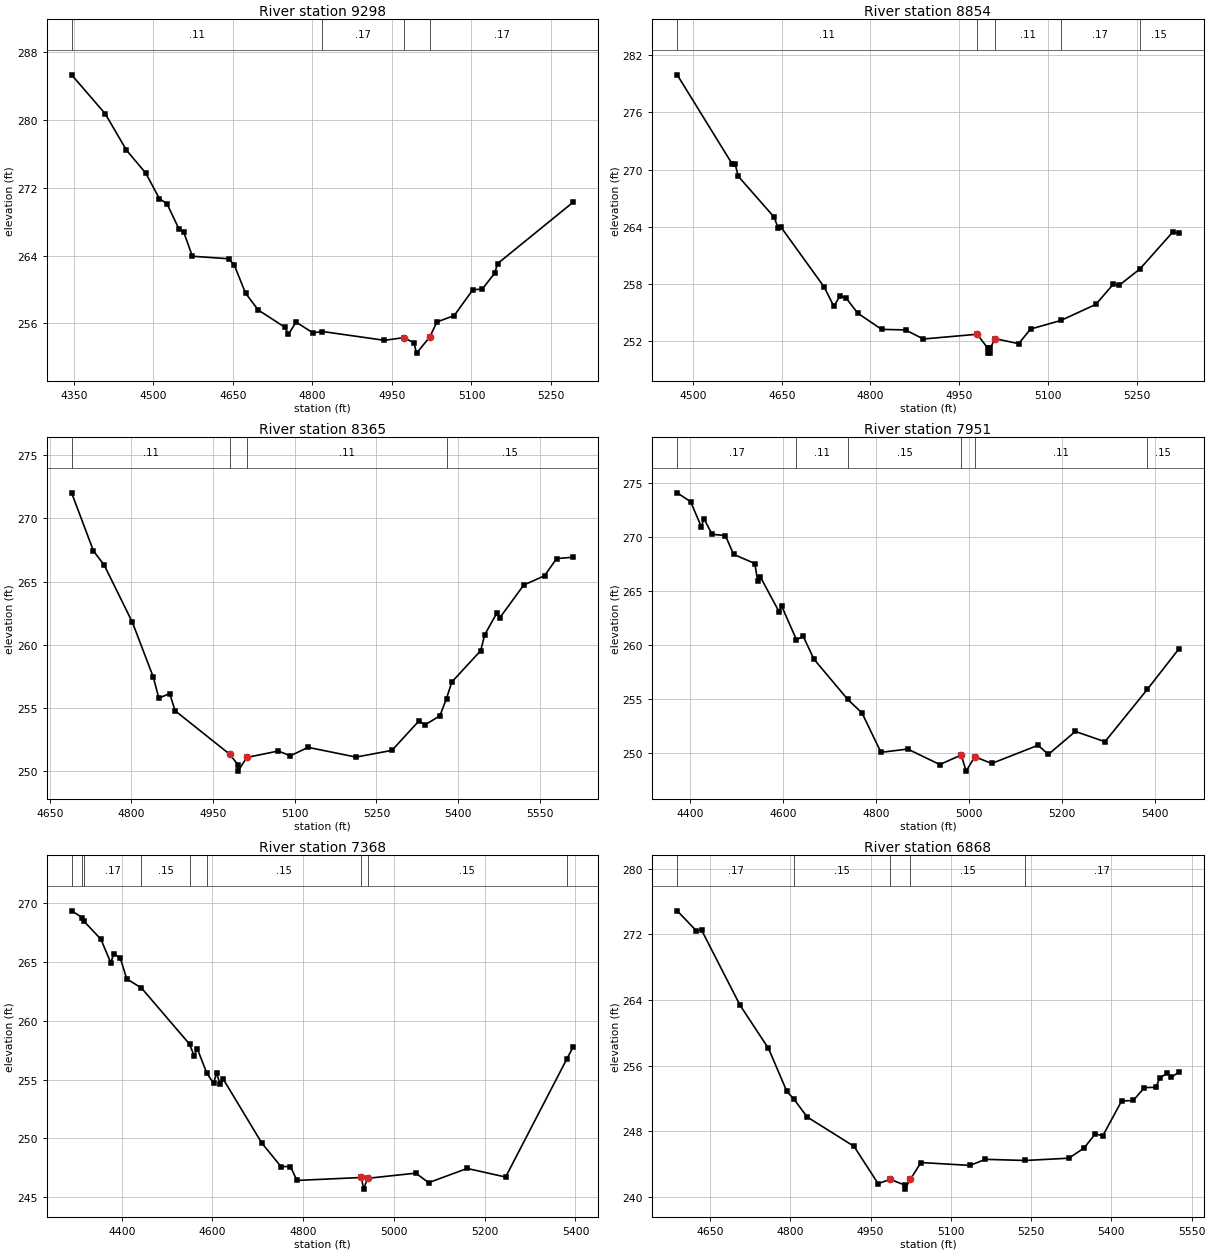
Type RM Length L Ch R = 1 ,9298    ,444,444,444
BEGIN DESCRIPTION:
LAKE CREEK TRIBUTARY NO. 22 16.0
END DESCRIPTION:
XS GIS Cut Line= 3
      3738867.83     10153561.08      3738249.69     10153776.21
      3737982.58     10153893.18
#Sta/Elev= 30
  4345.5  285.32    4409  280.72    4449  276.43  4485.4  273.73  4511.2  270.71
  4525.5  270.11  4547.6  267.19  4557.2  266.73  4573.4  263.92  4641.9  263.62
  4652.5  262.87  4673.7  259.56  4697.8  257.57  4747.8  255.55  4754.7   254.7
    4769  256.16  4800.8  254.88  4818.9  255.04  4935.9     254  4972.3  254.32
  4991.4   253.7  4996.4  252.49  5021.5   254.4  5034.8  256.17  5067.5  256.92
  5102.5  259.96  5120.5  260.05  5143.9  261.93  5149.3  263.05  5291.6  270.28
#Mann= 4 ,-1 , 0
  4345.5     .11       0  4818.9     .17       0  4972.3     .09       0
  5021.5     .17       0
Bank Sta=4972.3,5021.5
XS Rating Curve= 0 ,0
Exp/Cntr=0.3,0.1

Type RM Length L Ch R = 1 ,8854    ,489,489,489
BEGIN DESCRIPTION:
LAKE CREEK TRIBUTARY NO. 22 15.0
END DESCRIPTION:
XS GIS Cut Line= 3
      3738760.14     10153303.01      3738246.22     10153372.46
      3737917.81     10153361.07
#Sta/Elev= 30
  4473.4  279.94  4566.2  270.61  4571.3   270.6  4576.6  269.31  4637.2  265.03
  4643.9  263.91    4649  263.96  4721.6  257.72  4738.1  255.69  4748.2  256.73
  4758.3   256.6  4778.4  254.97  4818.8  253.27  4859.2  253.21  4889.4  252.26
  4980.3  252.76  4998.4  251.28  4998.6  250.78  5002.1  250.78  5002.4  251.28
  5010.4   252.3  5050.4  251.77  5070.4   253.3  5121.6   254.2  5180.9  255.89
  5210.5  258.02  5220.5   257.9  5255.3   259.6  5310.5  263.45  5320.6  263.41
#Mann= 5 ,-1 , 0
  4473.4     .11       0  4980.3     .07       0  5010.4     .11       0
  5121.6     .17       0  5255.3     .15       0
Bank Sta=4980.3,5010.4
XS Rating Curve= 0 ,0
Exp/Cntr=0.3,0.1

Type RM Length L Ch R = 1 ,8365    ,414,414,414
BEGIN DESCRIPTION:
LAKE CREEK TRIBUTARY NO. 22 14.0
END DESCRIPTION:
XS GIS Cut Line= 3
      3738667.88     10153061.07      3738358.22      10153075.4
      3737817.88     10153361.06
#Sta/Elev= 30
    4690  272.01  4730.1  267.42  4750.1  266.28  4801.7  261.77  4840.2  257.43
  4850.2  255.78  4870.2  256.14  4880.2  254.78  4980.3  251.35  4995.7  250.51
  4995.9  250.01  5011.7  251.09  5069.8   251.6  5091.8  251.22  5124.5  251.89
  5212.5  251.12  5278.6  251.65  5328.4  253.99  5338.9  253.66  5366.6  254.38
  5378.8  255.75  5388.6  257.06  5441.6  259.53    5449  260.79    5471  262.49
  5476.7  262.13  5520.7  264.72    5559  265.46    5581  266.81  5611.2  266.92
#Mann= 4 ,-1 , 0
    4690     .11       0  4980.3     .07       0  5011.7     .11       0
  5378.8     .15       0
Bank Sta=4980.3,5011.7
XS Rating Curve= 0 ,0
Exp/Cntr=0.3,0.1

Type RM Length L Ch R = 1 ,7951    ,583,583,583
BEGIN DESCRIPTION:
LAKE CREEK TRIBUTARY NO. 22 13.0
END DESCRIPTION:
XS GIS Cut Line= 3
      3738760.14     10152594.66      3738190.66     10152851.62
      3737817.83     10153111.09
#Sta/Elev= 30
  4372.5  274.07  4401.3  273.25  4424.5  270.93    4430  271.68  4447.6  270.23
  4476.2  270.12  4493.9  268.38  4539.6  267.53  4545.6  265.92  4551.1  266.32
  4591.8  263.07  4597.3   263.6  4629.2  260.48  4643.6  260.81  4666.7  258.69
  4739.4  254.97  4770.2  253.71    4811  250.07  4868.7  250.37  4937.6  248.94
  4983.8  249.82  4994.3  248.33  5012.9  249.66  5049.4  249.04    5149  250.72
  5171.3  249.88  5229.4     252  5293.1  251.05  5384.4   255.9  5451.5   259.6
#Mann= 6 ,-1 , 0
  4372.5     .17       0  4629.2     .11       0  4739.4     .15       0
  4983.8     .09       0  5012.9     .11       0  5384.4     .15       0
Bank Sta=4983.8,5012.9
XS Rating Curve= 0 ,0
Exp/Cntr=0.3,0.1

Type RM Length L Ch R = 1 ,7368    ,500,500,500
BEGIN DESCRIPTION:
LAKE CREEK TRIBUTARY NO. 22 12.0
END DESCRIPTION:
XS GIS Cut Line= 3
      3738273.99     10151955.79      3737799.23     10152484.39
      3737517.87     10152761.05
#Sta/Elev= 30
  4289.5  269.36  4313.2  268.78  4315.8  268.51  4354.1  266.94  4375.8  264.94
  4382.5   265.7  4396.7  265.36  4410.9  263.57  4443.5  262.79  4549.5  258.01
  4559.6  257.01  4566.4  257.64  4587.2  255.57  4602.3  254.67    4609  255.55
  4616.5  254.63  4623.2  255.07  4708.4  249.61    4751  247.59  4771.9  247.59
  4786.1  246.41  4928.2  246.66  4933.1  245.67  4941.8  246.59  5048.1  247.03
  5076.4  246.22  5161.3  247.43  5246.1   246.7  5381.4  256.78  5394.6  257.75
#Mann= 9 ,-1 , 0
  4289.5     .17       0  4313.2     .11       0  4315.8     .17       0
  4443.5     .15       0  4549.5     .17       0  4587.2     .15       0
  4928.2     .09       0  4941.8     .15       0  5381.4     .17       0
Bank Sta=4928.2,4941.8
XS Rating Curve= 0 ,0
Exp/Cntr=0.3,0.1

Type RM Length L Ch R = 1 ,6868    ,497,497,497
BEGIN DESCRIPTION:
LAKE CREEK TRIBUTARY NO. 22 11.0
END DESCRIPTION:
XS GIS Cut Line= 3
      3737917.85     10151961.07      3737556.34     10152157.03
      3737167.86     10152511.06
#Sta/Elev= 30
  4588.8  274.87  4624.4  272.45  4634.3  272.53  4706.2  263.37  4759.4   258.1
  4793.7  252.87  4806.8  251.93  4831.7  249.75  4919.2  246.17  4964.2  241.63
  4986.9  242.15  5013.8  241.46    5014  240.96  5024.6242.1609  5044.2   244.2
  5136.1  243.85  5164.5  244.59  5238.8  244.45  5320.5  244.73  5348.9  245.96
  5369.9  247.68  5384.1  247.47  5419.2   251.7  5440.8  251.76  5461.8  253.33
  5483.4  253.37  5490.1  254.47  5504.3  255.09  5511.8  254.58  5525.6  255.19
#Mann= 5 ,-1 , 0
  4588.8     .17       0  4806.8     .15       0  4986.9     .09       0
  5024.6     .15       0  5238.8     .17       0
Bank Sta=4986.9,5024.6
XS Rating Curve= 0 ,0
Exp/Cntr=0.3,0.1

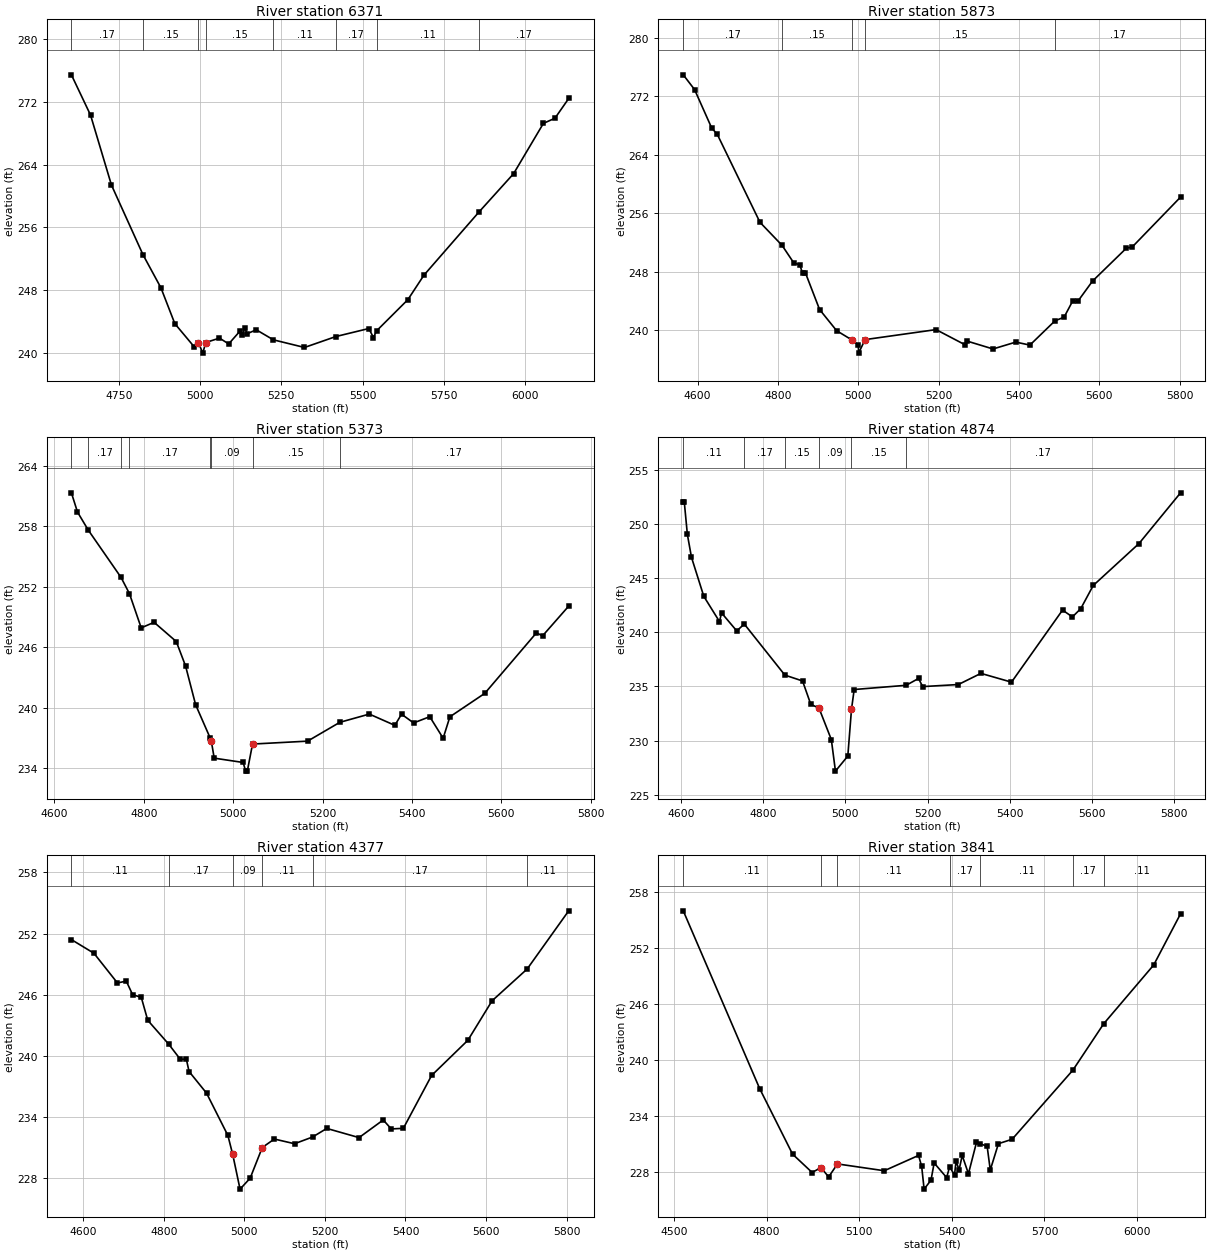
Type RM Length L Ch R = 1 ,6371    ,498,498,498
BEGIN DESCRIPTION:
LAKE CREEK TRIBUTARY NO. 22 10.0
END DESCRIPTION:
XS GIS Cut Line= 3
      3737567.86     10151661.06      3737231.73     10151870.79
      3736417.87     10152661.05
#Sta/Elev= 30
  4603.8  275.41  4662.7  270.29  4727.1  261.39  4824.3  252.52  4879.3  248.33
  4922.1  243.77    4981  240.86  4994.9  241.34  5008.2  240.02  5017.2  241.37
  5059.6  241.93  5087.9  241.19  5123.1  242.84  5130.3  242.36  5137.3  243.27
  5144.5  242.48  5172.7  242.99  5225.5  241.71  5321.2  240.74  5417.8  242.13
  5519.3  243.15  5533.4     242    5543  242.85  5639.4  246.82  5688.8  249.93
  5857.9  257.95  5964.8  262.84  6056.6  269.24  6092.1  269.89  6134.4   272.4
#Mann= 8 ,-1 , 0
  4603.8     .17       0  4824.3     .15       0  4994.9     .09       0
  5017.2     .15       0  5225.5     .11       0  5417.8     .17       0
    5543     .11       0  5857.9     .17       0
Bank Sta=4994.9,5017.2
XS Rating Curve= 0 ,0
Exp/Cntr=0.3,0.1

Type RM Length L Ch R = 1 ,5873    ,500,500,500
BEGIN DESCRIPTION:
LAKE CREEK TRIBUTARY NO. 22 9.0
END DESCRIPTION:
XS GIS Cut Line= 3
      3737167.87     10151261.05      3736863.24     10151572.56
      3736317.83      10152161.1
#Sta/Elev= 30
  4564.3  274.94  4592.5  272.92    4635  267.67  4649.1  266.78  4755.3  254.75
  4810.2   251.6  4840.1  249.14  4854.3  248.96  4861.3  247.77  4868.4  247.84
  4903.7  242.81  4946.2  239.91 4984.86238.6213    5000  237.96  5000.9  236.84
  5016.9  238.69  5193.7  240.06  5264.6  238.02  5271.4  238.48  5335.5  237.41
  5392.2  238.35  5427.3  237.94  5489.9  241.27  5512.4  241.76  5533.4  243.93
  5547.5     244  5583.2   246.7  5667.7  251.22  5681.9  251.36  5802.4   258.2
#Mann= 5 ,-1 , 0
  4564.3     .17       0  4810.2     .15       0 4984.86     .09       0
  5016.9     .15       0  5489.9     .17       0
Bank Sta=4984.86,5016.9
XS Rating Curve= 0 ,0
Exp/Cntr=0.3,0.1

Type RM Length L Ch R = 1 ,5373    ,499,499,499
BEGIN DESCRIPTION:
LAKE CREEK TRIBUTARY NO. 22 8.0
END DESCRIPTION:
XS GIS Cut Line= 3
      3736817.88     10151061.05      3736534.43     10151286.23
      3736117.84     10151911.09
#Sta/Elev= 30
    4638  261.34  4651.6  259.43  4675.8  257.63    4749  252.94  4767.9  251.32
  4794.2  247.92  4823.1  248.47  4872.7  246.56  4893.5  244.13    4916  240.28
    4949  236.93  4951.2  236.65  4957.6  234.97  5022.4  234.54    5028  233.68
  5031.7  233.68  5043.4  236.37  5166.6  236.66  5238.7  238.53  5304.8  239.35
  5361.9  238.23  5376.9  239.34  5403.9  238.47    5440  239.09    5470  236.95
  5485.1  239.08  5563.2  241.41  5678.9  247.43  5692.4  247.12    5751  250.08
#Mann= 8 ,-1 , 0
    4638     .15       0  4675.8     .17       0    4749     .15       0
  4767.9     .17       0    4949     .15       0  4951.2     .09       0
  5043.4     .15       0  5238.7     .17       0
Bank Sta=4951.2,5043.4
XS Rating Curve= 0 ,0
Exp/Cntr=0.3,0.1

Type RM Length L Ch R = 1 ,4874    ,497,497,497
BEGIN DESCRIPTION:
LAKE CREEK TRIBUTARY NO. 22 7.0
END DESCRIPTION:
XS GIS Cut Line= 3
      3736117.85     10150761.12      3736096.25     10151155.22
      3735967.85     10151961.06
#Sta/Elev= 30
  4605.3  252.02  4607.8  252.02  4615.3  249.03  4625.3  246.92  4655.3  243.32
  4693.5  240.99  4698.5  241.79  4735.5  240.13  4753.9  240.76  4852.7  236.05
  4895.7  235.51  4915.7  233.36  4935.8     233  4965.8   230.1  4975.8  227.19
  5005.9  228.58 5014.86232.8914  5021.4  234.72  5147.9  235.11  5178.1  235.74
  5188.2  234.99    5275  235.18    5330  236.21  5404.4   235.4  5528.7  242.05
  5552.7  241.42    5573  242.18  5603.4  244.32  5714.8  248.19    5816  252.87
#Mann= 6 ,-1 , 0
  4605.3     .11       0  4753.9     .17       0  4852.7     .15       0
  4935.8     .09       0 5014.86     .15       0  5147.9     .17       0
Bank Sta=4935.8,5014.86
XS Rating Curve= 0 ,0
Exp/Cntr=0.3,0.1

Type RM Length L Ch R = 1 ,4377    ,536,536,536
BEGIN DESCRIPTION:
LAKE CREEK TRIBUTARY NO. 22 6.0
END DESCRIPTION:
XS GIS Cut Line= 3
      3735836.48     10150782.21      3735626.12     10151156.78
      3735667.85      10151961.1
#Sta/Elev= 30
  4570.4  251.41  4626.4  250.07  4684.7  247.16  4706.7  247.34  4722.3  246.02
    4744  245.74    4760   243.5  4811.8  241.17    4841  239.67  4855.8  239.69
  4862.6  238.48    4906  236.36    4959  232.21    4971  230.35  4989.2  226.95
  5014.3  228.02  5044.4  231.03  5074.4  231.86  5124.5   231.4  5169.4  232.06
  5204.6   232.9  5284.7     232  5344.8  233.73  5364.8  232.85  5394.8  232.91
  5464.9  238.09    5555  241.54  5615.1  245.41  5702.3  248.53  5805.4  254.23
#Mann= 6 ,-1 , 0
  4570.4     .11       0  4811.8     .17       0    4971     .09       0
  5044.4     .11       0  5169.4     .17       0  5702.3     .11       0
Bank Sta=4971,5044.4
XS Rating Curve= 0 ,0
Exp/Cntr=0.3,0.1

Type RM Length L Ch R = 1 ,3841    ,635,635,635
BEGIN DESCRIPTION:
LAKE CREEK TRIBUTARY NO. 22 5.0
END DESCRIPTION:
XS GIS Cut Line= 3
      3735567.85     10150561.07      3735225.38      10150879.4
       3735385.1     10152011.32
#Sta/Elev= 30
    4530  255.94  4777.5  236.89    4884  229.87  4947.5   227.9  4975.9  228.43
  5000.9  227.43  5029.5  228.82    5181  228.09  5292.1  229.73  5302.2  228.55
  5310.1  226.12  5332.4  227.08  5342.6  228.92    5383  227.36  5392.7   228.5
  5408.6  227.64  5413.6  229.12  5423.4  228.18  5433.5  229.73  5453.7  227.77
  5479.7  231.12  5492.5  230.98  5514.3   230.7  5524.4  228.17  5550.8  230.99
  5595.1  231.46    5792  238.87  5891.8  243.84  6053.8  250.14  6140.7  255.62
#Mann= 7 ,-1 , 0
    4530     .11       0  4975.9     .06       0  5029.5     .11       0
  5392.7     .17       0  5492.5     .11       0    5792     .17       0
  5891.8     .11       0
Bank Sta=4975.9,5029.5
XS Rating Curve= 0 ,0
Exp/Cntr=0.3,0.1

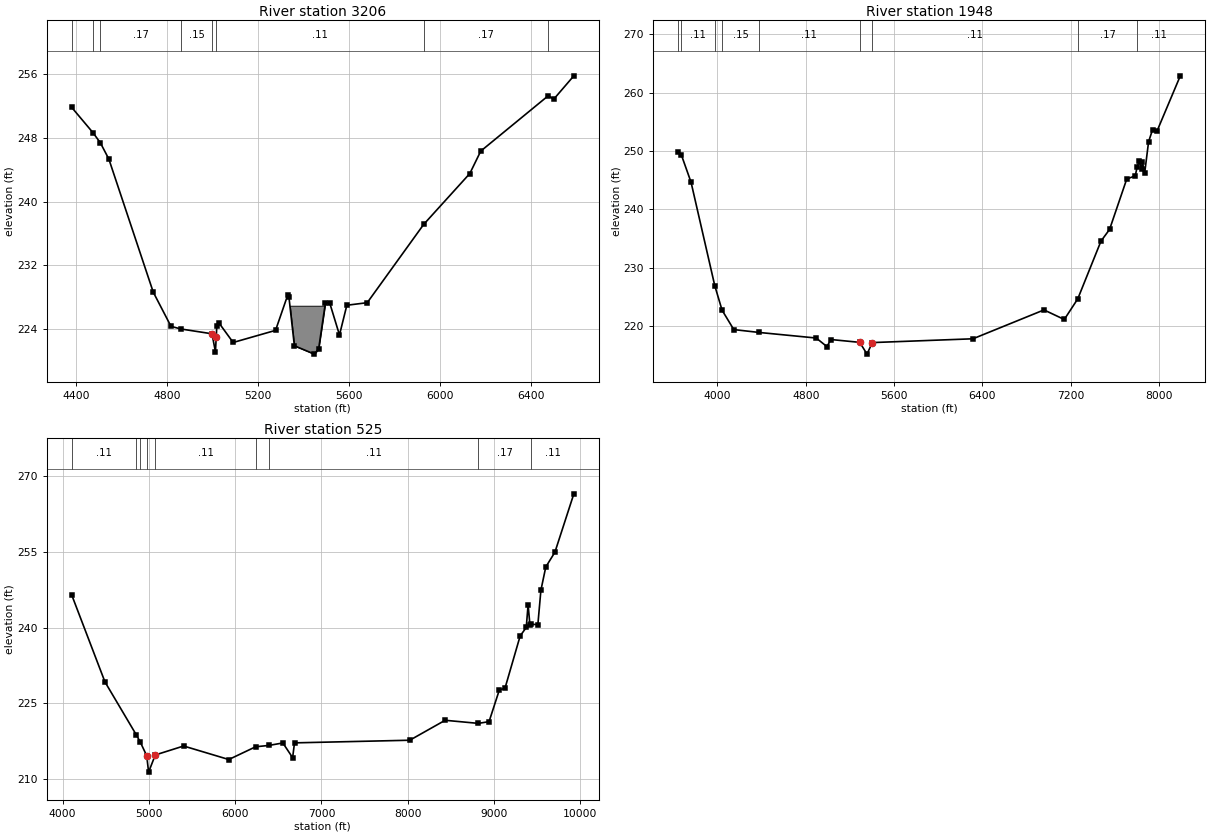
Type RM Length L Ch R = 1 ,3206    ,1258,1258,1258
BEGIN DESCRIPTION:
LAKE CREEK TRIBUTARY NO. 22 4.0
END DESCRIPTION:
XS GIS Cut Line= 3
      3735260.14     10150296.05      3734642.05     10150705.79
      3735197.42     10152066.44
#Sta/Elev= 30
  4378.7  251.83  4472.9  248.64  4505.1  247.38  4542.5  245.34    4738  228.65
  4816.2  224.36  4860.4  224.03  4996.7  223.43  5011.8  221.17  5015.3  223.03
  5017.8  224.36  5026.8  224.81  5089.9  222.34  5276.5  223.86  5329.9  228.27
  5335.3  228.07  5359.4  221.93  5447.6  220.88  5466.3  221.56  5495.7  227.25
  5514.4  227.35    5558  223.28  5590.4  227.01  5680.2  227.33  5928.8  237.15
  6131.9  243.53    6180  246.34    6478   253.3  6500.8  252.83  6589.9  255.78
#Mann= 8 ,-1 , 0
  4378.7     .17       0  4472.9     .11       0  4505.1     .17       0
  4860.4     .15       0  4996.7     .09       0  5015.3     .11       0
  5928.8     .17       0    6478     .11       0
#Block Obstruct= 1 ,-1
  5340.3 5506.06  226.95
Bank Sta=4996.7,5015.3
XS Rating Curve= 0 ,0
Exp/Cntr=0.3,0.1

Type RM Length L Ch R = 1 ,1948    ,1423,1423,1423
BEGIN DESCRIPTION:
LAKE CREEK TRIBUTARY NO. 22 3.0
END DESCRIPTION:
XS GIS Cut Line= 5
      3735169.79     10150247.45      3733820.11     10150115.66
      3733655.94     10150059.96       3733461.5     10150553.01
      3735253.04     10152282.06
#Sta/Elev= 30
  3643.9  249.79  3674.1  249.31  3761.2  244.65  3975.8  226.94  4041.9  222.73
  4148.2   219.4    4376  218.91  4894.8  217.95  4991.5  216.49  5029.3  217.69
  5289.1  217.21  5355.2  215.19  5402.8  217.17  6314.7  217.82  6958.3  222.77
  7142.2  221.13  7264.3  224.67  7474.6  234.57  7552.3  236.57  7707.9  245.21
  7785.6  245.77    7802   247.3  7821.1   248.3  7842.2  246.88  7849.4  248.12
  7870.5  246.27    7906  251.63  7941.3  253.64  7983.7   253.5  8193.2  262.91
#Mann= 9 ,-1 , 0
  3643.9     .17       0  3674.1     .11       0  3975.8     .17       0
  4041.9     .15       0    4376     .11       0  5289.1     .06       0
  5402.8     .11       0  7264.3     .17       0    7802     .11       0
Bank Sta=5289.1,5402.8
XS Rating Curve= 0 ,0
Exp/Cntr=0.3,0.1

Type RM Length L Ch R = 1 ,525     ,0,0,0
BEGIN DESCRIPTION:
LAKE CREEK TRIBUTARY NO. 22 1.0
END DESCRIPTION:
XS GIS Cut Line= 5
      3735593.45     10149671.07       3734771.6     10149315.42
      3733933.72     10149233.57      3733364.27     10150559.96
      3735252.43     10152406.46
#Sta/Elev= 30
  4104.5  246.47  4490.6  229.26  4855.1  218.77  4902.1   217.3    4975  214.67
  4996.4  211.44  5074.1  214.83  5402.7   216.6  5926.2  213.93  6237.8  216.45
  6389.6  216.71  6552.9   217.2  6666.2   214.3    6688  217.22  8024.1  217.74
  8434.3  221.68  8818.9  221.07  8943.3  221.41  9063.6  227.72  9127.2  227.96
  9304.1  238.35  9374.7  240.01    9396  244.52  9417.1  240.51  9432.6  240.66
  9509.1  240.56  9544.4  247.36    9601  251.96  9707.1  254.89  9926.3  266.41
#Mann= 9 ,-1 , 0
  4104.5     .11       0  4855.1     .15       0  4902.1     .11       0
    4975     .06       0  5074.1     .11       0  6237.8     .15       0
  6389.6     .11       0  8818.9     .17       0  9432.6     .11       0
Bank Sta=4975,5074.1
XS Rating Curve= 0 ,0
Exp/Cntr=0.3,0.1

Chan Stop Cuts=-1
Use User Specified Reach Order=0
Composite Channel Slope=5