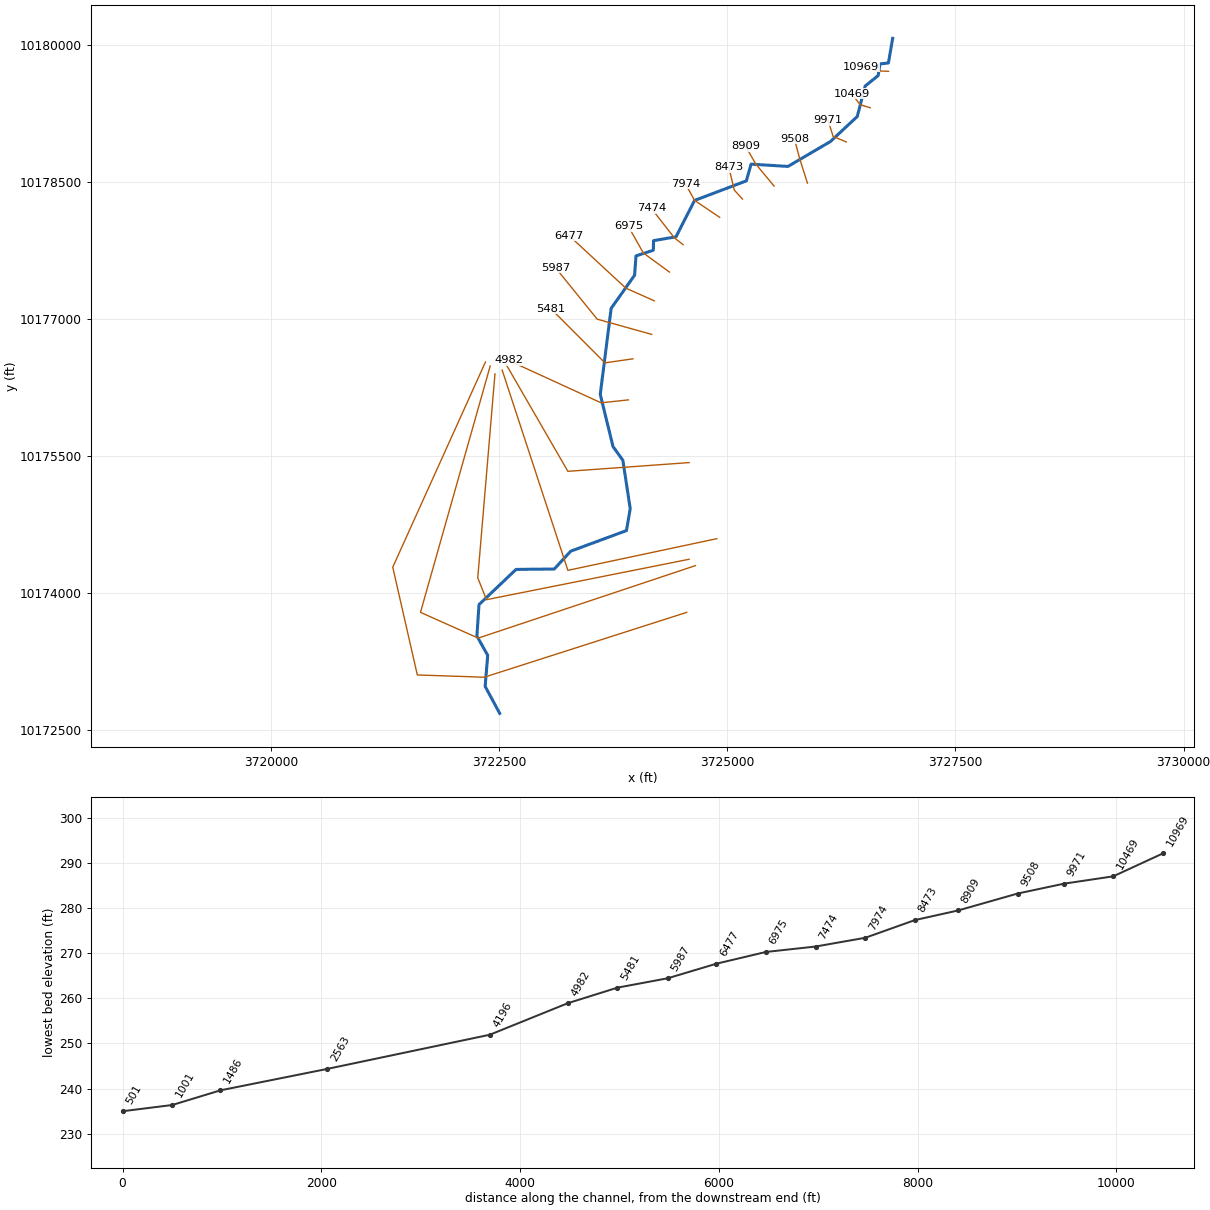
--- LAKE CREEK TRIBUTARY NO 27.prj (project) ---

Proj Title=LAKE CREEK TRIBUTARY NO 27 Base Level Engineering
Current Plan=p01
Default Exp/Contr=0.3,0.1
English Units
Geom File=g01
Flow File=f01
Plan File=p01
Y Axis Title=Elevation
X Axis Title(PF)=Main Channel Distance
X Axis Title(XS)=Station
BEGIN DESCRIPTION:
LAKE CREEK TRIBUTARY NO 27
END DESCRIPTION:
DSS Export Rating Curves= 0
DSS Export Rating Curve Sorted= 0
DSS Export Volume Flow Curves= 0
DXF OffsetX= 0
DXF OffsetY= 0
DXF ScaleX= 1
DXF ScaleY= 10

--- LAKE CREEK TRIBUTARY NO 27.p01 (plan) ---

Plan Title=Multiple Run
Short Identifier=Multiple
Geom File=g01
Flow File=f01
Subcritical Flow
K Sum by GR= 0
Std Step Tol= 0.01
Critical Tol= 0.01
Num of Std Step Trials= 20
Max Error Tol= 0.3
Flow Tol Ratio= 0.001
Split Flow NTrial= 30
Split Flow Tol= 0.02
Split Flow Ratio= 0.02
Log Output Level= 0
Friction Slope Method= 1
Unsteady Friction Slope Method= 2
Unsteady Bridges Friction Slope Method= 1
Parabolic Critical Depth
Global Vel Dist=  1 , 1 , 1
Global Log Level= 0
CheckData=True
Encroach Param= -1, 0, 0, 0
BEGIN DESCRIPTION:
Multiple Run
END DESCRIPTION:

--- LAKE CREEK TRIBUTARY NO 27.f01 (steady flow) ---

Flow Title=Multiple
Program Version=4.10
Number of Profiles= 7
Profile Names=10-year,25-year,50-year,1pct_min,100-year,1pct_plu,500-year
River Rch & RM=LAKE CREEK TRIBU,Reach-1         ,10969
     535     721     973     432    1304    3938    2423
River Rch & RM=LAKE CREEK TRIBU,Reach-1         ,5481
     879    1219    1672     754    2278    6879    4371
Boundary for River Rch & Prof#=LAKE CREEK TRIBU,Reach-1         , 1
Up Type= 0
Dn Type= 3
Dn Slope=0.005
Boundary for River Rch & Prof#=LAKE CREEK TRIBU,Reach-1         , 2
Up Type= 0
Dn Type= 3
Dn Slope=0.005
Boundary for River Rch & Prof#=LAKE CREEK TRIBU,Reach-1         , 3
Up Type= 0
Dn Type= 3
Dn Slope=0.005
Boundary for River Rch & Prof#=LAKE CREEK TRIBU,Reach-1         , 4
Up Type= 0
Dn Type= 3
Dn Slope=0.005
Boundary for River Rch & Prof#=LAKE CREEK TRIBU,Reach-1         , 5
Up Type= 0
Dn Type= 3
Dn Slope=0.005
Boundary for River Rch & Prof#=LAKE CREEK TRIBU,Reach-1         , 6
Up Type= 0
Dn Type= 3
Dn Slope=0.005
Boundary for River Rch & Prof#=LAKE CREEK TRIBU,Reach-1         , 7
Up Type= 0
Dn Type= 3
Dn Slope=0.005
DSS Import GetInterval= 0
DSS Import GetPeak= 0
DSS Import FillOption= 0

--- LAKE CREEK TRIBUTARY NO 27.g01 (geometry) ---

Geom Title=Existing Conditions
Program Version=4.10

River Reach=LAKE CREEK TRIBU,Reach-1
Reach XY= 30
      3726813.23     10180071.84      3726766.62     10179801.75
      3726674.14     10179791.68       3726654.2     10179663.73
      3726511.63     10179549.14      3726425.11     10179215.26
      3726131.65      10178941.6      3725666.52     10178668.54
       3725261.8     10178693.56      3725210.24     10178510.47
      3724643.12     10178296.23      3724439.25     10177897.48
      3724193.27     10177855.42      3724191.31     10177750.81
      3724001.23      10177688.6      3723985.96     10177476.99
      3723729.24     10177113.56      3723609.79     10176171.78
      3723749.67     10175599.34      3723857.65      10175448.5
      3723937.94     10174919.24      3723896.91     10174679.31
       3723286.5     10174453.81      3723105.87     10174258.16
      3722687.45     10174254.03       3722281.3     10173868.29
      3722258.51     10173523.75      3722376.89     10173312.69
      3722348.74     10172972.88      3722508.23     10172676.84

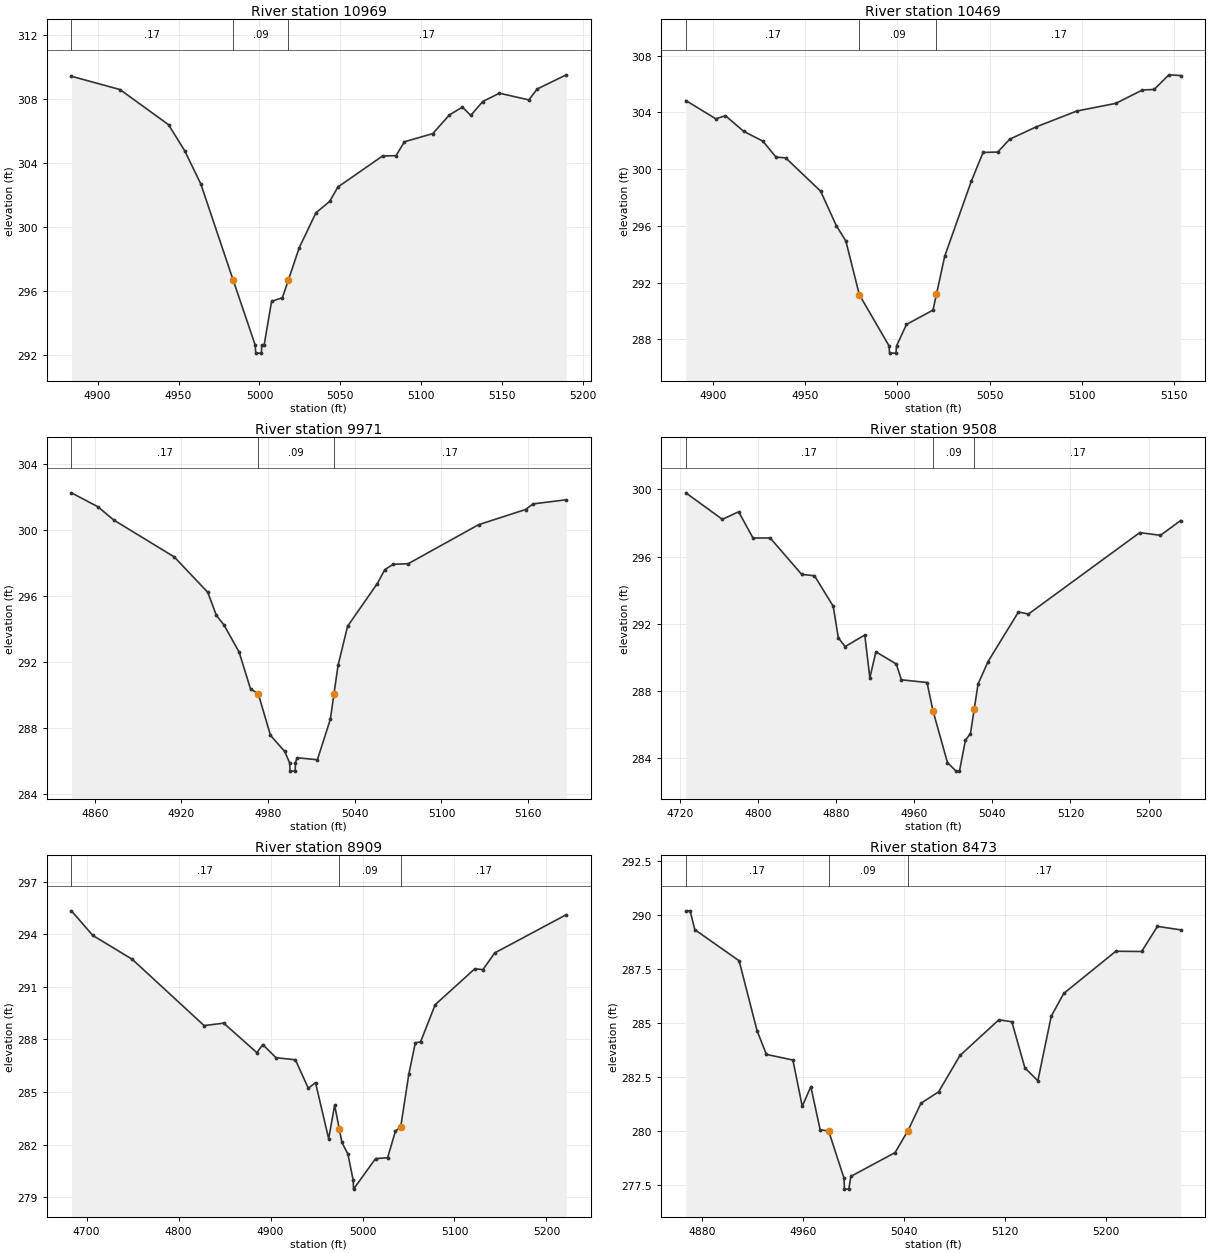
Type RM Length L Ch R = 1 ,10969   ,500,500,500
BEGIN DESCRIPTION:
LAKE CREEK TRIBUTARY NO. 27 17.0
END DESCRIPTION:
XS GIS Cut Line= 3
      3726767.81     10179711.07      3726651.66     10179714.63
      3726467.84     10179761.08
#Sta/Elev= 30
  4883.8  309.44  4913.8  308.61  4943.8  306.41  4953.8  304.78  4963.8  302.69
  4983.8  296.67  4997.4  292.61  4997.7  292.11  5001.2  292.11  5001.4  292.61
  5002.9  292.61  5007.5  295.35  5014.2  295.58 5017.88296.6874  5024.6  298.71
  5034.9  300.89  5043.4  301.61  5048.5  302.51  5076.1  304.45  5084.4  304.47
  5089.6  305.34  5107.1  305.85  5117.4  307.02  5125.4  307.51  5130.6  306.99
    5138  307.86  5148.3  308.38  5166.5  307.96  5171.6  308.64  5189.6  309.53
#Mann= 3 , 0 , 0
  4883.8     .17       0  4983.8     .09       0 5017.88     .17       0
Bank Sta=4983.8,5017.88
XS Rating Curve= 0 ,0
Exp/Cntr=0.3,0.1

Type RM Length L Ch R = 1 ,10469   ,498,498,498
BEGIN DESCRIPTION:
LAKE CREEK TRIBUTARY NO. 27 16.0
END DESCRIPTION:
XS GIS Cut Line= 3
      3726567.83     10179311.08      3726458.03     10179344.92
      3726362.17     10179465.19
#Sta/Elev= 30
  4885.1  304.83  4901.4  303.54  4906.6  303.76  4916.5  302.66  4926.9  301.97
  4934.1  300.84  4939.3  300.79  4958.3  298.44  4966.8  296.02    4972  294.93
  4979.3  291.15  4995.5  287.53  4995.7  287.03  4999.2  287.03  4999.5  287.53
  5004.9  289.05  5019.3  290.06 5021.18291.1794  5025.7  293.87  5040.1  299.14
  5046.5  301.17  5054.5   301.2  5060.9   302.1  5075.3  302.97  5097.4  304.09
  5118.6  304.63    5133  305.57  5139.4  305.61  5147.4  306.64  5153.8  306.59
#Mann= 3 , 0 , 0
  4885.1     .17       0  4979.3     .09       0 5021.18     .17       0
Bank Sta=4979.3,5021.18
XS Rating Curve= 0 ,0
Exp/Cntr=0.3,0.1

Type RM Length L Ch R = 1 ,9971    ,463,463,463
BEGIN DESCRIPTION:
LAKE CREEK TRIBUTARY NO. 27 15.0
END DESCRIPTION:
XS GIS Cut Line= 3
      3726304.78     10178936.85      3726160.89     10178997.62
      3726105.19     10179175.51
#Sta/Elev= 30
  4843.8  302.24  4862.1   301.4    4873   300.6    4915  298.36  4938.2  296.22
  4944.1  294.83  4949.5  294.23  4959.9   292.6  4967.8  290.37  4973.2  290.07
  4981.6  287.56  4991.5  286.58  4994.9  285.89  4995.2  285.39  4998.7  285.39
  4998.9  285.89    5000   286.2  5014.1  286.08  5023.1  288.54  5025.6290.0731
  5028.4  291.79    5035  294.16  5055.6  296.75  5060.8  297.59  5066.5  297.91
    5077  297.95  5125.7  300.31  5158.2  301.23  5163.4  301.57  5186.4  301.82
#Mann= 3 , 0 , 0
  4843.8     .17       0  4973.2     .09       0  5025.6     .17       0
Bank Sta=4973.2,5025.6
XS Rating Curve= 0 ,0
Exp/Cntr=0.3,0.1

Type RM Length L Ch R = 1 ,9508    ,599,599,599
BEGIN DESCRIPTION:
LAKE CREEK TRIBUTARY NO. 27 14.0
END DESCRIPTION:
XS GIS Cut Line= 3
      3725879.47     10178485.46      3725797.01     10178745.86
      3725736.24     10178971.57
#Sta/Elev= 30
    4726   299.8  4763.4  298.22  4780.1  298.67  4794.8  297.11  4812.4  297.11
  4844.7  294.94  4857.8  294.86    4877  293.04  4882.2  291.16  4889.2  290.64
  4909.3  291.33  4914.5  288.78  4920.7  290.33  4941.6   289.6  4946.8  288.66
  4973.1   288.5  4979.1  286.83    4994  283.73  5002.8  283.22  5006.3  283.22
  5012.4  285.06  5017.6  285.46 5021.35286.8919  5025.3   288.4  5035.6  289.75
  5066.7   292.7    5077  292.58    5191  297.43  5212.2  297.27  5232.9  298.15
#Mann= 3 , 0 , 0
    4726     .17       0  4979.1     .09       0 5021.35     .17       0
Bank Sta=4979.1,5021.35
XS Rating Curve= 0 ,0
Exp/Cntr=0.3,0.1

Type RM Length L Ch R = 1 ,8909    ,436,436,436
BEGIN DESCRIPTION:
LAKE CREEK TRIBUTARY NO. 27 13.0
END DESCRIPTION:
XS GIS Cut Line= 3
      3725513.76     10178453.59      3725312.35     10178696.67
      3725202.05     10178889.69
#Sta/Elev= 30
  4683.5  295.33  4706.7  293.93  4749.6  292.57  4827.8  288.79  4849.1  288.93
  4885.1  287.25  4891.6  287.71  4905.9  286.96    4927  286.84  4941.1  285.22
  4948.9  285.54  4963.2  282.34  4969.7  284.26 4974.73282.9039  4977.6  282.13
  4984.1  281.47  4989.9  279.97  4990.2  279.47  5014.2  281.21  5027.3  281.26
  5035.8  282.78  5041.5  283.01  5050.3  286.01  5057.4  287.81  5063.1  287.86
    5079  289.98  5122.1  292.03  5130.9  291.98  5143.7  292.93  5221.5  295.11
#Mann= 3 , 0 , 0
  4683.5     .17       0 4974.73     .09       0  5041.5     .17       0
Bank Sta=4974.73,5041.5
XS Rating Curve= 0 ,0
Exp/Cntr=0.3,0.1

Type RM Length L Ch R = 1 ,8473    ,499,499,499
BEGIN DESCRIPTION:
LAKE CREEK TRIBUTARY NO. 27 12.0
END DESCRIPTION:
XS GIS Cut Line= 3
      3725167.83     10178311.09      3725078.24     10178409.12
      3725017.85     10178661.08
#Sta/Elev= 30
  4867.2   290.2  4870.6   290.2  4874.3  289.33  4909.4  287.89  4923.6  284.66
    4931  283.56    4952   283.3  4959.4  281.16  4966.2  282.07  4973.6  280.07
  4980.3  280.02  4992.5  277.83  4992.8  277.33  4996.3  277.33  4997.9  277.92
  5032.9  279.02  5043.1  280.03  5053.4   281.3  5067.4  281.83  5084.3  283.51
  5115.1  285.16  5125.4  285.07  5135.7  282.94    5146  282.34  5156.6  285.33
  5166.5  286.38  5207.7  288.33  5228.2  288.32  5240.7  289.48  5259.1  289.32
#Mann= 3 , 0 , 0
  4867.2     .17       0  4980.3     .09       0  5043.1     .17       0
Bank Sta=4980.3,5043.1
XS Rating Curve= 0 ,0
Exp/Cntr=0.3,0.1

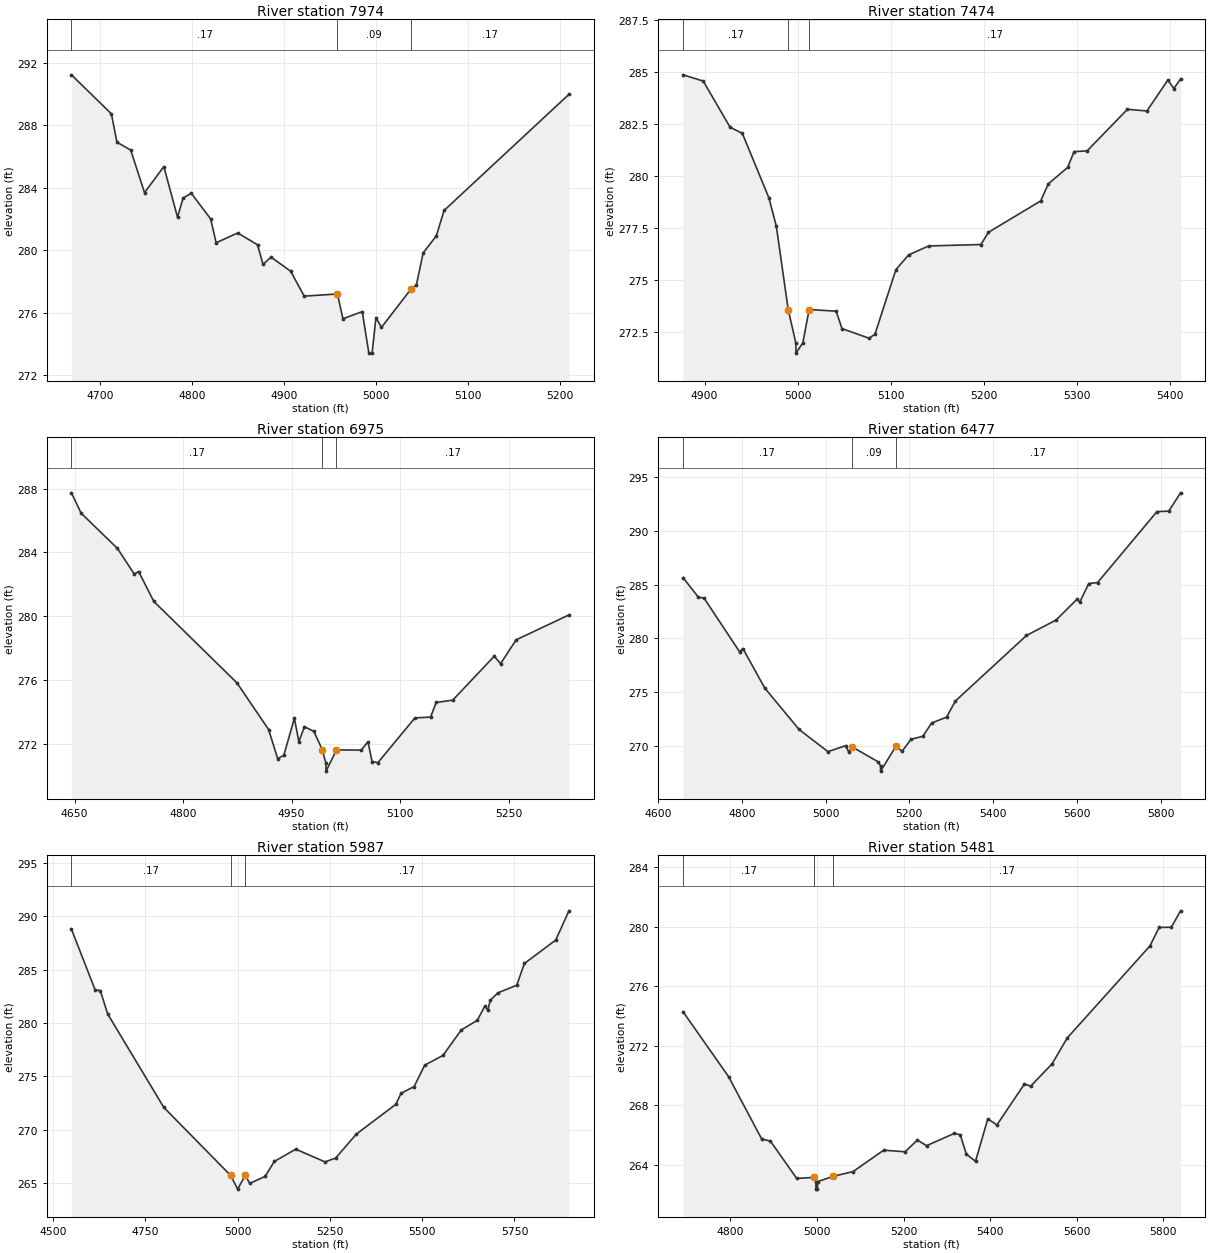
Type RM Length L Ch R = 1 ,7974    ,500,500,500
BEGIN DESCRIPTION:
LAKE CREEK TRIBUTARY NO. 27 11.0
END DESCRIPTION:
XS GIS Cut Line= 3
      3724917.85     10178111.07      3724643.12     10178296.23
      3724542.19     10178480.16
#Sta/Elev= 30
  4668.7  291.24  4712.2  288.74  4718.2  286.92  4733.2  286.42  4748.2  283.69
  4769.2  285.36  4784.1  282.12  4790.2  283.35  4799.1  283.65  4820.1  282.01
  4826.1  280.48  4849.6  281.11  4871.1  280.35  4877.1  279.09  4885.8  279.56
  4907.1  278.66  4921.9  277.06    4958   277.2    4964  275.61    4985  276.07
  4992.2  273.41  4995.7  273.41  4999.9  275.68  5005.9  275.06  5038.1  277.52
  5043.8  277.76  5051.2  279.82  5065.6  280.93    5074  282.55  5209.8  289.99
#Mann= 3 , 0 , 0
  4668.7     .17       0    4958     .09       0  5038.1     .17       0
Bank Sta=4958,5038.1
XS Rating Curve= 0 ,0
Exp/Cntr=0.3,0.1

Type RM Length L Ch R = 1 ,7474    ,499,499,499
BEGIN DESCRIPTION:
LAKE CREEK TRIBUTARY NO. 27 10.0
END DESCRIPTION:
XS GIS Cut Line= 3
      3724517.85     10177811.08      3724421.17     10177887.28
      3724167.86     10178211.06
#Sta/Elev= 30
  4876.9  284.87  4898.6  284.57  4927.4  282.35  4940.6  282.05  4969.1  278.95
  4977.1  277.58  4989.9 273.554    4998  271.97  4998.2  271.47  5005.6  271.97
  5012.3  273.57  5041.3  273.49  5047.6  272.65  5076.5  272.19  5082.9  272.37
  5105.5  275.49  5119.1   276.2  5140.7  276.63  5196.8   276.7  5204.9  277.29
    5261   278.8  5269.1  279.62  5289.9  280.41  5296.8  281.17  5310.8  281.21
  5354.1  283.21    5375  283.13  5397.5  284.62  5403.9  284.21  5411.1  284.67
#Mann= 3 , 0 , 0
  4876.9     .17       0  4989.9     .09       0  5012.3     .17       0
Bank Sta=4989.9,5012.3
XS Rating Curve= 0 ,0
Exp/Cntr=0.3,0.1

Type RM Length L Ch R = 1 ,6975    ,498,498,498
BEGIN DESCRIPTION:
LAKE CREEK TRIBUTARY NO. 27 9.0
END DESCRIPTION:
XS GIS Cut Line= 3
      3724367.85     10177511.07      3724081.89     10177720.58
      3723917.86     10178011.06
#Sta/Elev= 30
  4645.5  287.73    4659  286.45  4709.2  284.24  4732.3  282.64  4738.5  282.79
  4759.4  280.92  4874.4  275.81  4918.2  272.88  4930.8  271.05  4939.2  271.26
  4953.9  273.58  4960.1  272.12  4967.8  273.06  4980.9  272.76 4992.58271.5981
  4997.4  270.77  4997.7  270.27  5012.1   271.6  5046.5  271.59  5055.6  272.11
  5061.4  270.87  5069.5  270.81  5120.6  273.61  5142.3  273.66  5149.9  274.58
  5172.8  274.72  5230.3  277.48    5239  277.01  5260.7  278.51  5333.6  280.07
#Mann= 3 , 0 , 0
  4645.5     .17       0 4992.58     .09       0  5012.1     .17       0
Bank Sta=4992.58,5012.1
XS Rating Curve= 0 ,0
Exp/Cntr=0.3,0.1

Type RM Length L Ch R = 1 ,6477    ,490,490,490
BEGIN DESCRIPTION:
LAKE CREEK TRIBUTARY NO. 27 8.0
END DESCRIPTION:
XS GIS Cut Line= 3
      3724201.22     10177196.68       3723889.9     10177335.09
      3723267.82      10177911.1
#Sta/Elev= 30
  4659.3  285.66  4695.8  283.85  4709.6  283.75  4794.3  278.77  4802.6  279.05
  4854.6  275.39  4936.6  271.54  5005.5  269.48    5048  270.04  5055.4  269.42
  5062.2  269.95  5125.7  268.53  5131.1  268.17  5131.3  267.67  5168.2     270
  5182.4  269.51    5204  270.63  5232.3  270.91  5253.3  272.14    5289  272.69
    5310  274.19  5479.8  280.28  5550.4  281.71  5600.3  283.64  5607.1  283.39
  5628.6  285.11  5649.6   285.2  5791.3  291.79  5819.7  291.84  5847.8  293.54
#Mann= 3 , 0 , 0
  4659.3     .17       0  5062.2     .09       0  5168.2     .17       0
Bank Sta=5062.2,5168.2
XS Rating Curve= 0 ,0
Exp/Cntr=0.3,0.1

Type RM Length L Ch R = 1 ,5987    ,506,506,506
BEGIN DESCRIPTION:
LAKE CREEK TRIBUTARY NO. 27 7.0
END DESCRIPTION:
XS GIS Cut Line= 3
      3724173.47     10176828.61      3723576.24     10176995.28
      3723117.87     10177561.05
#Sta/Elev= 30
  4549.4  288.79  4613.3  283.13  4627.9  283.02  4647.5  280.85  4799.8  272.09
  4980.9  265.72  4999.9  264.44  5020.4  265.72  5032.8  264.98  5074.3  265.63
  5099.1  267.03  5157.4  268.18  5236.6  266.99  5265.4  267.35  5321.4  269.59
  5428.4  272.38  5442.8  273.42    5478  274.04  5506.8  276.05  5556.3  276.96
  5605.9  279.35    5649  280.24  5669.8  281.58  5677.8  281.21  5684.2  282.11
    5705  282.82  5756.1  283.53  5776.9  285.57  5861.7  287.76  5897.6   290.5
#Mann= 3 , 0 , 0
  4549.4     .17       0  4980.9     .09       0  5020.4     .17       0
Bank Sta=4980.9,5020.4
XS Rating Curve= 0 ,0
Exp/Cntr=0.3,0.1

Type RM Length L Ch R = 1 ,5481    ,499,499,499
BEGIN DESCRIPTION:
LAKE CREEK TRIBUTARY NO. 27 6.0
END DESCRIPTION:
XS GIS Cut Line= 3
      3723967.81     10176561.07      3723661.31     10176516.68
      3723067.88     10177111.05
#Sta/Elev= 30
  4690.3  274.29  4795.6  269.92  4872.1  265.73  4892.3  265.59    4953  263.08
  4993.4  263.15  4997.2  262.86  4997.5  262.36    5001  262.36  5001.2  262.86
 5036.68263.2169  5083.3  263.54    5154  264.98  5203.5  264.87  5231.8  265.66
    5253  265.28  5316.7   266.1  5330.8  266.02    5345  264.71  5366.2  264.23
  5394.5  267.08  5415.7  266.68  5479.3  269.43  5493.5  269.28    5543  270.78
  5578.3  272.53  5769.2  278.71  5790.4  279.95  5818.7  279.97  5839.9  281.07
#Mann= 3 , 0 , 0
  4690.3     .17       0  4993.4     .09       0 5036.68     .17       0
Bank Sta=4993.4,5036.68
XS Rating Curve= 0 ,0
Exp/Cntr=0.3,0.1

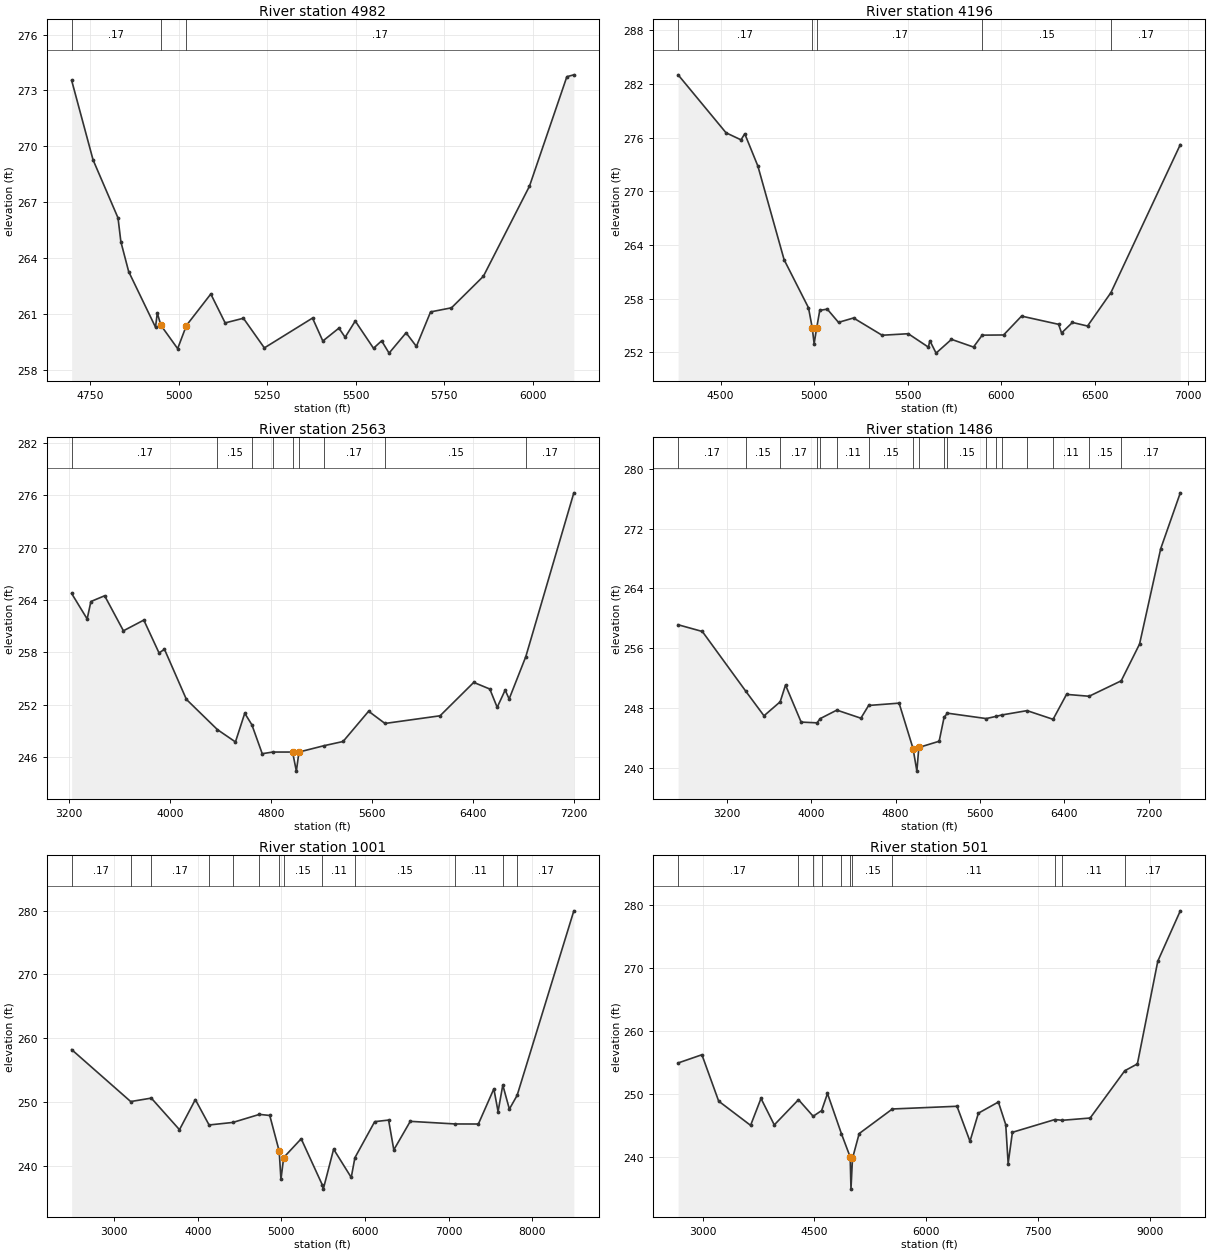
Type RM Length L Ch R = 1 ,4982    ,786,786,786
BEGIN DESCRIPTION:
LAKE CREEK TRIBUTARY NO. 27 5.0
END DESCRIPTION:
XS GIS Cut Line= 3
      3723917.89     10176111.08      3723618.08     10176079.24
      3722604.06     10176543.87
#Sta/Elev= 30
  4698.5  273.54  4758.9  269.28  4829.3  266.17  4837.4  264.89  4859.4  263.29
  4935.1  260.31  4940.1  261.07  4950.4  260.41  4997.6  259.16  5022.2   260.4
  5091.1  262.09  5131.6  260.54  5183.1  260.79  5242.2   259.2  5378.1   260.8
  5407.2  259.57  5452.6  260.26  5470.1  259.77  5498.6  260.64  5550.2  259.18
  5573.1  259.58  5594.1  258.92  5642.1  260.01  5671.2  259.28  5711.2  261.13
  5770.2  261.35  5860.2  263.04  5990.2  267.87  6095.7  273.74  6115.4  273.84
#Mann= 3 , 0 , 0
  4698.5     .17       0  4950.4     .09       0  5022.2     .17       0
Bank Sta=4950.4,5022.2
XS Rating Curve= 0 ,0
Exp/Cntr=0.3,0.1

Type RM Length L Ch R = 1 ,4196    ,1633,1633,1633
BEGIN DESCRIPTION:
Mapping XS 94b04ba0
END DESCRIPTION:
XS GIS Cut Line= 3
      3724583.19      10175424.1      3723255.06     10175328.61
      3722577.96     10176500.51
#Sta/Elev= 30
  4273.1  283.04  4529.3  276.56  4609.3  275.77  4629.4  276.45  4699.5  272.84
  4839.9  262.36  4970.2  256.99  4990.3  254.74  5000.3  252.97 5014.03  254.75
  5030.4   256.7  5070.5  256.84  5130.6  255.36  5210.9  255.85  5363.7  253.92
  5503.6  254.09  5611.2  252.59    5619  253.31  5652.3  251.92  5734.7  253.46
  5852.4   252.6  5898.9  253.93  6013.2  253.95  6109.3  256.06  6307.5  255.14
  6323.2  254.17  6381.3  255.35  6462.1  254.95  6587.2  258.69  6958.1  275.24
#Mann= 5 ,-1 , 0
  4273.1     .17       0  4990.3     .09       0 5014.03     .17       0
  5898.9     .15       0  6587.2     .17       0
Bank Sta=4990.3,5014.03
XS Rating Curve= 0 ,0
Exp/Cntr=0.3,0.1

Type RM Length L Ch R = 1 ,2563    ,1077,1077,1077
BEGIN DESCRIPTION:
LAKE CREEK TRIBUTARY NO. 27 4.0
END DESCRIPTION:
XS GIS Cut Line= 3
      3724886.98     10174590.76      3723255.06     10174243.54
      3722535.16     10176437.92
#Sta/Elev= 30
  3220.6  264.74  3343.4  261.82  3373.1  263.82  3481.9  264.48  3630.7  260.46
  3792.2  261.69  3912.8  257.92  3955.8  258.34  4129.6  252.59  4375.5  249.12
  4518.1  247.71  4591.7     251  4648.1  249.68  4730.2  246.36  4814.5  246.55
  4970.6  246.55  5000.5  244.36  5021.2  246.55  5217.4  247.27  5370.6  247.76
  5572.8  251.23  5702.5  249.83  6138.9  250.71  6405.6  254.54  6532.9  253.78
  6591.3  251.68  6654.5  253.66  6686.1  252.64  6817.8  257.49  7198.5  276.29
#Mann= 9 ,-1 , 0
  3220.6     .17       0  4375.5     .15       0  4648.1     .17       0
  4814.5     .15       0  4970.6     .09       0  5021.2     .15       0
  5217.4     .17       0  5702.5     .15       0  6817.8     .17       0
Bank Sta=4970.6,5021.2
XS Rating Curve= 0 ,0
Exp/Cntr=0.3,0.1

Type RM Length L Ch R = 1 ,1486    ,485,485,485
BEGIN DESCRIPTION:
LAKE CREEK TRIBUTARY NO. 27 3.0
END DESCRIPTION:
XS GIS Cut Line= 4
      3724583.17     10174365.07      3722363.88     10173922.44
      3722267.85     10174161.07      3722456.44      10176396.2
#Sta/Elev= 30
    2737  259.15  2966.8  258.25    3378  250.29  3551.5  246.99  3705.1  248.86
  3755.7   251.1  3903.8  246.15  4053.8  246.05  4085.6  246.62  4242.4  247.75
  4470.5  246.67  4544.1  248.37    4833  248.68  4965.4  242.62  5001.6   239.6
  5020.1  242.76  5212.9  243.59  5259.8  246.79  5291.8  247.34  5659.3  246.62
  5755.6  246.92  5807.3   247.1  6046.7  247.68  6293.5  246.52  6421.3  249.85
  6635.3   249.6  6939.6  251.66  7113.8  256.57  7314.5  269.31  7500.3  276.77
#Mann= 18 ,-1 , 0
    2737     .17       0    3378     .15       0  3705.1     .17       0
  4053.8     .15       0  4085.6     .17       0  4242.4     .11       0
  4544.1     .15       0  4965.4     .09       0  5020.1     .15       0
  5259.8     .17       0  5291.8     .15       0  5659.3     .11       0
  5755.6     .17       0  5807.3     .15       0  6046.7     .17       0
  6293.5     .11       0  6635.3     .15       0  6939.6     .17       0
Bank Sta=4965.4,5020.1
XS Rating Curve= 0 ,0
Exp/Cntr=0.3,0.1

Type RM Length L Ch R = 1 ,1001    ,500,500,500
BEGIN DESCRIPTION:
LAKE CREEK TRIBUTARY NO. 27 2.0
END DESCRIPTION:
XS GIS Cut Line= 4
      3724652.61     10174295.62      3722272.77     10173501.32
      3721640.47     10173783.47      3722404.35     10176483.09
#Sta/Elev= 30
  2491.1  258.21  3197.4  250.07    3444  250.61  3780.9  245.66  3970.5  250.38
    4135   246.4  4419.9   246.8  4737.3  248.06  4860.8  247.89  4973.6  242.31
  4994.6  237.86  5027.3   241.3  5236.7  244.24  5488.4  237.04    5501  236.35
  5624.6  242.61  5835.4  238.18  5879.2  241.27    6116  246.92  6282.3  247.17
  6344.6   242.5  6541.4  246.97  7078.1  246.56  7355.9  246.55  7541.3  252.06
  7591.7   248.5  7648.3  252.65  7726.9  248.89  7819.4  251.03    8498  279.95
#Mann= 13 ,-1 , 0
  2491.1     .17       0  3197.4     .15       0    3444     .17       0
    4135     .11       0  4419.9     .17       0  4737.3     .15       0
  4973.6     .09       0  5027.3     .15       0  5488.4     .11       0
  5879.2     .15       0  7078.1     .11       0  7648.3     .15       0
  7819.4     .17       0
Bank Sta=4973.6,5027.3
XS Rating Curve= 0 ,0
Exp/Cntr=0.3,0.1

Type RM Length L Ch R = 1 ,501     ,0,0,0
BEGIN DESCRIPTION:
LAKE CREEK TRIBUTARY NO. 27 1.0
END DESCRIPTION:
XS GIS Cut Line= 5
      3724557.14     10173783.47      3722338.94     10173073.03
      3721605.75     10173097.71      3721336.66     10174278.27
      3722352.18      10176526.3
#Sta/Elev= 30
  2670.8  254.93  2990.2  256.23  3215.2  248.89  3643.6  245.06  3783.1  249.32
  3961.6  245.13  4286.5  249.12  4483.5   246.5  4597.1   247.4  4675.6   250.1
  4863.3  243.72  4980.1  240.06    4991  234.97  5011.1  239.83  5101.1  243.76
  5546.6  247.65    6414  248.08  6588.3  242.54  6701.2  246.99  6969.5  248.75
  7068.2  245.17  7100.4  239.02  7157.7  243.96  7728.2  245.98  7826.2  245.86
  8201.1  246.22  8665.8   253.7  8835.1  254.78  9109.2  271.04  9411.2     279
#Mann= 11 ,-1 , 0
  2670.8     .17       0  4286.5     .11       0  4483.5     .17       0
  4597.1     .11       0  4863.3     .15       0  4980.1     .09       0
  5011.1     .15       0  5546.6     .11       0  7728.2     .15       0
  7826.2     .11       0  8665.8     .17       0
Bank Sta=4980.1,5011.1
XS Rating Curve= 0 ,0
Exp/Cntr=0.3,0.1

Chan Stop Cuts=-1
Use User Specified Reach Order=0
Composite Channel Slope=5