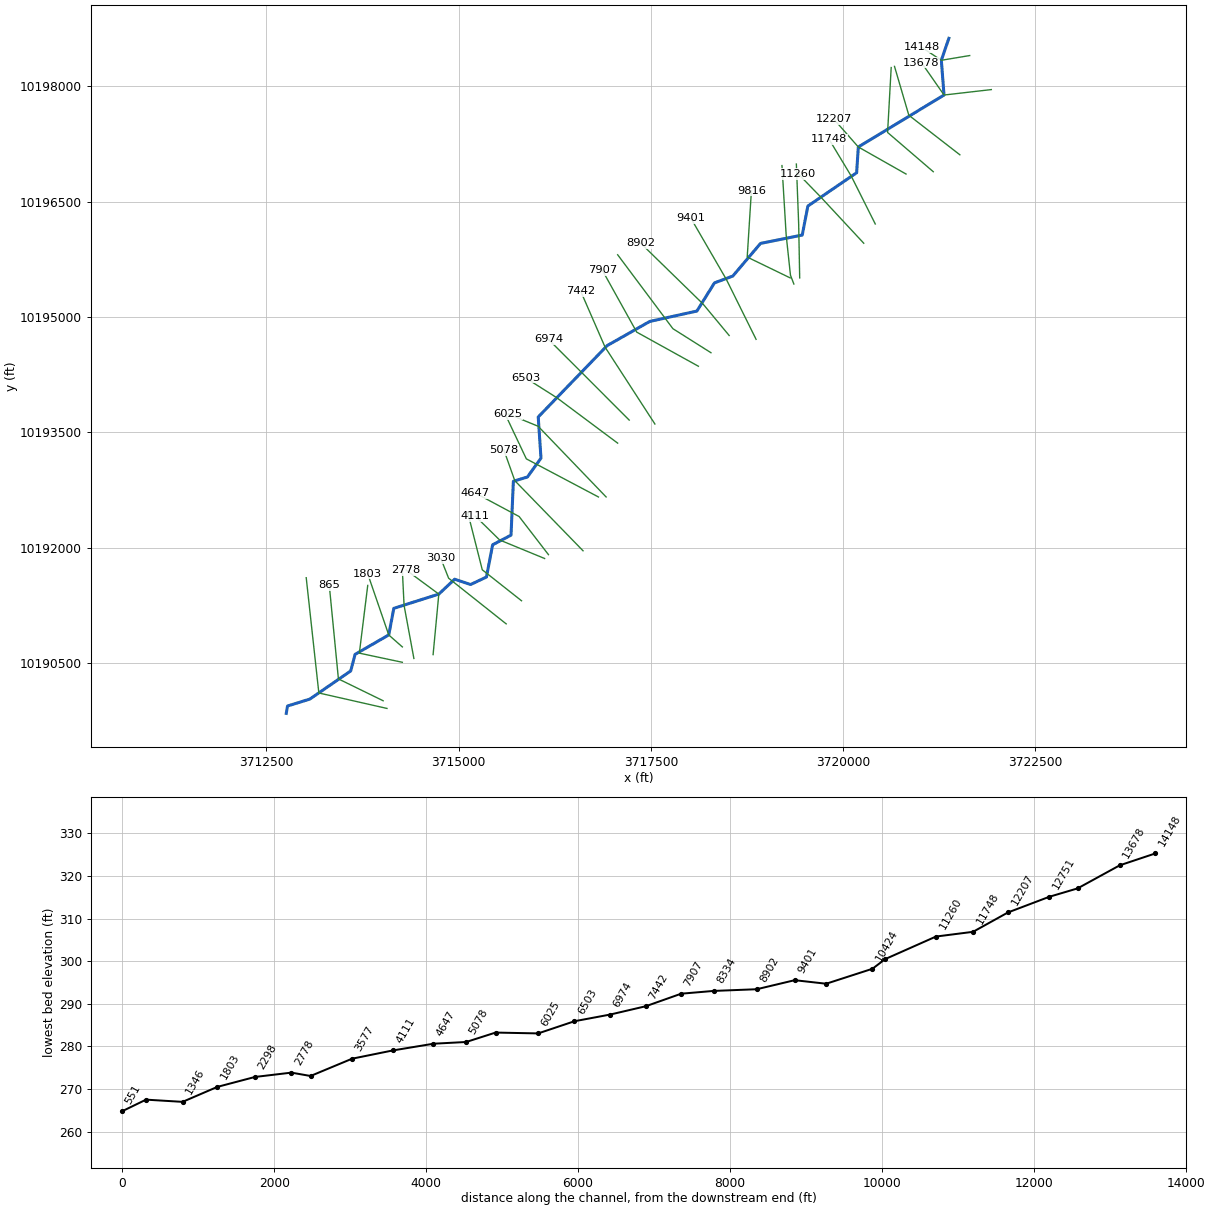
--- LAKE CREEK TRIBUTARY NO 28.prj (project) ---

Proj Title=LAKE CREEK TRIBUTARY NO 28 Base Level Engineering
Current Plan=p01
Default Exp/Contr=0.3,0.1
English Units
Geom File=g01
Flow File=f01
Plan File=p01
Y Axis Title=Elevation
X Axis Title(PF)=Main Channel Distance
X Axis Title(XS)=Station
BEGIN DESCRIPTION:
LAKE CREEK TRIBUTARY NO 28
END DESCRIPTION:
DSS Export Rating Curves= 0
DSS Export Rating Curve Sorted= 0
DSS Export Volume Flow Curves= 0
DXF OffsetX= 0
DXF OffsetY= 0
DXF ScaleX= 1
DXF ScaleY= 10

--- LAKE CREEK TRIBUTARY NO 28.p01 (plan) ---

Plan Title=Multiple Run
Short Identifier=Multiple
Geom File=g01
Flow File=f01
Subcritical Flow
K Sum by GR= 0
Std Step Tol= 0.01
Critical Tol= 0.01
Num of Std Step Trials= 20
Max Error Tol= 0.3
Flow Tol Ratio= 0.001
Split Flow NTrial= 30
Split Flow Tol= 0.02
Split Flow Ratio= 0.02
Log Output Level= 0
Friction Slope Method= 1
Unsteady Friction Slope Method= 2
Unsteady Bridges Friction Slope Method= 1
Parabolic Critical Depth
Global Vel Dist=  1 , 1 , 1
Global Log Level= 0
CheckData=True
Encroach Param= -1, 0, 0, 0
BEGIN DESCRIPTION:
Multiple Run
END DESCRIPTION:

--- LAKE CREEK TRIBUTARY NO 28.f01 (steady flow) ---

Flow Title=Multiple
Program Version=4.10
Number of Profiles= 7
Profile Names=10-year,25-year,50-year,1pct_min,100-year,1pct_plu,500-year
River Rch & RM=LAKE CREEK TRIBU,Reach-1         ,14148
     846    1178    1624     736    2223    6713    4310
River Rch & RM=LAKE CREEK TRIBU,Reach-1         ,11748
    1118    1579    2194    1003    3028    9144    5963
River Rch & RM=LAKE CREEK TRIBU,Reach-1         ,8902
    1463    2085    2914    1337    4038   12195    8026
River Rch & RM=LAKE CREEK TRIBU,Reach-1         ,6503
    1491    2111    2938    1340    4048   12225    7958
Boundary for River Rch & Prof#=LAKE CREEK TRIBU,Reach-1         , 1
Up Type= 0
Dn Type= 3
Dn Slope=0.005
Boundary for River Rch & Prof#=LAKE CREEK TRIBU,Reach-1         , 2
Up Type= 0
Dn Type= 3
Dn Slope=0.005
Boundary for River Rch & Prof#=LAKE CREEK TRIBU,Reach-1         , 3
Up Type= 0
Dn Type= 3
Dn Slope=0.005
Boundary for River Rch & Prof#=LAKE CREEK TRIBU,Reach-1         , 4
Up Type= 0
Dn Type= 3
Dn Slope=0.005
Boundary for River Rch & Prof#=LAKE CREEK TRIBU,Reach-1         , 5
Up Type= 0
Dn Type= 3
Dn Slope=0.005
Boundary for River Rch & Prof#=LAKE CREEK TRIBU,Reach-1         , 6
Up Type= 0
Dn Type= 3
Dn Slope=0.005
Boundary for River Rch & Prof#=LAKE CREEK TRIBU,Reach-1         , 7
Up Type= 0
Dn Type= 3
Dn Slope=0.005
DSS Import GetInterval= 0
DSS Import GetPeak= 0
DSS Import FillOption= 0

--- LAKE CREEK TRIBUTARY NO 28.g01 (geometry) ---

Geom Title=Existing Conditions
Program Version=4.10

River Reach=LAKE CREEK TRIBU,Reach-1
Reach XY= 30
      3721374.78     10198625.56       3721276.9     10198340.19
      3721312.06     10197888.37      3720197.48     10197212.59
      3720175.43     10196877.85      3719541.31     10196444.26
      3719468.19     10196067.38       3718925.6      10195958.6
      3718565.29     10195534.13      3718326.88     10195445.51
      3718098.27     10195078.94       3717485.5      10194943.9
      3716931.76     10194629.94      3716034.91      10193701.3
      3716070.68     10193166.11      3715894.49     10192921.03
      3715711.67     10192865.39      3715681.21     10192164.61
      3715441.92      10192039.2      3715361.54     10191619.86
      3715155.11     10191522.31      3714948.18     10191591.85
      3714742.15     10191397.93      3714157.09     10191212.83
      3714090.98     10190866.86      3713653.56     10190614.55
      3713596.27      10190398.6       3713065.2      10190032.8
      3712774.92     10189942.85      3712758.23     10189846.84

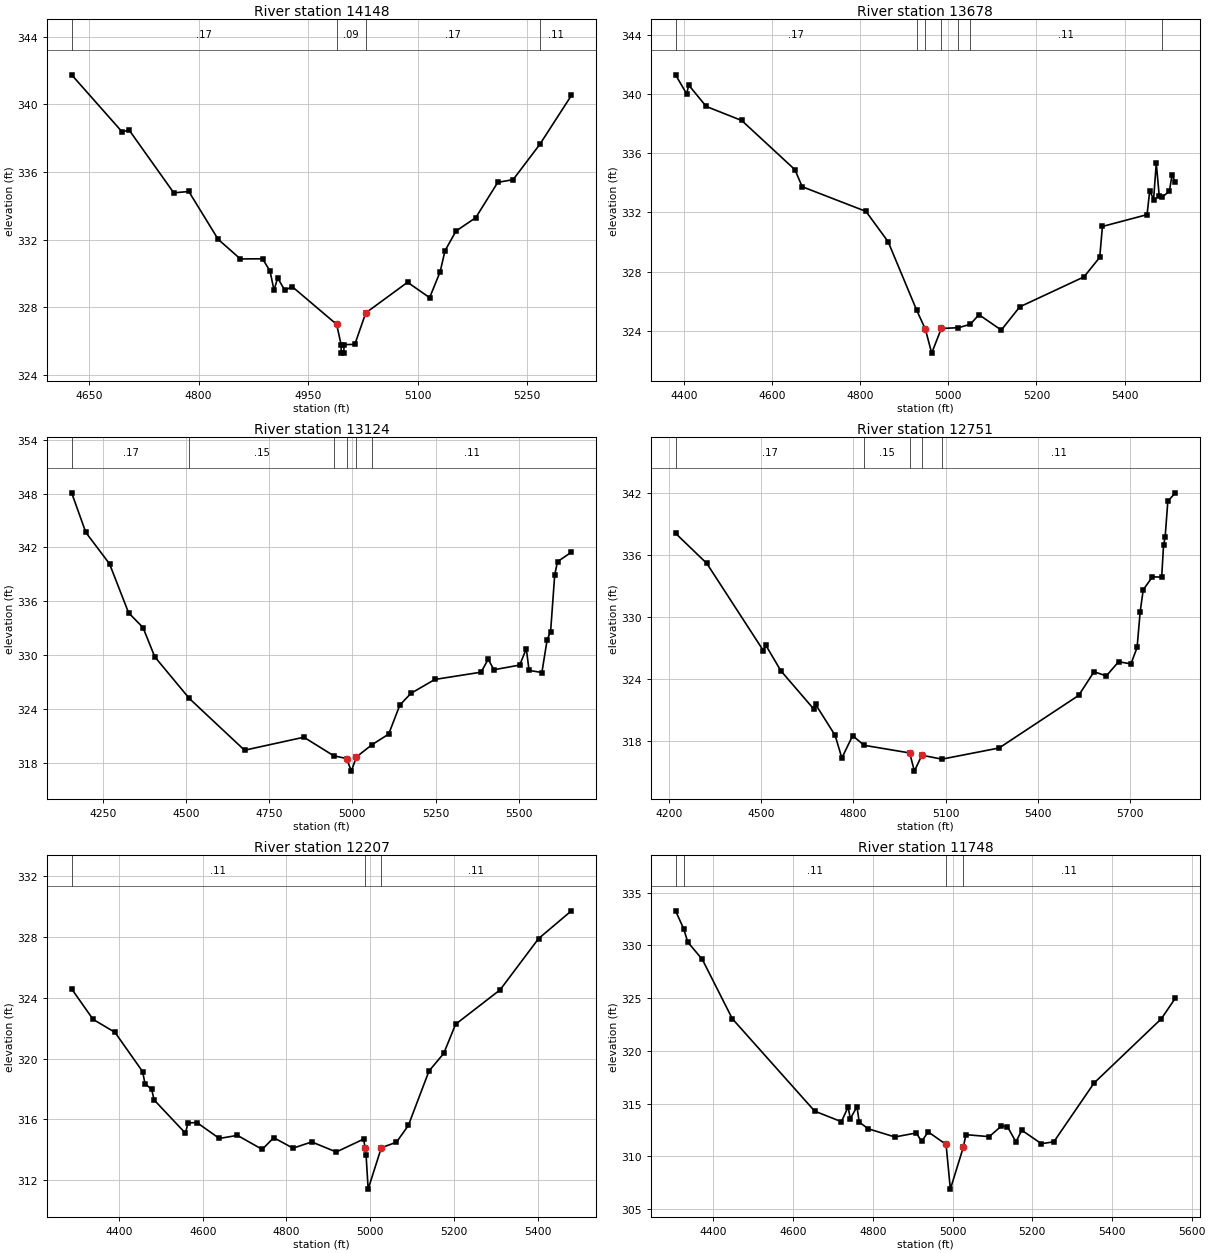
Type RM Length L Ch R = 1 ,14148   ,470,470,470
BEGIN DESCRIPTION:
LAKE CREEK TRIBUTARY NO. 28 30.0
END DESCRIPTION:
XS GIS Cut Line= 3
      3721645.71     10198401.69       3721276.9     10198340.19
      3721017.88     10198511.05
#Sta/Elev= 30
  4626.1  341.74  4694.9  338.38    4705  338.46  4765.9  334.76  4786.5  334.84
  4826.7  332.01  4857.1  330.85  4887.5  330.86  4897.7  330.13  4903.1  329.01
  4908.2  329.72  4917.9     329  4928.1  329.21  4988.9  326.98    4995  325.78
  4995.2  325.28  4998.7  325.28    4999  325.78  5013.8   325.8  5028.8  327.66
    5086  329.47  5116.2  328.56  5130.6  330.09  5137.2  331.33  5152.3   332.5
  5179.3  333.29  5209.5  335.38  5230.5  335.54  5267.1  337.63  5310.3  340.52
#Mann= 4 ,-1 , 0
  4626.1     .17       0  4988.9     .09       0  5028.8     .17       0
  5267.1     .11       0
Bank Sta=4988.9,5028.8
XS Rating Curve= 0 ,0
Exp/Cntr=0.3,0.1

Type RM Length L Ch R = 1 ,13678   ,554,554,554
BEGIN DESCRIPTION:
LAKE CREEK TRIBUTARY NO. 28 29.0
END DESCRIPTION:
XS GIS Cut Line= 3
      3721927.02     10197958.99      3721312.06     10197888.37
      3721017.86     10198311.06
#Sta/Elev= 30
    4381  341.31    4406  340.03    4411  340.61  4450.6  339.17  4531.1  338.22
  4651.9  334.89  4668.3  333.74    4813  332.07  4863.3  330.02  4927.9   325.4
 4947.93  324.09  4962.2  322.48  4984.1  324.15  5022.9   324.2  5049.7  324.43
  5069.5  325.08  5120.1  324.04    5162  325.61  5307.8  327.64  5343.5  328.96
  5349.6  331.05  5450.9  331.85    5457  333.48  5465.7  332.87  5471.8  335.33
  5478.5  333.12  5484.2  333.02  5501.5  333.43  5507.6  334.54    5515  334.03
#Mann= 7 ,-1 , 0
    4381     .17       0  4927.9     .11       0 4947.93     .07       0
  4984.1     .11       0  5022.9     .15       0  5049.7     .11       0
  5484.2     .17       0
Bank Sta=4947.93,4984.1
XS Rating Curve= 0 ,0
Exp/Cntr=0.3,0.1

Type RM Length L Ch R = 1 ,13124   ,373,373,373
BEGIN DESCRIPTION:
LAKE CREEK TRIBUTARY NO. 28 28.0
END DESCRIPTION:
XS GIS Cut Line= 3
      3721517.84     10197111.08      3720854.07     10197625.65
      3720667.85     10198261.07
#Sta/Elev= 30
  4156.2  348.09  4198.7  343.68  4270.1  340.17  4327.3  334.72  4370.7  333.07
    4406  329.81  4509.8  325.17  4675.8   319.4  4854.1  320.85  4943.9  318.78
  4982.7  318.47  4996.7  317.07  5012.1  318.65  5057.9  319.99  5109.1   321.2
  5142.5  324.43  5175.9  325.74  5247.9  327.29  5386.8   328.1  5408.1  329.54
  5425.4  328.37  5502.7  328.89  5522.7  330.71  5530.9   328.3  5569.5  328.06
  5585.3  331.72  5595.7  332.63  5608.1  338.97  5616.5  340.42  5658.2  341.47
#Mann= 6 ,-1 , 0
  4156.2     .17       0  4509.8     .15       0  4943.9     .17       0
  4982.7     .09       0  5012.1     .17       0  5057.9     .11       0
Bank Sta=4982.7,5012.1
XS Rating Curve= 0 ,0
Exp/Cntr=0.3,0.1

Type RM Length L Ch R = 1 ,12751   ,544,544,544
BEGIN DESCRIPTION:
LAKE CREEK TRIBUTARY NO. 28 27.0
END DESCRIPTION:
XS GIS Cut Line= 3
      3721171.76     10196891.29      3720578.03      10197401.7
       3720624.9     10198245.43
#Sta/Elev= 30
  4220.5  338.12  4322.2  335.21  4506.6  326.76  4514.2   327.3  4563.6  324.81
  4670.1  321.13  4676.7  321.56  4740.3  318.56  4762.2  316.37  4797.4  318.53
  4834.8   317.6  4983.2  316.86  4998.5   315.1  5022.9  316.64  5088.2  316.26
  5274.5  317.34  5533.7  322.43  5583.7  324.72  5623.8  324.32  5663.9  325.69
  5703.9  325.48    5724  327.07    5734  330.51    5744  332.66    5774  333.91
  5804.1  333.88  5810.3  337.02  5815.3  337.72  5824.1  341.22  5848.5  342.04
#Mann= 5 ,-1 , 0
  4220.5     .17       0  4834.8     .15       0  4983.2     .09       0
  5022.9     .17       0  5088.2     .11       0
Bank Sta=4983.2,5022.9
XS Rating Curve= 0 ,0
Exp/Cntr=0.3,0.1

Type RM Length L Ch R = 1 ,12207   ,459,459,459
BEGIN DESCRIPTION:
LAKE CREEK TRIBUTARY NO. 28 26.0
END DESCRIPTION:
XS GIS Cut Line= 3
      3720817.82     10196861.09      3720197.48     10197212.59
      3719880.08      10197573.6
#Sta/Elev= 30
    4287  324.57  4338.2  322.57  4390.4  321.72  4456.5  319.14  4462.2  318.34
  4478.1  317.98  4483.9  317.28  4558.9  315.09  4564.7  315.77  4586.3  315.79
  4639.7  314.75    4683  314.95  4742.2  314.03  4769.7   314.8  4815.7  314.11
  4860.5  314.52  4919.1  313.86  4984.6  314.71  4987.9314.0963  4990.3  313.65
  4995.2  311.42  5026.7  314.14  5062.7   314.5  5091.2   315.6  5140.6  319.18
  5175.7  320.33  5204.1  322.25  5310.4  324.51  5402.4  327.88  5480.7   329.7
#Mann= 3 , 0 , 0
    4287     .11       0  4987.9     .06       0  5026.7     .11       0
Bank Sta=4987.9,5026.7
XS Rating Curve= 0 ,0
Exp/Cntr=0.3,0.1

Type RM Length L Ch R = 1 ,11748   ,488,488,488
BEGIN DESCRIPTION:
LAKE CREEK TRIBUTARY NO. 28 25.0
END DESCRIPTION:
XS GIS Cut Line= 3
      3720417.85     10196211.07      3720106.42     10196832.28
      3719817.87     10197311.05
#Sta/Elev= 30
  4305.1  333.29  4325.3   331.6  4335.8  330.32  4372.2  328.68  4447.5  323.05
  4654.2  314.28  4721.2  313.28    4738  314.67  4743.6  313.57  4760.3   314.7
  4765.9  313.24  4788.3  312.61  4855.3  311.83  4909.2  312.21  4922.3  311.41
  4939.1  312.31  4983.8  311.12  4994.6  306.88    5027  310.84  5033.6  312.05
    5092  311.86  5122.2  312.85  5137.7  312.82  5159.1  311.36  5173.7  312.47
  5223.1  311.19  5254.2  311.37  5355.2  316.95    5524  323.05    5559     325
#Mann= 4 ,-1 , 0
  4305.1     .17       0  4325.3     .11       0  4983.8     .06       0
    5027     .11       0
Bank Sta=4983.8,5027
XS Rating Curve= 0 ,0
Exp/Cntr=0.3,0.1

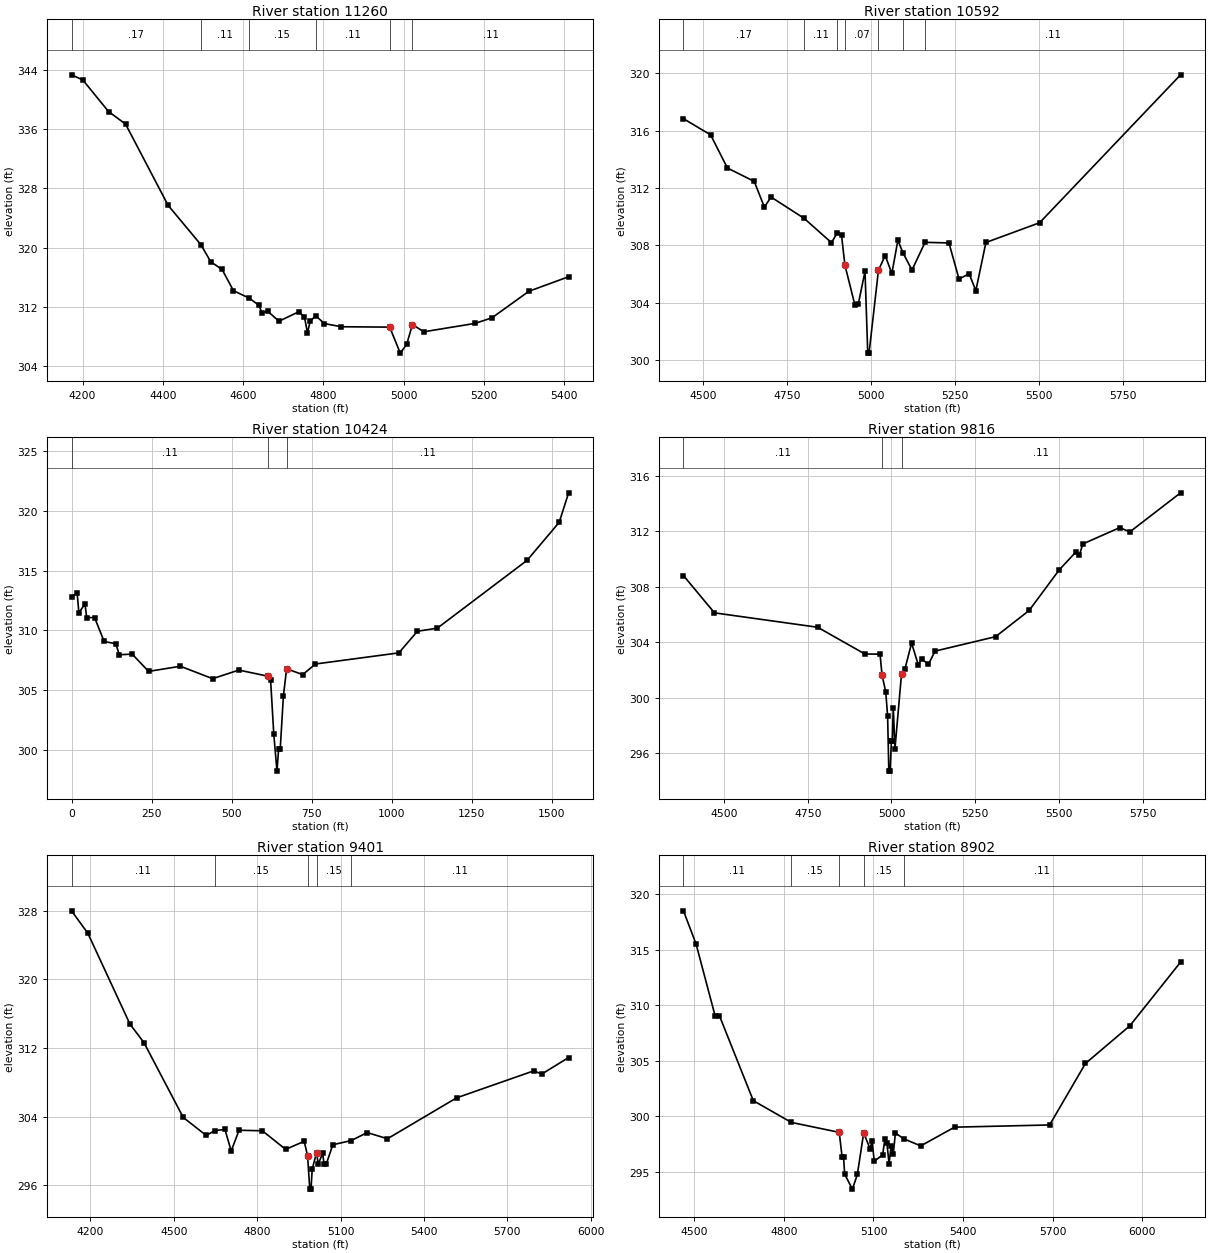
Type RM Length L Ch R = 1 ,11260   ,668,668,668
BEGIN DESCRIPTION:
LAKE CREEK TRIBUTARY NO. 28 24.0
END DESCRIPTION:
XS GIS Cut Line= 3
      3720267.86     10195961.06      3719704.08     10196566.65
      3719417.86     10196861.06
#Sta/Elev= 30
  4172.6  343.33  4200.7  342.64  4264.7  338.38  4307.2  336.68  4413.2  325.71
    4495  320.39  4519.3   318.1  4547.6  317.06  4575.9  314.19  4614.2  313.22
  4639.4  312.23  4646.8   311.2  4660.9  311.43  4689.3  310.08  4738.6  311.35
  4752.8  310.65  4760.1   308.5    4767  310.06  4780.7  310.82  4802.1  309.76
  4844.6  309.33    4965  309.28  4991.3  305.77  5007.4  306.96  5021.6  309.63
  5049.9  308.65  5177.2  309.78  5219.6  310.53  5311.7  314.12  5410.6  316.08
#Mann= 6 ,-1 , 0
  4172.6     .17       0    4495     .11       0  4614.2     .15       0
  4780.7     .11       0    4965     .06       0  5021.6     .11       0
Bank Sta=4965,5021.6
XS Rating Curve= 0 ,0
Exp/Cntr=0.3,0.1

Type RM Length L Ch R = 1 ,10592   ,168,168,168
BEGIN DESCRIPTION:
LAKE CREEK TRIBUTARY NO. 28 23.0
END DESCRIPTION:
XS GIS Cut Line= 3
      3719434.94     10195510.15      3719421.78     10196208.99
      3719391.73     10196990.65
#Sta/Elev= 30
    4441  316.84  4521.9  315.71  4571.9   313.4    4652  312.46    4682  310.67
    4702  311.37  4800.2  309.89    4882  308.19  4898.4  308.83    4912   308.7
    4922  306.63    4952  303.82    4962  303.91    4982  306.19  4990.1  300.48
    4994  300.48    5022  306.26    5042  307.29    5062  306.04  5079.9  308.36
  5094.9  307.48    5122  306.28  5160.8  308.21  5232.1  308.17  5262.1  305.65
  5292.2  306.02  5312.2  304.84  5342.2   308.2  5502.3  309.58  5922.2   319.9
#Mann= 7 ,-1 , 0
    4441     .17       0  4800.2     .11       0  4898.4     .17       0
    4922     .07       0    5022     .17       0  5094.9     .15       0
  5160.8     .11       0
Bank Sta=4922,5022
XS Rating Curve= 0 ,0
Exp/Cntr=0.3,0.1

Type RM Length L Ch R = 1 ,10424   ,608,608,608
BEGIN DESCRIPTION:
LAKE CREEK TRIBUTARY NO. 28 22.0
END DESCRIPTION:
XS GIS Cut Line= 4
      3719359.38     10195430.29      3719314.96     10195545.02
      3719259.23      10196066.1       3719204.5     10196970.54
#Sta/Elev= 30
       0  312.81    17.5  313.15    22.9  311.48    42.1   312.2    47.4  311.06
      72  311.07   101.9  309.07   138.5  308.87   149.2  307.95   189.5  308.01
   240.8  306.56   340.3  306.99   440.9  305.95   522.7  306.67     615  306.15
   621.9  305.88     632  301.29     642  298.21   647.1  300.07   652.1  300.07
   662.1  304.53   672.1  306.78   722.2  306.29   762.3  307.18  1022.7  308.11
  1080.8  309.92    1143  310.18  1423.5  315.86  1523.7  319.04  1553.2  321.51
#Mann= 3 ,-1 , 0
       0     .11       0     615     .07       0   672.1     .11       0
Bank Sta=615,672.1
XS Rating Curve= 0 ,0
Exp/Cntr=0.3,0.1

Type RM Length L Ch R = 1 ,9816    ,415,415,415
BEGIN DESCRIPTION:
LAKE CREEK TRIBUTARY NO. 28 21.0
END DESCRIPTION:
XS GIS Cut Line= 3
      3719311.06      10195510.2      3718752.49      10195781.1
      3718807.01     10196642.18
#Sta/Elev= 30
  4379.2  308.81  4471.7  306.12  4779.8  305.08  4920.8  303.15  4965.9  303.14
  4971.8  301.64  4982.9  300.42  4988.5  298.69  4992.1   294.7    4996   294.7
  4999.8  296.87  5002.5  296.87  5005.4  299.29  5010.4  296.31    5030  301.71
    5040  302.06  5060.1  303.94  5080.1  302.36  5090.1  302.79  5110.2  302.41
  5130.2  303.36  5310.6   304.4  5410.8  306.29    5501  309.23  5551.1  310.53
  5561.1  310.31  5571.1  311.09  5681.3  312.27  5711.4  311.96  5862.8  314.78
#Mann= 3 , 0 , 0
  4379.2     .11       0  4971.8     .06       0    5030     .11       0
Bank Sta=4971.8,5030
XS Rating Curve= 0 ,0
Exp/Cntr=0.3,0.1

Type RM Length L Ch R = 1 ,9401    ,499,499,499
BEGIN DESCRIPTION:
LAKE CREEK TRIBUTARY NO. 28 20.0
END DESCRIPTION:
XS GIS Cut Line= 3
      3718867.86     10194711.06      3718482.44     10195488.47
      3718020.68       10196285.
#Sta/Elev= 30
  4132.3  328.01  4191.1  325.39  4342.5  314.79  4392.9  312.63  4534.1   303.9
  4617.1  301.79  4647.9  302.37  4684.3  302.49  4706.8  299.98    4735   302.4
  4818.9  302.34  4902.5  300.17  4969.4  301.11  4981.4  299.45  4989.5  295.53
  4993.9  295.53  4998.2  297.86    5014   299.8  5019.7  298.44  5035.5  299.69
  5041.3  298.43  5049.2  298.49  5072.4  300.71  5138.7   301.2  5196.1  302.13
  5268.9  301.41  5517.5  306.18  5795.8  309.34  5823.7  308.95  5920.7  310.89
#Mann= 5 ,-1 , 0
  4132.3     .11       0  4647.9     .15       0  4981.4     .09       0
    5014     .15       0  5138.7     .11       0
Bank Sta=4981.4,5014
XS Rating Curve= 0 ,0
Exp/Cntr=0.3,0.1

Type RM Length L Ch R = 1 ,8902    ,568,568,568
BEGIN DESCRIPTION:
LAKE CREEK TRIBUTARY NO. 28 19.0
END DESCRIPTION:
XS GIS Cut Line= 3
      3718517.86     10194761.06      3718175.54     10195173.51
      3717367.85     10195961.07
#Sta/Elev= 30
    4464  318.52  4506.3  315.52  4570.1  309.03  4584.5  309.05  4697.9  301.39
  4825.2  299.43  4985.5 298.532  4995.2  296.28    5000  296.28  5003.7  294.76
  5029.5  293.41  5046.1  294.73  5067.3  298.48  5088.6  297.06  5095.6  297.73
  5102.7  295.93    5131   296.5    5138  297.91  5145.2  297.54  5152.2  295.72
  5159.3  297.31  5166.3  296.55  5173.5  298.48  5200.8  297.96  5258.3  297.31
  5371.5     299  5689.7   299.2  5809.8  304.75  5958.4  308.15  6128.1  313.89
#Mann= 5 ,-1 , 0
    4464     .11       0  4825.2     .15       0  4985.5     .09       0
  5067.3     .15       0  5200.8     .11       0
Bank Sta=4985.5,5067.3
XS Rating Curve= 0 ,0
Exp/Cntr=0.3,0.1

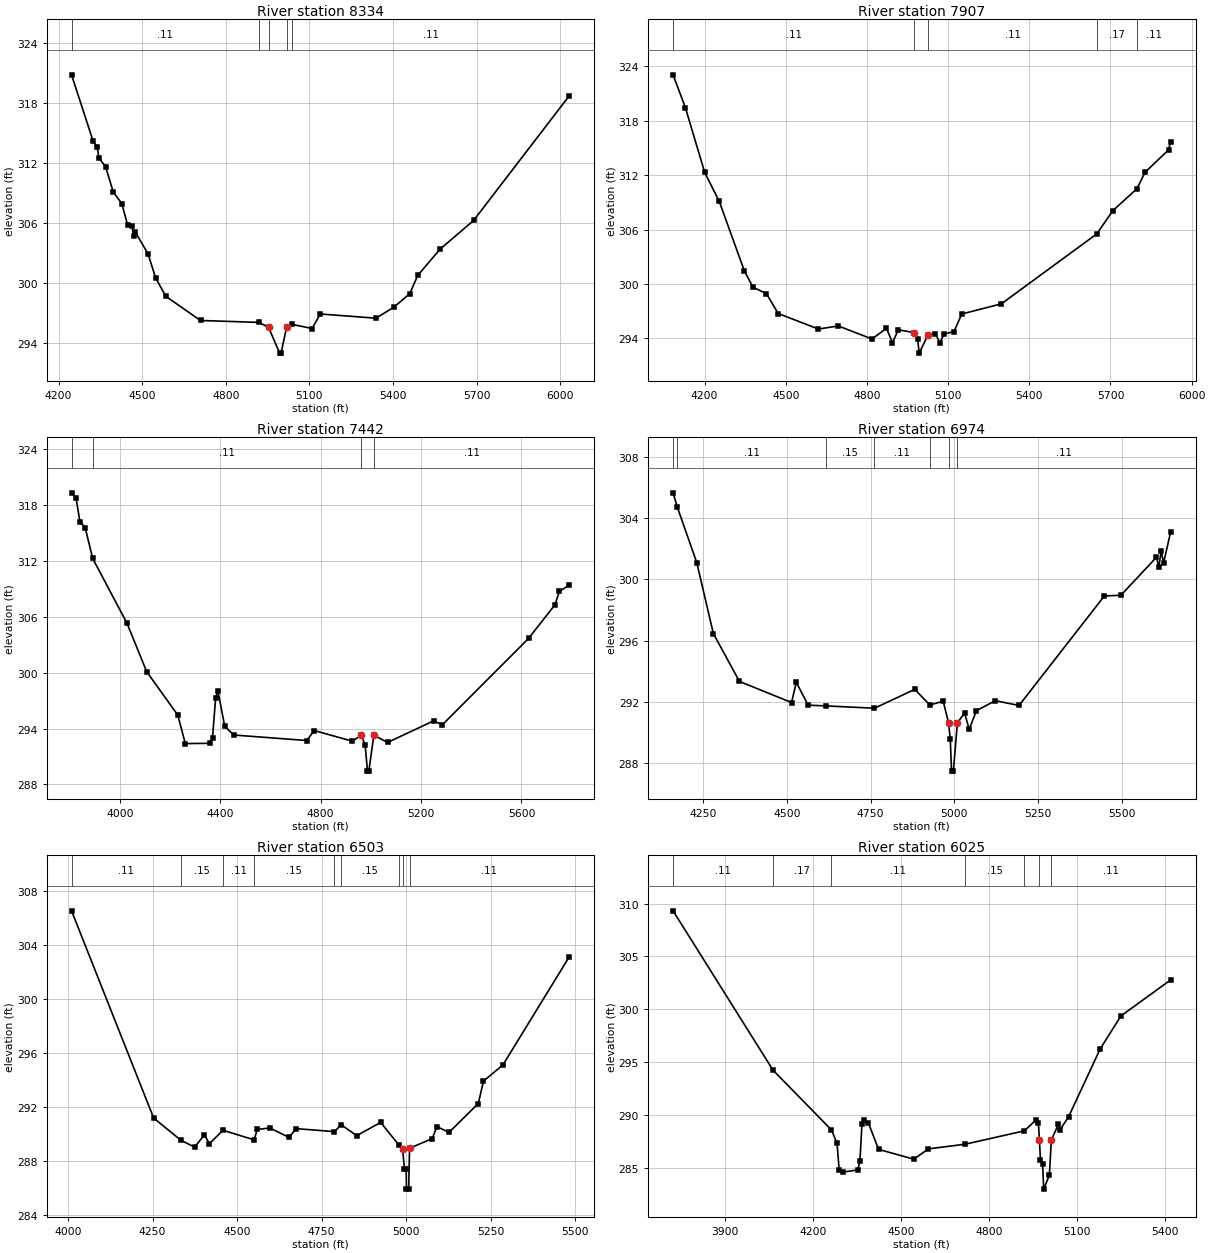
Type RM Length L Ch R = 1 ,8334    ,427,427,427
BEGIN DESCRIPTION:
LAKE CREEK TRIBUTARY NO. 28 18.0
END DESCRIPTION:
XS GIS Cut Line= 3
      3718281.12     10194537.13      3717786.36     10194849.61
      3717067.88     10195811.04
#Sta/Elev= 30
  4246.6  320.81  4323.4  314.24  4338.7  313.57  4345.1   312.5  4368.7  311.63
  4396.4   309.1  4426.9  307.95  4448.1  305.77  4463.4  305.72  4469.3  304.73
  4475.2  305.12    4521  302.92  4548.1  300.54  4584.6  298.69  4709.3  296.27
  4918.8  296.08  4953.4  295.59  4993.3  293.01  4998.4  293.01    5018  295.58
    5038  295.88  5109.7  295.47  5138.9  296.92    5339   296.5  5403.6  297.61
  5459.9  298.94  5489.1  300.78  5568.3  303.38  5689.2  306.26    6032   318.7
#Mann= 5 ,-1 , 0
  4246.6     .11       0  4918.8     .15       0  4953.4     .09       0
    5018     .15       0    5038     .11       0
Bank Sta=4953.4,5018
XS Rating Curve= 0 ,0
Exp/Cntr=0.3,0.1

Type RM Length L Ch R = 1 ,7907    ,465,465,465
BEGIN DESCRIPTION:
LAKE CREEK TRIBUTARY NO. 28 17.0
END DESCRIPTION:
XS GIS Cut Line= 3
      3718117.85     10194361.07      3717315.93     10194804.81
      3716867.86     10195611.06
#Sta/Elev= 30
  4083.5  323.08  4129.2  319.44  4200.3  312.31  4254.1  309.11  4346.9  301.44
    4379  299.63  4428.2  298.94  4472.1  296.73  4620.7  295.02  4693.9  295.36
  4818.7  293.92  4872.1   295.1  4894.3  293.52    4916  294.93  4974.9  294.63
    4987  293.93  4993.3  292.36  5025.6  294.38  5053.1  294.51  5069.1   293.5
  5085.1  294.48  5121.6  294.73  5150.3  296.68  5296.7   297.8  5649.7  305.53
  5708.5  308.08  5797.9  310.51  5827.5  312.31  5914.4  314.79  5922.4  315.71
#Mann= 5 ,-1 , 0
  4083.5     .11       0  4974.9     .06       0  5025.6     .11       0
  5649.7     .17       0  5797.9     .11       0
Bank Sta=4974.9,5025.6
XS Rating Curve= 0 ,0
Exp/Cntr=0.3,0.1

Type RM Length L Ch R = 1 ,7442    ,468,468,468
BEGIN DESCRIPTION:
LAKE CREEK TRIBUTARY NO. 28 16.0
END DESCRIPTION:
XS GIS Cut Line= 3
      3717552.01     10193609.99      3716903.94     10194610.07
      3716588.43     10195334.01
#Sta/Elev= 30
  3808.3  319.33  3826.3  318.78  3841.5  316.24  3862.6   315.6  3892.4  312.28
  4028.7  305.34  4107.5  300.11  4231.1  295.45  4261.4  292.38    4361  292.41
  4369.6  293.01  4382.2  297.31  4391.3  298.02  4418.4  294.22  4454.7   293.3
  4744.8  292.71  4774.8  293.78  4926.1  292.64  4962.4  293.28  4977.4  292.23
  4986.7  289.42  4992.1  289.42    5012  293.28  5066.5   292.5  5249.8  294.82
  5284.7   294.4  5628.4  303.69    5733  307.29    5751  308.74  5789.7  309.41
#Mann= 4 ,-1 , 0
  3808.3     .17       0  3892.4     .11       0  4962.4     .06       0
    5012     .11       0
#Block Obstruct= 2 , 0
         4389.49  297.89
Bank Sta=4962.4,5012
XS Rating Curve= 0 ,0
Exp/Cntr=0.3,0.1

Type RM Length L Ch R = 1 ,6974    ,471,471,471
BEGIN DESCRIPTION:
LAKE CREEK TRIBUTARY NO. 28 15.0
END DESCRIPTION:
XS GIS Cut Line= 3
      3717217.84     10193661.09      3716624.42     10194255.04
      3716167.85     10194711.07
#Sta/Elev= 30
  4160.4  305.65  4173.3   304.7  4231.1  301.09  4280.6  296.46  4358.4  293.33
  4513.9  291.95  4528.1  293.27  4563.4  291.78  4616.1  291.73  4761.4  291.58
  4881.6  292.81  4926.8  291.79  4966.5  292.04  4982.6290.6031  4987.7  289.54
  4991.3  287.47  4996.8  287.47  5008.9  290.62  5030.1  291.27  5044.3   290.2
  5065.5  291.42    5122  292.07  5192.8  291.76  5447.3  298.91  5496.8  298.96
  5602.9  301.44  5609.9  300.81    5617  301.85  5624.1  301.07  5645.3   303.1
#Mann= 7 ,-1 , 0
  4160.4     .17       0  4173.3     .11       0  4616.1     .15       0
  4761.4     .11       0  4926.8     .15       0  4982.6     .06       0
  5008.9     .11       0
Bank Sta=4982.6,5008.9
XS Rating Curve= 0 ,0
Exp/Cntr=0.3,0.1

Type RM Length L Ch R = 1 ,6503    ,478,478,478
BEGIN DESCRIPTION:
LAKE CREEK TRIBUTARY NO. 28 14.0
END DESCRIPTION:
XS GIS Cut Line= 3
      3717067.86     10193361.07      3716274.69       10193953.
      3715867.84     10194211.08
#Sta/Elev= 30
  4010.3  306.51  4253.2  291.16  4333.8  289.52  4374.1  289.01  4403.3  289.92
  4417.9  289.26    4458  290.26  4550.2  289.55  4559.6  290.32  4596.8  290.43
  4653.5  289.73  4674.3  290.38  4787.6  290.16    4808  290.66  4853.6  289.86
  4924.5  290.84  4977.7  289.19  4989.1  288.89  4994.9  287.39    5000  287.39
  5000.7   285.9  5007.2   285.9  5009.9  288.93  5076.8  289.64    5091  290.53
  5126.5   290.1  5213.2  292.24  5228.5   293.9  5286.1   295.1  5481.8  303.09
#Mann= 9 ,-1 , 0
  4010.3     .11       0  4333.8     .15       0    4458     .11       0
  4550.2     .15       0  4787.6     .11       0    4808     .15       0
  4977.7     .11       0  4989.1     .06       0  5009.9     .11       0
Bank Sta=4989.1,5009.9
XS Rating Curve= 0 ,0
Exp/Cntr=0.3,0.1

Type RM Length L Ch R = 1 ,6025    ,560,560,560
BEGIN DESCRIPTION:
LAKE CREEK TRIBUTARY NO. 28 13.0
END DESCRIPTION:
XS GIS Cut Line= 3
      3716917.83     10192661.09      3716033.59     10193580.75
       3715645.7     10193740.25
#Sta/Elev= 30
  3724.2  309.31  4064.9  294.26  4263.8  288.63  4282.8  287.36    4290  284.87
  4304.2  284.66  4353.6  284.85  4360.8  285.71  4367.7   289.2  4374.9  289.52
  4389.1  289.32  4424.3  286.79  4544.5  285.87  4594.1  286.84  4719.2  287.28
  4920.8  288.54  4961.8   289.6    4969  289.24 4972.08287.6955  4975.9  285.78
  4983.1  285.41  4986.8  283.04  5006.2  284.36  5012.8  287.66  5036.8  289.16
  5042.2  288.64  5071.5  289.86  5179.2  296.27  5250.1  299.39  5419.4  302.79
#Mann= 7 ,-1 , 0
  3724.2     .11       0  4064.9     .17       0  4263.8     .11       0
  4719.2     .15       0  4920.8     .11       0 4972.08     .06       0
  5012.8     .11       0
Bank Sta=4972.08,5012.8
XS Rating Curve= 0 ,0
Exp/Cntr=0.3,0.1

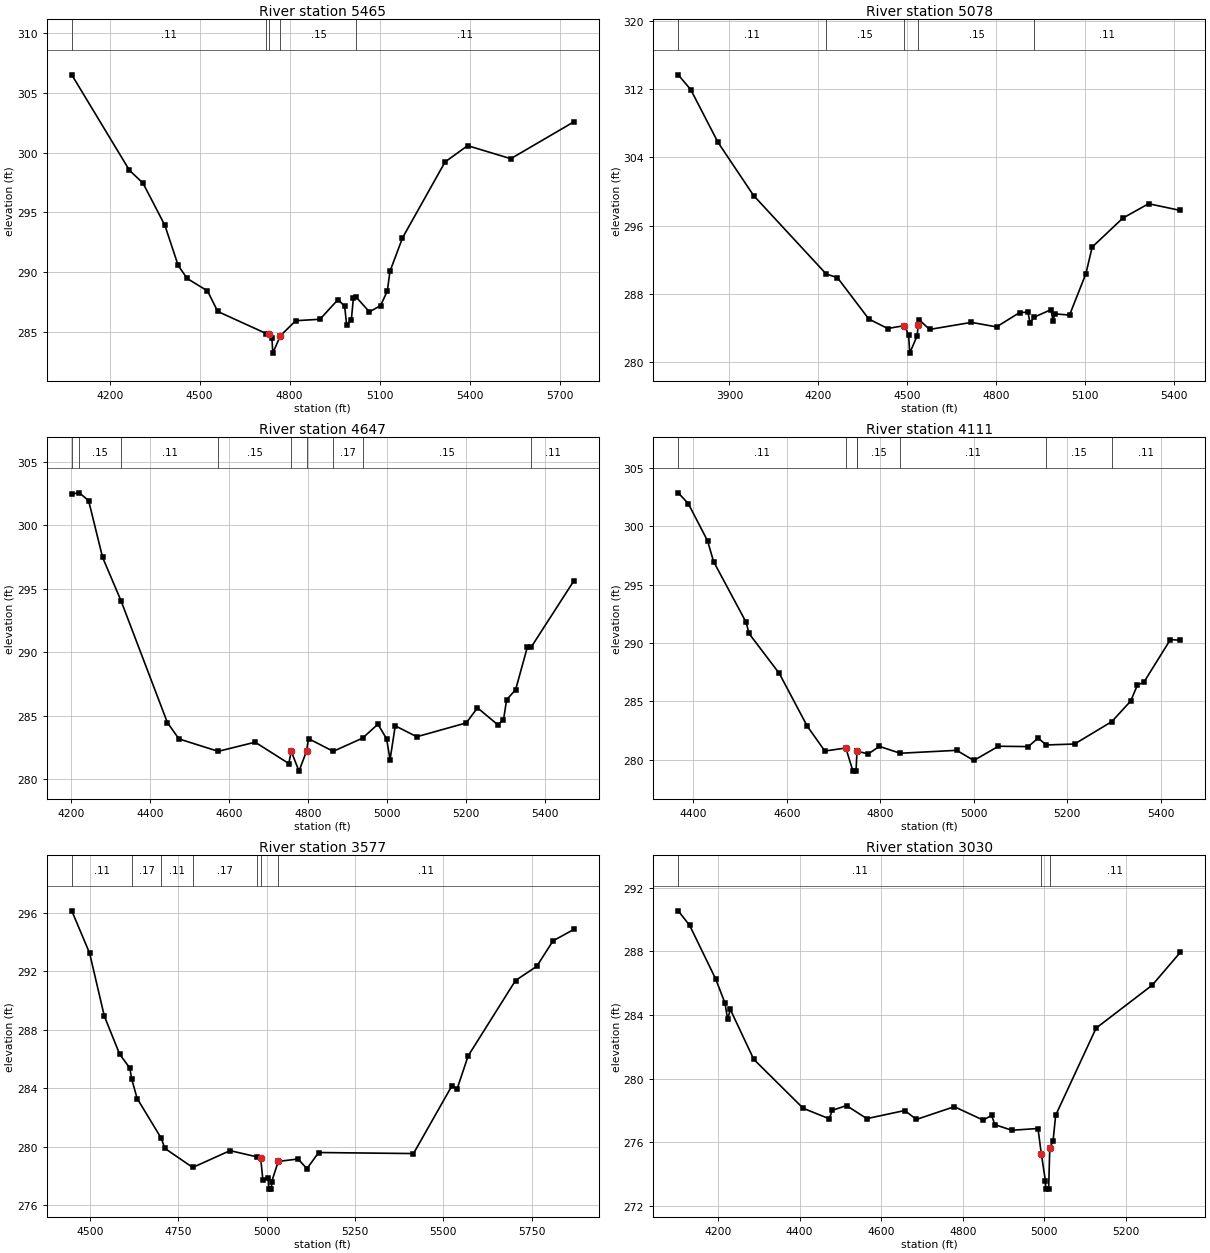
Type RM Length L Ch R = 1 ,5465    ,387,387,387
BEGIN DESCRIPTION:
LAKE CREEK TRIBUTARY NO. 28 12.0
END DESCRIPTION:
XS GIS Cut Line= 3
      3716817.85     10192661.07      3715880.11      10193156.9
      3715617.83     10193711.11
#Sta/Elev= 30
  4073.6   306.5  4265.9  298.52  4311.2  297.44  4384.2  293.91  4428.3  290.57
  4458.2  289.48  4526.1  288.44  4560.3  286.72  4722.5  284.87  4730.7  284.84
    4741  284.47  4743.8  283.24  4769.1  284.69  4820.2  285.95  4901.1  286.07
  4961.5  287.72  4983.5  287.14  4989.9  285.62  5005.5  285.98  5012.5  287.83
  5022.6   287.9  5065.9  286.69    5103  287.21  5125.6  288.43  5134.4  290.07
  5176.2  292.87  5318.2  299.22  5393.4  300.58  5537.3  299.49  5747.5  302.57
#Mann= 5 ,-1 , 0
  4073.6     .11       0  4722.5     .15       0  4730.7     .09       0
  4769.1     .15       0  5022.6     .11       0
Bank Sta=4730.7,4769.1
XS Rating Curve= 0 ,0
Exp/Cntr=0.3,0.1

Type RM Length L Ch R = 1 ,5078    ,431,431,431
BEGIN DESCRIPTION:
LAKE CREEK TRIBUTARY NO. 28 11.0
END DESCRIPTION:
XS GIS Cut Line= 3
      3716617.82      10191961.1      3715730.22     10192873.34
      3715588.45     10193271.45
#Sta/Elev= 30
  3727.2   313.7  3769.5  311.96  3861.5  305.77  3981.7  299.53  4227.1  290.31
  4264.6   289.9  4370.6  285.04  4434.4  283.92    4491  284.26  4505.1  283.19
  4508.8  281.03  4533.4  283.01 4538.28284.3764  4540.4  284.97  4575.8  283.81
  4717.3  284.64    4802  284.11  4879.9  285.79  4908.2  285.84  4915.1  284.59
  4929.9  285.27  4985.9  286.13    4993  284.78  4998.1  285.64  5048.6   285.5
  5103.7  290.35    5125  293.48  5228.2  296.87  5315.4  298.57  5422.6  297.78
#Mann= 5 ,-1 , 0
  3727.2     .11       0  4227.1     .15       0    4491     .06       0
 4538.28     .15       0  4929.9     .11       0
Bank Sta=4491,4538.28
XS Rating Curve= 0 ,0
Exp/Cntr=0.3,0.1

Type RM Length L Ch R = 1 ,4647    ,536,536,536
BEGIN DESCRIPTION:
LAKE CREEK TRIBUTARY NO. 28 10.0
END DESCRIPTION:
XS GIS Cut Line= 3
      3716167.87     10191911.05      3715786.36      10192406.9
      3715217.85     10192711.07
#Sta/Elev= 30
  4202.3  302.47  4221.3  302.55  4244.9  301.94  4280.2  297.47  4326.7  294.06
  4444.2  284.45  4473.3  283.16  4572.8  282.18  4666.3   282.9  4751.4  281.22
  4757.7  282.18  4777.2  280.62 4796.26 282.188  4801.3  283.18  4863.9  282.18
  4938.1  283.22    4977  284.32  4998.9  283.16  5007.7  281.53  5020.8  284.19
  5075.3  283.33  5200.5  284.42  5228.9  285.61  5279.9  284.28  5294.7  284.65
  5302.6  286.25  5325.3  287.03  5354.9  290.37  5364.9   290.4  5472.7  295.61
#Mann= 9 ,-1 , 0
  4202.3     .11       0  4221.3     .15       0  4326.7     .11       0
  4572.8     .15       0  4757.7     .09       0 4796.26     .15       0
  4863.9     .17       0  4938.1     .15       0  5364.9     .11       0
Bank Sta=4757.7,4796.26
XS Rating Curve= 0 ,0
Exp/Cntr=0.3,0.1

Type RM Length L Ch R = 1 ,4111    ,534,534,534
BEGIN DESCRIPTION:
LAKE CREEK TRIBUTARY NO. 28 9.0
END DESCRIPTION:
XS GIS Cut Line= 3
      3716117.83     10191861.08      3715533.19     10192101.65
      3715217.84     10192411.08
#Sta/Elev= 30
  4367.8  302.86  4389.4  301.93  4430.4  298.76  4443.5  296.97    4513  291.78
  4519.2  290.82    4584   287.4  4643.6   282.9  4681.4  280.76  4726.3  281.02
  4741.5  279.04  4748.1  279.04  4750.2  280.74  4750.5  280.75  4774.2  280.51
  4798.1  281.16  4842.5  280.57  4963.5  280.82    5000  279.95  5052.8  281.17
  5116.5  281.14  5137.7  281.87    5155  281.28  5215.6  281.36  5295.3  283.28
  5335.7  285.04  5349.9   286.4    5364  286.66  5420.6   290.3  5441.8  290.24
#Mann= 7 ,-1 , 0
  4367.8     .11       0  4726.3     .06       0  4750.2     .11       0
  4750.5     .15       0  4842.5     .11       0    5155     .15       0
  5295.3     .11       0
Bank Sta=4726.3,4750.2
XS Rating Curve= 0 ,0
Exp/Cntr=0.3,0.1

Type RM Length L Ch R = 1 ,3577    ,547,547,547
BEGIN DESCRIPTION:
LAKE CREEK TRIBUTARY NO. 28 8.0
END DESCRIPTION:
XS GIS Cut Line= 3
      3715817.83     10191311.09      3715307.19      10191714.2
      3715117.85     10192461.09
#Sta/Elev= 30
  4448.6  296.12  4499.1  293.23  4540.7  288.93  4584.1  286.33  4612.9  285.38
  4618.3  284.62  4633.7   283.3  4701.7  280.59  4712.3  279.89    4791  278.59
  4896.6  279.74  4971.6  279.32  4983.3  279.24  4989.6  277.71  5004.1  277.87
  5006.9  277.11  5013.9  277.11  5014.4  277.61    5033     279    5089  279.17
  5114.1  278.51  5147.5  279.61  5415.8  279.54  5523.9  284.14  5539.6  283.98
  5570.5  286.21  5704.6  291.36  5764.7  292.33  5810.8  294.07  5869.7  294.85
#Mann= 7 ,-1 , 0
  4448.6     .11       0  4618.3     .17       0  4701.7     .11       0
    4791     .17       0  4971.6     .11       0  4983.3     .06       0
    5033     .11       0
Bank Sta=4983.3,5033
XS Rating Curve= 0 ,0
Exp/Cntr=0.3,0.1

Type RM Length L Ch R = 1 ,3030    ,252,252,252
BEGIN DESCRIPTION:
LAKE CREEK TRIBUTARY NO. 28 7.0
END DESCRIPTION:
XS GIS Cut Line= 3
      3715617.88     10191011.05      3714869.69     10191604.82
      3714767.86     10191861.06
#Sta/Elev= 30
  4102.5  290.54  4130.6  289.62  4194.6  286.24  4217.1  284.74  4223.5  283.73
  4230.2  284.34  4287.6  281.21  4408.9  278.13  4472.8  277.47  4479.9     278
  4515.1   278.3  4564.8  277.48  4657.7  277.99  4686.5  277.43  4779.2  278.23
    4850  277.39  4870.8  277.68  4878.8   277.1  4920.4  276.75  4984.5  276.86
  4992.6  275.27  5002.8  273.55  5003.3  273.05  5010.6  273.05  5013.4  275.64
  5021.4  276.07  5027.8  277.69    5127  283.17  5264.6  285.87  5333.4  287.93
#Mann= 3 , 0 , 0
  4102.5     .11       0  4992.6     .06       0  5013.4     .11       0
Bank Sta=4992.6,5013.4
XS Rating Curve= 0 ,0
Exp/Cntr=0.3,0.1

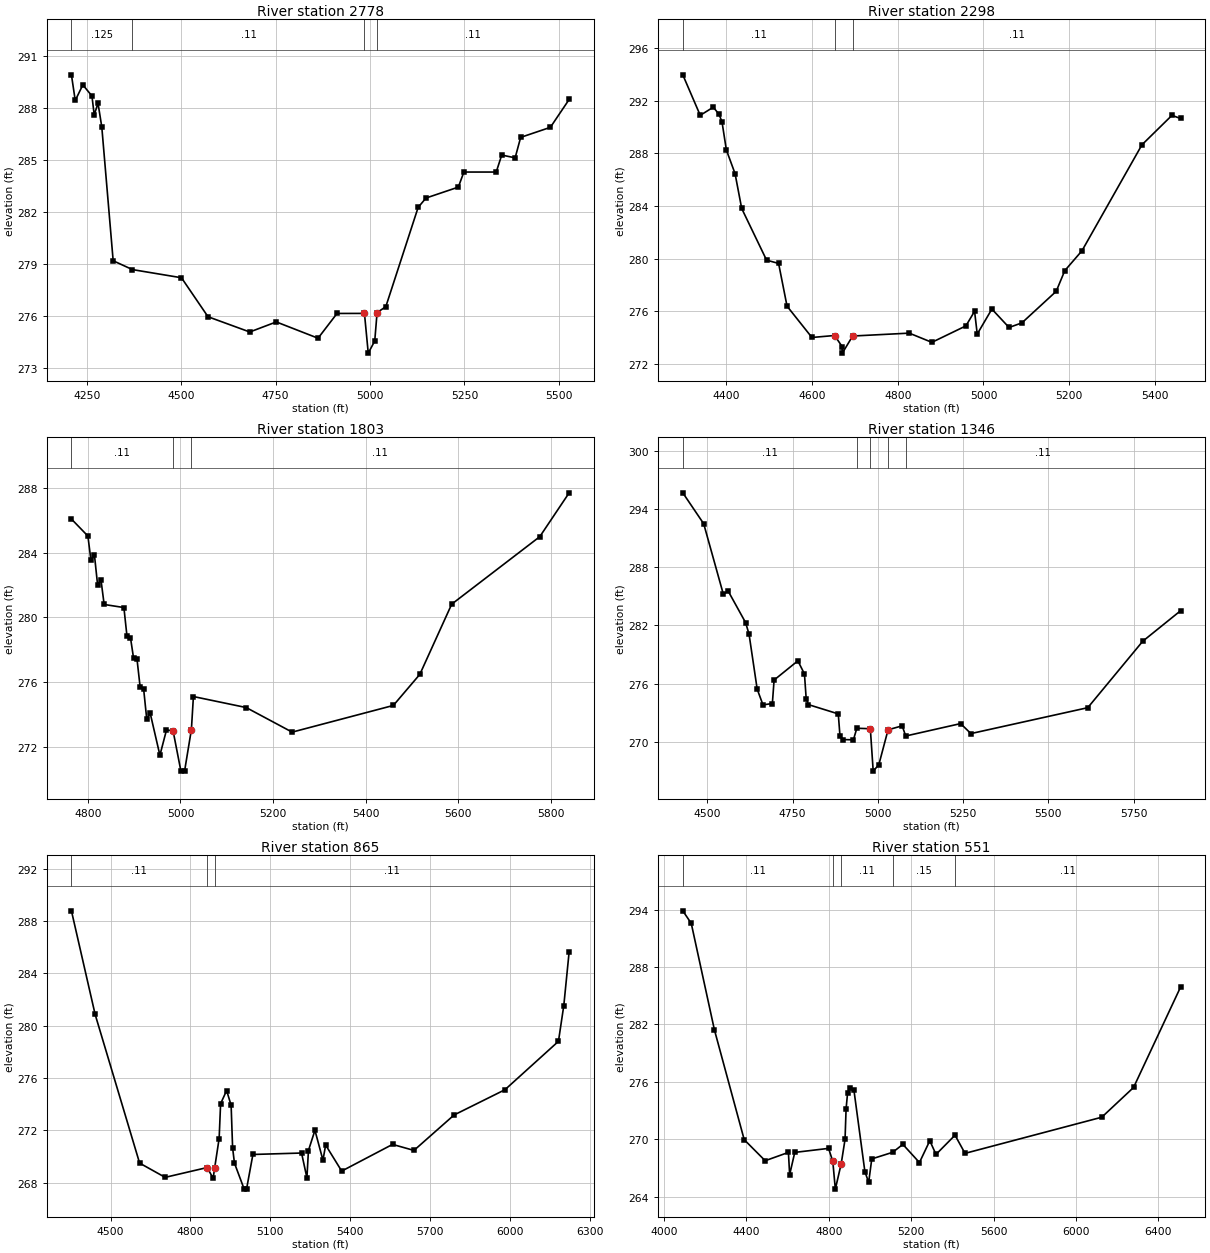
Type RM Length L Ch R = 1 ,2778    ,480,480,480
BEGIN DESCRIPTION:
LAKE CREEK TRIBUTARY NO. 28 6.0
END DESCRIPTION:
XS GIS Cut Line= 3
      3714667.85     10190611.03      3714742.15     10191397.93
      3714317.88     10191711.05
#Sta/Elev= 30
  4209.6   289.9  4219.7  288.42  4239.8  289.32  4263.9  288.68  4269.9  287.59
    4280  288.26    4290  286.89  4320.1  279.17  4371.2  278.66  4500.9  278.19
  4571.2  275.94  4681.7  275.06    4752  275.64  4862.5   274.7  4912.8  276.13
 4985.37276.1319  4995.4  273.84  5012.6  274.54  5018.8  276.18  5041.9  276.52
  5127.5  282.25  5148.3  282.79  5233.9  283.42  5248.6  284.29  5334.2  284.29
  5348.8  285.27  5384.3  285.11  5398.9  286.29  5477.6  286.87  5527.3  288.48
#Mann= 4 ,-1 , 0
  4209.6    .125       0  4371.2     .11       0 4985.37     .06       0
  5018.8     .11       0
Bank Sta=4985.37,5018.8
XS Rating Curve= 0 ,0
Exp/Cntr=0.3,0.1

Type RM Length L Ch R = 1 ,2298    ,495,495,495
BEGIN DESCRIPTION:
LAKE CREEK TRIBUTARY NO. 28 5.0
END DESCRIPTION:
XS GIS Cut Line= 3
      3714417.85     10190561.06      3714290.41     10191251.39
      3714267.85     10191711.04
#Sta/Elev= 30
    4298  293.98  4338.7   290.9  4369.2  291.52  4382.5  290.98  4389.5  290.41
  4399.7  288.27    4420  286.47  4435.5  283.82  4493.6  279.89  4521.7  279.64
  4541.4  276.39  4599.5  274.01  4652.4  274.16    4670  273.32  4670.5  272.82
  4694.6  274.12  4826.8  274.34  4879.6  273.64    4959  274.89  4979.3     276
  4985.5  274.27  5019.7  276.17  5059.8  274.77  5089.8  275.12  5169.9  277.52
  5189.9  279.09    5230   280.6  5370.1  288.66  5440.2   290.9  5460.2  290.66
#Mann= 3 , 0 , 0
    4298     .11       0  4652.4     .06       0  4694.6     .11       0
Bank Sta=4652.4,4694.6
XS Rating Curve= 0 ,0
Exp/Cntr=0.3,0.1

Type RM Length L Ch R = 1 ,1803    ,457,457,457
BEGIN DESCRIPTION:
LAKE CREEK TRIBUTARY NO. 28 4.0
END DESCRIPTION:
XS GIS Cut Line= 3
      3714267.85     10190711.07      3714090.98     10190866.86
      3713817.84     10191661.11
#Sta/Elev= 30
  4764.3  286.07  4799.9  285.02  4806.5  283.52  4814.1  283.83  4820.8  282.01
  4828.3  282.28    4835  280.79  4877.7   280.6  4884.3  278.84  4891.9  278.74
  4898.6  277.47  4906.1  277.39  4912.8  275.68  4920.4  275.55    4927  273.72
  4934.6  274.06  4955.5  271.47  4969.7  273.03  4983.9  272.99  5000.9  270.49
  5008.8  270.49 5023.55273.0587  5027.9   275.1  5141.9  274.42  5241.3   272.9
    5460  274.55  5517.2  276.47  5586.1  280.81  5776.4  284.98  5839.9  287.69
#Mann= 3 , 0 , 0
  4764.3     .11       0  4983.9     .06       0 5023.55     .11       0
Bank Sta=4983.9,5023.55
XS Rating Curve= 0 ,0
Exp/Cntr=0.3,0.1

Type RM Length L Ch R = 1 ,1346    ,481,481,481
BEGIN DESCRIPTION:
LAKE CREEK TRIBUTARY NO. 28 3.0
END DESCRIPTION:
XS GIS Cut Line= 3
      3714267.85     10190511.07      3713708.65     10190629.98
      3713817.85     10191511.04
#Sta/Elev= 30
  4428.3  295.67  4489.6  292.48  4547.2  285.21  4561.2  285.55  4612.3   282.3
  4622.5  281.11  4646.4  275.43  4663.4  273.81  4690.9  273.95    4696  276.37
  4765.7  278.35    4785     277  4790.1  274.45  4796.4  273.84  4884.2  272.88
  4889.3  270.55  4898.6  270.23  4928.6  270.21  4938.6   271.4  4978.2  271.35
  4986.6  266.98  5003.1  267.64  5030.2  271.24  5071.6  271.65  5081.9   270.6
  5242.9  271.88  5273.1  270.85  5615.8  273.52    5777  280.37  5887.8  283.51
#Mann= 5 ,-1 , 0
  4428.3     .11       0  4938.6     .15       0  4978.2     .09       0
  5030.2     .15       0  5081.9     .11       0
Bank Sta=4978.2,5030.2
XS Rating Curve= 0 ,0
Exp/Cntr=0.3,0.1

Type RM Length L Ch R = 1 ,865     ,314,314,314
BEGIN DESCRIPTION:
LAKE CREEK TRIBUTARY NO. 28 2.0
END DESCRIPTION:
XS GIS Cut Line= 3
      3714017.86     10190011.07      3713436.51     10190295.03
      3713317.85     10191511.05
#Sta/Elev= 30
    4353  288.78    4442  280.86    4609  269.49  4704.9   268.4  4862.5  269.15
  4885.1  268.33  4890.6   269.1  4907.6  271.37  4913.1  274.03  4935.7  275.04
  4952.6  273.91  4958.2  270.65  4965.1  269.49  5001.6   267.5  5010.5   267.5
  5034.4  270.15  5217.1  270.26  5237.2  268.36  5242.9  270.45  5267.3     272
  5297.4  269.71  5307.5  270.87  5367.8  268.88  5558.7  270.92  5639.1  270.46
  5789.8  273.17  5980.7   275.1  6181.6   278.8  6201.7  281.54  6221.8  285.66
#Mann= 3 , 0 , 0
    4353     .11       0  4862.5     .06       0  4890.6     .11       0
Bank Sta=4862.5,4890.6
XS Rating Curve= 0 ,0
Exp/Cntr=0.3,0.1

Type RM Length L Ch R = 1 ,551     ,0,0,0
BEGIN DESCRIPTION:
LAKE CREEK TRIBUTARY NO. 28 1.0
END DESCRIPTION:
XS GIS Cut Line= 3
      3714067.86     10189911.07      3713181.99     10190112.13
      3713017.85     10191611.07
#Sta/Elev= 30
  4091.6  293.88  4132.6  292.57    4245  281.44  4389.7  269.95  4491.5  267.75
  4604.3  268.62  4610.3  266.29  4635.1  268.62  4799.2  269.04  4819.7  267.69
  4832.1  264.78  4860.7  267.45  4879.2  269.98  4884.3  273.18  4891.4   274.8
  4901.7   275.4  4922.2  275.16  4975.6   266.6    4994  265.49    5009  267.94
  5110.5  268.63  5159.9  269.46  5240.4  267.56  5290.7  269.84  5320.8  268.41
  5413.1  270.42  5461.7  268.52  6125.6   272.3  6279.9  275.41  6507.9   285.9
#Mann= 5 ,-1 , 0
  4091.6     .11       0  4819.7     .06       0  4860.7     .11       0
  5110.5     .15       0  5413.1     .11       0
Bank Sta=4819.7,4860.7
XS Rating Curve= 0 ,0
Exp/Cntr=0.3,0.1

Chan Stop Cuts=-1
Use User Specified Reach Order=0
Composite Channel Slope=5