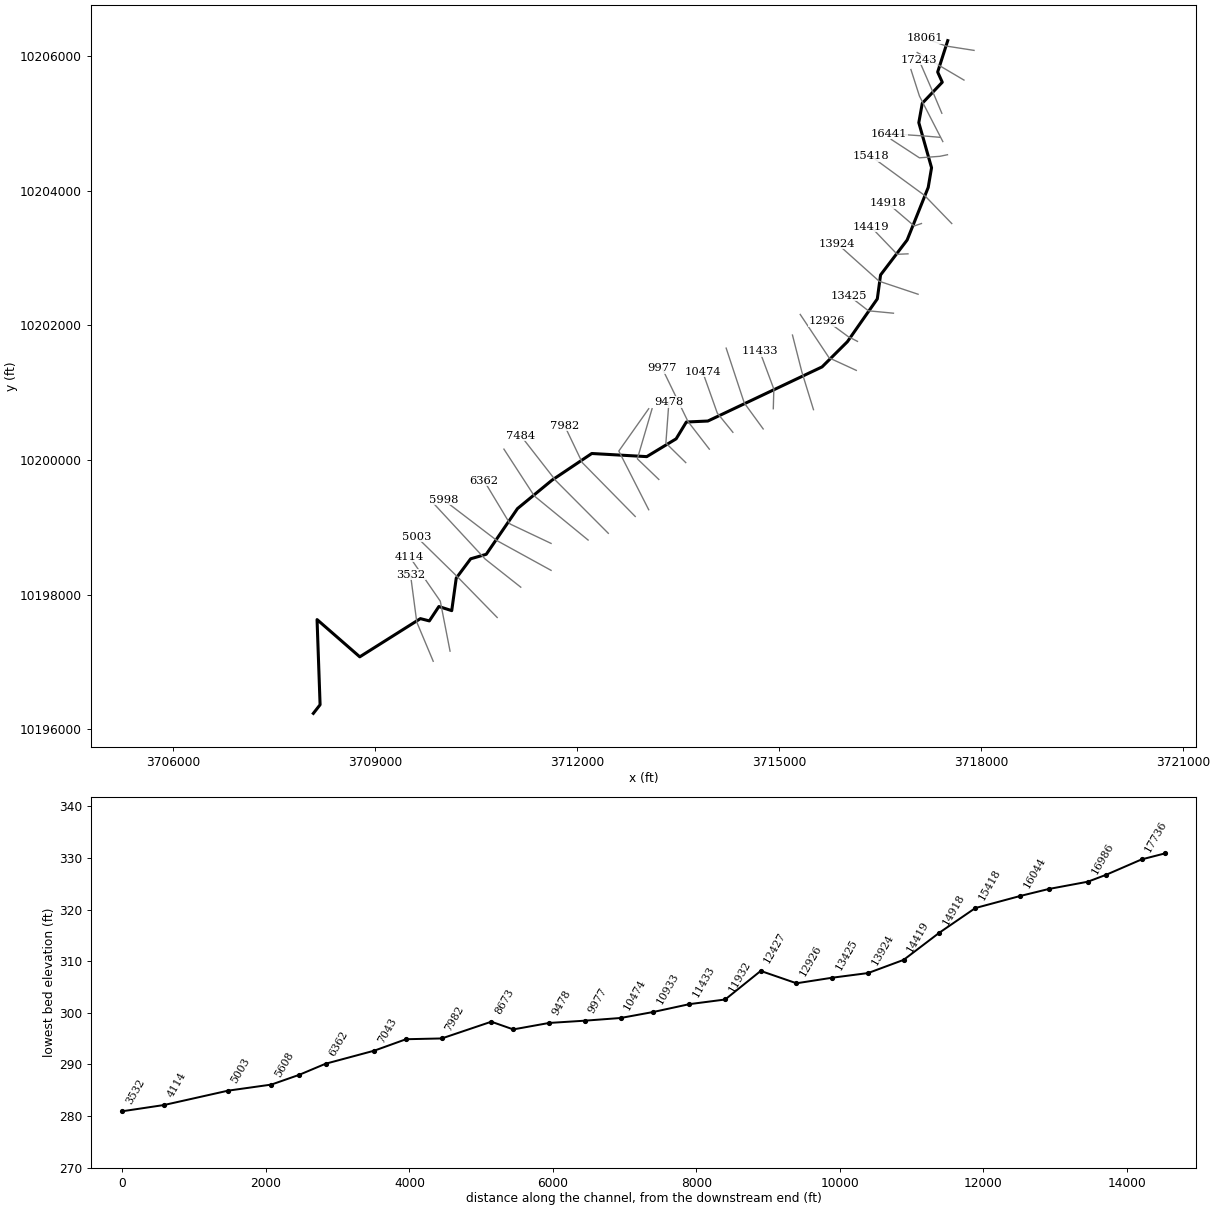
--- LAKE CREEK TRIBUTARY NO 29.prj (project) ---

Proj Title=LAKE CREEK TRIBUTARY NO 29 Base Level Engineering
Current Plan=p01
Default Exp/Contr=0.3,0.1
English Units
Geom File=g01
Flow File=f01
Plan File=p01
Y Axis Title=Elevation
X Axis Title(PF)=Main Channel Distance
X Axis Title(XS)=Station
BEGIN DESCRIPTION:
LAKE CREEK TRIBUTARY NO 29
END DESCRIPTION:
DSS Export Rating Curves= 0
DSS Export Rating Curve Sorted= 0
DSS Export Volume Flow Curves= 0
DXF OffsetX= 0
DXF OffsetY= 0
DXF ScaleX= 1
DXF ScaleY= 10

--- LAKE CREEK TRIBUTARY NO 29.p01 (plan) ---

Plan Title=Multiple Run
Short Identifier=Multiple
Geom File=g01
Flow File=f01
Subcritical Flow
K Sum by GR= 0
Std Step Tol= 0.01
Critical Tol= 0.01
Num of Std Step Trials= 20
Max Error Tol= 0.3
Flow Tol Ratio= 0.001
Split Flow NTrial= 30
Split Flow Tol= 0.02
Split Flow Ratio= 0.02
Log Output Level= 0
Friction Slope Method= 1
Unsteady Friction Slope Method= 2
Unsteady Bridges Friction Slope Method= 1
Parabolic Critical Depth
Global Vel Dist=  1 , 1 , 1
Global Log Level= 0
CheckData=True
Encroach Param= -1, 0, 0, 0
BEGIN DESCRIPTION:
Multiple Run
END DESCRIPTION:

--- LAKE CREEK TRIBUTARY NO 29.f01 (steady flow) ---

Flow Title=Multiple
Program Version=4.10
Number of Profiles= 7
Profile Names=10-year,25-year,50-year,1pct_min,100-year,1pct_plu,500-year
River Rch & RM=LAKE CREEK TRIBU,Reach-1         ,18061
     823    1143    1571     711    2146    6481    4140
River Rch & RM=LAKE CREEK TRIBU,Reach-1         ,15418
    1189    1673    2320    1056    3189    9631    6237
River Rch & RM=LAKE CREEK TRIBU,Reach-1         ,7982
    1326    1862    2577    1170    3532   10666    6870
Boundary for River Rch & Prof#=LAKE CREEK TRIBU,Reach-1         , 1
Up Type= 0
Dn Type= 3
Dn Slope=0.005
Boundary for River Rch & Prof#=LAKE CREEK TRIBU,Reach-1         , 2
Up Type= 0
Dn Type= 3
Dn Slope=0.005
Boundary for River Rch & Prof#=LAKE CREEK TRIBU,Reach-1         , 3
Up Type= 0
Dn Type= 3
Dn Slope=0.005
Boundary for River Rch & Prof#=LAKE CREEK TRIBU,Reach-1         , 4
Up Type= 0
Dn Type= 3
Dn Slope=0.005
Boundary for River Rch & Prof#=LAKE CREEK TRIBU,Reach-1         , 5
Up Type= 0
Dn Type= 3
Dn Slope=0.005
Boundary for River Rch & Prof#=LAKE CREEK TRIBU,Reach-1         , 6
Up Type= 0
Dn Type= 3
Dn Slope=0.005
Boundary for River Rch & Prof#=LAKE CREEK TRIBU,Reach-1         , 7
Up Type= 0
Dn Type= 3
Dn Slope=0.005
DSS Import GetInterval= 0
DSS Import GetPeak= 0
DSS Import FillOption= 0

--- LAKE CREEK TRIBUTARY NO 29.g01 (geometry) ---

Geom Title=Existing Conditions
Program Version=4.10

River Reach=LAKE CREEK TRIBU,Reach-1
Reach XY= 30
      3717508.23     10206226.84      3717358.46     10205760.69
      3717427.13      10205609.3       3717130.2     10205296.89
      3717078.64     10205008.87      3717267.79     10204339.71
      3717218.23     10204046.84       3716905.3     10203266.19
      3716510.76     10202747.63      3716462.32     10202392.15
       3716018.1     10201756.09      3715642.25     10201382.29
       3713946.6     10200578.32      3713626.67      10200563.6
       3713475.2     10200314.05      3713038.91     10200049.69
      3712222.53     10200096.24      3711632.24     10199700.36
       3711119.1     10199277.98       3710655.2     10198599.25
      3710423.89     10198532.48      3710209.69     10198245.33
      3710142.79     10197762.62      3709951.91     10197823.95
      3709810.41     10197610.17      3709677.44     10197644.15
      3708777.35     10197076.67      3708142.91     10197630.13
      3708188.04     10196365.21      3708087.88     10196237.15

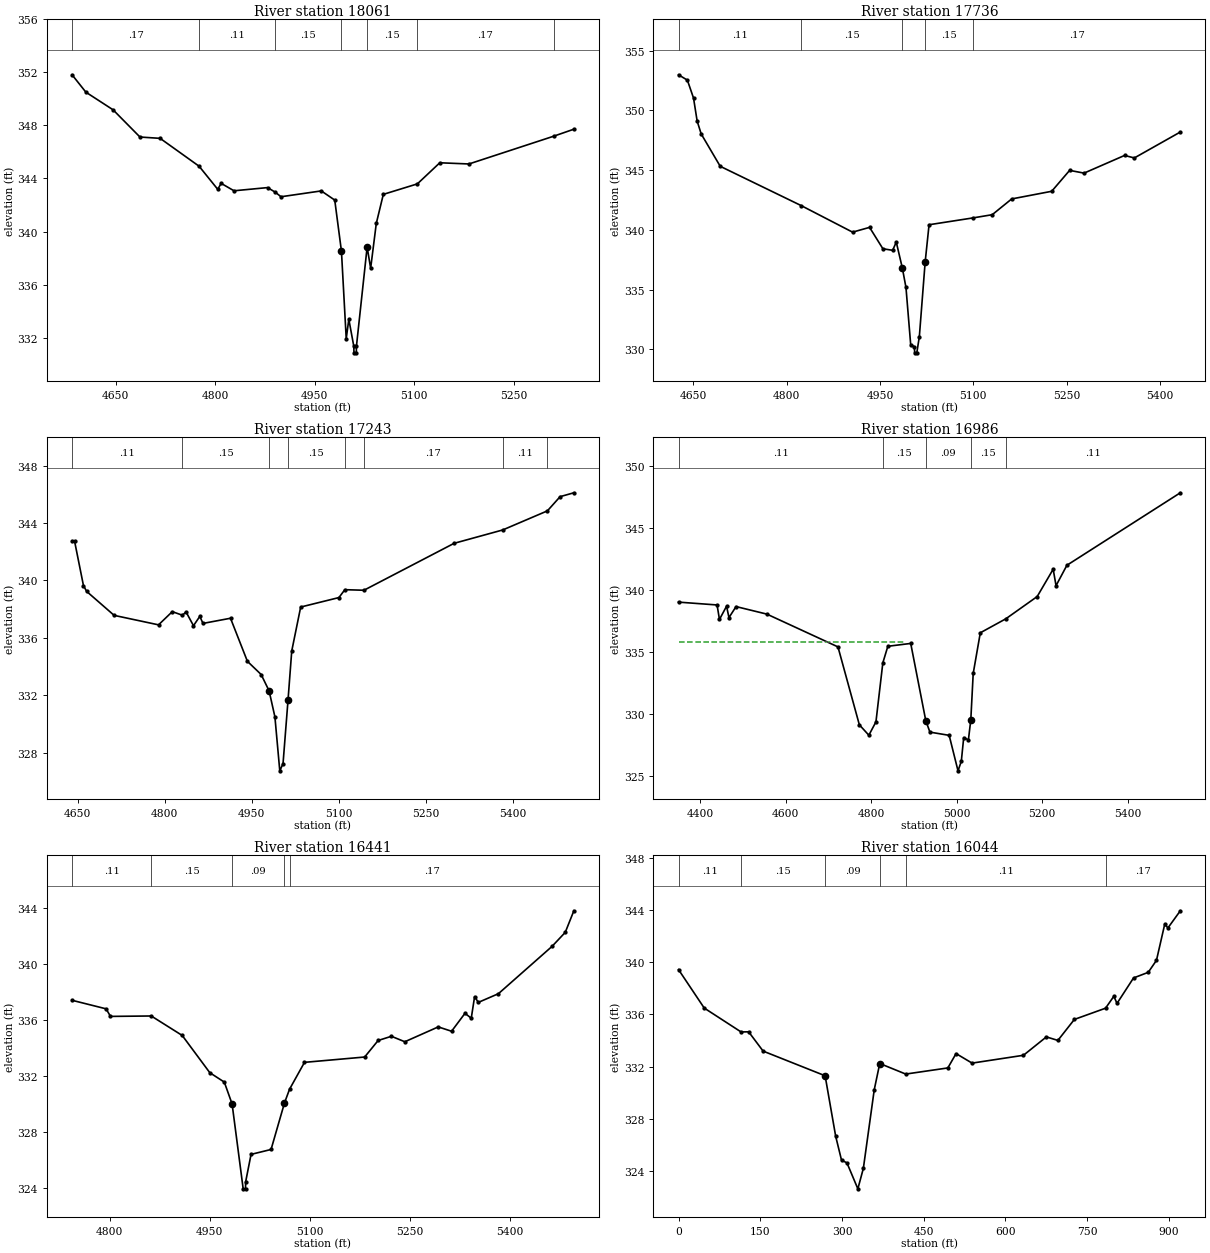
Type RM Length L Ch R = 1 ,18061   ,325,325,325
BEGIN DESCRIPTION:
LAKE CREEK TRIBUTARY NO. 29 33.0
END DESCRIPTION:
XS GIS Cut Line= 3
      3717898.93     10206082.16       3717485.1     10206146.62
      3717167.83     10206261.08
#Sta/Elev= 30
  4584.4  351.81  4605.2   350.5  4646.2  349.17  4686.7  347.12  4717.1  347.02
  4775.8  344.92  4803.9  343.18    4809  343.63  4828.4  343.07    4879  343.31
  4890.7  342.96  4899.2  342.62  4959.9  343.06  4980.2  342.37  4990.3  338.52
  4997.5  331.93  5001.4  333.39  5008.9  331.36  5009.2  330.86  5012.7  330.86
  5012.9  331.36    5029  338.83  5034.3  337.23  5042.8  340.61  5053.4   342.8
  5104.7  343.59  5138.5  345.18  5182.4  345.09    5310  347.18  5340.5  347.71
#Mann= 7 ,-1 , 0
  4584.4     .17       0  4775.8     .11       0  4890.7     .15       0
  4990.3     .09       0    5029     .15       0  5104.7     .17       0
    5310     .11       0
Bank Sta=4990.3,5029
XS Rating Curve= 0 ,0
Exp/Cntr=0.3,0.1

Type RM Length L Ch R = 1 ,17736   ,493,493,493
BEGIN DESCRIPTION:
Mapping XS ebfd88d7
END DESCRIPTION:
XS GIS Cut Line= 2
       3717749.2     10205641.26      3717054.62     10206050.94
#Sta/Elev= 30
  4626.4  352.97  4640.6  352.52  4650.5  351.02  4656.3   349.1  4662.8  348.02
  4693.4  345.31  4823.6  342.02  4906.1   339.8  4933.4   340.2  4954.8  338.41
  4970.5  338.28  4976.3  338.97  4986.1  336.79  4991.9  335.17  4999.5  330.38
  5005.6   330.2  5005.8   329.7  5009.3   329.7  5013.4  331.06  5022.7  337.28
    5029  340.42  5099.4  340.99  5130.5  341.26  5161.8  342.58  5226.1  343.22
  5254.9  344.97  5278.1  344.74  5343.2  346.22  5358.9  346.01  5432.8  348.18
#Mann= 5 ,-1 , 0
  4626.4     .11       0  4823.6     .15       0  4986.1     .09       0
  5022.7     .15       0  5099.4     .17       0
Bank Sta=4986.1,5022.7
XS Rating Curve= 0 ,0
Exp/Cntr=0.3,0.1

Type RM Length L Ch R = 1 ,17243   ,257,257,257
BEGIN DESCRIPTION:
LAKE CREEK TRIBUTARY NO. 29 32.0
END DESCRIPTION:
XS GIS Cut Line= 3
      3717420.64     10205148.34      3717279.21      10205483.2
      3717079.56     10205942.81
#Sta/Elev= 30
  4640.6  342.75  4644.8  342.75  4660.2  339.64  4665.7  339.23  4713.1  337.56
  4789.6   336.9  4813.3  337.82  4830.7  337.57    4837   337.8  4849.8  336.84
  4860.7  337.49  4866.2     337  4913.6  337.36  4942.7  334.36  4966.4  333.44
  4980.1   332.3  4990.1  330.49  4998.5  326.73  5004.1  327.23  5012.7  331.66
  5019.1  335.08  5034.5  338.14  5100.4   338.8  5110.6  339.35  5143.5  339.31
  5298.9  342.58  5382.6  343.51  5459.6  344.84  5481.5  345.83  5505.2   346.1
#Mann= 8 ,-1 , 0
  4640.6     .11       0  4830.7     .15       0  4980.1     .09       0
  5012.7     .15       0  5110.6     .11       0  5143.5     .17       0
  5382.6     .11       0  5459.6     .17       0
Bank Sta=4980.1,5012.7
XS Rating Curve= 0 ,0
Exp/Cntr=0.3,0.1

Type RM Length L Ch R = 1 ,16986   ,545,545,545
BEGIN DESCRIPTION:
LAKE CREEK TRIBUTARY NO. 29 31.0
END DESCRIPTION:
XS GIS Cut Line= 3
       3717435.2     10204728.22      3717087.87     10205404.17
      3716961.52     10205797.72
#Sta/Elev= 30
  4349.5  339.02  4439.6  338.79  4445.2  337.62  4461.8  338.69  4467.4  337.77
    4484  338.66  4556.1  338.05  4722.3   335.4  4772.3   329.1  4794.5  328.26
  4811.1  329.34  4827.2  334.11  4838.9  335.45  4892.4  335.68  4927.6  329.44
  4937.3  328.51  4982.3  328.25    5003  325.38  5010.7  326.15  5016.3  328.07
  5027.3  327.88  5032.9  329.51  5038.5  333.25  5055.1  336.54  5114.7  337.67
  5188.1  339.47  5225.5  341.68  5232.2  340.35  5257.6     342  5522.8  347.86
#Mann= 5 ,-1 , 0
  4349.5     .11       0  4827.2     .15       0  4927.6     .09       0
  5032.9     .15       0  5114.7     .11       0
#XS Ineff= 2 , 0
         4876.79  335.77
Permanent Ineff=
       F       F
Bank Sta=4927.6,5032.9
XS Rating Curve= 0 ,0
Exp/Cntr=0.3,0.1

Type RM Length L Ch R = 1 ,16441   ,397,397,397
BEGIN DESCRIPTION:
LAKE CREEK TRIBUTARY NO. 29 30.0
END DESCRIPTION:
XS GIS Cut Line= 3
      3717385.22     10204791.89      3717176.12     10204809.68
        3716635.      10204846.1
#Sta/Elev= 30
  4743.6  337.43  4794.6  336.82  4801.2  336.28  4862.3  336.31  4908.7  334.92
  4950.1  332.26  4971.8  331.59 4983.48330.0316  5000.1  323.97  5003.6  323.97
  5003.8  324.47  5011.9  326.43  5041.9  326.78    5062   330.1  5069.6  331.08
    5092     333  5182.2  333.38  5202.4  334.56  5222.3  334.86  5242.4  334.47
  5292.5  335.53  5312.5  335.22  5332.6   336.5    5342  336.15    5347  337.69
  5352.6  337.28  5382.7   337.9  5462.9  341.27  5482.9  342.28  5495.8  343.82
#Mann= 5 ,-1 , 0
  4743.6     .11       0  4862.3     .15       0 4983.48     .09       0
    5062     .11       0  5069.6     .17       0
Bank Sta=4983.48,5062
XS Rating Curve= 0 ,0
Exp/Cntr=0.3,0.1

Type RM Length L Ch R = 1 ,16044   ,626,626,626
BEGIN DESCRIPTION:
LAKE CREEK TRIBUTARY NO. 29 29.0
END DESCRIPTION:
XS GIS Cut Line= 4
      3717504.09     10204532.72      3717390.49     10204509.06
      3717087.57     10204486.77      3716667.85     10204761.07
#Sta/Elev= 30
       0  339.43    47.2  336.48   114.8  334.65   128.7  334.66   155.3  333.18
   269.1  331.29   288.5  326.65   299.2  324.82   309.2  324.61   329.2  322.62
   339.3  324.19   359.3  330.22   369.4  332.23   417.1  331.42   494.4  331.89
   509.5  332.99   538.9  332.26   633.2  332.86   675.3  334.27   696.4     334
   726.7  335.61   783.9  336.47   799.1  337.38     805  336.84   835.3  338.79
   862.3  339.22   877.4  340.14   892.5   342.9   898.5  342.63   921.2  343.94
#Mann= 6 ,-1 , 0
       0     .11       0   114.8     .15       0   269.1     .09       0
   369.4     .15       0   417.1     .11       0   783.9     .17       0
Bank Sta=269.1,369.4
XS Rating Curve= 0 ,0
Exp/Cntr=0.3,0.1

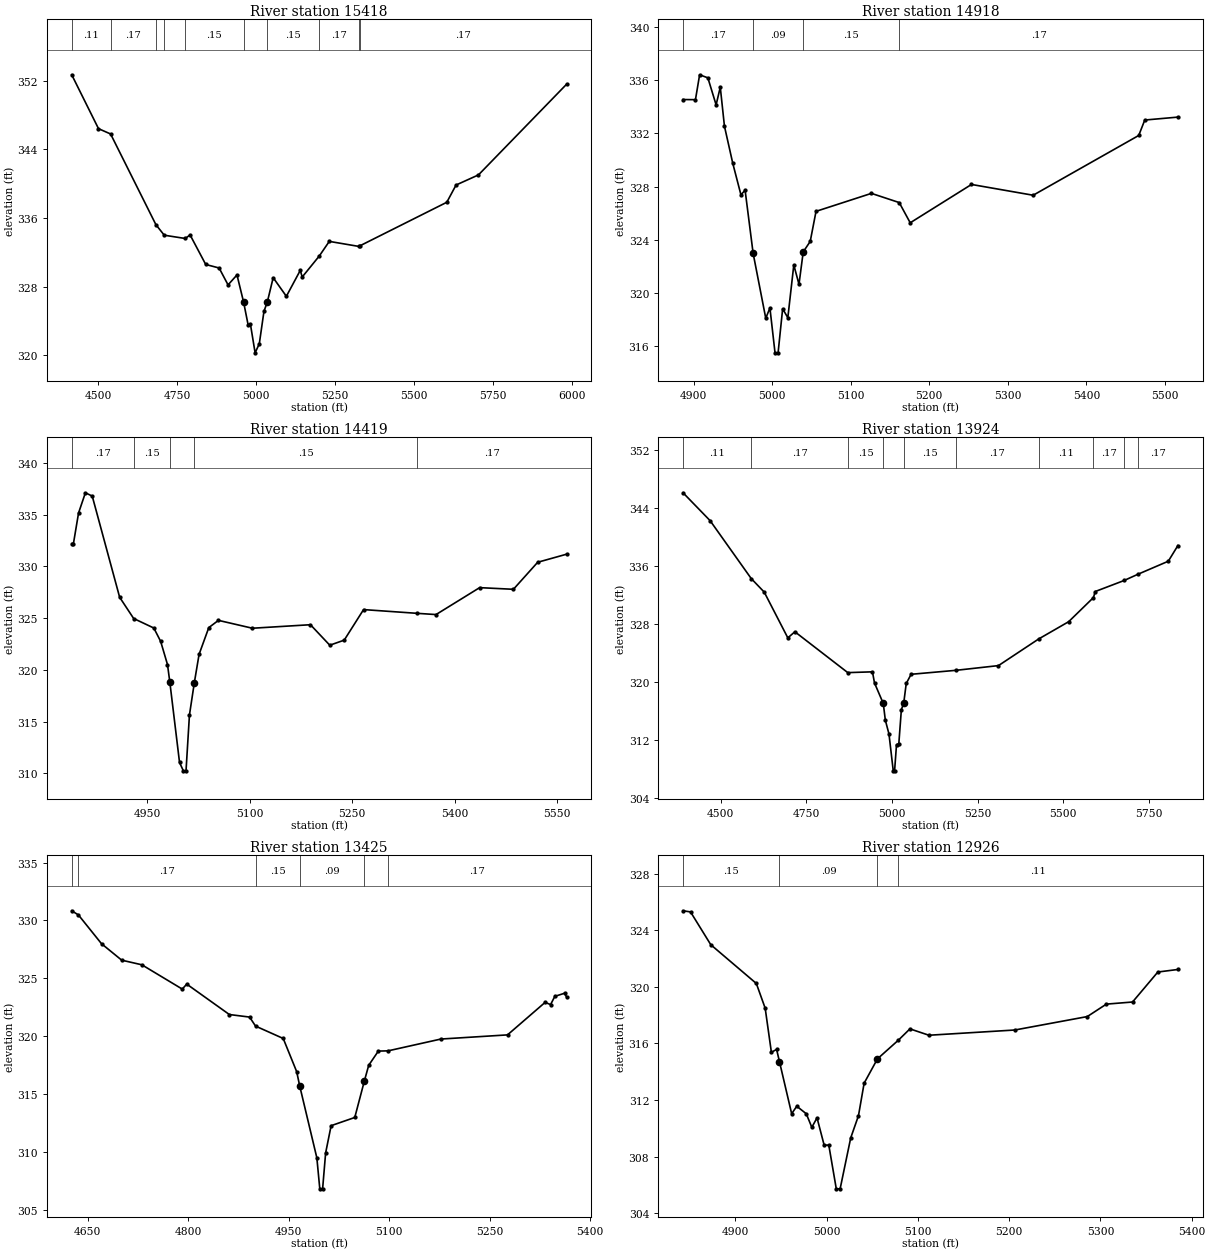
Type RM Length L Ch R = 1 ,15418   ,500,500,500
BEGIN DESCRIPTION:
LAKE CREEK TRIBUTARY NO. 29 28.0
END DESCRIPTION:
XS GIS Cut Line= 3
      3717567.88     10203511.04      3717162.08      10203929.9
      3716367.89     10204511.04
#Sta/Elev= 30
  4416.8  352.69  4501.6  346.41  4539.9  345.79  4683.4  335.22  4709.9  333.99
  4776.2  333.61  4791.7  334.02  4841.2  330.58  4883.6  330.17  4911.9   328.2
  4940.2  329.36  4961.3  326.17  4975.4  323.55  4982.6  323.66  4997.6  320.28
  5010.9  321.34  5025.6  325.11  5036.5326.2375  5054.8  329.04  5096.6  326.87
  5140.6  329.89  5146.8  329.12  5200.9  331.57  5232.5  333.27  5326.8  332.68
  5329.3  332.75  5604.7  337.83    5634  339.84    5705  341.02  5984.1  351.59
#Mann= 10 ,-1 , 0
  4416.8     .11       0  4539.9     .17       0  4683.4     .11       0
  4709.9     .17       0  4776.2     .15       0  4961.3     .09       0
  5036.5     .15       0  5200.9     .17       0  5326.8     .15       0
  5329.3     .17       0
Bank Sta=4961.3,5036.5
XS Rating Curve= 0 ,0
Exp/Cntr=0.3,0.1

Type RM Length L Ch R = 1 ,14918   ,499,499,499
BEGIN DESCRIPTION:
LAKE CREEK TRIBUTARY NO. 29 27.0
END DESCRIPTION:
XS GIS Cut Line= 3
      3717117.85     10203511.07       3717010.2      10203475.1
      3716617.89     10203811.04
#Sta/Elev= 30
  4886.5  334.55  4902.3  334.54  4907.6  336.41  4918.1  336.18  4928.6  334.15
  4933.9  335.48  4939.2  332.55  4949.8  329.76  4960.2  327.39  4965.5  327.74
 4975.73322.9945  4991.8  318.12  4997.1  318.89  5003.6  315.52  5007.5  315.52
  5013.3  318.83  5019.9  318.16  5027.5  322.12  5034.1  320.67  5039.5 323.105
  5048.4  323.89  5055.8  326.15  5126.3   327.5  5161.7  326.81  5175.7  325.29
  5253.7  328.17  5332.2  327.36  5466.6  331.85  5474.3  333.01  5516.5  333.23
#Mann= 4 ,-1 , 0
  4886.5     .17       0 4975.73     .09       0  5039.5     .15       0
  5161.7     .17       0
Bank Sta=4975.73,5039.5
XS Rating Curve= 0 ,0
Exp/Cntr=0.3,0.1

Type RM Length L Ch R = 1 ,14419   ,495,495,495
BEGIN DESCRIPTION:
LAKE CREEK TRIBUTARY NO. 29 26.0
END DESCRIPTION:
XS GIS Cut Line= 3
      3716917.85     10203061.07       3716757.7     10203053.99
      3716367.89     10203461.04
#Sta/Elev= 30
  4839.7  332.19  4842.2  332.19  4849.7  335.15  4859.7   337.1  4869.7  336.78
  4909.8  327.01  4930.3  324.96  4959.8  324.04  4969.8  322.75  4979.8  320.51
 4983.27318.7853  4997.4  311.06    5003  310.25  5006.9  310.25  5011.9  315.64
  5019.1  318.78    5026   321.5  5040.2  324.08  5054.3  324.78    5104  324.02
  5188.9  324.36  5217.2  322.38  5238.3  322.87  5266.6  325.82  5344.8  325.46
  5372.6  325.34  5436.4  327.94  5485.8  327.78  5521.3  330.39  5563.6  331.17
#Mann= 5 ,-1 , 0
  4839.7     .17       0  4930.3     .15       0 4983.27     .09       0
  5019.1     .15       0  5344.8     .17       0
Bank Sta=4983.27,5019.1
XS Rating Curve= 0 ,0
Exp/Cntr=0.3,0.1

Type RM Length L Ch R = 1 ,13924   ,499,499,499
BEGIN DESCRIPTION:
LAKE CREEK TRIBUTARY NO. 29 25.0
END DESCRIPTION:
XS GIS Cut Line= 3
      3717067.85     10202461.07      3716489.69     10202654.33
      3715867.82      10203211.1
#Sta/Elev= 30
  4390.4  346.09  4469.4  342.24  4589.5  334.24  4627.3  332.38  4696.2  326.06
  4716.8   326.9  4871.2  321.26  4943.2  321.37  4949.2  319.83  4974.8     317
  4980.8  314.69  4991.4  312.79  5003.9   307.7  5007.8   307.7  5013.4  311.32
  5020.1  311.42  5027.6  316.16  5034.3  317.01  5041.8  319.76    5056  321.03
  5187.5  321.58    5311  322.23  5428.4  325.91  5515.8  328.29  5588.1  331.62
  5593.5  332.46  5677.7  333.98  5717.5  334.83  5806.6  336.64  5834.7  338.81
#Mann= 10 ,-1 , 0
  4390.4     .11       0  4589.5     .17       0  4871.2     .15       0
  4974.8     .09       0  5034.3     .15       0  5187.5     .17       0
  5428.4     .11       0  5588.1     .17       0  5677.7     .11       0
  5717.5     .17       0
Bank Sta=4974.8,5034.3
XS Rating Curve= 0 ,0
Exp/Cntr=0.3,0.1

Type RM Length L Ch R = 1 ,13425   ,499,499,499
BEGIN DESCRIPTION:
LAKE CREEK TRIBUTARY NO. 29 24.0
END DESCRIPTION:
XS GIS Cut Line= 3
      3716702.11     10202179.48      3716330.03     10202215.26
       3716041.8     10202439.04
#Sta/Elev= 30
  4626.2  330.84  4636.2  330.48  4670.7  327.99  4700.8  326.57  4730.9  326.17
  4791.2  324.07  4797.9   324.5  4861.5  321.87  4891.7  321.65  4900.6  320.87
  4941.9   319.8    4962  316.93 4966.58  315.68  4992.1  309.48  4996.5   306.8
  5000.7   306.8  5005.2   309.9  5013.4  312.26  5048.7  312.97  5063.1  316.14
  5069.5  317.48  5083.9  318.71  5098.4  318.73  5177.2  319.75  5276.7  320.11
  5332.8  322.92    5341  322.73  5347.3  323.44  5361.8  323.71  5364.9  323.38
#Mann= 6 ,-1 , 0
  4626.2     .11       0  4636.2     .17       0  4900.6     .15       0
 4966.58     .09       0  5063.1     .15       0  5098.4     .17       0
Bank Sta=4966.58,5063.1
XS Rating Curve= 0 ,0
Exp/Cntr=0.3,0.1

Type RM Length L Ch R = 1 ,12926   ,499,499,499
BEGIN DESCRIPTION:
LAKE CREEK TRIBUTARY NO. 29 23.0
END DESCRIPTION:
XS GIS Cut Line= 3
      3716167.82     10201761.09      3716028.06     10201833.27
      3715717.82     10202061.09
#Sta/Elev= 30
  4842.7  325.38  4850.9   325.3  4873.1  322.98    4923  320.24  4932.7  318.49
  4939.5  315.37  4945.2  315.58 4948.36314.7087  4961.7  311.03  4967.3  311.56
  4977.7  311.03  4983.8  310.07  4989.5  310.74  4997.3  308.81  5002.4  308.81
  5010.6  305.72  5014.8  305.72  5026.4  309.32  5034.9  310.89  5041.1  313.19
  5055.7  314.91  5078.6  316.23  5091.3  317.03  5112.1  316.58  5206.2  316.95
  5285.6   317.9  5306.5  318.78  5335.2  318.93  5362.9  321.05  5384.9  321.23
#Mann= 4 ,-1 , 0
  4842.7     .15       0 4948.36     .09       0  5055.7     .15       0
  5078.6     .11       0
Bank Sta=4948.36,5055.7
XS Rating Curve= 0 ,0
Exp/Cntr=0.3,0.1

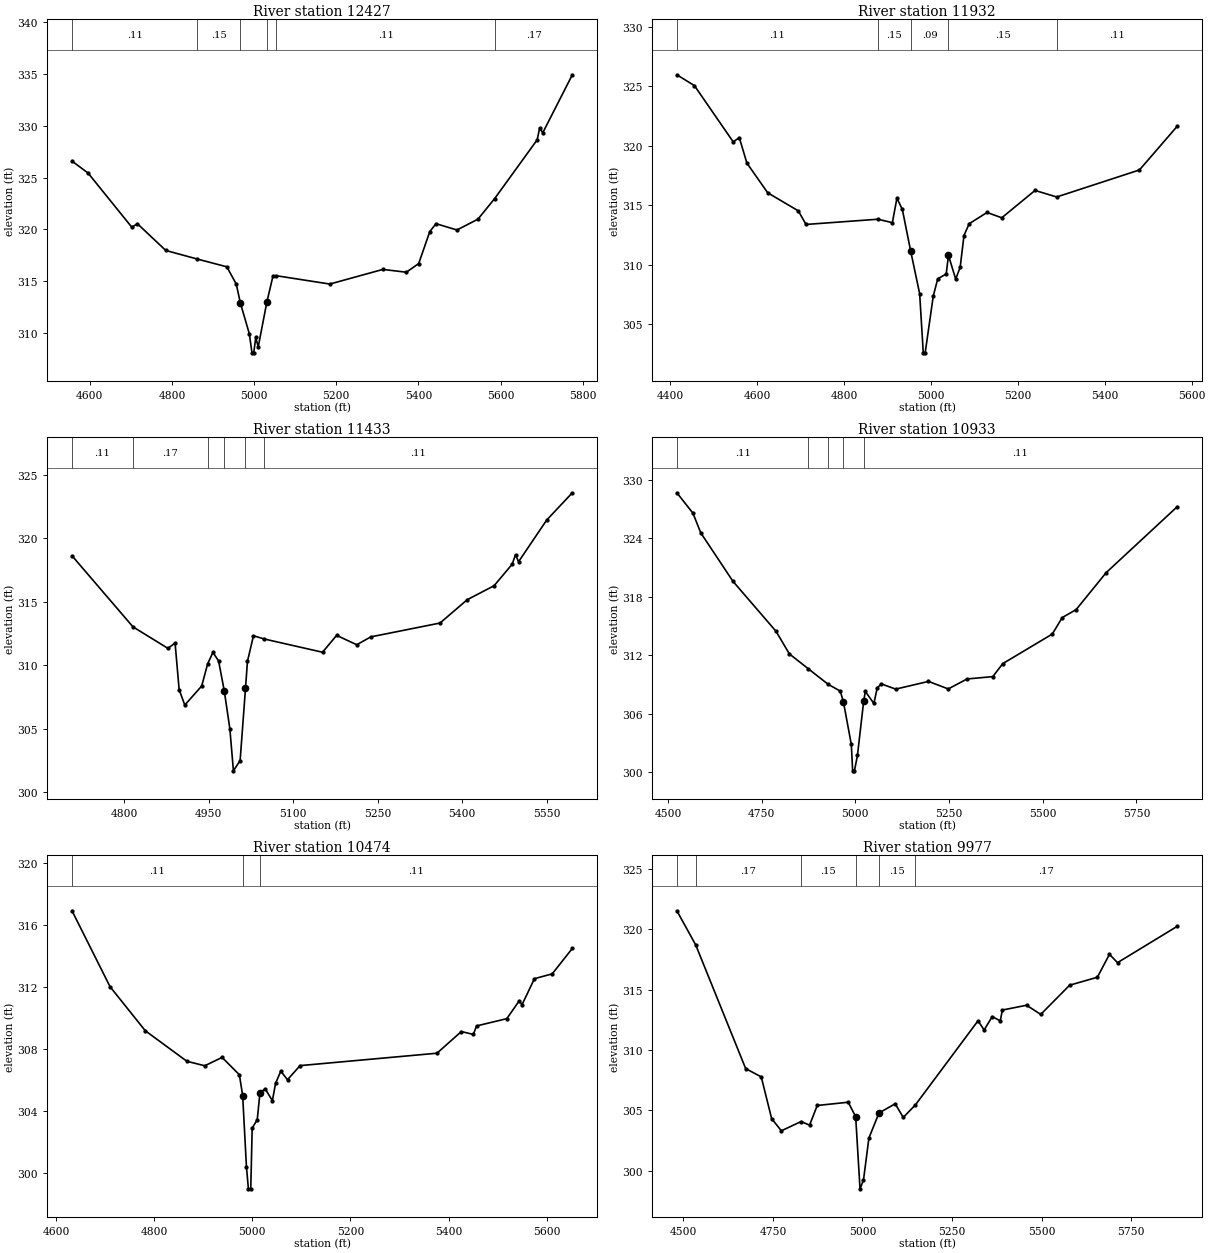
Type RM Length L Ch R = 1 ,12427   ,495,495,495
BEGIN DESCRIPTION:
LAKE CREEK TRIBUTARY NO. 29 22.0
END DESCRIPTION:
XS GIS Cut Line= 3
       3716150.1      10201330.5      3715747.25     10201515.99
      3715317.87     10202161.05
#Sta/Elev= 30
  4556.5  326.59  4595.6  325.44  4702.1  320.22  4715.9  320.55  4784.8  317.98
  4861.6  317.15  4933.6   316.4  4956.6  314.73  4966.3  312.95  4988.3  309.95
  4994.8  308.11  4999.1  308.11    5004  309.59    5010  308.68  5031.1  313.02
  5046.1  315.54  5054.5  315.54  5184.3  314.74  5313.6  316.15  5370.7  315.88
  5400.7  316.71  5427.8  319.79  5442.8  320.56  5493.9  319.95    5545  320.99
  5585.8  322.98  5689.3  328.64  5695.3  329.77  5702.9  329.32  5774.9  334.91
#Mann= 6 ,-1 , 0
  4556.5     .11       0  4861.6     .15       0  4966.3     .09       0
  5031.1     .15       0  5054.5     .11       0  5585.8     .17       0
Bank Sta=4966.3,5031.1
XS Rating Curve= 0 ,0
Exp/Cntr=0.3,0.1

Type RM Length L Ch R = 1 ,11932   ,499,499,499
BEGIN DESCRIPTION:
LAKE CREEK TRIBUTARY NO. 29 21.0
END DESCRIPTION:
XS GIS Cut Line= 3
      3715514.67     10200747.14      3715342.58     10201305.74
      3715202.56     10201854.97
#Sta/Elev= 30
  4415.5  325.95  4455.9  325.04  4545.2  320.31  4559.2  320.67  4576.6  318.53
  4624.6  316.03  4695.1  314.51  4712.6  313.37  4878.1  313.81  4911.4  313.52
  4921.9  315.58  4934.4  314.63  4953.3  311.17  4974.2  307.55  4982.5  302.58
  4986.9  302.58  5005.5  307.35  5015.8   308.8  5035.3  309.21  5040.5  310.77
  5057.1  308.78  5067.4  309.77  5076.2  312.44  5088.1  313.43  5129.3  314.38
  5163.1  313.93  5239.7  316.23  5289.5  315.68  5479.9  317.95  5566.8  321.62
#Mann= 5 ,-1 , 0
  4415.5     .11       0  4878.1     .15       0  4953.3     .09       0
  5040.5     .15       0  5289.5     .11       0
Bank Sta=4953.3,5040.5
XS Rating Curve= 0 ,0
Exp/Cntr=0.3,0.1

Type RM Length L Ch R = 1 ,11433   ,500,500,500
BEGIN DESCRIPTION:
LAKE CREEK TRIBUTARY NO. 29 20.0
END DESCRIPTION:
XS GIS Cut Line= 3
      3714917.85     10200761.06      3714925.94     10201053.45
      3714717.85     10201611.09
#Sta/Elev= 30
  4707.5  318.62  4815.7  313.02  4877.6  311.33  4890.4  311.74  4897.6  308.08
  4907.6  306.86  4937.6  308.36  4948.2  310.11  4957.6  311.01  4967.6  310.33
  4977.6     308  4987.6  304.99  4993.9  301.68  5005.8  302.49 5015.32308.1707
  5018.8   310.3  5029.5  312.32    5049  312.06    5152  311.02    5177  312.35
  5212.7  311.61  5237.6  312.23  5360.4  313.32  5408.8  315.16  5456.4  316.26
  5488.4  317.95  5494.4   318.7  5499.8  318.15  5549.7  321.43  5595.2  323.58
#Mann= 6 ,-1 , 0
  4707.5     .11       0  4815.7     .17       0  4948.2     .15       0
  4977.6     .09       0 5015.32     .15       0    5049     .11       0
Bank Sta=4977.6,5015.32
XS Rating Curve= 0 ,0
Exp/Cntr=0.3,0.1

Type RM Length L Ch R = 1 ,10933   ,459,459,459
BEGIN DESCRIPTION:
LAKE CREEK TRIBUTARY NO. 29 19.0
END DESCRIPTION:
XS GIS Cut Line= 3
      3714767.86     10200461.06      3714487.26     10200845.69
      3714217.86     10201661.04
#Sta/Elev= 30
  4523.9  328.65  4566.8  326.56  4587.6  324.55  4673.4  319.59  4788.5  314.46
    4824  312.15  4874.4  310.63  4926.9  309.05    4960  308.33  4968.4   307.2
  4989.3  302.88  4992.9  300.17  4997.7  300.17  5005.7  301.76  5022.3307.2964
  5026.7   308.3  5049.5  307.07  5058.3  308.64  5068.9  309.08  5107.7  308.54
  5195.2  309.33  5247.9  308.56  5298.1  309.58  5366.8  309.82  5393.3  311.15
  5525.5  314.18    5552  315.87    5589  316.68  5669.2  320.47  5858.7  327.22
#Mann= 5 ,-1 , 0
  4523.9     .11       0  4874.4     .15       0  4926.9     .11       0
  4968.4     .06       0  5022.3     .11       0
Bank Sta=4968.4,5022.3
XS Rating Curve= 0 ,0
Exp/Cntr=0.3,0.1

Type RM Length L Ch R = 1 ,10474   ,497,497,497
BEGIN DESCRIPTION:
LAKE CREEK TRIBUTARY NO. 29 18.0
END DESCRIPTION:
XS GIS Cut Line= 3
      3714317.86     10200411.06      3714086.16     10200696.32
      3713867.84      10201311.1
#Sta/Elev= 30
  4632.5  316.94  4710.1  312.04  4781.9   309.2  4866.7  307.23  4903.1  306.94
  4938.5  307.48  4973.7  306.36  4980.4  305.02  4988.1  300.42  4992.1     299
  4996.9     299  4999.8  302.92  5010.1  303.46  5015.7  305.21  5026.3  305.45
    5041  304.69  5047.5  305.81  5058.1  306.59  5071.8  306.04  5097.4  306.95
  5376.5  307.75  5426.2  309.15  5450.7  308.96  5457.1  309.51  5518.8  309.98
  5544.4  311.14  5549.7  310.87  5575.2  312.56  5611.4  312.87  5652.4  314.51
#Mann= 3 , 0 , 0
  4632.5     .11       0  4980.4     .06       0  5015.7     .11       0
Bank Sta=4980.4,5015.7
XS Rating Curve= 0 ,0
Exp/Cntr=0.3,0.1

Type RM Length L Ch R = 1 ,9977    ,499,499,499
BEGIN DESCRIPTION:
LAKE CREEK TRIBUTARY NO. 29 17.0
END DESCRIPTION:
XS GIS Cut Line= 3
      3713967.86     10200161.06      3713651.18     10200570.98
      3713267.84      10201361.1
#Sta/Elev= 30
    4482  321.53  4534.6   318.7    4674  308.45  4717.5  307.76  4746.5   304.3
  4773.6  303.29  4828.7  304.06  4852.4  303.76  4873.7  305.39  4960.2  305.66
    4981  304.46  4993.1  298.48  5002.8  299.21  5017.9  302.69  5046.1  304.77
  5091.2  305.53  5113.8   304.4  5147.7  305.44  5322.4  312.41  5339.5  311.65
    5362  312.76  5384.6   312.4  5390.2   313.3  5457.9   313.7  5497.4  312.94
  5578.1  315.36  5655.4  316.02  5689.2  317.92  5711.7  317.23  5878.2  320.24
#Mann= 6 ,-1 , 0
    4482     .15       0  4534.6     .17       0  4828.7     .15       0
    4981     .09       0  5046.1     .15       0  5147.7     .17       0
Bank Sta=4981,5046.1
XS Rating Curve= 0 ,0
Exp/Cntr=0.3,0.1

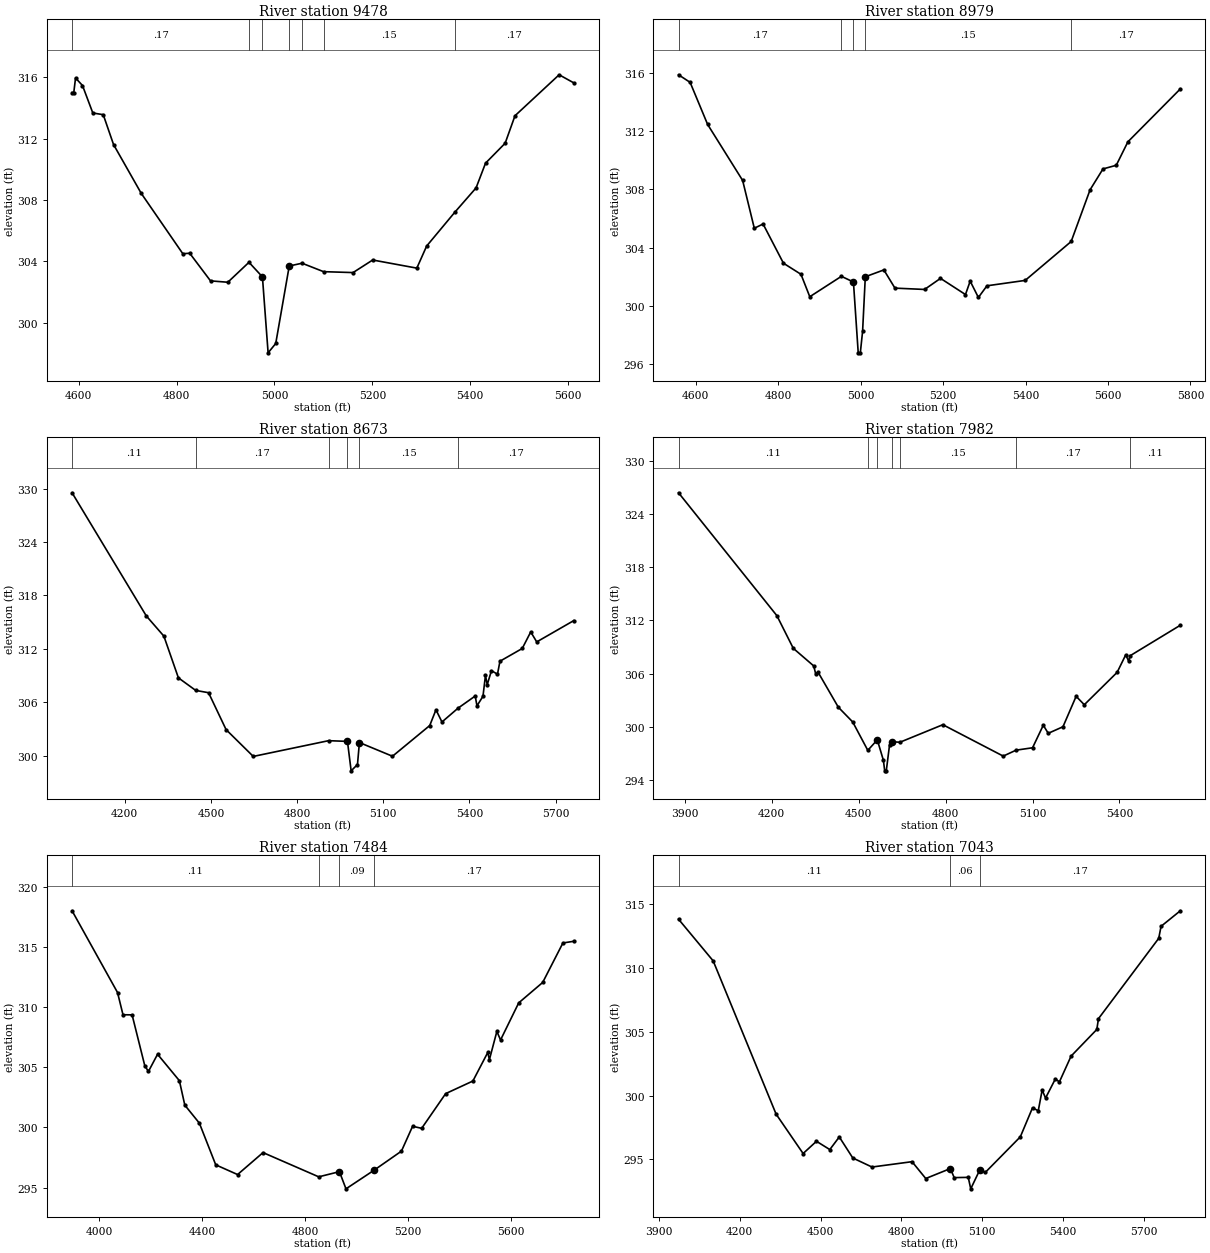
Type RM Length L Ch R = 1 ,9478    ,499,499,499
BEGIN DESCRIPTION:
LAKE CREEK TRIBUTARY NO. 29 16.0
END DESCRIPTION:
XS GIS Cut Line= 3
      3713617.88     10199961.04      3713322.88     10200250.94
      3713367.85     10200861.09
#Sta/Elev= 30
  4586.4     315  4589.9     315  4593.5  315.95  4607.7  315.46  4628.8  313.67
  4650.1  313.56  4671.2  311.61  4727.8  308.43  4812.7   304.5  4826.8  304.53
  4869.3  302.73  4904.7  302.64  4947.9  303.94  4975.4  302.99    4987  298.04
  5002.6  298.65  5030.2   303.7  5056.4  303.88  5100.3  303.33  5160.6  303.27
  5200.7  304.09  5290.9  303.56    5311     305  5368.2  307.19    5412  308.79
  5431.3   310.4  5471.4   311.7  5491.5  313.49  5581.7  316.16  5611.8  315.63
#Mann= 7 ,-1 , 0
  4586.4     .17       0  4947.9     .15       0  4975.4     .09       0
  5030.2     .15       0  5056.4     .17       0  5100.3     .15       0
  5368.2     .17       0
Bank Sta=4975.4,5030.2
XS Rating Curve= 0 ,0
Exp/Cntr=0.3,0.1

Type RM Length L Ch R = 1 ,8979    ,306,306,306
BEGIN DESCRIPTION:
LAKE CREEK TRIBUTARY NO. 29 15.0
END DESCRIPTION:
XS GIS Cut Line= 3
      3713217.82      10199711.1      3712899.14     10200017.08
      3713117.86      10200761.1
#Sta/Elev= 30
  4558.2  315.87  4586.3  315.35  4628.8  312.46  4713.7  308.62    4742  305.34
  4763.3  305.63  4812.7  302.94  4855.2  302.18  4876.6  300.64  4953.3  302.04
  4982.5  301.65  4994.1  296.79  4999.2  296.79  5004.7  298.26  5011.3  302.01
  5056.3  302.48  5083.2  301.23  5155.1  301.14  5193.7   301.9  5254.3  300.79
  5265.7  301.71  5285.6  300.59  5306.4  301.39  5399.1  301.76  5510.7  304.43
  5556.6  307.98  5587.9  309.41  5620.1  309.66  5648.3  311.27  5775.5   314.9
#Mann= 5 ,-1 , 0
  4558.2     .17       0  4953.3     .15       0  4982.5     .09       0
  5011.3     .15       0  5510.7     .17       0
Bank Sta=4982.5,5011.3
XS Rating Curve= 0 ,0
Exp/Cntr=0.3,0.1

Type RM Length L Ch R = 1 ,8673    ,691,691,691
BEGIN DESCRIPTION:
LAKE CREEK TRIBUTARY NO. 29 14.0
END DESCRIPTION:
XS GIS Cut Line= 3
      3713067.84      10199261.1      3712624.03      10200132.6
      3713067.86     10200761.09
#Sta/Elev= 30
  4016.4  329.53  4274.9  315.69  4336.1  313.42  4386.7  308.73  4446.9  307.32
  4491.7  307.06  4552.8  302.91  4647.4   299.9  4909.8  301.67  4975.4  301.59
  4988.2  298.28  5010.3  298.99    5017  301.46  5132.2  299.92  5261.9  303.37
  5283.6  305.14  5304.5  303.77  5360.7  305.33  5420.3  306.69  5426.4  305.58
  5447.3  306.66    5456     309  5462.1  307.97  5476.9  309.54  5497.8  309.14
  5506.5   310.6    5584  312.03  5613.6  313.89  5634.5  312.77  5763.8  315.17
#Mann= 6 ,-1 , 0
  4016.4     .11       0  4446.9     .17       0  4909.8     .15       0
  4975.4     .09       0    5017     .15       0  5360.7     .17       0
Bank Sta=4975.4,5017
XS Rating Curve= 0 ,0
Exp/Cntr=0.3,0.1

Type RM Length L Ch R = 1 ,7982    ,498,498,498
BEGIN DESCRIPTION:
LAKE CREEK TRIBUTARY NO. 29 13.0
END DESCRIPTION:
XS GIS Cut Line= 3
      3712867.86     10199161.07      3712081.29     10199960.77
      3711817.86     10200511.06
#Sta/Elev= 30
  3878.3  326.38  4217.7  312.53  4274.3  308.85    4345  306.86  4352.1   305.9
  4359.1   306.2  4429.8  302.21  4479.4  300.55  4531.5  297.35  4564.3  298.53
  4585.4  296.22  4589.8  295.04  4595.3  295.04  4606.7     298  4613.7  298.33
  4642.2  298.26  4790.5  300.24  4998.9   296.7  5043.2  297.37  5100.1  297.64
  5137.1  300.18  5154.3  299.27  5205.1  300.01  5250.5  303.44  5278.7  302.49
    5392  306.14  5421.6  308.11  5431.8  307.41  5436.7  308.01  5610.1  311.45
#Mann= 7 ,-1 , 0
  3878.3     .11       0  4531.5     .17       0  4564.3     .09       0
  4613.7     .17       0  4642.2     .15       0  5043.2     .17       0
  5436.7     .11       0
Bank Sta=4564.3,4613.7
XS Rating Curve= 0 ,0
Exp/Cntr=0.3,0.1

Type RM Length L Ch R = 1 ,7484    ,441,441,441
BEGIN DESCRIPTION:
LAKE CREEK TRIBUTARY NO. 29 12.0
END DESCRIPTION:
XS GIS Cut Line= 3
      3712467.87     10198911.05       3711687.6     10199693.77
      3711167.87     10200361.05
#Sta/Elev= 30
  3894.8  318.05  4071.6  311.24  4092.8  309.39  4128.2  309.38  4177.7  305.13
  4191.8  304.67  4227.2   306.1    4312   303.9  4333.2  301.86  4389.8  300.36
  4453.4  296.89  4538.3  296.08  4637.3  297.91  4853.8  295.89  4934.3  296.32
  4959.8  294.89  5069.6  296.45  5175.4  298.03  5218.8   300.1  5254.1  299.93
  5347.3  302.82  5453.2  303.87  5511.1  306.25  5517.4  305.65  5546.4     308
  5560.8  307.29  5631.4  310.38  5724.6  312.08  5803.3  315.37  5845.8  315.51
#Mann= 4 ,-1 , 0
  3894.8     .11       0  4853.8     .17       0  4934.3     .09       0
  5069.6     .17       0
Bank Sta=4934.3,5069.6
XS Rating Curve= 0 ,0
Exp/Cntr=0.3,0.1

Type RM Length L Ch R = 1 ,7043    ,681,681,681
BEGIN DESCRIPTION:
LAKE CREEK TRIBUTARY NO. 29 11.0
END DESCRIPTION:
XS GIS Cut Line= 3
      3712167.84     10198811.08      3711368.82     10199465.93
      3710917.85     10200161.08
#Sta/Elev= 30
  3972.8  313.83  4101.3  310.56  4334.8  298.54    4435  295.45  4484.5  296.41
    4534  295.76  4569.2  296.75  4619.3   295.1  4690.5  294.39  4839.1  294.81
    4890  293.49  4981.3  294.27  4995.5  293.56  5047.7  293.58  5056.9  292.68
  5089.9  294.14    5111  293.97  5240.9  296.76  5286.2  299.04  5307.4   298.8
  5321.9  300.43  5334.5   299.8  5370.8   301.3  5385.9  301.07  5429.2  303.09
  5524.6  305.18  5530.9  306.03  5754.4  312.33    5763  313.27  5834.5  314.49
#Mann= 3 , 0 , 0
  3972.8     .11       0  4981.3     .06       0  5089.9     .17       0
Bank Sta=4981.3,5089.9
XS Rating Curve= 0 ,0
Exp/Cntr=0.3,0.1

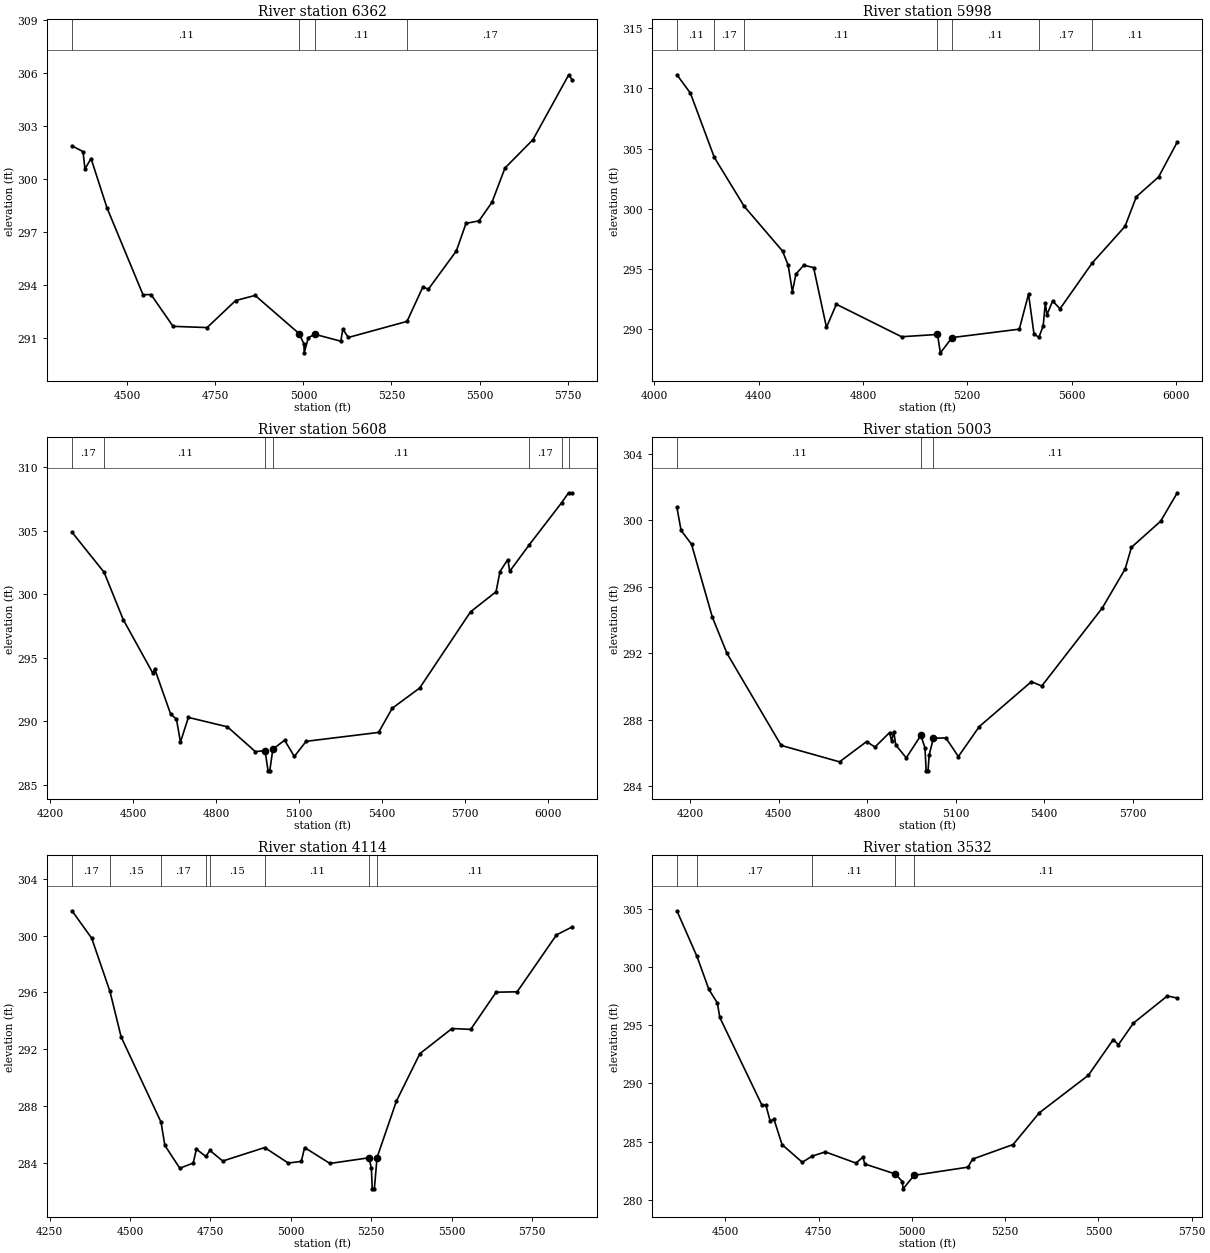
Type RM Length L Ch R = 1 ,6362    ,364,364,364
BEGIN DESCRIPTION:
LAKE CREEK TRIBUTARY NO. 29 10.0
END DESCRIPTION:
XS GIS Cut Line= 3
      3711617.82     10198761.09      3711009.45     10199049.27
      3710624.03     10199689.89
#Sta/Elev= 30
  4342.9  301.86  4374.2  301.53  4379.7  300.55    4397  301.14  4442.4  298.34
  4544.5  293.43  4567.2  293.44  4629.9  291.64  4726.5  291.57  4807.6   293.1
  4862.9  293.39  4987.7  291.23  5001.6  290.64  5002.1  290.14  5014.2     291
  5032.3  291.19  5106.1   290.8  5111.9  291.48  5127.5  291.01  5294.2  291.92
  5339.2  293.87  5354.7  293.74  5434.3  295.91  5461.7  297.47  5498.5  297.61
  5535.4  298.66  5572.3   300.6  5651.9  302.21  5753.4  305.88  5763.7  305.57
#Mann= 4 ,-1 , 0
  4342.9     .11       0  4987.7     .06       0  5032.3     .11       0
  5294.2     .17       0
Bank Sta=4987.7,5032.3
XS Rating Curve= 0 ,0
Exp/Cntr=0.3,0.1

Type RM Length L Ch R = 1 ,5998    ,390,390,390
BEGIN DESCRIPTION:
LAKE CREEK TRIBUTARY NO. 29 9.0
END DESCRIPTION:
XS GIS Cut Line= 3
      3711617.83     10198361.08       3710817.3     10198800.92
      3710017.84     10199411.08
#Sta/Elev= 30
  4086.6  311.14  4138.2  309.62    4230  304.27  4344.6   300.2  4491.6  296.48
  4513.4   295.3  4529.5   293.1    4543  294.56    4573   295.3  4610.9   295.1
  4660.2  290.13  4698.1  292.05  4948.2  289.35    5086  289.54  5097.1  288.01
  5142.2  289.28  5399.8  289.98  5435.2   292.9    5456   289.6  5474.7  289.29
  5491.3  290.24  5499.6  292.14  5505.9  291.18  5527.7  292.33  5555.8  291.67
  5679.3  295.48  5805.2  298.53  5848.8     301    5934  302.64  6005.7  305.55
#Mann= 7 ,-1 , 0
  4086.6     .11       0    4230     .17       0  4344.6     .11       0
    5086     .06       0  5142.2     .11       0  5474.7     .17       0
  5679.3     .11       0
Bank Sta=5086,5142.2
XS Rating Curve= 0 ,0
Exp/Cntr=0.3,0.1

Type RM Length L Ch R = 1 ,5608    ,605,605,605
BEGIN DESCRIPTION:
LAKE CREEK TRIBUTARY NO. 29 8.0
END DESCRIPTION:
XS GIS Cut Line= 3
      3711167.88     10198111.05      3710639.66     10198528.43
      3709867.88     10199361.04
#Sta/Elev= 30
  4278.8  304.87  4394.8  301.72    4464     298  4571.4  293.77  4577.8  294.12
  4635.5  290.56  4656.3  290.18  4670.8  288.37  4699.4  290.31  4840.6  289.57
  4941.6  287.62  4976.4   287.7  4987.5  286.11  4993.6  286.11  5004.7  287.81
  5047.3  288.52  5082.4  287.24  5124.9  288.43  5386.9  289.13  5436.2  291.03
  5535.4  292.62  5719.2  298.61  5811.5  300.19  5825.7  301.78    5854  302.72
  5860.9   301.8  5931.5  303.88  6048.8   307.2  6073.7  307.97  6087.3  307.92
#Mann= 7 ,-1 , 0
  4278.8     .17       0  4394.8     .11       0  4976.4     .06       0
  5004.7     .11       0  5931.5     .17       0  6048.8     .11       0
  6073.7     .17       0
Bank Sta=4976.4,5004.7
XS Rating Curve= 0 ,0
Exp/Cntr=0.3,0.1

Type RM Length L Ch R = 1 ,5003    ,889,889,889
BEGIN DESCRIPTION:
LAKE CREEK TRIBUTARY NO. 29 7.0
END DESCRIPTION:
XS GIS Cut Line= 3
      3710817.86     10197661.06      3710226.76     10198266.03
      3709617.84     10198861.08
#Sta/Elev= 30
  4154.2  300.77  4168.3  299.39  4203.7  298.56  4274.4  294.17  4323.9     292
  4507.8  286.46  4705.8  285.47  4797.6  286.69  4825.9  286.36  4875.5  287.23
  4882.5  286.72  4889.7  287.28  4896.7  286.48  4932.1  285.71  4981.5  287.06
  4995.6  286.32  4999.6  284.93  5005.9  284.93  5009.9  285.89  5024.1  286.89
  5066.5  286.91  5108.9  285.79  5179.7  287.59  5356.4  290.29  5391.7  290.03
  5596.9  294.72  5674.6  297.07  5695.9  298.37  5794.9  299.94  5851.4  301.65
#Mann= 3 ,-1 , 0
  4154.2     .11       0  4981.5     .06       0  5024.1     .11       0
Bank Sta=4981.5,5024.1
XS Rating Curve= 0 ,0
Exp/Cntr=0.3,0.1

Type RM Length L Ch R = 1 ,4114    ,582,582,582
BEGIN DESCRIPTION:
LAKE CREEK TRIBUTARY NO. 29 6.0
END DESCRIPTION:
XS GIS Cut Line= 3
      3710117.86     10197161.04      3709972.99     10197903.43
      3709517.84     10198561.09
#Sta/Elev= 30
  4319.6  301.76  4380.8  299.83  4437.6  296.08  4472.5  292.86  4596.5  286.86
  4608.4  285.22  4654.9  283.61  4696.6  283.98  4706.5  284.96  4735.8  284.44
  4748.4  284.87  4788.3  284.12  4918.8  285.07  4992.1  283.98  5032.8  284.09
    5043  285.07  5121.8  283.95  5243.4  284.35  5250.7   283.6  5253.5  282.16
    5260  282.16 5268.27284.3622  5328.5  288.34  5401.5  291.69  5501.4  293.46
  5559.6   293.4  5638.6  296.02  5704.1  296.05  5826.4  300.06  5875.8  300.63
#Mann= 8 ,-1 , 0
  4319.6     .17       0  4437.6     .15       0  4596.5     .17       0
  4735.8     .11       0  4748.4     .15       0  4918.8     .11       0
  5243.4     .06       0 5268.27     .11       0
Bank Sta=5243.4,5268.27
XS Rating Curve= 0 ,0
Exp/Cntr=0.3,0.1

Type RM Length L Ch R = 1 ,3532    ,468,468,468
BEGIN DESCRIPTION:
LAKE CREEK TRIBUTARY NO. 29 5.0
END DESCRIPTION:
XS GIS Cut Line= 3
      3709867.83     10197011.12      3709623.85     10197592.28
       3709530.5     10198297.63
#Sta/Elev= 30
  4369.7  304.81  4423.5  300.89  4455.5  298.06  4478.1   296.9  4484.7  295.66
  4597.4  288.15  4608.3  288.13  4619.8  286.77  4629.9  286.93  4651.6  284.75
  4705.9  283.23  4732.6  283.76  4767.8  284.12  4849.9  283.16  4868.3  283.67
  4873.7  283.08  4955.8  282.22  4974.2  281.57  4976.3  280.95  5005.7  282.11
  5150.1  282.81  5162.6   283.5  5271.1  284.75  5341.7  287.48  5472.9  290.69
  5539.8  293.76  5553.6  293.32  5593.9  295.17  5684.7   297.5  5711.5  297.32
#Mann= 5 ,-1 , 0
  4369.7     .11       0  4423.5     .17       0  4732.6     .11       0
  4955.8     .06       0  5005.7     .11       0
Bank Sta=4955.8,5005.7
XS Rating Curve= 0 ,0
Exp/Cntr=0.3,0.1