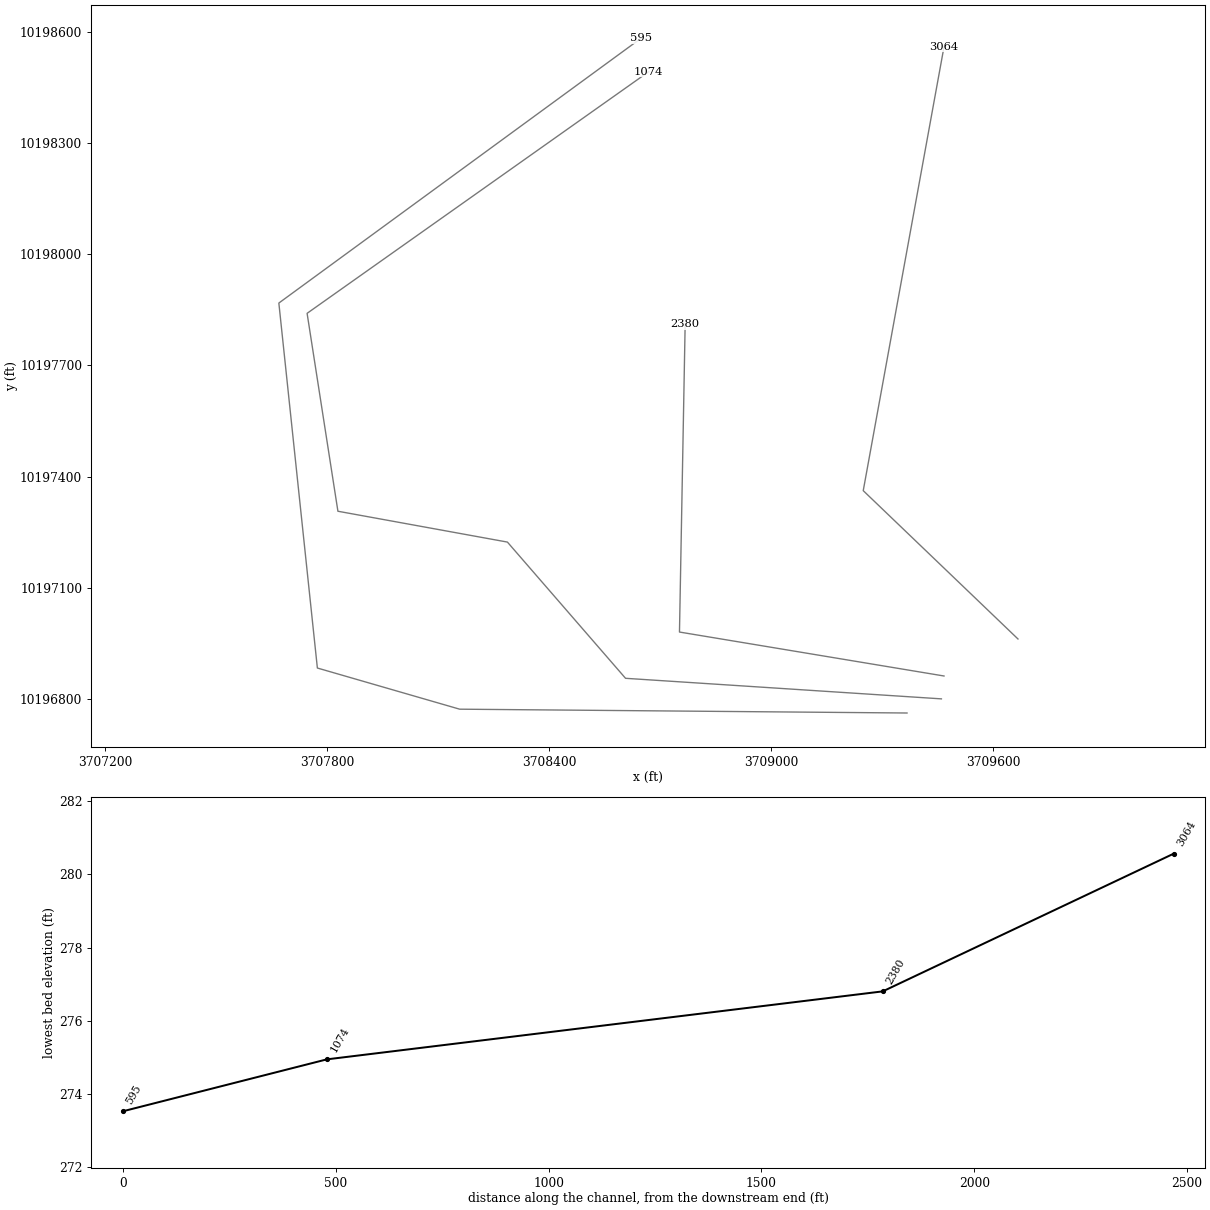
HEC-RAS study LAKE CREEK TRIBUTARY NO 29.prj: LAKE CREEK TRIBUTARY NO 29 Base Level Engineering

--- LAKE CREEK TRIBUTARY NO 29.g01 (geometry) --- (continued)

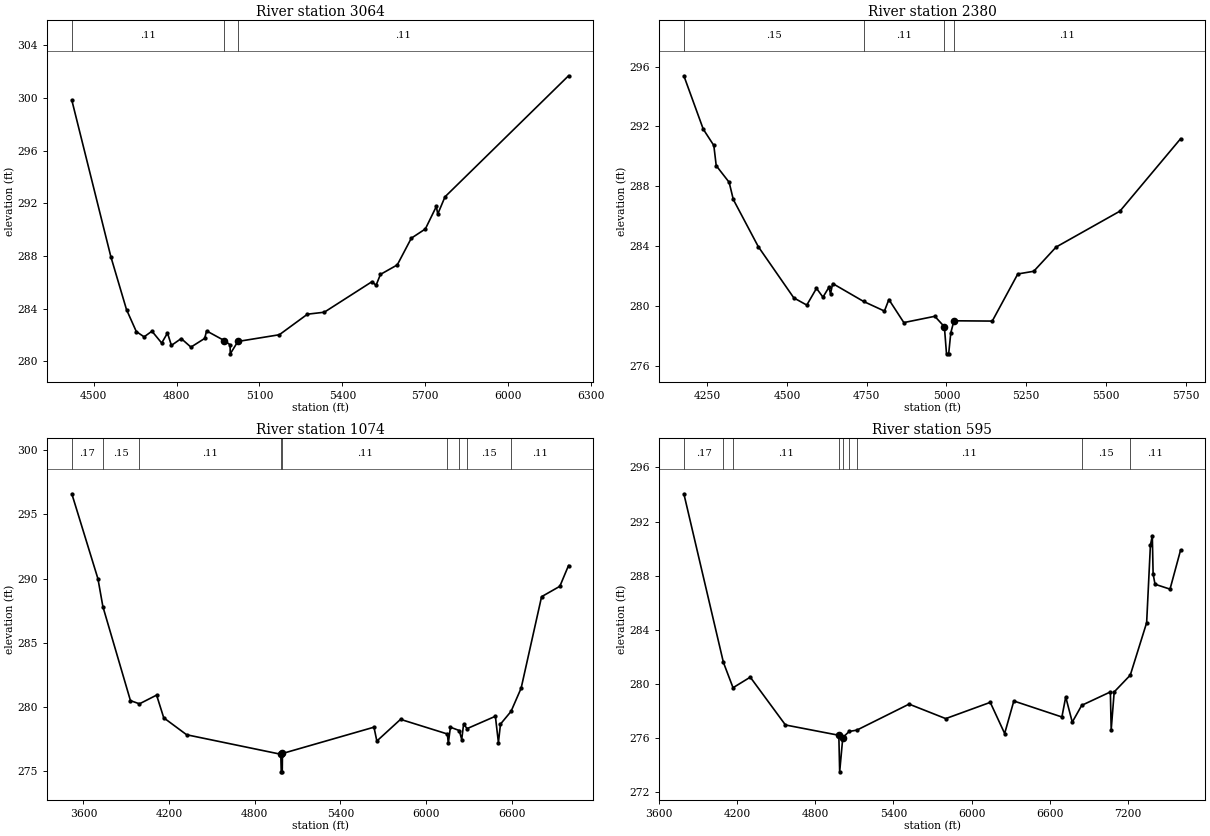
Type RM Length L Ch R = 1 ,3064    ,684,684,684
BEGIN DESCRIPTION:
LAKE CREEK TRIBUTARY NO. 29 4.0
END DESCRIPTION:
XS GIS Cut Line= 3
      3709667.86     10196961.06      3709249.41     10197361.82
      3709467.85     10198561.09
#Sta/Elev= 30
  4420.6  299.83    4562  287.94  4618.6  283.93  4654.1  282.26  4682.4  281.86
  4710.7  282.29    4746  281.39    4767  282.15  4781.2  281.21  4816.7  281.73
  4851.9  281.08  4901.6  281.74  4908.6  282.31  4972.4  281.58  4993.5  281.26
  4994.3  280.57  5021.9  281.51    5172  282.02  5273.7  283.58  5334.7  283.73
  5507.5  286.05  5522.1  285.77    5538   286.6  5598.9  287.32  5649.8  289.35
  5700.6  290.05  5740.4  291.76  5745.5  291.18  5771.7  292.49    6219  301.68
#Mann= 3 , 0 , 0
  4420.6     .11       0  4972.4     .06       0  5021.9     .11       0
Bank Sta=4972.4,5021.9
XS Rating Curve= 0 ,0
Exp/Cntr=0.3,0.1

Type RM Length L Ch R = 1 ,2380    ,1306,1306,1306
BEGIN DESCRIPTION:
LAKE CREEK TRIBUTARY NO. 29 3.0
END DESCRIPTION:
XS GIS Cut Line= 3
      3709467.85     10196861.07       3708752.5     10196979.82
      3708767.85     10197811.05
#Sta/Elev= 30
  4177.2  295.39    4238  291.82  4271.1  290.73  4278.6  289.38  4319.1  288.27
  4332.1  287.12  4410.3  283.97  4521.8  280.54  4562.4  280.06  4592.8  281.18
  4613.1  280.59  4631.7  281.25  4636.8  280.81  4643.5   281.5  4740.6   280.3
  4805.7  279.66  4819.6  280.43  4866.5  278.89  4963.6  279.31  4993.6  278.61
  5000.2   276.8    5007   276.8  5013.6   278.2  5023.6  279.01  5143.6  278.99
  5223.6  282.14  5273.6  282.32  5343.7  283.94  5543.7  286.34  5733.7  291.18
#Mann= 4 ,-1 , 0
  4177.2     .15       0  4740.6     .11       0  4993.6     .06       0
  5023.6     .11       0
Bank Sta=4993.6,5023.6
XS Rating Curve= 0 ,0
Exp/Cntr=0.3,0.1

Type RM Length L Ch R = 1 ,1074    ,479,479,479
BEGIN DESCRIPTION:
LAKE CREEK TRIBUTARY NO. 29 2.0
END DESCRIPTION:
XS GIS Cut Line= 6
      3709460.81     10196799.27      3708606.67     10196854.82
      3708287.23     10197222.88      3707828.89     10197306.21
      3707745.56     10197840.93      3708669.15      10198493.7
#Sta/Elev= 30
  3518.2  296.61  3701.5  289.98  3735.9  287.82  3929.1  280.49  3992.3  280.24
  4112.4  280.92  4162.5  279.15  4322.9  277.83  4982.8  276.31    4986  274.94
    4993  274.94  4994.6  276.37  5635.9  278.42  5656.1  277.34  5822.1  279.03
  6150.3  277.89  6156.9  277.16  6171.6  278.42  6233.3  278.16  6250.9  277.46
  6263.9  278.65    6289  278.31  6486.8  279.27  6508.1  277.22  6522.5  278.66
  6596.5  279.65  6667.3  281.46  6810.6  288.59  6938.6   289.4  6999.5  291.02
#Mann= 9 ,-1 , 0
  3518.2     .17       0  3735.9     .15       0  3992.3     .11       0
  4982.8     .06       0  4994.6     .11       0  6150.3     .15       0
  6233.3     .11       0    6289     .15       0  6596.5     .11       0
Bank Sta=4982.8,4994.6
XS Rating Curve= 0 ,0
Exp/Cntr=0.3,0.1

Type RM Length L Ch R = 1 ,595     ,0,0,0
BEGIN DESCRIPTION:
LAKE CREEK TRIBUTARY NO. 29 1.0
END DESCRIPTION:
XS GIS Cut Line= 5
      3709367.88     10196761.07      3708158.12      10196771.4
      3707773.34      10196882.6      3707669.17     10197868.71
      3708648.32     10198583.98
#Sta/Elev= 30
  3790.2  294.05  4093.9   281.6  4167.8  279.73  4300.2  280.51  4570.3  276.98
  4980.3  276.22  4986.7  273.52  5010.7  276.05  5059.5   276.5  5118.6   276.6
  5519.7  278.52  5801.2  277.45  6143.1  278.65  6253.7  276.35  6324.1  278.75
  6693.3  277.57  6722.7  279.05  6772.9  277.19  6845.5  278.43  7065.6  279.42
  7071.8  276.62  7094.9  279.42  7218.4  280.66  7344.1  284.53    7373  290.25
  7387.6  290.96  7393.8  288.13  7408.5  287.37  7523.6  287.01  7604.7  289.89
#Mann= 9 ,-1 , 0
  3790.2     .17       0  4093.9     .15       0  4167.8     .11       0
  4980.3     .06       0  5010.7     .11       0  5059.5     .15       0
  5118.6     .11       0  6845.5     .15       0  7218.4     .11       0
Bank Sta=4980.3,5010.7
XS Rating Curve= 0 ,0
Exp/Cntr=0.3,0.1

Chan Stop Cuts=-1
Use User Specified Reach Order=0
Composite Channel Slope=5