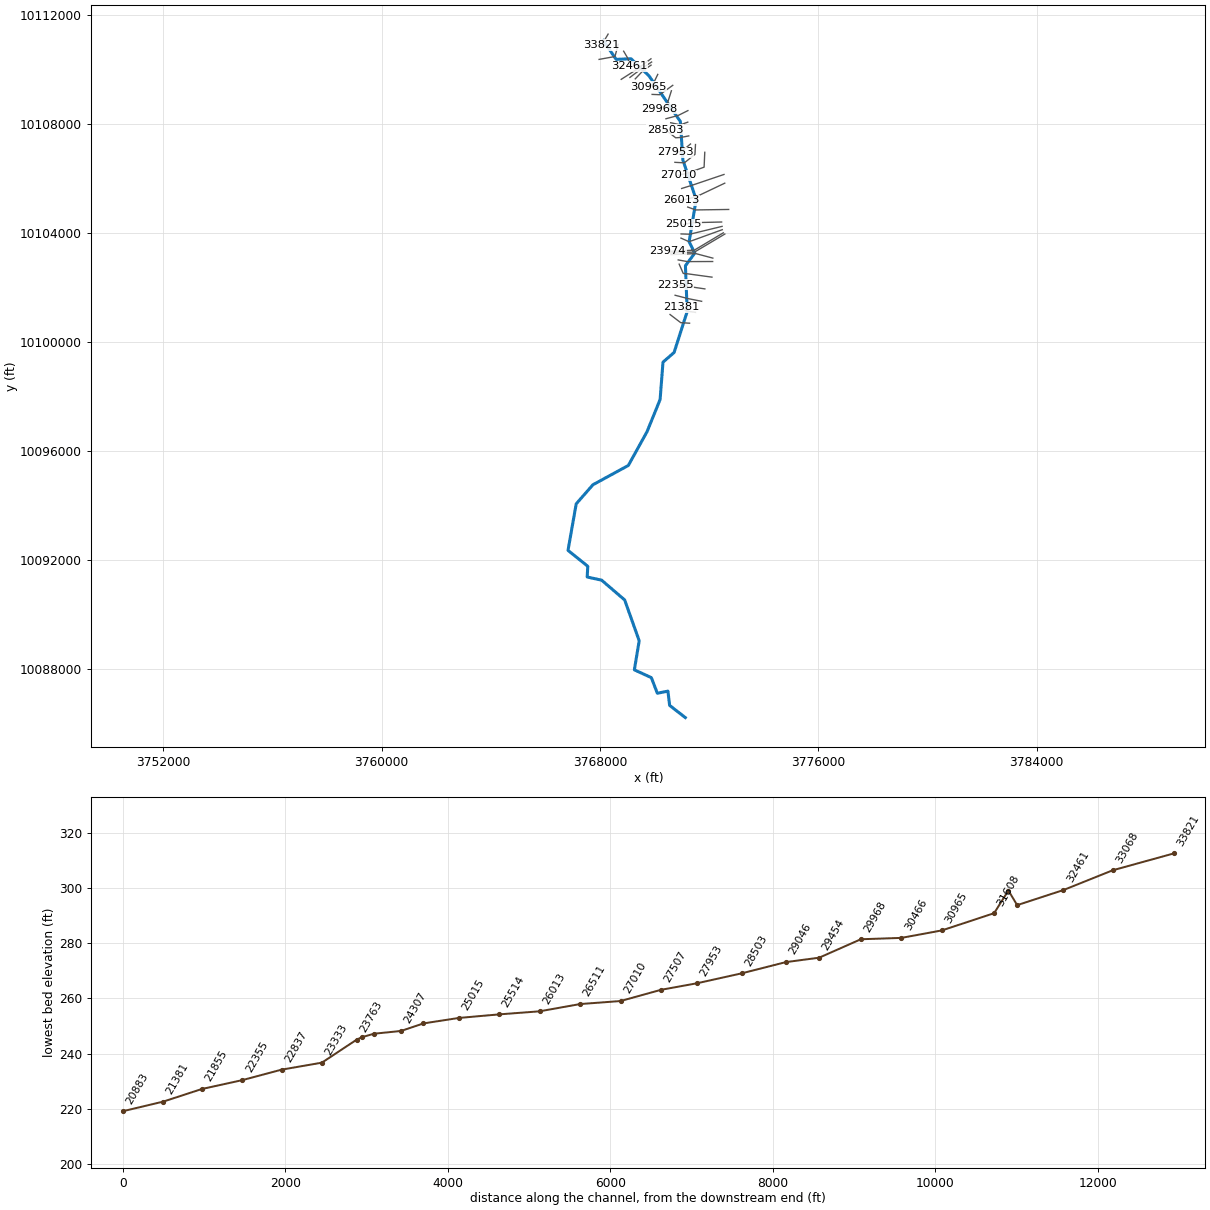
--- LAKE CREEK TRIBUTARY NO 3.prj (project) ---

Proj Title=LAKE CREEK TRIBUTARY NO 3 Base Level Engineering
Current Plan=p01
Default Exp/Contr=0.3,0.1
English Units
Geom File=g01
Flow File=f01
Plan File=p01
Y Axis Title=Elevation
X Axis Title(PF)=Main Channel Distance
X Axis Title(XS)=Station
BEGIN DESCRIPTION:
LAKE CREEK TRIBUTARY NO 3
END DESCRIPTION:
DSS Export Rating Curves= 0
DSS Export Rating Curve Sorted= 0
DSS Export Volume Flow Curves= 0
DXF OffsetX= 0
DXF OffsetY= 0
DXF ScaleX= 1
DXF ScaleY= 10

--- LAKE CREEK TRIBUTARY NO 3.p01 (plan) ---

Plan Title=Multiple Run
Short Identifier=Multiple
Geom File=g01
Flow File=f01
Subcritical Flow
K Sum by GR= 0
Std Step Tol= 0.01
Critical Tol= 0.01
Num of Std Step Trials= 20
Max Error Tol= 0.3
Flow Tol Ratio= 0.001
Split Flow NTrial= 30
Split Flow Tol= 0.02
Split Flow Ratio= 0.02
Log Output Level= 0
Friction Slope Method= 1
Unsteady Friction Slope Method= 2
Unsteady Bridges Friction Slope Method= 1
Parabolic Critical Depth
Global Vel Dist=  1 , 1 , 1
Global Log Level= 0
CheckData=True
Encroach Param= -1, 0, 0, 0
BEGIN DESCRIPTION:
Multiple Run
END DESCRIPTION:

--- LAKE CREEK TRIBUTARY NO 3.f01 (steady flow) ---

Flow Title=Multiple
Program Version=4.10
Number of Profiles= 7
Profile Names=10-year,25-year,50-year,1pct_min,100-year,1pct_plu,500-year
River Rch & RM=LAKE CREEK TRIBU,Reach-1         ,33821
     783    1071    1459     653    1973    5958    3732
River Rch & RM=LAKE CREEK TRIBU,Reach-1         ,26511
    1311    1850    2571    1173    3543   10700    6961
River Rch & RM=LAKE CREEK TRIBU,Reach-1         ,23763
    1311    1850    2571    1173    3543   10700    6961
River Rch & RM=LAKE CREEK TRIBU,Reach-1         ,20383
    1447    2035    2821    1282    3871   11690    7547
River Rch & RM=LAKE CREEK TRIBU,Reach-1         ,12417
    1812    2578    3597    1646    4971   15012    9823
River Rch & RM=LAKE CREEK TRIBU,Reach-1         ,4371
    1690    2379    3298    1498    4524   13662    8812
Boundary for River Rch & Prof#=LAKE CREEK TRIBU,Reach-1         , 1
Up Type= 0
Dn Type= 3
Dn Slope=0.005
Boundary for River Rch & Prof#=LAKE CREEK TRIBU,Reach-1         , 2
Up Type= 0
Dn Type= 3
Dn Slope=0.005
Boundary for River Rch & Prof#=LAKE CREEK TRIBU,Reach-1         , 3
Up Type= 0
Dn Type= 3
Dn Slope=0.005
Boundary for River Rch & Prof#=LAKE CREEK TRIBU,Reach-1         , 4
Up Type= 0
Dn Type= 3
Dn Slope=0.005
Boundary for River Rch & Prof#=LAKE CREEK TRIBU,Reach-1         , 5
Up Type= 0
Dn Type= 3
Dn Slope=0.005
Boundary for River Rch & Prof#=LAKE CREEK TRIBU,Reach-1         , 6
Up Type= 0
Dn Type= 3
Dn Slope=0.005
Boundary for River Rch & Prof#=LAKE CREEK TRIBU,Reach-1         , 7
Up Type= 0
Dn Type= 3
Dn Slope=0.005
DSS Import GetInterval= 0
DSS Import GetPeak= 0
DSS Import FillOption= 0

--- LAKE CREEK TRIBUTARY NO 3.g01 (geometry) ---

Geom Title=Existing Conditions
Program Version=4.10

River Reach=LAKE CREEK TRIBU,Reach-1
Reach XY= 30
      3768123.23     10111051.84       3768592.8     10110362.72
      3769139.04     10110384.18      3769796.69     10109758.48
       3770946.5     10108085.19      3771038.94       10106672.
      3771526.52     10105223.53      3771266.47     10103678.61
      3771475.12     10103262.69      3771131.94     10102798.71
      3771196.73     10101119.37      3770715.93     10099616.85
      3770309.78     10099265.26      3770203.86      10097895.7
      3769725.53     10096716.11      3769038.67     10095477.16
      3767742.02     10094770.17      3767128.92     10094072.02
      3766828.49     10092365.93      3767552.94     10091781.52
      3767531.44     10091389.19      3768059.79     10091273.61
      3768904.58     10090548.86      3769437.65     10089051.96
      3769260.28     10087986.76       3769882.9     10087701.04
      3770102.94     10087128.58      3770490.44     10087205.34
      3770552.31     10086683.59      3771128.23     10086236.84

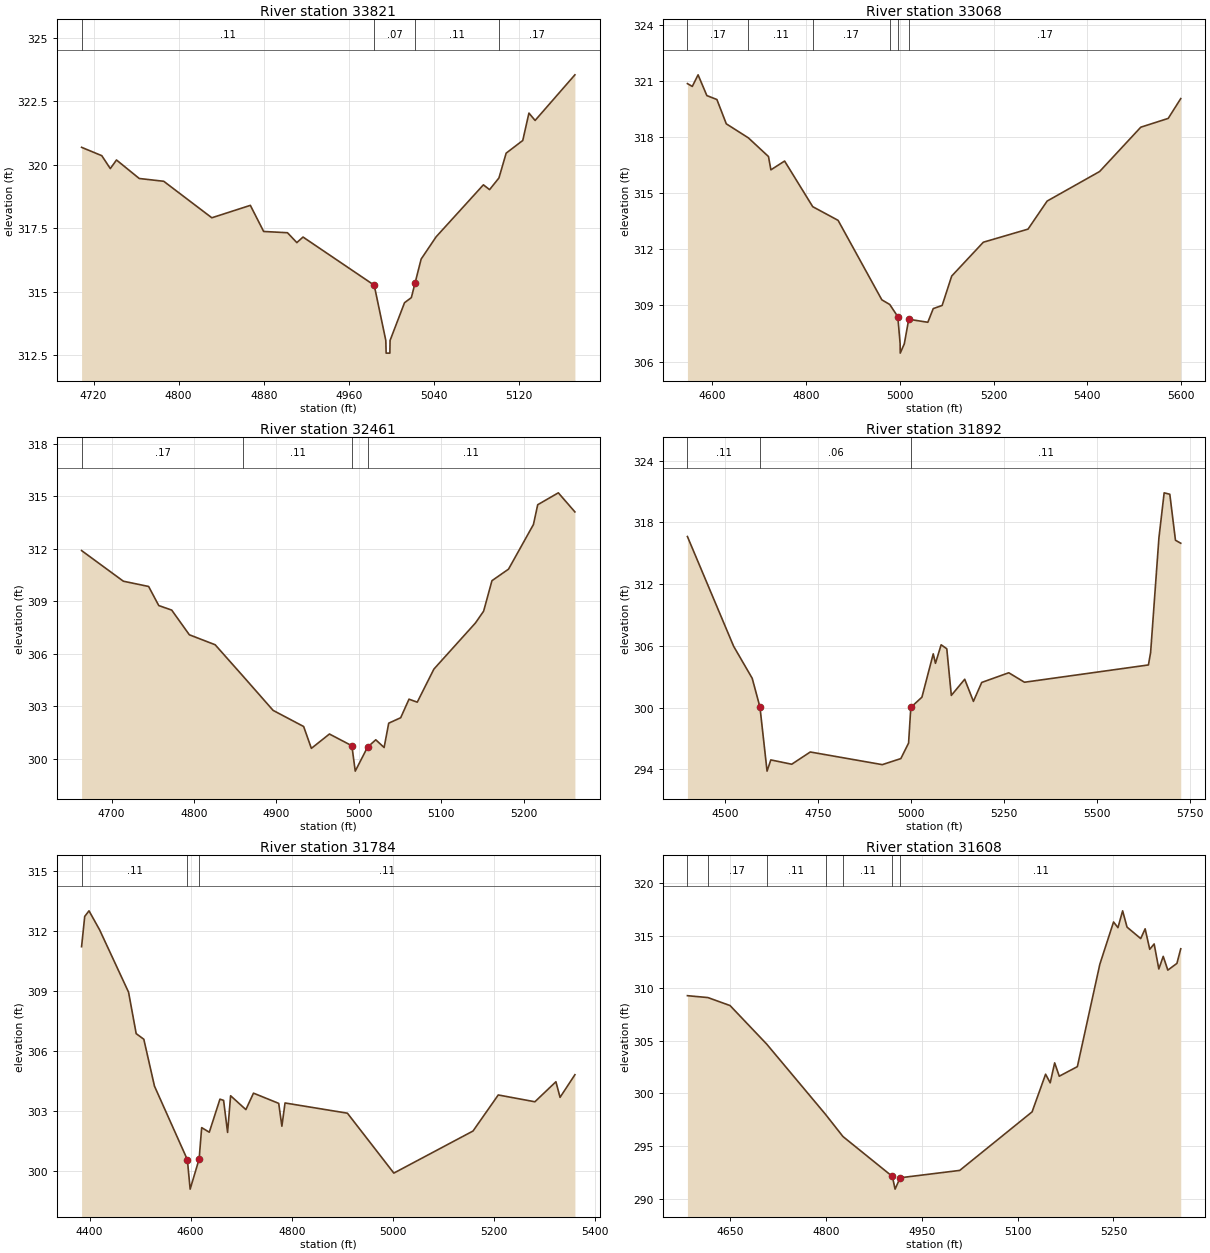
Type RM Length L Ch R = 1 ,33821   ,753,753,753
BEGIN DESCRIPTION:
LAKE CREEK TRIBUTARY NO. 3 63.0
END DESCRIPTION:
XS GIS Cut Line= 2
      3768297.74      10111287.4      3768060.76     10110888.95
#Sta/Elev= 30
  4708.8  320.69  4727.8  320.36  4735.8  319.85  4741.6  320.19    4763  319.46
    4786  319.35  4831.2  317.91  4867.4   318.4  4879.9  317.37  4902.3  317.32
  4911.1  316.93  4916.9  317.15  4983.8  315.25  4994.7  313.07    4995  312.57
  4998.5  312.57  4998.7  313.07  5012.3  314.56  5018.7  314.76  5022.2315.3383
  5027.9  316.28    5042  317.16  5086.4  319.21  5092.2  319.02    5101  319.48
  5107.8  320.46  5123.4  320.96  5129.2  322.04    5135  321.75  5172.4  323.55
#Mann= 4 ,-1 , 0
  4708.8     .11       0  4983.8     .07       0  5022.2     .11       0
    5101     .17       0
Bank Sta=4983.8,5022.2
XS Rating Curve= 0 ,0
Exp/Cntr=0.3,0.1

Type RM Length L Ch R = 1 ,33068   ,607,607,607
BEGIN DESCRIPTION:
LAKE CREEK TRIBUTARY NO. 3 62.0
END DESCRIPTION:
XS GIS Cut Line= 3
      3768667.86     10110911.11      3768549.24     10110466.83
      3767967.82     10110361.07
#Sta/Elev= 30
    4548  320.86  4558.4  320.71  4570.7  321.33  4589.4  320.22  4610.8  320.01
  4630.8  318.71  4677.8  317.96  4720.7  316.96  4725.8  316.25    4755  316.72
  4814.9  314.28  4868.9  313.55  4962.1   309.3    4979  309.05  4996.1   308.4
  5001.1  306.95  5001.3  306.45    5010  306.95  5019.4  308.26  5060.1   308.1
  5071.6  308.83  5090.6     309  5110.9  310.57  5178.3  312.38  5273.5  313.08
  5314.2  314.58    5426  316.16  5513.7  318.53  5572.1     319  5598.8  320.06
#Mann= 6 ,-1 , 0
    4548     .17       0  4677.8     .11       0  4814.9     .17       0
    4979     .11       0  4996.1     .07       0  5019.4     .17       0
Bank Sta=4996.1,5019.4
XS Rating Curve= 0 ,0
Exp/Cntr=0.3,0.1

Type RM Length L Ch R = 1 ,32461   ,569,569,569
BEGIN DESCRIPTION:
LAKE CREEK TRIBUTARY NO. 3 61.0
END DESCRIPTION:
XS GIS Cut Line= 3
      3768867.84      10110661.1      3769038.78     10110371.48
      3769067.85      10110111.1
#Sta/Elev= 30
  4663.7  311.89  4714.4  310.14    4745  309.84  4757.3  308.75    4773  308.49
  4794.4  307.08  4825.7  306.51  4859.8   304.7    4896  302.76    4933  301.84
  4942.4  300.59  4964.3  301.41  4991.5  300.74  4995.6  299.29  5010.5  300.66
  5020.5  301.08  5030.6  300.64  5036.2  302.03  5050.7  302.34  5060.8   303.4
  5070.8  303.23    5091  305.12  5141.3  307.75  5151.3  308.43  5161.4  310.17
  5181.5  310.83  5211.7  313.38  5216.9  314.51  5241.9  315.19    5262   314.1
#Mann= 4 ,-1 , 0
  4663.7     .17       0  4859.8     .11       0  4991.5     .06       0
  5010.5     .11       0
Bank Sta=4991.5,5010.5
XS Rating Curve= 0 ,0
Exp/Cntr=0.3,0.1

Type RM Length L Ch R = 1 ,31892   ,108,108,108
BEGIN DESCRIPTION:
LAKE CREEK TRIBUTARY NO. 3 60.0
END DESCRIPTION:
XS GIS Cut Line= 3
      3769868.66     10110383.48      3769386.05     10110018.92
      3768778.38     10109630.01
#Sta/Elev= 30
    4398  316.62  4522.3  305.95  4572.2  302.84    4593  300.04  4612.1  293.82
  4622.2  294.91  4678.4  294.49  4728.3  295.68  4921.9  294.45  4971.8  295.04
  4992.6  296.55  4998.6  300.01  5028.5  301.01  5058.9  305.22  5064.9   304.3
  5080.1   306.1  5095.3  305.71  5107.5  301.18  5143.5  302.75  5166.9   300.6
  5189.2  302.44  5261.9  303.38  5304.2  302.46  5637.4  304.14  5643.3  305.35
  5665.6  316.48  5679.7  320.87  5694.9  320.73  5710.1  316.26  5724.3  315.97
#Mann= 3 , 0 , 0
    4398     .11       0    4593     .06       0  4998.6     .11       0
Bank Sta=4593,4998.6
XS Rating Curve= 0 ,0
Exp/Cntr=0.3,0.1

Type RM Length L Ch R = 1 ,31784   ,176,176,176
BEGIN DESCRIPTION:
Mapping XS 3613160b
END DESCRIPTION:
XS GIS Cut Line= 4
      3769893.03     10110265.47      3769601.32     10110074.47
      3769250.63     10109817.53      3769097.85     10109699.47
#Sta/Elev= 30
  4384.1  311.22  4390.3  312.73  4398.8  313.01  4419.8  312.06  4477.1  308.95
  4492.2  306.88  4507.3   306.6  4528.4  304.26  4593.5  300.59    4599  299.12
  4616.8300.6222  4621.8  302.19  4636.9  301.96    4658  303.61  4665.2  303.55
  4673.1  301.95  4679.1  303.78  4709.3  303.09  4724.4  303.91  4774.3   303.4
  4780.6  302.26  4786.8  303.42  4910.3  302.91  5002.2  299.92  5158.9  302.02
  5208.9  303.82  5281.4  303.48    5323  304.48  5331.2   303.7  5360.6  304.83
#Mann= 3 , 0 , 0
  4384.1     .11       0  4593.5     .06       0  4616.8     .11       0
Bank Sta=4593.5,4616.8
XS Rating Curve= 0 ,0
Exp/Cntr=0.3,0.1

Type RM Length L Ch R = 1 ,31608   ,643,643,643
BEGIN DESCRIPTION:
LAKE CREEK TRIBUTARY NO. 3 59.0
END DESCRIPTION:
XS GIS Cut Line= 3
      3769872.13     10110150.84      3769583.96     10109952.95
      3769292.57     10109647.67
#Sta/Elev= 30
  4583.6   309.3  4615.6  309.12  4650.3  308.36  4707.5   304.7  4799.6  298.01
  4826.9   295.9  4904.1  292.11  4908.4   290.9  4916.3  291.98  5009.5  292.68
  5122.7  298.25  5143.8  301.83    5151  301.01    5158  302.91  5165.2  301.64
  5193.5  302.55  5228.7   312.3  5250.1  316.31    5257  315.77  5264.3  317.37
  5271.2  315.82  5292.6  314.73  5299.5  315.66  5306.7  313.71  5313.6  314.22
  5320.9  311.84  5327.8  313.04    5335  311.73  5349.2  312.37  5355.2  313.76
#Mann= 7 ,-1 , 0
  4583.6     .11       0  4615.6     .17       0  4707.5     .11       0
  4799.6     .17       0  4826.9     .11       0  4904.1     .06       0
  4916.3     .11       0
Bank Sta=4904.1,4916.3
XS Rating Curve= 0 ,0
Exp/Cntr=0.3,0.1

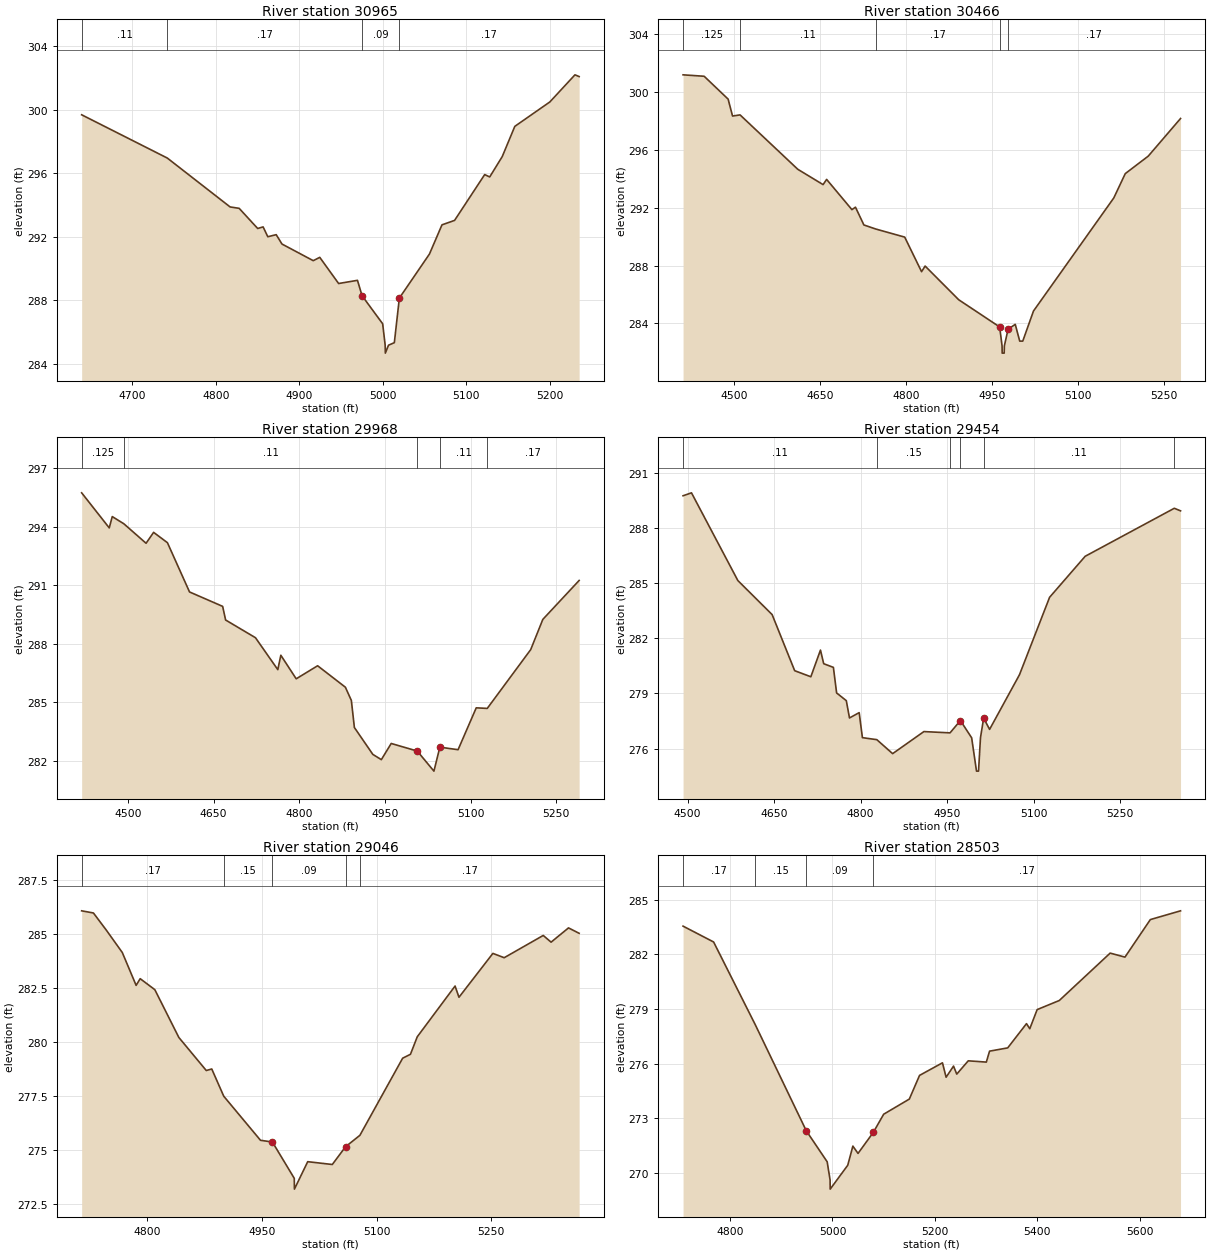
Type RM Length L Ch R = 1 ,30965   ,499,499,499
BEGIN DESCRIPTION:
LAKE CREEK TRIBUTARY NO. 3 58.0
END DESCRIPTION:
XS GIS Cut Line= 3
      3770117.85     10109811.07      3769961.02     10109486.14
       3769764.8     10109355.91
#Sta/Elev= 30
  4639.2  299.69  4741.9  296.96  4817.1  293.88    4828  293.79  4850.2  292.52
  4856.7  292.62  4862.3     292  4872.4  292.13  4879.3  291.54  4916.8  290.49
  4924.6   290.7  4947.2  289.05  4969.8  289.25  4975.3  288.28    5000  286.51
    5003  285.16  5003.2  284.66    5007  285.16    5014  285.32    5020  288.13
  5056.1  290.91  5071.1  292.75  5086.2  293.03  5122.3  295.92  5128.3  295.77
  5143.3  297.05  5158.4  298.96  5200.4   300.5  5230.5  302.21  5235.5   302.1
#Mann= 4 ,-1 , 0
  4639.2     .11       0  4741.9     .17       0  4975.3     .09       0
    5020     .17       0
Bank Sta=4975.3,5020
XS Rating Curve= 0 ,0
Exp/Cntr=0.3,0.1

Type RM Length L Ch R = 1 ,30466   ,498,498,498
BEGIN DESCRIPTION:
LAKE CREEK TRIBUTARY NO. 3 57.0
END DESCRIPTION:
XS GIS Cut Line= 3
      3770667.89      10109411.1      3770190.25      10109066.8
      3769911.57      10109077.9
#Sta/Elev= 30
  4411.2  301.19    4448  301.09  4489.8  299.51  4497.5  298.34  4510.6  298.42
  4611.3  294.66  4655.4   293.6  4661.6  293.96  4705.7  291.87  4711.9  292.04
  4726.6  290.81  4747.3  290.53  4797.8  289.97  4827.2  287.58  4833.4  287.97
    4892  285.64  4963.4  283.76  4967.6  282.45  4967.8  281.95  4971.3  281.95
  4971.6  282.45  4978.1   283.6  4990.6  283.94  4998.4  282.78  5003.7  282.78
  5022.4  284.86  5162.5  292.68  5182.5  294.36  5222.6  295.57  5278.9  298.17
#Mann= 5 ,-1 , 0
  4411.2    .125       0  4510.6     .11       0  4747.3     .17       0
  4963.4     .09       0  4978.1     .17       0
Bank Sta=4963.4,4978.1
XS Rating Curve= 0 ,0
Exp/Cntr=0.3,0.1

Type RM Length L Ch R = 1 ,29968   ,514,514,514
BEGIN DESCRIPTION:
LAKE CREEK TRIBUTARY NO. 3 56.0
END DESCRIPTION:
XS GIS Cut Line= 3
      3770617.86     10109211.09      3770441.48     10108657.41
      3770167.84     10108561.07
#Sta/Elev= 30
  4418.9  295.75  4467.2  293.95  4472.5  294.53  4492.8  294.16  4531.7  293.16
  4544.9  293.72  4569.1  293.19  4607.8  290.66  4665.8  289.92    4671  289.22
  4723.3  288.31  4762.4  286.67  4767.7  287.41  4794.6   286.2  4832.1  286.87
  4880.7  285.77  4891.2  285.09  4896.5   283.7  4928.8  282.32  4943.7  282.05
    4961  282.88  5006.6  282.49  5035.8  281.46  5046.2  282.69  5078.1  282.56
  5109.9  284.71  5129.2  284.68  5205.3   287.7  5226.5  289.25  5290.1  291.25
#Mann= 5 ,-1 , 0
  4418.9    .125       0  4492.8     .11       0  5006.6     .07       0
  5046.2     .11       0  5129.2     .17       0
Bank Sta=5006.6,5046.2
XS Rating Curve= 0 ,0
Exp/Cntr=0.3,0.1

Type RM Length L Ch R = 1 ,29454   ,408,408,408
BEGIN DESCRIPTION:
LAKE CREEK TRIBUTARY NO. 3 55.0
END DESCRIPTION:
XS GIS Cut Line= 3
      3771222.81     10108484.17      3770868.69     10108307.11
      3770418.25     10108185.84
#Sta/Elev= 30
  4492.3  289.74  4506.9   289.9  4587.3  285.13  4646.7  283.28  4685.8  280.23
  4713.8   279.9  4730.5  281.35  4736.1  280.61  4752.9  280.41  4758.5  279.02
  4775.3   278.6  4780.8  277.66  4797.6  277.95  4803.2  276.59  4828.2  276.48
  4855.6  275.72  4909.8  276.92  4955.1  276.85  4973.1  277.52  4992.6  276.58
    5001  274.77  5004.5  274.77  5007.9  276.59  5013.4  277.65  5023.7  277.04
  5075.5  280.01  5127.7  284.22  5189.4  286.45  5343.9  289.06  5354.7  288.92
#Mann= 6 ,-1 , 0
  4492.3     .11       0  4828.2     .15       0  4955.1     .11       0
  4973.1     .07       0  5013.4     .11       0  5343.9     .17       0
Bank Sta=4973.1,5013.4
XS Rating Curve= 0 ,0
Exp/Cntr=0.3,0.1

Type RM Length L Ch R = 1 ,29046   ,543,543,543
BEGIN DESCRIPTION:
LAKE CREEK TRIBUTARY NO. 3 54.0
END DESCRIPTION:
XS GIS Cut Line= 3
       3771217.9     10108061.09      3770948.55     10107963.36
      3770591.92     10108039.53
#Sta/Elev= 30
  4713.9  286.06  4729.3  285.96  4745.9  285.18  4767.1  284.13  4785.2  282.61
  4790.5  282.92  4809.7  282.41  4841.1   280.2    4877  278.67  4884.2  278.74
  4899.9  277.48    4948  275.44  4963.6  275.36  4992.2  273.68  4992.4  273.18
  5009.8  274.45    5042  274.32  5059.3  275.14  5078.1  275.67  5134.1  279.24
  5144.3  279.42  5153.2  280.23  5202.7  282.58  5207.8  282.06  5252.2  284.09
    5267  283.89  5318.1  284.92  5328.4  284.61  5351.2  285.27  5365.1  285.02
#Mann= 5 ,-1 , 0
  4713.9     .17       0  4899.9     .15       0  4963.6     .09       0
  5059.3     .15       0  5078.1     .17       0
Bank Sta=4963.6,5059.3
XS Rating Curve= 0 ,0
Exp/Cntr=0.3,0.1

Type RM Length L Ch R = 1 ,28503   ,550,550,550
BEGIN DESCRIPTION:
LAKE CREEK TRIBUTARY NO. 3 53.0
END DESCRIPTION:
XS GIS Cut Line= 4
      3771254.09     10107557.11      3770967.71     10107500.61
      3770774.94     10107487.67      3770392.97     10107789.77
#Sta/Elev= 30
  4708.1  283.55  4767.8  282.68  4849.4  278.13  4948.9  272.32  4989.7  270.62
  4995.4  269.62  4995.6  269.12  5029.9  270.43  5039.9  271.48    5050  271.08
    5080  272.24  5100.1  273.23  5150.2  274.06  5170.2  275.36    5215  276.05
  5222.1  275.26  5236.6  275.87  5242.9  275.43  5265.4  276.16  5300.7  276.09
    5307  276.69  5342.5  276.87  5379.2   278.2  5385.6  277.92    5400  278.97
  5443.3  279.47  5542.7  282.07  5571.6  281.85  5621.2  283.91  5680.2  284.39
#Mann= 4 ,-1 , 0
  4708.1     .17       0  4849.4     .15       0  4948.9     .09       0
    5080     .17       0
Bank Sta=4948.9,5080
XS Rating Curve= 0 ,0
Exp/Cntr=0.3,0.1

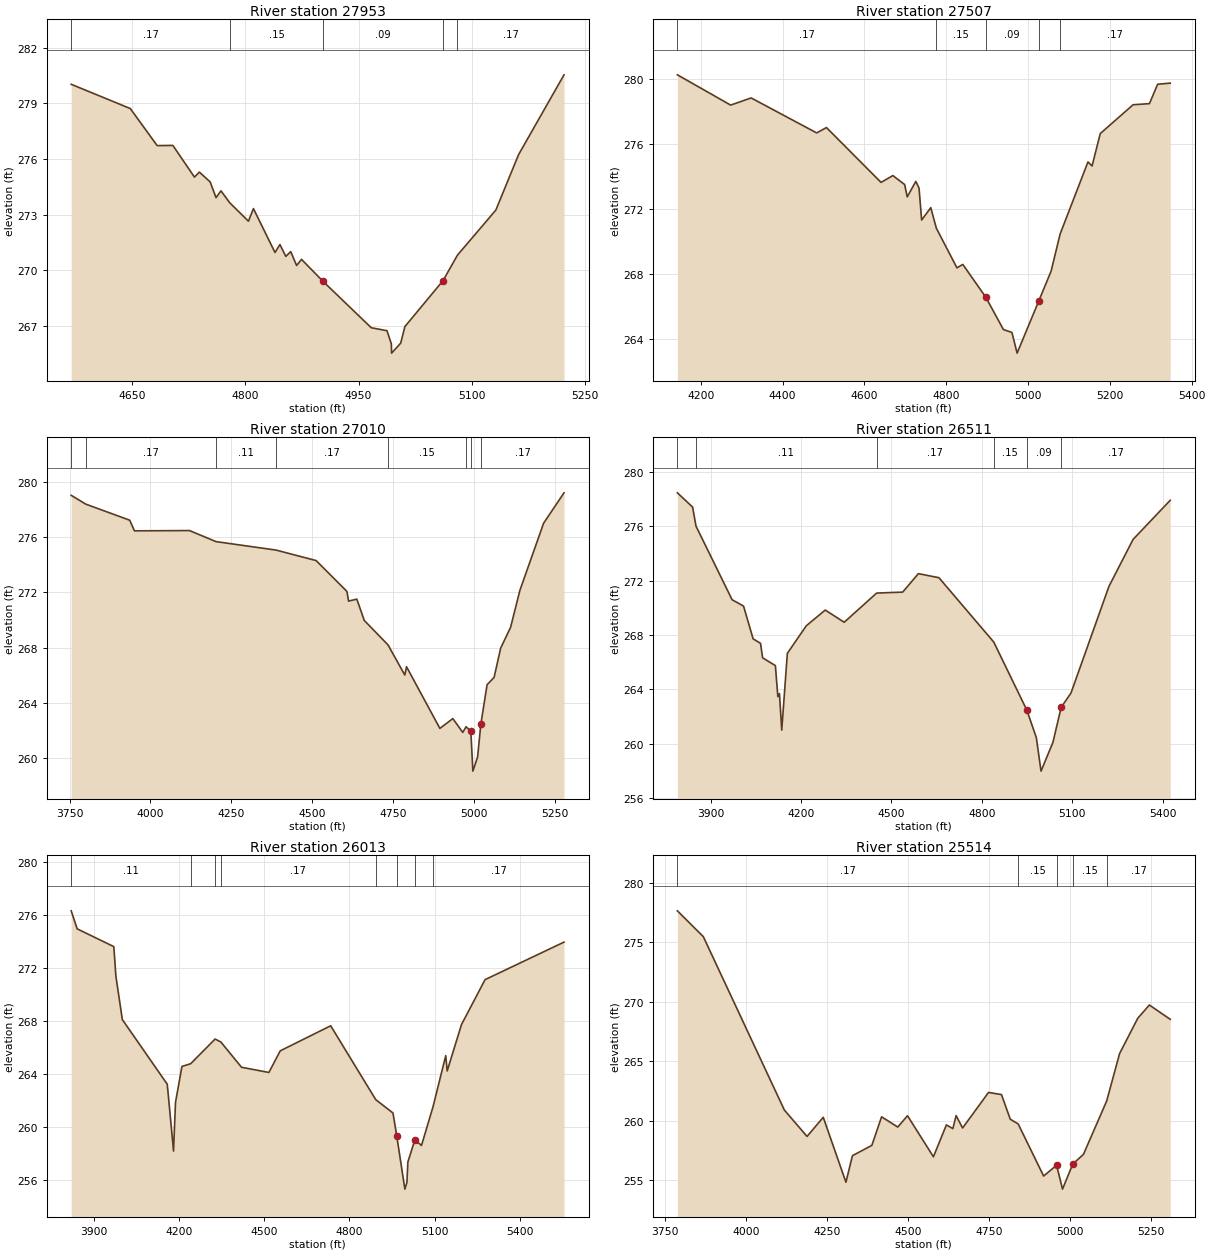
Type RM Length L Ch R = 1 ,27953   ,446,446,446
BEGIN DESCRIPTION:
LAKE CREEK TRIBUTARY NO. 3 52.0
END DESCRIPTION:
XS GIS Cut Line= 3
      3771317.87     10107261.08      3770983.27     10106980.72
      3770767.89     10106961.08
#Sta/Elev= 30
  4569.4  280.03  4647.7  278.72  4683.3  276.72  4704.1  276.73  4732.7  275.02
  4739.2  275.29  4753.5  274.76  4761.3  273.91  4767.8  274.28  4779.3  273.64
  4804.2  272.64  4810.8  273.32  4839.4  270.95  4845.9  271.38  4853.7  270.74
  4860.2     271    4868  270.25  4874.5  270.58  4903.1  269.39  4966.9  266.89
  4987.7  266.73  4993.5  266.02  4993.8  265.52  5005.9  266.06  5011.4  266.95
  5061.9  269.43  5081.1  270.81  5131.9  273.24    5162  276.23  5222.2  280.54
#Mann= 5 ,-1 , 0
  4569.4     .17       0  4779.3     .15       0  4903.1     .09       0
  5061.9     .15       0  5081.1     .17       0
Bank Sta=4903.1,5061.9
XS Rating Curve= 0 ,0
Exp/Cntr=0.3,0.1

Type RM Length L Ch R = 1 ,27507   ,497,497,497
BEGIN DESCRIPTION:
LAKE CREEK TRIBUTARY NO. 3 51.0
END DESCRIPTION:
XS GIS Cut Line= 4
      3771500.63     10107241.09       3771481.3     10106881.63
      3771094.24     10106569.85      3770747.13     10106588.36
#Sta/Elev= 30
    4143  280.23  4273.2  278.37  4323.3  278.81  4483.5  276.66  4507.4  276.99
  4640.8  273.62  4669.6  274.04  4698.4  273.49  4704.8  272.73  4725.7  273.68
  4733.6  273.28    4740  271.31  4762.4  272.07  4775.9  270.81  4826.3  268.37
  4840.7  268.58  4896.7  266.57  4939.9  264.58  4960.7   264.4  4973.4  263.13
  5026.4  266.34  5056.5  268.17  5078.5  270.45  5146.6  274.88  5156.6  274.63
  5176.6  276.62  5256.8  278.39  5296.8  278.46  5316.8  279.65  5347.6  279.72
#Mann= 5 ,-1 , 0
    4143     .17       0  4775.9     .15       0  4896.7     .09       0
  5026.4     .15       0  5078.5     .17       0
Bank Sta=4896.7,5026.4
XS Rating Curve= 0 ,0
Exp/Cntr=0.3,0.1

Type RM Length L Ch R = 1 ,27010   ,499,499,499
BEGIN DESCRIPTION:
LAKE CREEK TRIBUTARY NO. 3 50.0
END DESCRIPTION:
XS GIS Cut Line= 4
      3771840.91     10106956.45      3771816.63     10106411.19
      3771158.68     10106174.89      3770886.03     10106119.61
#Sta/Elev= 30
  3755.1  279.02  3800.4  278.38    3936  277.22  3950.7  276.45  4120.8  276.47
  4202.8  275.67    4388  275.06  4512.1   274.3  4607.2  272.07  4612.5  271.37
  4637.9  271.51  4660.9  269.97  4734.3   268.2  4786.2  266.02  4791.5  266.62
  4894.6  262.16  4934.6  262.87  4965.3  261.87  4975.5  262.28  4990.3  261.95
  4996.5  259.07  5011.1  260.09  5021.3  262.49  5040.5  265.32  5062.1  265.85
  5082.5  267.97  5113.1  269.47  5141.8  272.14  5215.1     277  5278.2   279.2
#Mann= 8 ,-1 , 0
  3755.1     .11       0  3800.4     .17       0  4202.8     .11       0
    4388     .17       0  4734.3     .15       0  4975.5     .17       0
  4990.3     .09       0  5021.3     .17       0
Bank Sta=4990.3,5021.3
XS Rating Curve= 0 ,0
Exp/Cntr=0.3,0.1

Type RM Length L Ch R = 1 ,26511   ,498,498,498
BEGIN DESCRIPTION:
LAKE CREEK TRIBUTARY NO. 3 49.0
END DESCRIPTION:
XS GIS Cut Line= 3
      3772545.76     10106143.91      3771399.36     10105755.85
      3770993.72     10105630.04
#Sta/Elev= 30
  3789.7  278.46  3840.2  277.41  3851.4  276.01  3971.2  270.59  4009.2  270.12
  4040.9  267.71  4065.5  267.38  4072.5  266.31  4114.8  265.74    4123  263.45
  4128.3  263.68  4135.9  260.99  4154.5  266.64  4217.3  268.67  4280.2  269.83
  4343.1  268.93  4450.8  271.08  4537.1  271.15  4589.2  272.51  4657.4  272.21
  4839.4  267.47  4948.8  262.47  4980.5  260.44  4996.1  257.97  5035.6  260.09
    5063  262.67  5095.5  263.72  5221.4  271.57  5301.5  275.03  5424.7  277.91
#Mann= 6 ,-1 , 0
  3789.7    .125       0  3851.4     .11       0  4450.8     .17       0
  4839.4     .15       0  4948.8     .09       0    5063     .17       0
Bank Sta=4948.8,5063
XS Rating Curve= 0 ,0
Exp/Cntr=0.3,0.1

Type RM Length L Ch R = 1 ,26013   ,499,499,499
BEGIN DESCRIPTION:
LAKE CREEK TRIBUTARY NO. 3 48.0
END DESCRIPTION:
XS GIS Cut Line= 3
      3772573.51     10105824.46      3771507.67     10105317.66
      3770965.93     10105192.53
#Sta/Elev= 30
  3819.8  276.33    3841  274.97    3970  273.63  3977.3  271.41    4000  268.13
  4158.3  263.25  4180.4  258.21  4187.3  261.88    4210  264.59  4240.8   264.8
  4326.8  266.66    4347  266.44    4420  264.53  4516.4  264.14  4556.3  265.77
    4734  267.66  4892.8  262.09  4953.5  261.08  4966.6  259.38  4995.4  255.34
  5002.5  255.84    5006  257.39  5030.6  259.06  5053.9  258.63  5094.4  261.54
  5139.4  265.41  5144.5  264.25  5194.8  267.75  5277.9  271.14    5556  273.97
#Mann= 8 ,-1 , 0
  3819.8     .11       0  4240.8     .17       0  4326.8     .11       0
    4347     .17       0  4892.8     .15       0  4966.6     .09       0
  5030.6     .15       0  5094.4     .17       0
Bank Sta=4966.6,5030.6
XS Rating Curve= 0 ,0
Exp/Cntr=0.3,0.1

Type RM Length L Ch R = 1 ,25514   ,499,499,499
BEGIN DESCRIPTION:
LAKE CREEK TRIBUTARY NO. 3 47.0
END DESCRIPTION:
XS GIS Cut Line= 3
      3772717.88     10104861.07      3771506.91     10104843.42
      3771215.93     10104949.46
#Sta/Elev= 30
  3788.9  277.63  3868.9  275.46    4119  260.88    4189  258.66    4239  260.27
    4309  254.81    4329  257.04    4389  257.91    4419  260.31    4469  259.45
    4499   260.4    4579  256.95    4619  259.63    4639  259.32    4649  260.41
    4669  259.37    4749  262.36    4789  262.18  4816.1  260.11  4840.5  259.71
  4919.1  255.33  4959.1  256.24  4977.3  254.23  5009.1256.3447  5041.9  257.15
  5113.5  261.63  5153.5  265.63  5209.4  268.59  5245.3  269.71  5309.7  268.51
#Mann= 5 ,-1 , 0
  3788.9     .17       0  4840.5     .15       0  4959.1     .09       0
  5009.1     .15       0  5113.5     .17       0
Bank Sta=4959.1,5009.1
XS Rating Curve= 0 ,0
Exp/Cntr=0.3,0.1

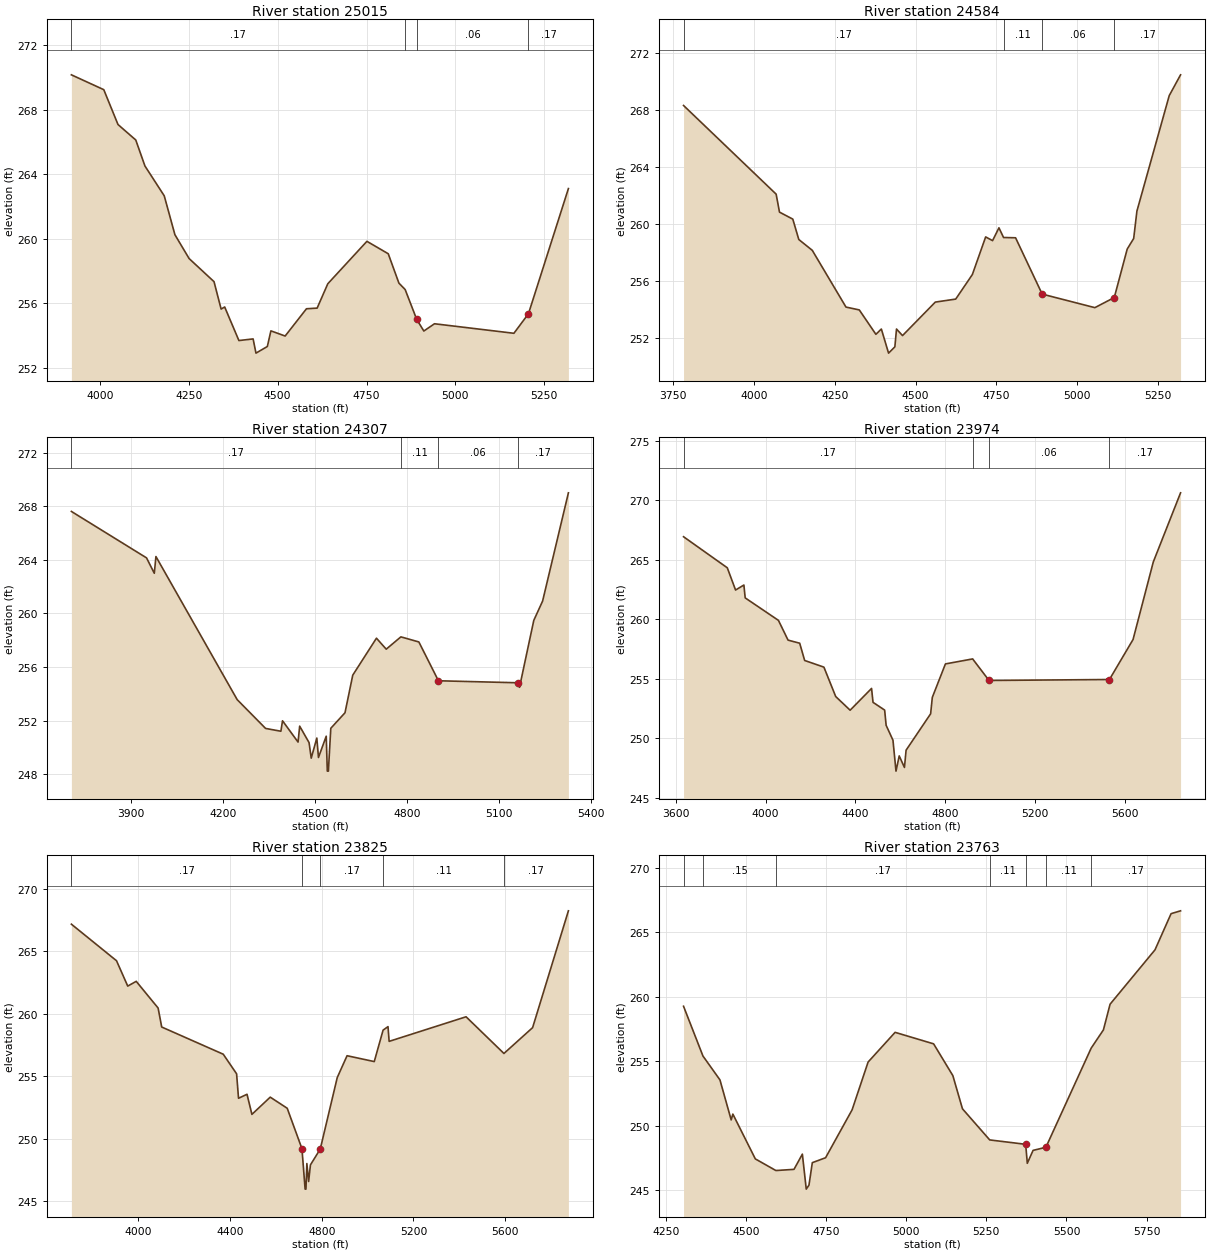
Type RM Length L Ch R = 1 ,25015   ,431,431,431
BEGIN DESCRIPTION:
LAKE CREEK TRIBUTARY NO. 3 46.0
END DESCRIPTION:
XS GIS Cut Line= 3
      3772458.94     10104400.86      3771379.03     10104375.95
      3771067.82     10104311.07
#Sta/Elev= 30
  3919.8  270.17  4010.9  269.25  4050.9  267.09  4100.9  266.13  4126.7  264.52
    4181  262.67    4211  260.26    4251  258.78    4321  257.35    4341  255.65
    4351  255.78    4391   253.7    4431   253.8    4439  252.92    4471  253.33
    4481   254.3  4521.1  253.98  4581.1  255.67  4611.1  255.71  4641.1  257.22
  4751.1  259.85  4811.1  259.08  4841.1  257.26  4858.7  256.86  4891.2  255.01
  4911.2  254.29  4941.2  254.74  5164.6  254.15  5205.5  255.36  5317.9  263.12
#Mann= 4 ,-1 , 0
  3919.8     .17       0  4858.7     .11       0  4891.2     .06       0
  5205.5     .17       0
Bank Sta=4891.2,5205.5
XS Rating Curve= 0 ,0
Exp/Cntr=0.3,0.1

Type RM Length L Ch R = 1 ,24584   ,277,277,277
BEGIN DESCRIPTION:
LAKE CREEK TRIBUTARY NO. 3 45.0
END DESCRIPTION:
XS GIS Cut Line= 3
      3772476.32     10104241.14      3771292.55     10103953.16
      3770972.81     10103963.36
#Sta/Elev= 30
  3781.7  268.33  4068.3  262.11  4078.6  260.85  4119.8  260.36  4138.4  258.93
  4180.1  258.17  4284.4  254.19  4325.6  253.99    4377  252.28  4393.9  252.65
  4416.2  250.96  4435.7   251.4  4440.8  252.65  4459.4  252.19  4560.9  254.54
    4624  254.75  4675.5  256.47  4716.7  259.11  4738.1  258.85  4757.8  259.75
  4772.1  259.07  4809.3  259.05  4891.6   255.1  5054.7  254.15  5114.8  254.86
  5154.8  258.26  5174.8     259  5184.8  260.92  5284.8  269.02  5319.9  270.48
#Mann= 4 ,-1 , 0
  3781.7     .17       0  4772.1     .11       0  4891.6     .06       0
  5114.8     .17       0
Bank Sta=4891.6,5114.8
XS Rating Curve= 0 ,0
Exp/Cntr=0.3,0.1

Type RM Length L Ch R = 1 ,24307   ,333,333,333
BEGIN DESCRIPTION:
LAKE CREEK TRIBUTARY NO. 3 44.0
END DESCRIPTION:
XS GIS Cut Line= 3
      3772483.22      10104119.6      3771266.47     10103678.61
      3770967.83     10103811.08
#Sta/Elev= 30
  3705.8  267.62  3950.9  264.15  3976.2     263  3981.5  264.25  4246.5  253.56
  4339.1  251.41    4389   251.2  4394.4  251.98    4445  250.39  4450.3  251.58
  4480.9  250.35    4488  249.19  4506.2  250.69  4511.6  249.24  4536.9  250.83
  4540.4  248.22  4543.9  248.22  4551.8  251.42  4598.1  252.58  4623.4  255.39
  4700.7  258.15  4732.6  257.33  4780.3  258.25    4839  257.87  4902.8  254.97
  5161.7  254.82  5167.2  254.48  5213.8  259.48  5242.5  260.92  5326.7  269.01
#Mann= 4 ,-1 , 0
  3705.8     .17       0  4780.3     .11       0  4902.8     .06       0
  5161.7     .17       0
Bank Sta=4902.8,5161.7
XS Rating Curve= 0 ,0
Exp/Cntr=0.3,0.1

Type RM Length L Ch R = 1 ,23974   ,149,149,149
BEGIN DESCRIPTION:
Mapping XS 733972d3
END DESCRIPTION:
XS GIS Cut Line= 3
      3772521.42       10104005.      3771458.96     10103369.61
      3770486.74       10103321.
#Sta/Elev= 30
  3635.2  266.92  3829.8  264.31  3866.7  262.44  3903.7  262.86  3909.5  261.78
  4057.4  259.89  4100.2  258.23    4152  257.97  4174.1  256.52  4259.7  255.96
  4312.2  253.49  4376.4  252.34  4471.7  254.17  4478.3     253    4530  252.35
  4536.6  251.07    4567  249.82  4580.5  247.22  4594.8   248.5  4618.1  247.53
  4625.4  248.98  4734.6  252.04  4742.1  253.42  4800.4  256.23  4921.5  256.65
  4994.4  254.84 5530.14  254.92  5635.2  258.28  5725.3   264.8  5846.6  270.61
#Mann= 4 ,-1 , 0
  3635.2     .17       0  4921.5     .11       0  4994.4     .06       0
 5530.14     .17       0
Bank Sta=4994.4,5530.14
XS Rating Curve= 0 ,0
Exp/Cntr=0.3,0.1

Type RM Length L Ch R = 1 ,23825   ,62,62,62
BEGIN DESCRIPTION:
LAKE CREEK TRIBUTARY NO. 3 43.0
END DESCRIPTION:
XS GIS Cut Line= 3
      3772577.03      10103959.9      3771466.88     10103299.75
      3770591.85     10103265.48
#Sta/Elev= 30
  3708.4  267.18  3905.2  264.25  3954.1  262.22  3991.1   262.6  4086.6  260.46
  4102.2  258.94  4370.6  256.76  4428.8  255.19  4437.2  253.23  4474.2  253.55
  4495.6  251.94  4575.5  253.32  4649.5  252.43  4713.8  249.19  4727.6  245.95
  4731.2  245.95  4735.2     248  4742.9  246.56  4750.8  247.89  4793.6  249.16
  4867.7  254.89  4910.5  256.64  5029.1  256.17  5067.6  258.69    5089  258.97
    5094  257.79  5429.4  259.76  5594.6  256.82  5719.6  258.89  5875.7  268.25
#Mann= 5 ,-1 , 0
  3708.4     .17       0  4713.8     .09       0  4793.6     .17       0
  5067.6     .11       0  5594.6     .17       0
Bank Sta=4713.8,4793.6
XS Rating Curve= 0 ,0
Exp/Cntr=0.3,0.1

Type RM Length L Ch R = 1 ,23763   ,430,430,430
BEGIN DESCRIPTION:
Mapping XS a4dae6f7
END DESCRIPTION:
XS GIS Cut Line= 3
      3772136.07     10103077.94      3771511.24     10103243.34
      3770608.25     10103206.42
#Sta/Elev= 30
  4305.8  259.26  4366.3  255.41  4419.3  253.56  4454.4  250.46  4459.6  250.91
  4529.7  247.44  4593.8  246.54  4650.3  246.63  4676.4  247.81  4688.5   245.1
    4697  245.41  4707.4  247.15  4748.8  247.53  4831.5  251.24  4881.4  254.94
  4965.6  257.24  5085.7  256.35  5145.7  253.89  5175.7  251.32  5260.7  248.91
  5372.9  248.57  5377.9   247.1  5395.9   248.1  5435.9  248.34  5577.2  256.02
  5615.3  257.43  5636.1  259.42  5776.2  263.63  5826.3  266.43  5855.9  266.65
#Mann= 7 ,-1 , 0
  4305.8     .17       0  4366.3     .15       0  4593.8     .17       0
  5260.7     .11       0  5372.9     .06       0  5435.9     .11       0
  5577.2     .17       0
Bank Sta=5372.9,5435.9
XS Rating Curve= 0 ,0
Exp/Cntr=0.3,0.1

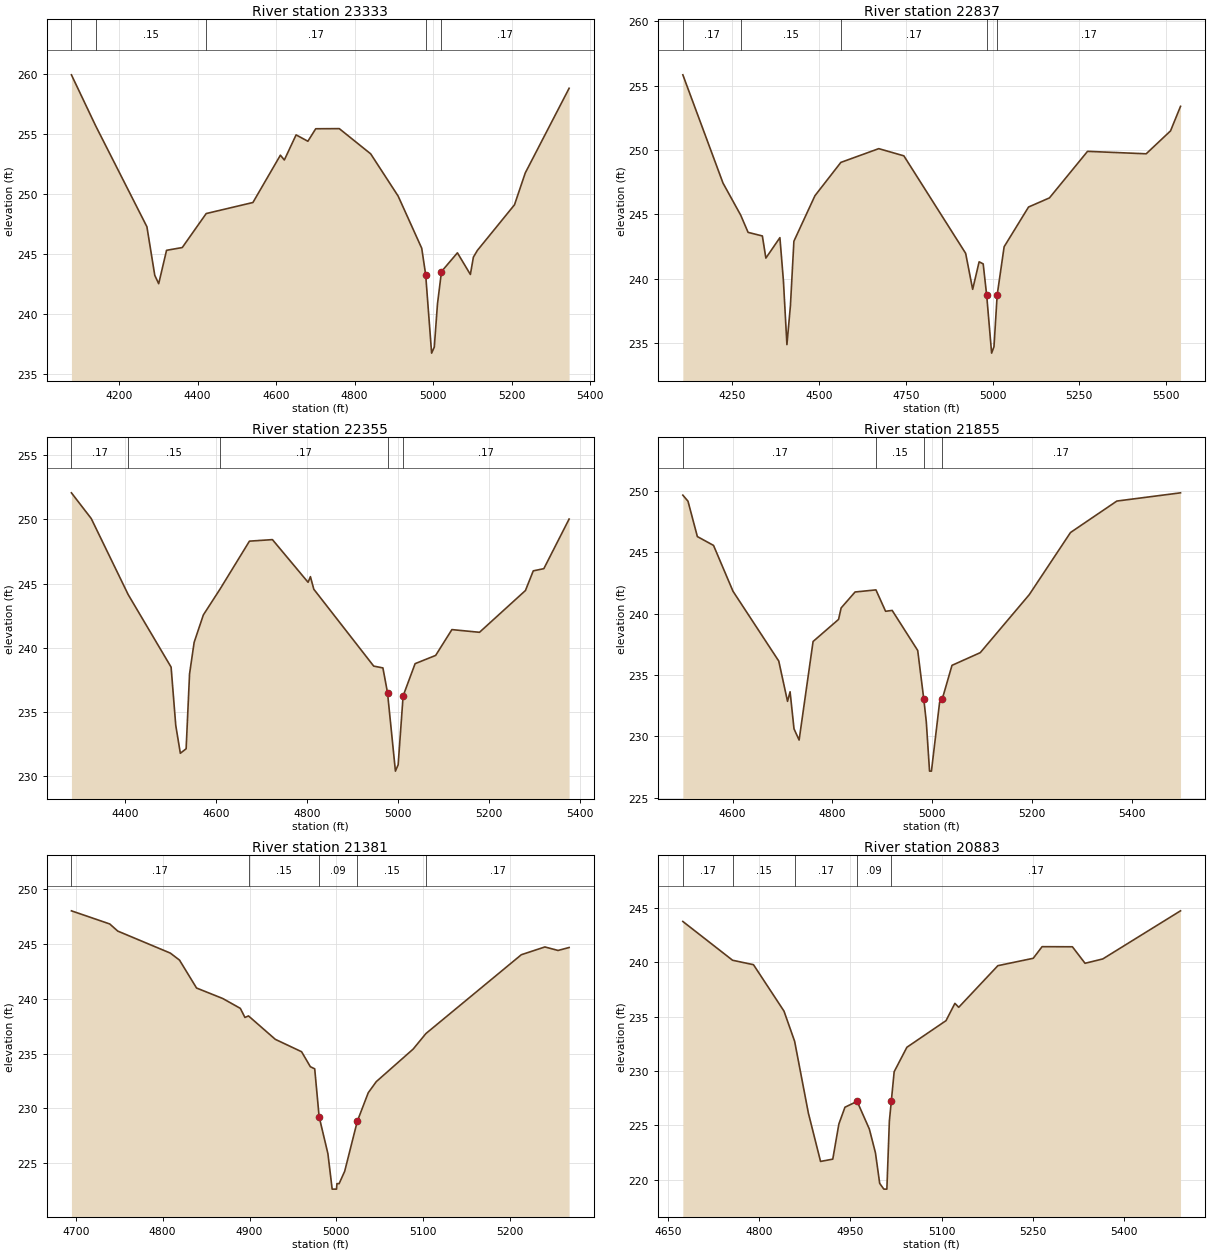
Type RM Length L Ch R = 1 ,23333   ,496,496,496
BEGIN DESCRIPTION:
LAKE CREEK TRIBUTARY NO. 3 42.0
END DESCRIPTION:
XS GIS Cut Line= 3
      3772130.11     10102953.05      3771208.82     10102949.71
      3770867.89     10103011.06
#Sta/Elev= 30
  4078.7   259.9  4140.2  255.67    4271  247.25    4291  243.21    4301  242.51
    4321  245.29    4361  245.52    4422  248.35    4541  249.27    4611  253.21
    4621  252.81    4651   254.9    4681  254.37    4701  255.41    4761  255.42
    4841  253.32    4911   249.8    4971  245.46    4981  243.27  4996.2  236.73
    5003  237.23  5011.1  240.82  5021.3  243.52  5061.9  245.08  5094.9  243.28
  5102.6  244.72  5112.7  245.28  5207.3  249.08  5234.7  251.73  5346.4  258.78
#Mann= 5 ,-1 , 0
  4078.7     .17       0  4140.2     .15       0    4422     .17       0
    4981     .09       0  5021.3     .17       0
Bank Sta=4981,5021.3
XS Rating Curve= 0 ,0
Exp/Cntr=0.3,0.1

Type RM Length L Ch R = 1 ,22837   ,482,482,482
BEGIN DESCRIPTION:
LAKE CREEK TRIBUTARY NO. 3 41.0
END DESCRIPTION:
XS GIS Cut Line= 4
      3772104.75     10102380.03      3771221.17     10102500.84
      3771052.71     10102515.45      3770902.94      10102856.3
#Sta/Elev= 30
  4108.2  255.84  4223.9  247.42  4274.8  244.93  4296.1  243.59  4337.2  243.31
  4347.3  241.59  4387.7  243.18  4397.8  239.84  4407.9  234.86    4418  237.89
    4428   242.9  4488.6  246.44  4563.2  249.03  4672.4   250.1  4744.7  249.54
  4922.6  241.96  4942.8  239.16  4961.4   241.3  4973.1  241.14  4983.2  238.69
  4997.4   234.2  5004.2   234.7  5013.4  238.72  5033.4  242.47  5103.7  245.56
  5163.9  246.27  5273.6  249.89  5442.5   249.7  5512.6  251.48  5541.4  253.39
#Mann= 5 ,-1 , 0
  4108.2     .17       0  4274.8     .15       0  4563.2     .17       0
  4983.2     .09       0  5013.4     .17       0
Bank Sta=4983.2,5013.4
XS Rating Curve= 0 ,0
Exp/Cntr=0.3,0.1

Type RM Length L Ch R = 1 ,22355   ,500,500,500
BEGIN DESCRIPTION:
LAKE CREEK TRIBUTARY NO. 3 40.0
END DESCRIPTION:
XS GIS Cut Line= 3
      3771844.43     10101949.47      3771134.69     10102054.71
      3770762.91      10102106.7
#Sta/Elev= 30
  4282.5  252.06    4326  250.06  4407.2  244.14  4501.4   238.5  4511.6  233.97
  4521.7   231.8  4534.4  232.15  4541.9  237.97    4552  240.43  4572.2  242.56
  4609.2  244.59  4673.4   248.3  4723.9  248.42  4802.2   245.1  4807.3  245.54
  4814.8  244.56  4946.3  238.58  4966.5  238.44  4976.6  236.52    4994  230.41
    5000  230.91  5010.9  236.26  5037.2  238.77  5082.3  239.41    5118  241.42
  5178.6  241.21  5279.5  244.46  5296.7  245.99  5319.9  246.16  5375.4  250.02
#Mann= 5 ,-1 , 0
  4282.5     .17       0  4407.2     .15       0  4609.2     .17       0
  4976.6     .09       0  5010.9     .17       0
Bank Sta=4976.6,5010.9
XS Rating Curve= 0 ,0
Exp/Cntr=0.3,0.1

Type RM Length L Ch R = 1 ,21855   ,474,474,474
BEGIN DESCRIPTION:
LAKE CREEK TRIBUTARY NO. 3 39.0
END DESCRIPTION:
XS GIS Cut Line= 3
      3771726.39     10101494.73      3771236.27     10101592.11
      3770754.25     10101716.06
#Sta/Elev= 30
  4500.3  249.64  4510.6  249.15  4529.4  246.27  4561.8  245.55  4600.8  241.82
  4692.5  236.14  4710.1  232.86  4715.2  233.64  4723.1  230.62  4733.3  229.71
  4761.3  237.73  4812.4  239.53  4817.5  240.46  4845.5  241.76  4887.3  241.93
  4906.6  240.19  4919.8  240.26    4971     237 4983.23233.0221  4988.2  231.19
  4994.7  227.18  4998.5  227.18  5014.9  232.79    5020  233.02  5039.7  235.79
  5096.3  236.82  5194.5  241.54  5277.2   246.6  5370.1  249.16  5497.7  249.83
#Mann= 4 ,-1 , 0
  4500.3     .17       0  4887.3     .15       0 4983.23     .09       0
    5020     .17       0
Bank Sta=4983.23,5020
XS Rating Curve= 0 ,0
Exp/Cntr=0.3,0.1

Type RM Length L Ch R = 1 ,21381   ,498,498,498
BEGIN DESCRIPTION:
LAKE CREEK TRIBUTARY NO. 3 38.0
END DESCRIPTION:
XS GIS Cut Line= 3
      3771500.71     10101091.08       3771198.1     10101129.19
      3770972.08     10101272.82
#Sta/Elev= 30
    4695  248.04  4739.1  246.84  4748.3  246.19  4808.8  244.18  4819.4  243.54
    4839  240.99  4869.2  240.03  4889.4  239.13  4894.7   238.3  4898.8  238.44
  4929.7   236.3  4959.9  235.17    4970   233.8    4975  233.61  4980.1  229.23
  4990.2  225.86  4995.1  222.62  5000.1  222.62  5000.6  223.12  5003.1  223.12
  5009.5  224.25    5024  228.81  5036.6  231.42  5045.9  232.44  5088.3  235.41
    5103  236.83  5212.8  244.03  5239.9  244.74  5255.1  244.42  5267.8  244.69
#Mann= 5 ,-1 , 0
    4695     .17       0  4898.8     .15       0  4980.1     .09       0
    5024     .15       0    5103     .17       0
Bank Sta=4980.1,5024
XS Rating Curve= 0 ,0
Exp/Cntr=0.3,0.1

Type RM Length L Ch R = 1 ,20883   ,500,500,500
BEGIN DESCRIPTION:
LAKE CREEK TRIBUTARY NO. 3 37.0
END DESCRIPTION:
XS GIS Cut Line= 3
      3771283.74     10100691.77      3770958.85     10100711.77
      3770567.85     10101011.07
#Sta/Elev= 30
  4674.5  243.77  4756.2   240.2  4790.6  239.79  4840.7  235.52  4858.2  232.74
  4880.8  226.13  4900.8  221.68  4920.9  221.89  4930.9  225.12  4940.9  226.67
  4960.9  227.21    4981  224.66    4991  222.48    4998  219.66  5004.8  219.13
  5009.8  219.13  5013.9  225.39 5017.12227.2447  5021.8  229.94  5042.7  232.19
    5107  234.64  5121.6  236.23  5127.9  235.87  5192.2   239.7  5250.3  240.38
  5264.9  241.45  5314.7  241.44  5335.5  239.92  5364.6  240.32  5492.4  244.75
#Mann= 5 ,-1 , 0
  4674.5     .17       0  4756.2     .15       0  4858.2     .17       0
  4960.9     .09       0 5017.12     .17       0
Bank Sta=4960.9,5017.12
XS Rating Curve= 0 ,0
Exp/Cntr=0.3,0.1