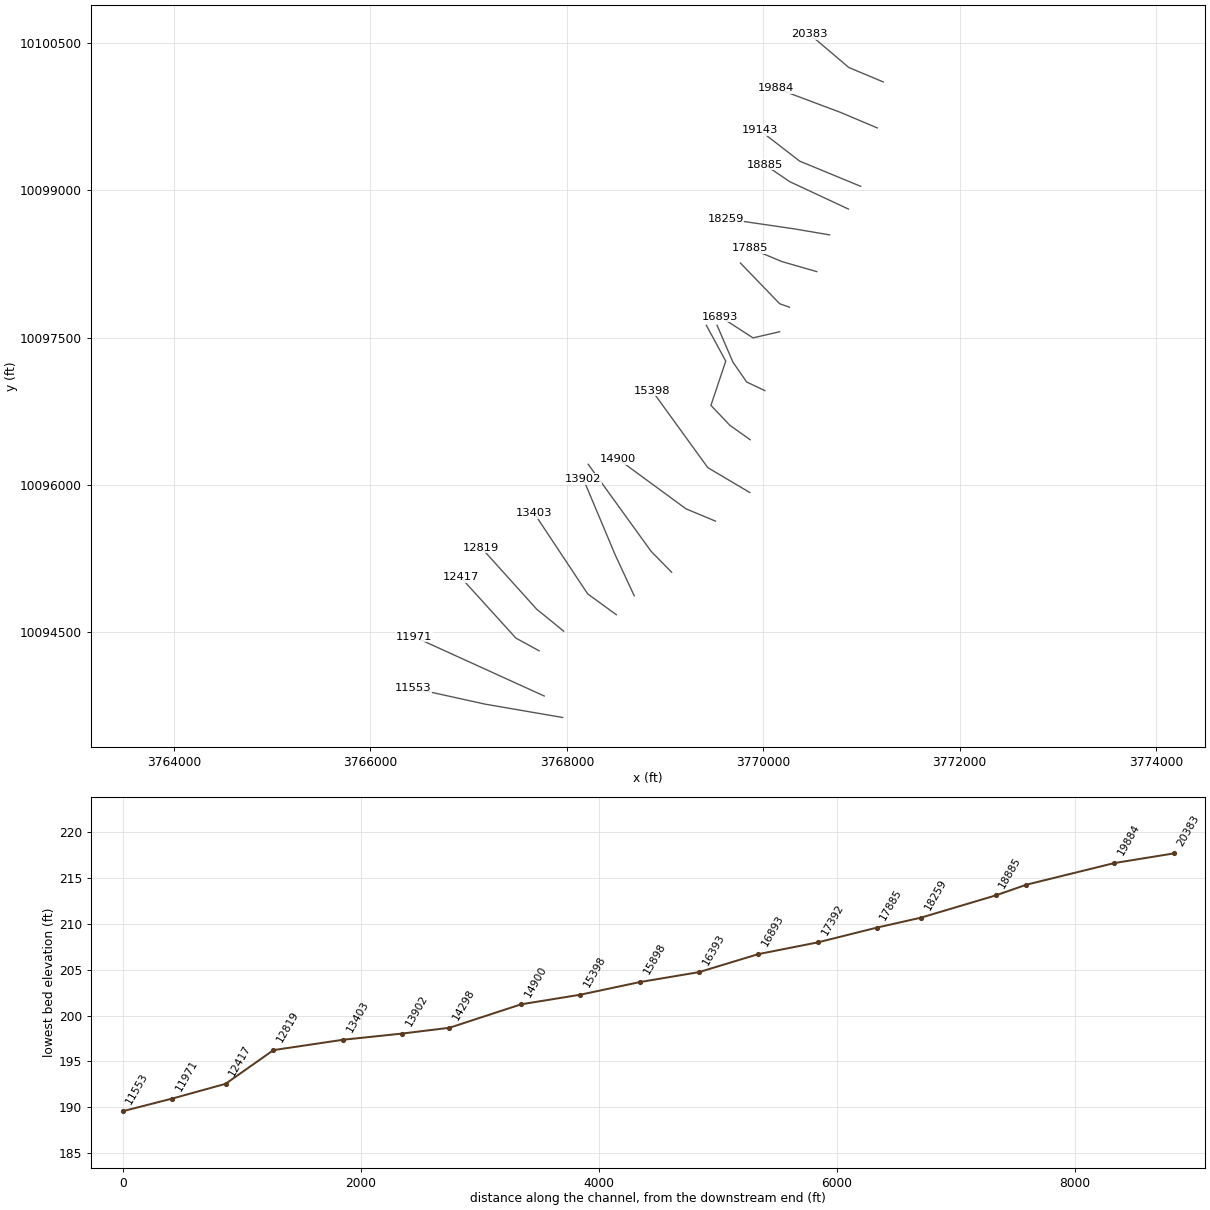
HEC-RAS study LAKE CREEK TRIBUTARY NO 3.prj: LAKE CREEK TRIBUTARY NO 3 Base Level Engineering

--- LAKE CREEK TRIBUTARY NO 3.g01 (geometry) --- (continued)

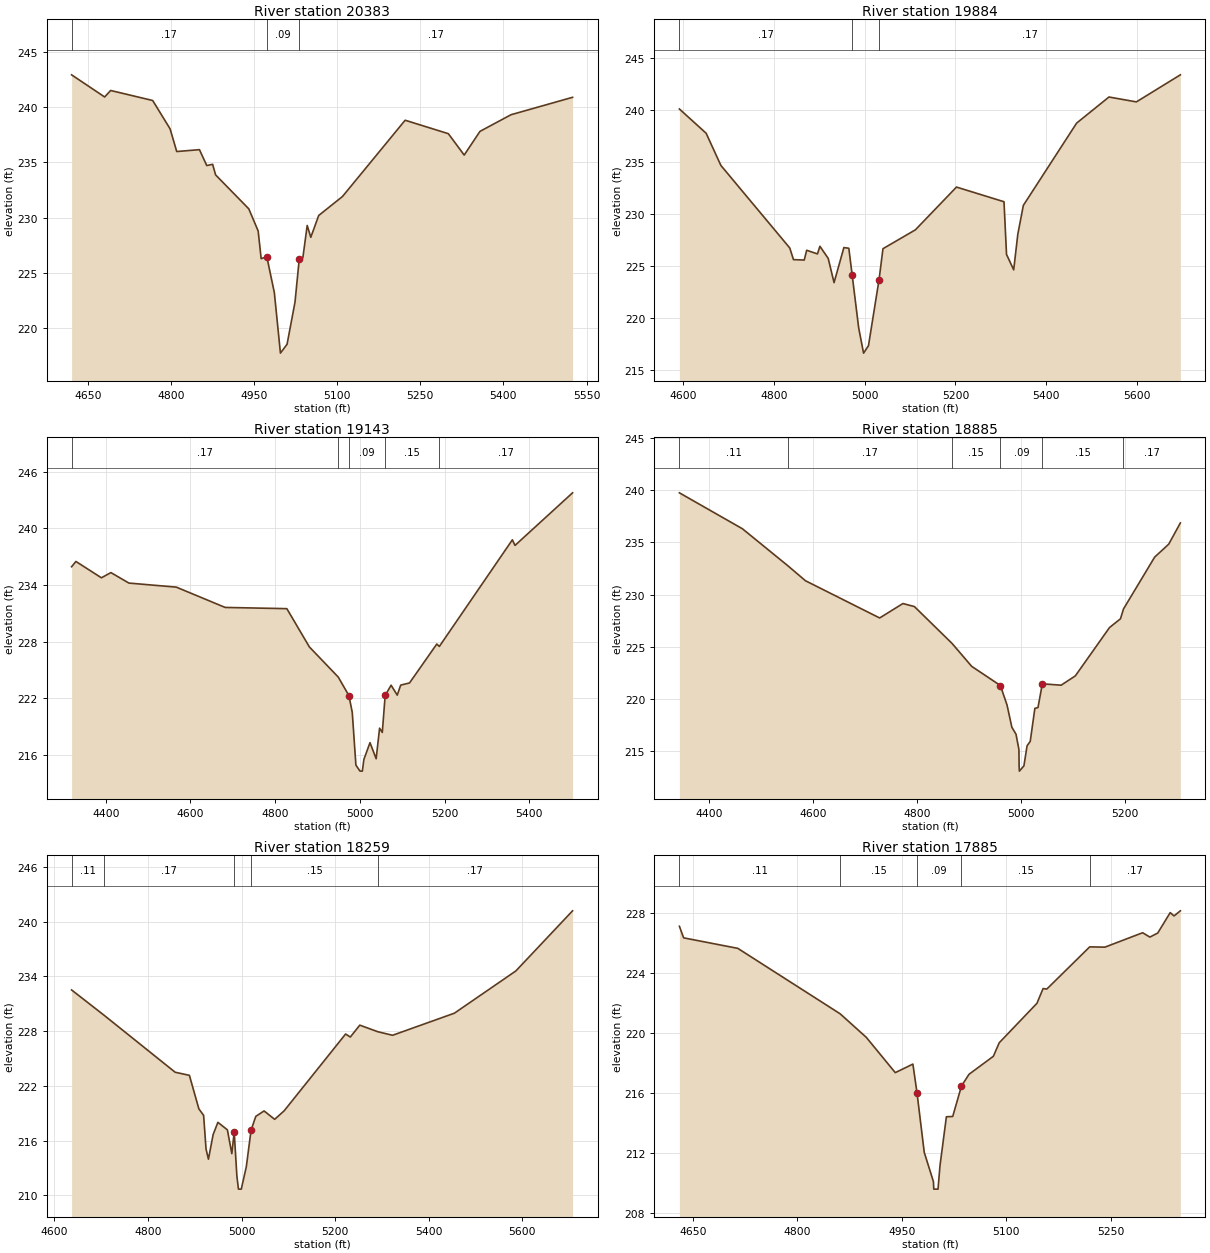
Type RM Length L Ch R = 1 ,20383   ,499,499,499
BEGIN DESCRIPTION:
LAKE CREEK TRIBUTARY NO. 3 36.0
END DESCRIPTION:
XS GIS Cut Line= 3
      3771222.93     10100105.84      3770872.82     10100252.27
      3770472.49     10100591.61
#Sta/Elev= 30
  4620.5  242.95  4680.2  240.94    4691  241.53  4766.9  240.62  4798.3  238.05
  4810.3  235.99  4851.3  236.16  4864.5  234.72  4875.1  234.83  4880.5  233.87
  4940.4  230.79  4957.3  228.78  4962.7  226.27  4972.9  226.45  4986.5  223.19
  4997.5   217.7  5009.5  218.51  5023.8  222.33  5031.5  226.26    5038  226.37
  5045.8  229.28  5052.3  228.21  5066.6  230.19  5109.5  231.91  5222.6  238.83
  5300.6  237.61  5329.2  235.67  5357.7  237.82  5413.7  239.33  5524.8  240.91
#Mann= 3 , 0 , 0
  4620.5     .17       0  4972.9     .09       0  5031.5     .17       0
Bank Sta=4972.9,5031.5
XS Rating Curve= 0 ,0
Exp/Cntr=0.3,0.1

Type RM Length L Ch R = 1 ,19884   ,741,741,741
BEGIN DESCRIPTION:
LAKE CREEK TRIBUTARY NO. 3 35.0
END DESCRIPTION:
XS GIS Cut Line= 3
      3771162.19     10099637.09      3770785.49     10099796.13
      3770133.56     10100040.72
#Sta/Elev= 30
  4591.1   240.1  4650.1  237.77  4682.6  234.68  4834.6  226.75  4842.8  225.63
  4866.5  225.59  4871.9  226.53  4895.7  226.18  4901.1  226.91  4919.4  225.75
  4932.3  223.42    4954  226.79  4964.9  226.72  4972.2  224.17  4986.6  219.08
  4997.4  216.65  5008.2  217.36  5031.6  223.71  5040.2  226.68  5111.7  228.49
  5202.4   232.6  5307.2  231.19  5312.8  226.13  5328.6  224.65  5337.7  228.07
  5349.9  230.84  5467.4  238.74  5538.8  241.25  5599.3  240.78  5696.3  243.38
#Mann= 3 , 0 , 0
  4591.1     .17       0  4972.2     .09       0  5031.6     .17       0
Bank Sta=4972.2,5031.6
XS Rating Curve= 0 ,0
Exp/Cntr=0.3,0.1

Type RM Length L Ch R = 1 ,19143   ,258,258,258
BEGIN DESCRIPTION:
LAKE CREEK TRIBUTARY NO. 3 34.0
END DESCRIPTION:
XS GIS Cut Line= 3
      3770992.95     10099042.45      3770372.27     10099298.54
      3769967.88     10099611.05
#Sta/Elev= 30
  4319.5  235.93  4329.7  236.49  4389.9  234.76  4412.3  235.31  4454.8   234.2
  4566.7  233.77    4682  231.62  4827.6  231.49  4880.9  227.43    4949  224.24
  4974.1  222.28    4982  220.51  4990.6  214.92  5000.3  214.28  5005.8  214.28
  5009.4  215.51  5023.9   217.3  5038.4  215.59  5046.5  218.83  5052.9  218.38
  5059.7   222.3  5073.7  223.38  5088.2  222.33  5096.3  223.39  5117.2  223.62
  5181.5  227.74  5187.6  227.49  5359.9  238.78  5366.2  238.19    5502  243.76
#Mann= 5 ,-1 , 0
  4319.5     .17       0    4949     .15       0  4974.1     .09       0
  5059.7     .15       0  5187.6     .17       0
Bank Sta=4974.1,5059.7
XS Rating Curve= 0 ,0
Exp/Cntr=0.3,0.1

Type RM Length L Ch R = 1 ,18885   ,626,626,626
BEGIN DESCRIPTION:
LAKE CREEK TRIBUTARY NO. 3 33.0
END DESCRIPTION:
XS GIS Cut Line= 3
      3770867.84     10098811.08      3770271.59     10099089.15
      3770017.85     10099261.07
#Sta/Elev= 30
  4342.1  239.73  4463.5  236.29  4550.5  232.77  4584.8  231.32  4727.6  227.76
  4772.4  229.14  4794.5  228.85  4867.1  225.32  4904.8  223.13    4960   221.3
  4972.8  219.44  4982.1  217.31  4990.1  216.64  4995.7  215.18  4996.1  213.61
  4996.6  213.11  5005.3  213.61  5011.4  215.53  5017.5  215.96  5026.4  219.11
  5032.4  219.19  5040.8  221.46    5077  221.33  5104.3  222.22  5170.2  226.85
  5191.2  227.68    5197  228.62    5257  233.58  5284.1  234.82  5306.5  236.85
#Mann= 6 ,-1 , 0
  4342.1     .11       0  4550.5     .17       0  4867.1     .15       0
    4960     .09       0  5040.8     .15       0    5197     .17       0
Bank Sta=4960,5040.8
XS Rating Curve= 0 ,0
Exp/Cntr=0.3,0.1

Type RM Length L Ch R = 1 ,18259   ,374,374,374
BEGIN DESCRIPTION:
LAKE CREEK TRIBUTARY NO. 3 32.0
END DESCRIPTION:
XS GIS Cut Line= 3
      3770676.07     10098547.68      3770320.18     10098608.44
      3769617.88     10098711.07
#Sta/Elev= 30
  4636.7  232.52  4706.3  229.74  4858.1   223.5  4888.5  223.16  4908.8  219.48
  4918.9  218.78  4924.1  215.08  4929.2  213.97  4939.2  216.66  4949.4  218.01
  4969.7  217.19  4979.2  214.58  4984.3  216.95    4990  212.12  4993.4  210.69
  4999.4  210.69  5010.2  213.15  5020.3  217.14  5030.4  218.66  5048.1  219.26
  5070.8  218.34    5091  219.27  5222.4  227.69  5232.5  227.36  5252.7  228.66
  5291.3  227.94  5322.8  227.55  5454.9  229.97  5586.3   234.6  5707.5  241.19
#Mann= 5 ,-1 , 0
  4636.7     .11       0  4706.3     .17       0  4984.3     .09       0
  5020.3     .15       0  5291.3     .17       0
Bank Sta=4984.3,5020.3
XS Rating Curve= 0 ,0
Exp/Cntr=0.3,0.1

Type RM Length L Ch R = 1 ,17885   ,493,493,493
BEGIN DESCRIPTION:
LAKE CREEK TRIBUTARY NO. 3 31.0
END DESCRIPTION:
XS GIS Cut Line= 3
      3770545.86     10098173.55      3770190.76     10098275.69
      3769867.89     10098411.06
#Sta/Elev= 30
  4630.5   227.1  4636.6  226.33  4714.4  225.63  4861.4  221.27    4899   219.7
  4940.6  217.35  4965.9  217.92  4971.8  216.01  4982.2  212.04  4995.4  210.09
  4995.9  209.59    5002  209.59  5004.8  211.14    5014  214.41  5023.1  214.43
  5035.7  216.46  5046.5  217.24  5081.5  218.44  5089.9  219.34  5144.1  221.97
  5152.9  222.95  5158.3  222.92  5219.9  225.73  5241.7  225.71  5295.9  226.67
  5306.3  226.38  5317.6  226.65  5335.5  228.01    5341  227.79  5350.1  228.13
#Mann= 5 ,-1 , 0
  4630.5     .11       0  4861.4     .15       0  4971.8     .09       0
  5035.7     .15       0  5219.9     .17       0
Bank Sta=4971.8,5035.7
XS Rating Curve= 0 ,0
Exp/Cntr=0.3,0.1

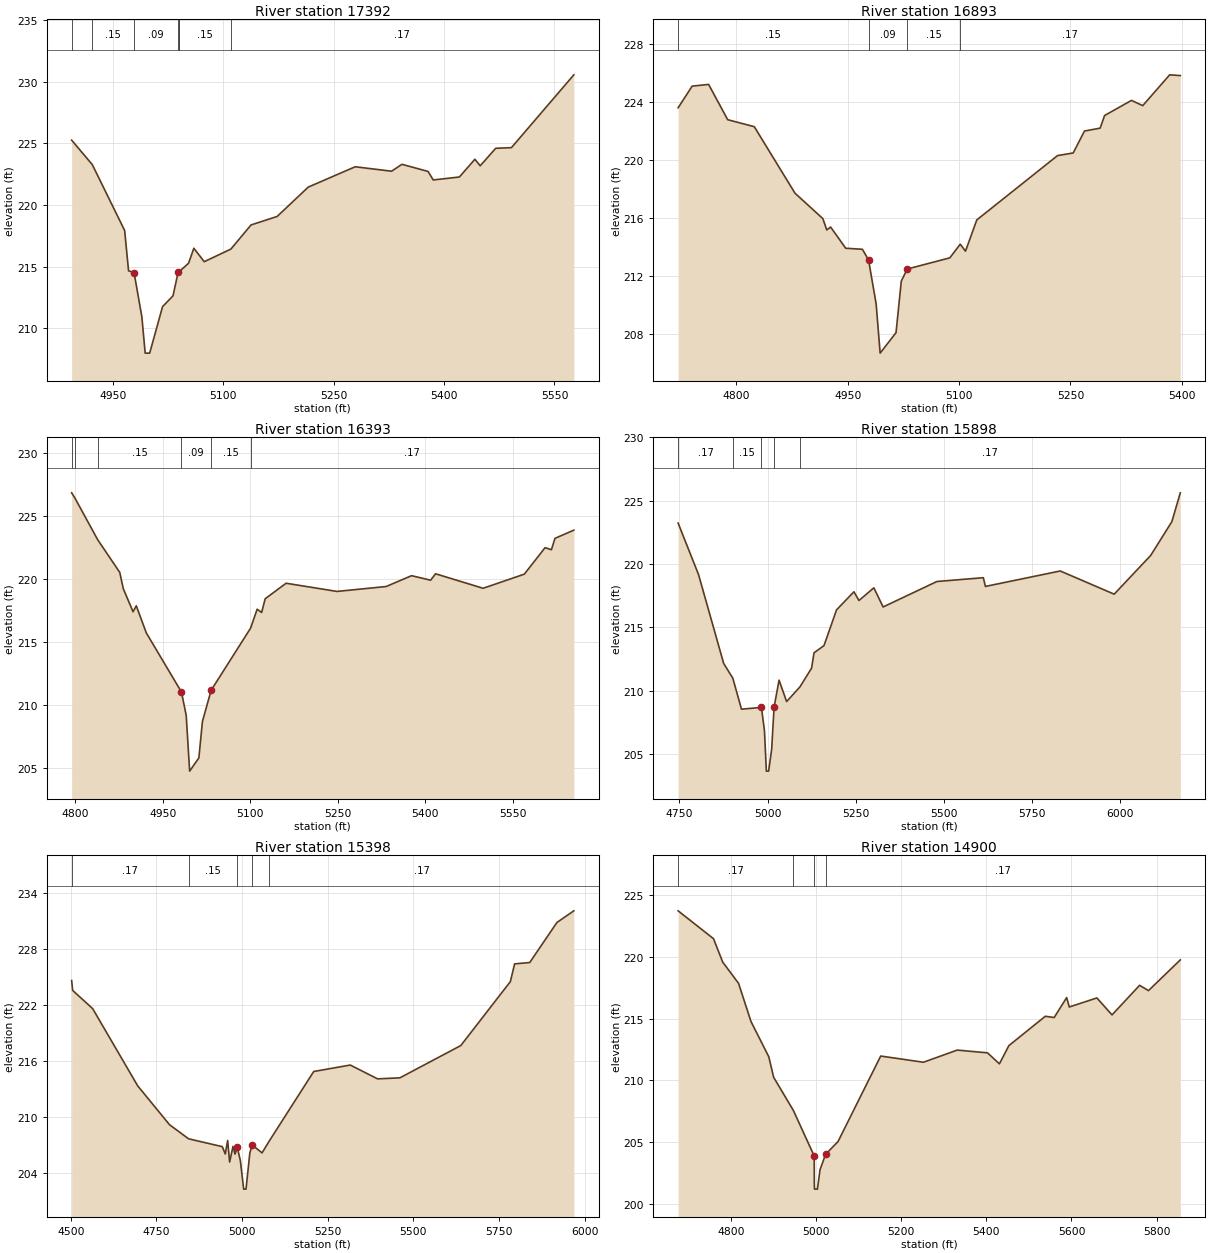
Type RM Length L Ch R = 1 ,17392   ,499,499,499
BEGIN DESCRIPTION:
LAKE CREEK TRIBUTARY NO. 3 30.0
END DESCRIPTION:
XS GIS Cut Line= 3
      3770267.81     10097811.09      3770167.95     10097846.33
      3769767.83     10098261.09
#Sta/Elev= 30
  4894.1  225.27  4922.2  223.28  4966.1  217.94  4971.4  214.67  4978.9  214.52
  4989.5  210.93    4994  207.99  5000.1  207.99  5017.6  211.76  5031.8  212.64
  5038.7  214.54  5039.4  214.56  5052.9  215.28  5060.1   216.5  5074.2  215.41
  5110.4  216.43  5137.8  218.39  5173.3  219.08  5215.5  221.46  5279.3  223.11
  5328.7  222.75  5342.8  223.31  5378.3  222.73  5385.3  222.04  5420.8  222.28
  5441.9  223.72  5449.1  223.19  5470.2  224.61  5491.5  224.66  5576.3  230.57
#Mann= 7 ,-1 , 0
  4894.1     .11       0  4922.2     .15       0  4978.9     .09       0
  5038.7     .12       0  5039.4     .11       0  5039.4     .15       0
  5110.4     .17       0
Bank Sta=4978.9,5038.7
XS Rating Curve= 0 ,0
Exp/Cntr=0.3,0.1

Type RM Length L Ch R = 1 ,16893   ,500,500,500
BEGIN DESCRIPTION:
LAKE CREEK TRIBUTARY NO. 3 29.0
END DESCRIPTION:
XS GIS Cut Line= 3
      3770167.87     10097561.08      3769896.38     10097498.55
      3769562.22     10097714.74
#Sta/Elev= 30
  4721.4   223.6  4740.3  225.09  4762.5  225.21  4788.2  222.78    4824   222.3
  4878.9  217.72  4916.4  215.97  4921.7  215.19  4926.9  215.39  4947.2  213.93
  4969.7  213.86    4978  213.12  4988.2   210.1  4993.6  206.71    5015  208.12
  5022.1  211.67  5030.1   212.5  5087.5  213.27  5101.5  214.21  5108.6  213.73
  5123.8  215.88  5232.6  220.31  5253.7  220.49  5268.9     222    5290   222.2
    5296  223.07  5332.2  224.11  5347.4  223.75  5383.7  225.87    5398  225.82
#Mann= 4 ,-1 , 0
  4721.4     .15       0    4978     .09       0  5030.1     .15       0
  5101.5     .17       0
Bank Sta=4978,5030.1
XS Rating Curve= 0 ,0
Exp/Cntr=0.3,0.1

Type RM Length L Ch R = 1 ,16393   ,495,495,495
BEGIN DESCRIPTION:
LAKE CREEK TRIBUTARY NO. 3 28.0
END DESCRIPTION:
XS GIS Cut Line= 4
      3770017.85     10096961.07      3769831.71     10097049.09
      3769691.71     10097251.66      3769530.38     10097626.36
#Sta/Elev= 30
  4794.1  226.81  4799.3  226.43  4838.6   223.1  4876.5   220.5  4882.6   219.2
  4899.3  217.38  4904.8  217.85    4922   215.7  4982.2  211.01  4990.3  209.16
  4996.2  204.74    5012  205.79  5018.1  208.68    5033  211.15  5100.6  216.08
  5111.8  217.58  5119.5  217.32  5125.6  218.41  5161.4  219.64  5248.6  218.99
  5332.7  219.38  5376.3  220.24  5408.9  219.88  5417.4  220.39  5498.8  219.24
  5569.4  220.36  5604.9  222.46  5615.8   222.3  5621.9   223.2  5654.2  223.85
#Mann= 6 ,-1 , 0
  4794.1     .17       0  4799.3     .11       0  4838.6     .15       0
  4982.2     .09       0    5033     .15       0  5100.6     .17       0
Bank Sta=4982.2,5033
XS Rating Curve= 0 ,0
Exp/Cntr=0.3,0.1

Type RM Length L Ch R = 1 ,15898   ,500,500,500
BEGIN DESCRIPTION:
LAKE CREEK TRIBUTARY NO. 3 27.0
END DESCRIPTION:
XS GIS Cut Line= 5
      3769867.86     10096461.07      3769660.96     10096607.54
      3769467.85     10096811.07      3769618.79     10097262.08
      3769421.02      10097626.4
#Sta/Elev= 30
  4746.5  223.24  4804.4  219.18  4875.7  212.16  4901.6     211  4926.2  208.55
  4982.8  208.69  4991.4  206.84  4996.8  203.66  5003.2  203.66  5011.8  205.39
  5018.7  208.72  5032.8  210.84  5054.2  209.15    5092  210.31    5125  211.79
  5131.9     213  5160.2  213.57  5195.8  216.39  5245.2  217.82  5259.3  217.13
  5301.6  218.13  5327.9  216.62  5480.5  218.63  5612.1  218.93    5618  218.24
  5830.2  219.46  5983.2  217.63  6086.8  220.69  6146.7  223.35  6170.7  225.63
#Mann= 5 ,-1 , 0
  4746.5     .17       0  4901.6     .15       0  4982.8     .09       0
  5018.7     .15       0    5092     .17       0
Bank Sta=4982.8,5018.7
XS Rating Curve= 0 ,0
Exp/Cntr=0.3,0.1

Type RM Length L Ch R = 1 ,15398   ,498,498,498
BEGIN DESCRIPTION:
LAKE CREEK TRIBUTARY NO. 3 26.0
END DESCRIPTION:
XS GIS Cut Line= 3
      3769863.58     10095923.54      3769435.77      10096176.9
      3768867.87     10096961.05
#Sta/Elev= 30
  4502.8  224.62  4505.7  223.57  4564.2  221.61  4695.4  213.35  4788.4  209.18
  4844.1  207.67  4942.4  206.83  4951.1  206.04    4958  207.49  4963.8  205.18
  4973.6  206.85  4979.5  206.03    4986  206.75  4995.1  205.34  5004.8  202.28
  5011.6  202.28  5022.8  206.17  5029.8  207.01  5058.4  206.16  5079.4  207.43
  5209.2  214.88  5315.9  215.57  5395.6  214.09  5460.6   214.2  5638.4  217.66
    5783  224.51  5795.4  226.41  5839.5  226.55  5918.8  230.84  5968.2  232.09
#Mann= 5 ,-1 , 0
  4502.8     .17       0  4844.1     .15       0    4986     .09       0
  5029.8     .15       0  5079.4     .17       0
Bank Sta=4986,5029.8
XS Rating Curve= 0 ,0
Exp/Cntr=0.3,0.1

Type RM Length L Ch R = 1 ,14900   ,602,602,602
BEGIN DESCRIPTION:
LAKE CREEK TRIBUTARY NO. 3 25.0
END DESCRIPTION:
XS GIS Cut Line= 3
      3769514.64     10095631.87      3769215.28     10095756.32
      3768525.04     10096262.08
#Sta/Elev= 30
  4675.8  223.69    4759  221.44  4780.6  219.55  4817.8  217.84    4847  214.76
  4888.9  211.91  4900.2  210.26  4946.6  207.58  4995.6   203.9  4995.8  201.73
  4996.3  201.23  5003.1  201.23  5009.2  202.79  5022.2  204.03  5051.5  205.07
  5151.8  211.97  5252.2  211.47  5331.5  212.45  5402.7  212.23  5430.7  211.34
  5452.9  212.81  5538.5  215.18  5559.4  215.08  5588.7  216.69  5594.9  215.93
  5659.7  216.66  5695.3  215.29  5760.1  217.68  5780.9  217.25  5855.7  219.73
#Mann= 4 ,-1 , 0
  4675.8     .17       0  4946.6     .15       0  4995.6     .09       0
  5022.2     .17       0
Bank Sta=4995.6,5022.2
XS Rating Curve= 0 ,0
Exp/Cntr=0.3,0.1

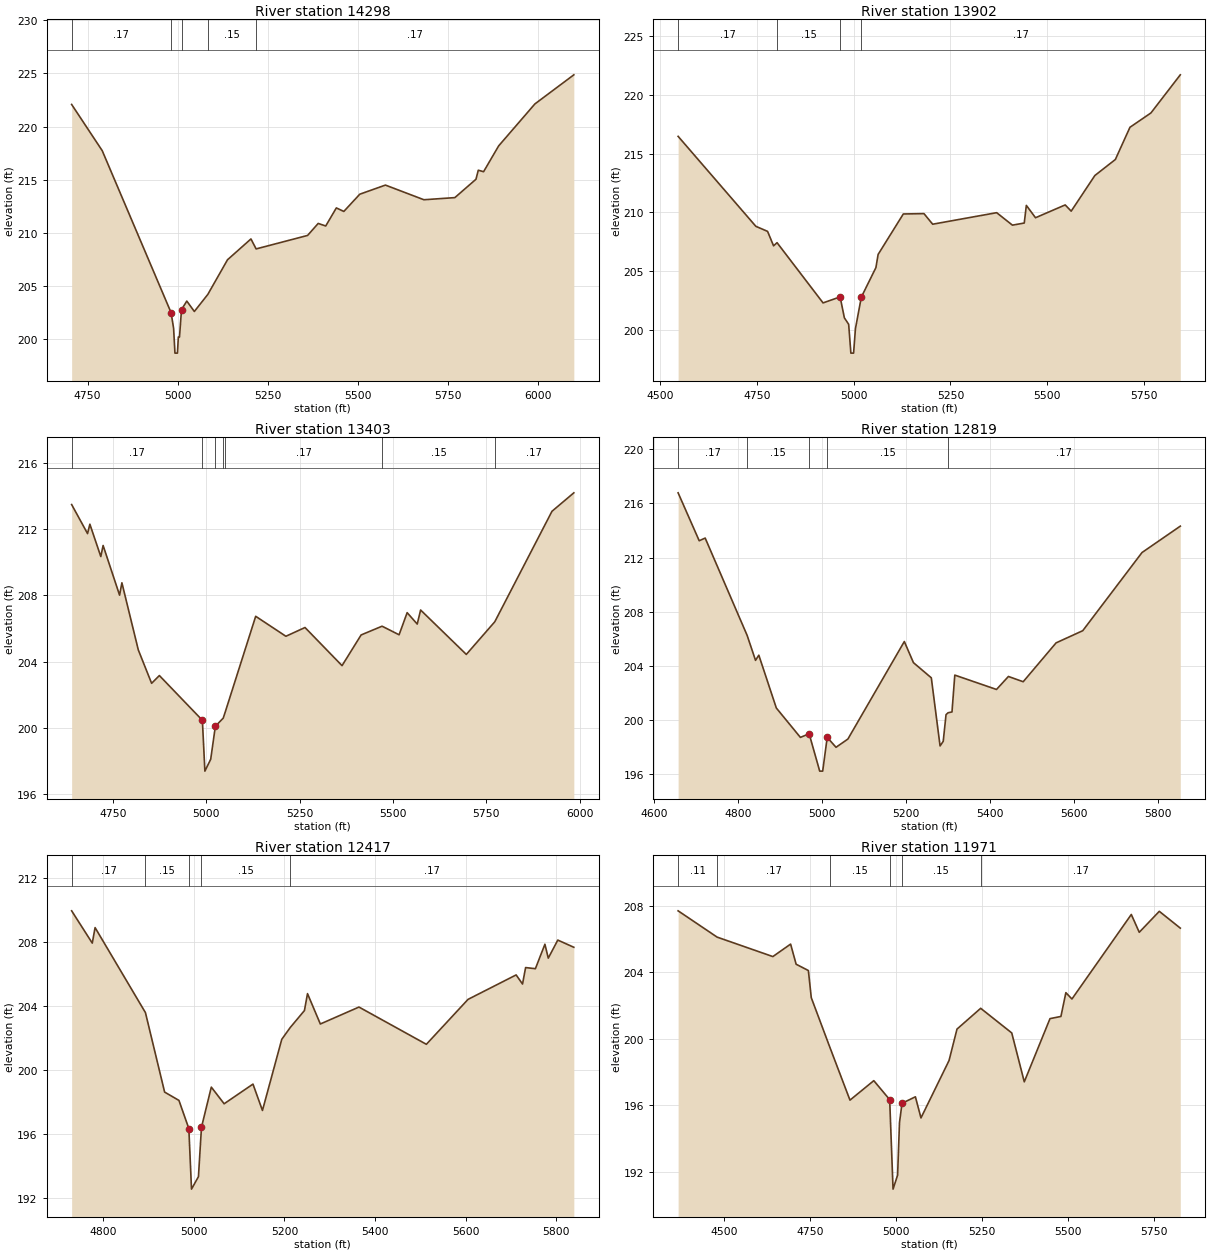
Type RM Length L Ch R = 1 ,14298   ,396,396,396
BEGIN DESCRIPTION:
LAKE CREEK TRIBUTARY NO. 3 24.0
END DESCRIPTION:
XS GIS Cut Line= 3
      3769067.84     10095111.08      3768858.38     10095324.58
      3768217.84     10096211.09
#Sta/Elev= 30
  4705.6  222.08  4790.4  217.73  4981.4  202.48  4988.4     201  4992.1  198.67
    4999  198.67  5001.5  200.19  5004.7  200.19  5010.3  202.77    5025  203.57
  5045.9  202.59  5083.3   204.2  5137.9  207.46  5202.9  209.42  5217.2  208.48
    5360  209.75  5389.4  210.88  5410.3  210.64  5439.7  212.34  5460.5  212.01
  5504.7  213.63  5575.8  214.49  5682.6  213.11  5768.4  213.31    5827  215.04
  5833.4  215.89  5848.1  215.75  5889.9  218.18  5990.4  222.13  6098.4  224.87
#Mann= 5 ,-1 , 0
  4705.6     .17       0  4981.4     .09       0  5010.3     .17       0
  5083.3     .15       0  5217.2     .17       0
Bank Sta=4981.4,5010.3
XS Rating Curve= 0 ,0
Exp/Cntr=0.3,0.1

Type RM Length L Ch R = 1 ,13902   ,499,499,499
BEGIN DESCRIPTION:
LAKE CREEK TRIBUTARY NO. 3 23.0
END DESCRIPTION:
XS GIS Cut Line= 3
      3768686.49     10094871.48      3768495.04     10095282.81
      3768167.87     10096061.03
#Sta/Elev= 30
  4546.3  216.47  4747.2  208.82  4777.5  208.39    4793  207.16    4802  207.43
  4920.9  202.31    4965  202.82    4976  201.04  4987.1  200.49  4992.8  198.04
  4999.8  198.04  5004.6  200.12  5019.8   202.8  5057.5  205.31  5063.2  206.43
  5128.3  209.87  5181.7   209.9  5204.2     209  5369.6  209.98  5410.3  208.92
  5440.9   209.1  5446.3   210.6    5470  209.55  5546.7  210.64  5562.2  210.11
  5623.4  213.14  5676.3   214.5  5714.1  217.24  5768.3  218.46  5844.2   221.7
#Mann= 4 ,-1 , 0
  4546.3     .17       0    4802     .15       0    4965     .09       0
  5019.8     .17       0
Bank Sta=4965,5019.8
XS Rating Curve= 0 ,0
Exp/Cntr=0.3,0.1

Type RM Length L Ch R = 1 ,13403   ,584,584,584
BEGIN DESCRIPTION:
LAKE CREEK TRIBUTARY NO. 3 22.0
END DESCRIPTION:
XS GIS Cut Line= 3
      3768504.18     10094678.77       3768212.4     10094890.83
      3767667.88     10095711.03
#Sta/Elev= 30
  4639.3  213.51  4681.9  211.75  4688.1  212.32  4717.4  210.36  4723.6  211.03
  4767.7  208.02  4773.9  208.77  4817.9   204.7  4853.5  202.68  4874.3  203.15
  4989.5  200.44  4996.2  197.36  5011.8  198.08  5024.3  200.08  5045.3  200.57
  5051.4  200.99  5132.3  206.74  5213.2  205.53  5264.4  206.06  5363.6  203.75
  5414.7  205.61  5470.8  206.14  5516.4  205.62    5538  206.96    5565  206.27
  5574.1  207.12  5696.5  204.43  5772.8  206.41  5925.9   213.1  5984.5  214.22
#Mann= 7 ,-1 , 0
  4639.3     .17       0  4989.5     .09       0  5024.3     .17       0
  5045.3     .15       0  5051.4     .17       0  5470.8     .15       0
  5772.8     .17       0
Bank Sta=4989.5,5024.3
XS Rating Curve= 0 ,0
Exp/Cntr=0.3,0.1

Type RM Length L Ch R = 1 ,12819   ,402,402,402
BEGIN DESCRIPTION:
LAKE CREEK TRIBUTARY NO. 3 21.0
END DESCRIPTION:
XS GIS Cut Line= 3
      3767967.83     10094511.09      3767691.71     10094736.04
      3767129.21     10095361.04
#Sta/Elev= 30
  4656.3  216.78  4706.6  213.24  4720.8  213.44    4821  206.24  4840.8  204.41
  4848.7  204.79  4890.4  200.89  4947.8  198.72  4968.6  198.99  4993.8  196.23
  5000.9  196.23  5011.7  198.72  5032.7  197.99    5061   198.6  5195.5   205.8
  5217.2  204.24  5259.8  203.12  5280.7  198.09  5288.2  198.43  5294.9   200.4
  5299.8  200.54  5309.1   200.6  5315.8  203.32  5415.2  202.26  5443.6  203.22
  5478.8  202.83  5557.2   205.7  5620.8   206.6    5762  212.37  5853.3  214.32
#Mann= 5 ,-1 , 0
  4656.3     .17       0    4821     .15       0  4968.6     .09       0
  5011.7     .15       0  5299.8     .17       0
Bank Sta=4968.6,5011.7
XS Rating Curve= 0 ,0
Exp/Cntr=0.3,0.1

Type RM Length L Ch R = 1 ,12417   ,446,446,446
BEGIN DESCRIPTION:
LAKE CREEK TRIBUTARY NO. 3 20.0
END DESCRIPTION:
XS GIS Cut Line= 3
      3767717.82     10094311.09      3767481.42     10094440.29
      3766917.88     10095061.04
#Sta/Elev= 30
  4730.6  209.96  4776.1  207.94  4782.3  208.91  4893.4  203.59  4935.7  198.62
  4967.3   198.1  4989.1  196.34    4995  192.55  5010.3  193.33    5017  196.42
  5038.7  198.93    5067  197.89  5130.6  199.12  5151.5  197.47  5194.1  201.92
  5212.8  202.66  5244.1  203.72  5250.9  204.78  5279.2  202.88  5364.4  203.94
  5513.1  201.61    5605  204.42  5711.1  205.95  5725.2  205.38    5732  206.41
  5753.6  206.34  5774.6  207.87    5782     207    5803  208.13  5838.4  207.68
#Mann= 5 ,-1 , 0
  4730.6     .17       0  4893.4     .15       0  4989.1     .09       0
    5017     .15       0  5212.8     .17       0
Bank Sta=4989.1,5017
XS Rating Curve= 0 ,0
Exp/Cntr=0.3,0.1

Type RM Length L Ch R = 1 ,11971   ,418,418,418
BEGIN DESCRIPTION:
LAKE CREEK TRIBUTARY NO. 3 19.0
END DESCRIPTION:
XS GIS Cut Line= 2
      3767769.81     10093850.63      3766442.31     10094454.52
#Sta/Elev= 30
  4367.4  207.68  4480.6   206.1  4642.5  204.93  4694.1  205.68  4710.1  204.47
  4745.7  204.09  4754.1  202.46  4809.5   199.4  4866.5   196.3  4935.7  197.47
  4981.8  196.33  4991.6  190.95  5004.8  191.79  5010.3  194.95  5017.7  196.11
  5056.5   196.5  5072.7  195.23  5154.2  198.68  5177.3  200.57  5246.1  201.82
  5336.3  200.34  5372.7   197.4  5447.4   201.2  5479.1  201.33  5493.5  202.76
  5511.1  202.38  5683.5  207.46  5706.6  206.39  5764.8  207.65  5825.8  206.64
#Mann= 6 ,-1 , 0
  4367.4     .11       0  4480.6     .17       0  4809.5     .15       0
  4981.8     .09       0  5017.7     .15       0  5246.1     .17       0
Bank Sta=4981.8,5017.7
XS Rating Curve= 0 ,0
Exp/Cntr=0.3,0.1

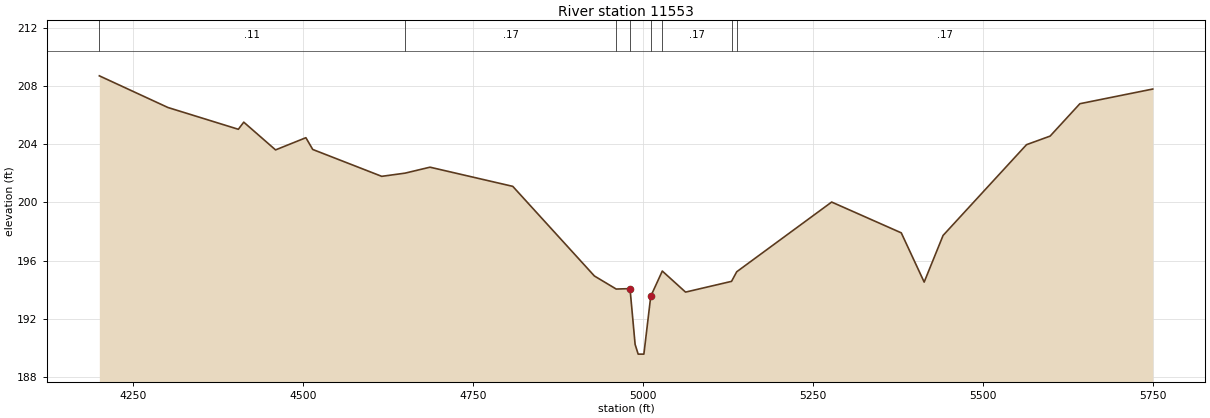
Type RM Length L Ch R = 1 ,11553   ,631,631,631
BEGIN DESCRIPTION:
LAKE CREEK TRIBUTARY NO. 3 18.0
END DESCRIPTION:
XS GIS Cut Line= 3
       3767957.3     10093631.88      3767170.88     10093767.29
      3766436.51     10093928.75
#Sta/Elev= 30
  4199.8  208.72  4300.7  206.54  4404.3  205.04  4412.3  205.53  4459.1  203.62
  4503.7  204.46  4513.8  203.65  4615.3   201.8  4649.6  202.02  4686.3  202.43
  4808.1  201.11  4928.2  194.94  4960.3  194.04  4980.6  194.07  4988.1  190.23
  4992.6  189.56    5001  189.56  5011.1  193.54  5028.1  195.28  5062.3  193.83
    5130  194.57  5137.6  195.23  5277.3  200.03  5379.7  197.91  5413.4  194.52
  5441.2  197.73    5564  203.98  5598.7  204.57  5642.5   206.8  5749.7  207.81
#Mann= 8 ,-1 , 0
  4199.8     .11       0  4649.6     .17       0  4960.3     .15       0
  4980.6     .09       0  5011.1     .15       0  5028.1     .17       0
    5130     .15       0  5137.6     .17       0
Bank Sta=4980.6,5011.1
XS Rating Curve= 0 ,0
Exp/Cntr=0.3,0.1