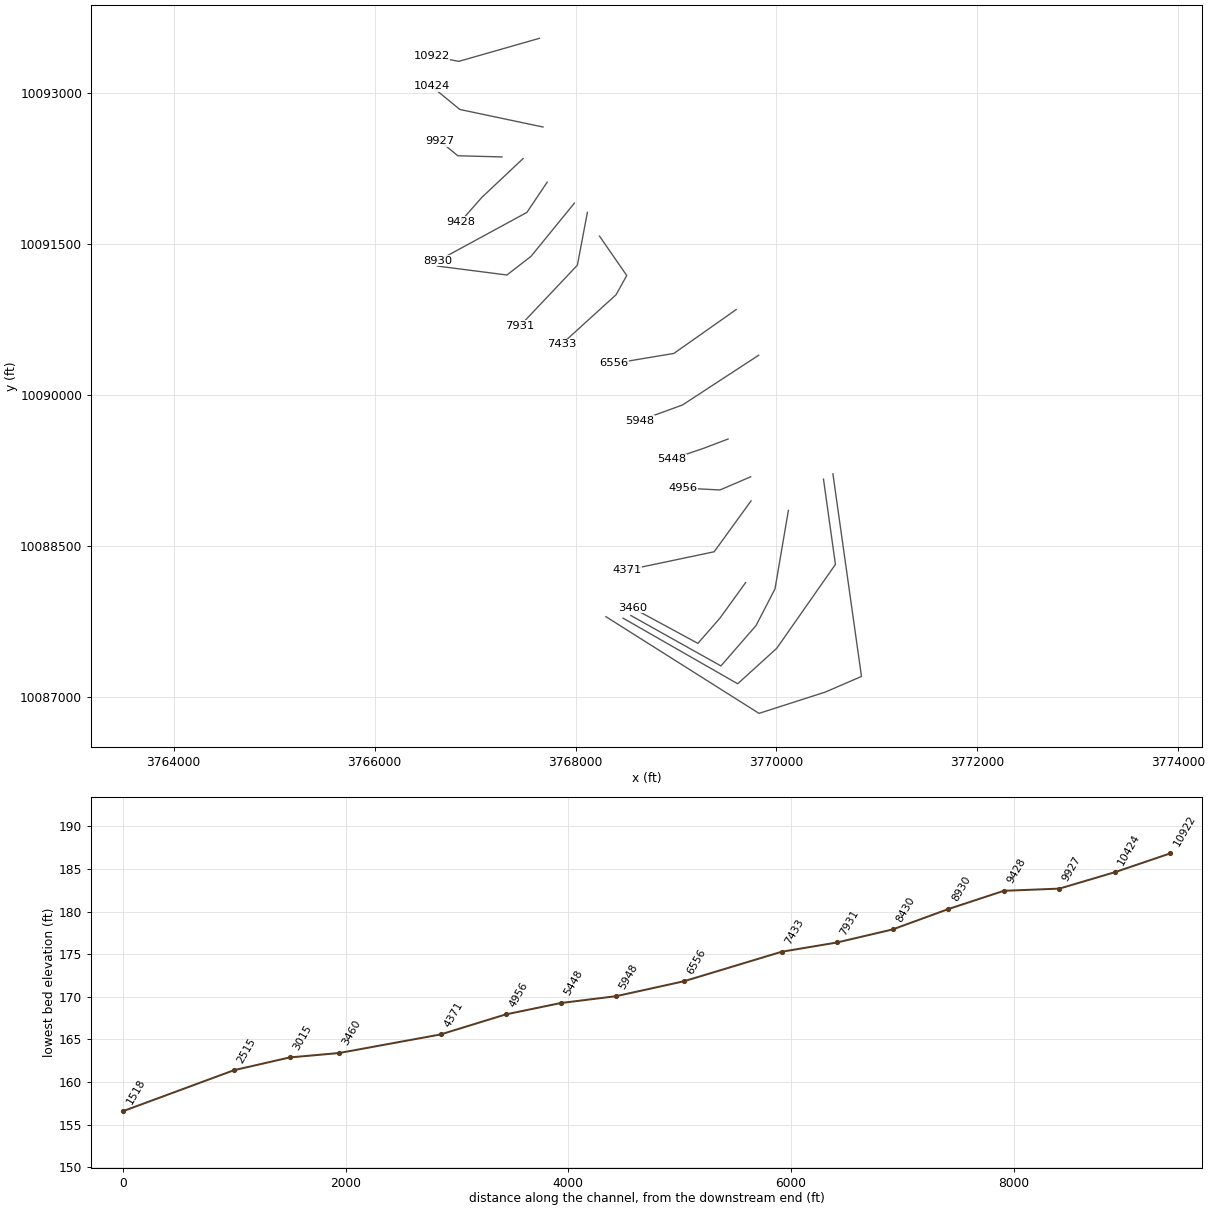
HEC-RAS study LAKE CREEK TRIBUTARY NO 3.prj: LAKE CREEK TRIBUTARY NO 3 Base Level Engineering

--- LAKE CREEK TRIBUTARY NO 3.g01 (geometry) --- (continued)

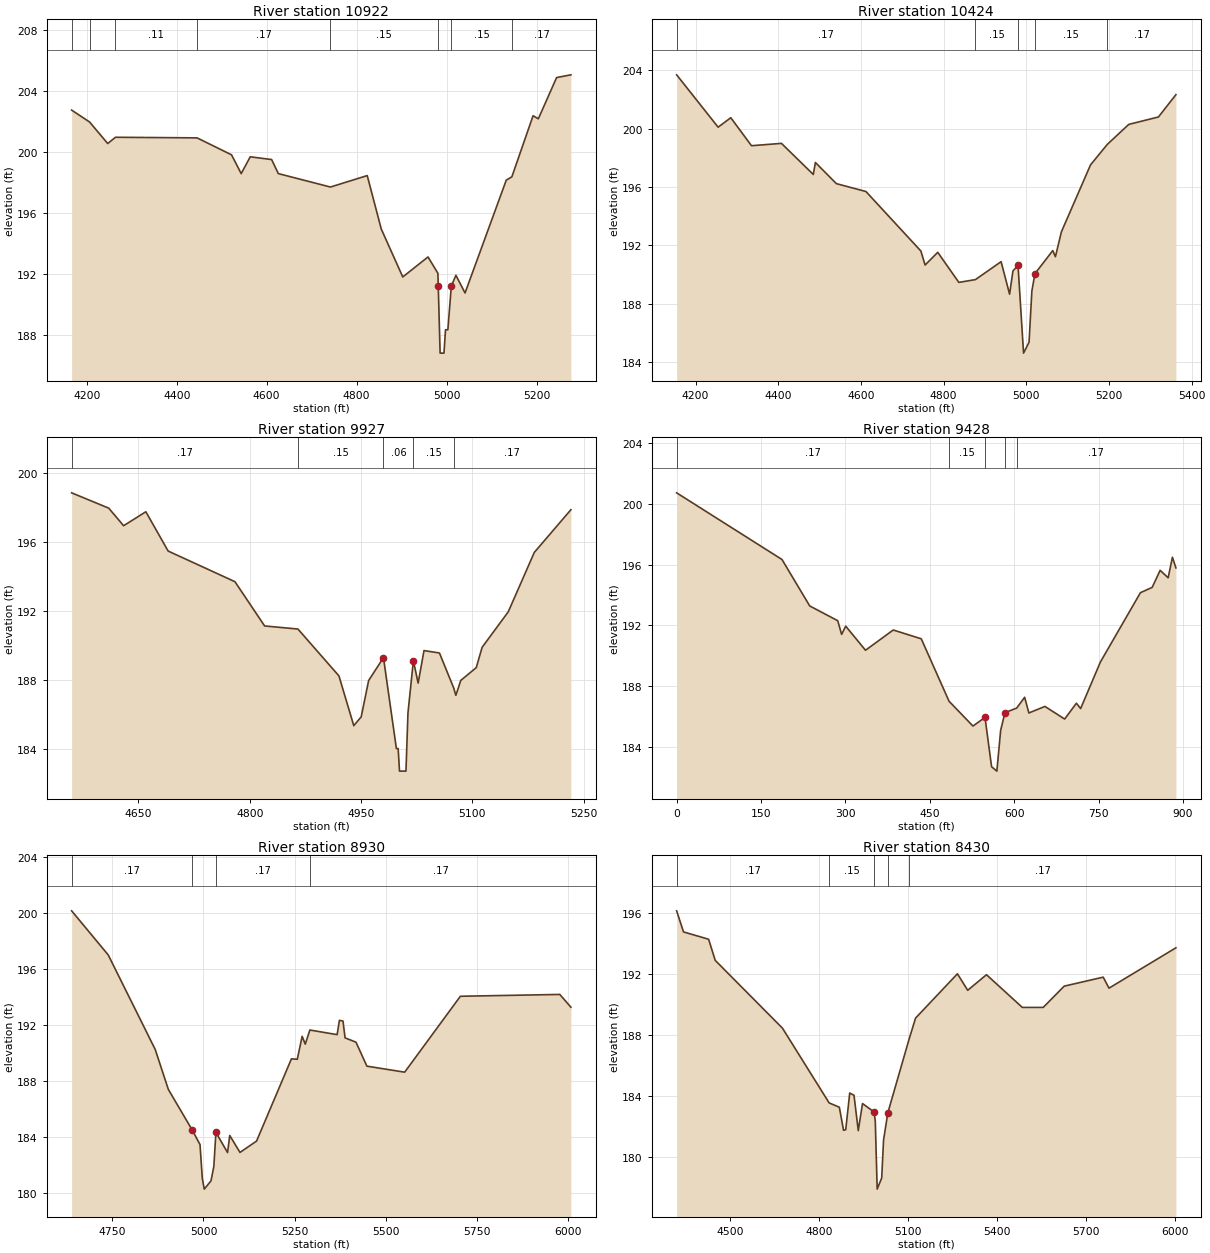
Type RM Length L Ch R = 1 ,10922   ,498,498,498
BEGIN DESCRIPTION:
LAKE CREEK TRIBUTARY NO. 3 17.0
END DESCRIPTION:
XS GIS Cut Line= 3
      3767639.65     10093538.13      3766838.08     10093309.65
       3766566.7     10093361.04
#Sta/Elev= 30
  4166.5  202.74  4206.4  201.96  4246.7  200.55  4263.9  200.96  4445.3  200.92
  4521.9  199.81  4543.4  198.58  4563.5  199.68    4611   199.5  4625.9  198.58
  4741.8   197.7  4823.5  198.45  4854.7  194.95  4902.5  191.81  4958.6  193.12
  4980.6  192.05 4981.36191.2332  4985.5  186.82  4994.1  186.82  4997.5  188.35
  5002.7  188.35  5010.4  191.21  5020.6  191.92  5040.9  190.76  5132.5  198.15
    5145  198.37  5192.1  202.37  5203.8  202.17  5244.4  204.87  5276.2  205.05
#Mann= 8 ,-1 , 0
  4166.5     .11       0  4206.4     .17       0  4263.9     .11       0
  4445.3     .17       0  4741.8     .15       0 4981.36     .09       0
  5010.4     .15       0    5145     .17       0
Bank Sta=4981.36,5010.4
XS Rating Curve= 0 ,0
Exp/Cntr=0.3,0.1

Type RM Length L Ch R = 1 ,10424   ,497,497,497
BEGIN DESCRIPTION:
LAKE CREEK TRIBUTARY NO. 3 16.0
END DESCRIPTION:
XS GIS Cut Line= 3
      3767676.06     10092657.92      3766848.28     10092832.09
      3766567.88     10093061.05
#Sta/Elev= 30
  4154.1  203.69  4254.5   200.1  4285.1  200.75  4335.2  198.83  4407.7  198.99
  4484.7  196.86  4489.8  197.68  4540.6  196.23  4612.1  195.69    4745  191.61
  4755.2  190.65  4785.8  191.52  4836.9  189.46  4876.9  189.65  4939.1  190.88
  4959.6  188.65  4967.7  190.24    4980  190.63  4993.4  184.61  5006.7  185.36
  5013.5  188.87    5021  190.06  5064.1  191.64  5070.5  191.22  5084.9  192.92
  5155.5  197.52    5196  198.92  5247.9  200.29  5319.7   200.8    5362  202.33
#Mann= 5 ,-1 , 0
  4154.1     .17       0  4876.9     .15       0    4980     .09       0
    5021     .15       0    5196     .17       0
Bank Sta=4980,5021
XS Rating Curve= 0 ,0
Exp/Cntr=0.3,0.1

Type RM Length L Ch R = 1 ,9927    ,499,499,499
BEGIN DESCRIPTION:
LAKE CREEK TRIBUTARY NO. 3 15.0
END DESCRIPTION:
XS GIS Cut Line= 3
      3767267.81     10092361.07      3766828.06     10092372.59
      3766647.84      10092519.8
#Sta/Elev= 30
  4560.1  198.85  4610.1  197.96  4630.1  196.94  4660.1  197.75  4690.1  195.47
  4780.1  193.69  4820.1  191.12    4865  190.94  4920.2  188.22  4940.2  185.33
  4950.2  185.84  4960.2  187.95  4980.2  189.28  4997.6     184    5000     184
  5001.8  182.69  5010.5  182.69  5013.2  186.07  5020.5   189.1  5026.9   187.8
  5034.8  189.69  5055.6  189.55  5074.8  187.52  5077.7  187.09  5084.4  187.96
  5105.2   188.7  5113.1  189.88  5148.3  191.94  5183.4  195.39  5232.7  197.87
#Mann= 5 ,-1 , 0
  4560.1     .17       0    4865     .15       0  4980.2     .06       0
  5020.5     .15       0  5074.8     .17       0
Bank Sta=4980.2,5020.5
XS Rating Curve= 0 ,0
Exp/Cntr=0.3,0.1

Type RM Length L Ch R = 1 ,9428    ,498,498,498
BEGIN DESCRIPTION:
LAKE CREEK TRIBUTARY NO. 3 14.0
END DESCRIPTION:
XS GIS Cut Line= 3
      3767478.17     10092345.41      3767067.42     10091959.51
       3766852.7     10091716.71
#Sta/Elev= 30
       0  200.71   187.3  196.33   236.6  193.28   286.4  192.31   293.3  191.41
   300.6  191.95   335.8  190.37   385.1   191.7   434.9  191.12   484.3  187.02
   526.8  185.39   548.2  185.96   559.9  182.72   569.3  182.43     576   185.1
   583.6  186.27   604.5  186.57   618.7  187.28   626.2  186.25   654.7  186.68
   689.8  185.85   710.7  186.89   718.2  186.54   753.4   189.6   824.5  194.15
   845.4   194.5   859.6  195.62   873.8  195.13   881.4  196.48   887.6  195.78
#Mann= 5 ,-1 , 0
       0     .17       0   484.3     .15       0   548.2     .06       0
   583.6     .15       0   604.5     .17       0
Bank Sta=548.2,583.6
XS Rating Curve= 0 ,0
Exp/Cntr=0.3,0.1

Type RM Length L Ch R = 1 ,8930    ,500,500,500
BEGIN DESCRIPTION:
LAKE CREEK TRIBUTARY NO. 3 13.0
END DESCRIPTION:
XS GIS Cut Line= 3
      3767717.86     10092111.09      3767515.97     10091810.62
      3766629.23      10091329.8
#Sta/Elev= 30
    4638  200.16  4738.5  197.01  4867.5  190.26  4903.5  187.41  4969.5  184.49
  4990.5  183.47  4996.7  181.07  5002.1  180.29  5020.6  180.88  5028.4  181.91
  5034.1  184.34  5066.1   182.9  5072.1  184.12  5100.2  182.91  5145.7  183.72
  5241.4  189.59  5257.5  189.56  5270.9   191.2  5279.4  190.64  5292.1  191.65
  5366.9  191.32  5373.2  192.34    5383  192.29  5388.7  191.09  5418.7  190.78
  5448.6  189.07  5552.3  188.64  5705.3  194.06  5978.2  194.19  6008.7  193.28
#Mann= 4 ,-1 , 0
    4638     .17       0  4969.5     .06       0  5034.1     .17       0
  5292.1     .17       0
Bank Sta=4969.5,5034.1
XS Rating Curve= 0 ,0
Exp/Cntr=0.3,0.1

Type RM Length L Ch R = 1 ,8430    ,499,499,499
BEGIN DESCRIPTION:
LAKE CREEK TRIBUTARY NO. 3 12.0
END DESCRIPTION:
XS GIS Cut Line= 4
      3767988.58      10091902.7      3767557.36     10091374.97
      3767316.71     10091189.16      3766623.98     10091277.71
#Sta/Elev= 30
  4318.5  196.11  4341.7  194.73  4426.4  194.25  4448.6  192.87  4675.5  188.43
  4832.9  183.54  4867.2  183.26  4881.5  181.75  4888.8  181.79  4902.3  184.19
  4916.7  184.04  4931.1  181.73  4945.4   183.5 4984.42182.9494  4988.5  182.34
  4994.9   177.9  5010.1  178.63  5016.4  181.12  5030.9   182.9  5102.3   187.7
  5124.3  189.09  5265.5  191.99  5300.2  190.91  5363.5  191.93  5484.4  189.79
  5554.9  189.79  5625.5  191.18  5757.2  191.77  5776.7  191.05  6002.4  193.69
#Mann= 5 ,-1 , 0
  4318.5     .17       0  4832.9     .15       0 4984.42     .06       0
  5030.9     .15       0  5102.3     .17       0
Bank Sta=4984.42,5030.9
XS Rating Curve= 0 ,0
Exp/Cntr=0.3,0.1

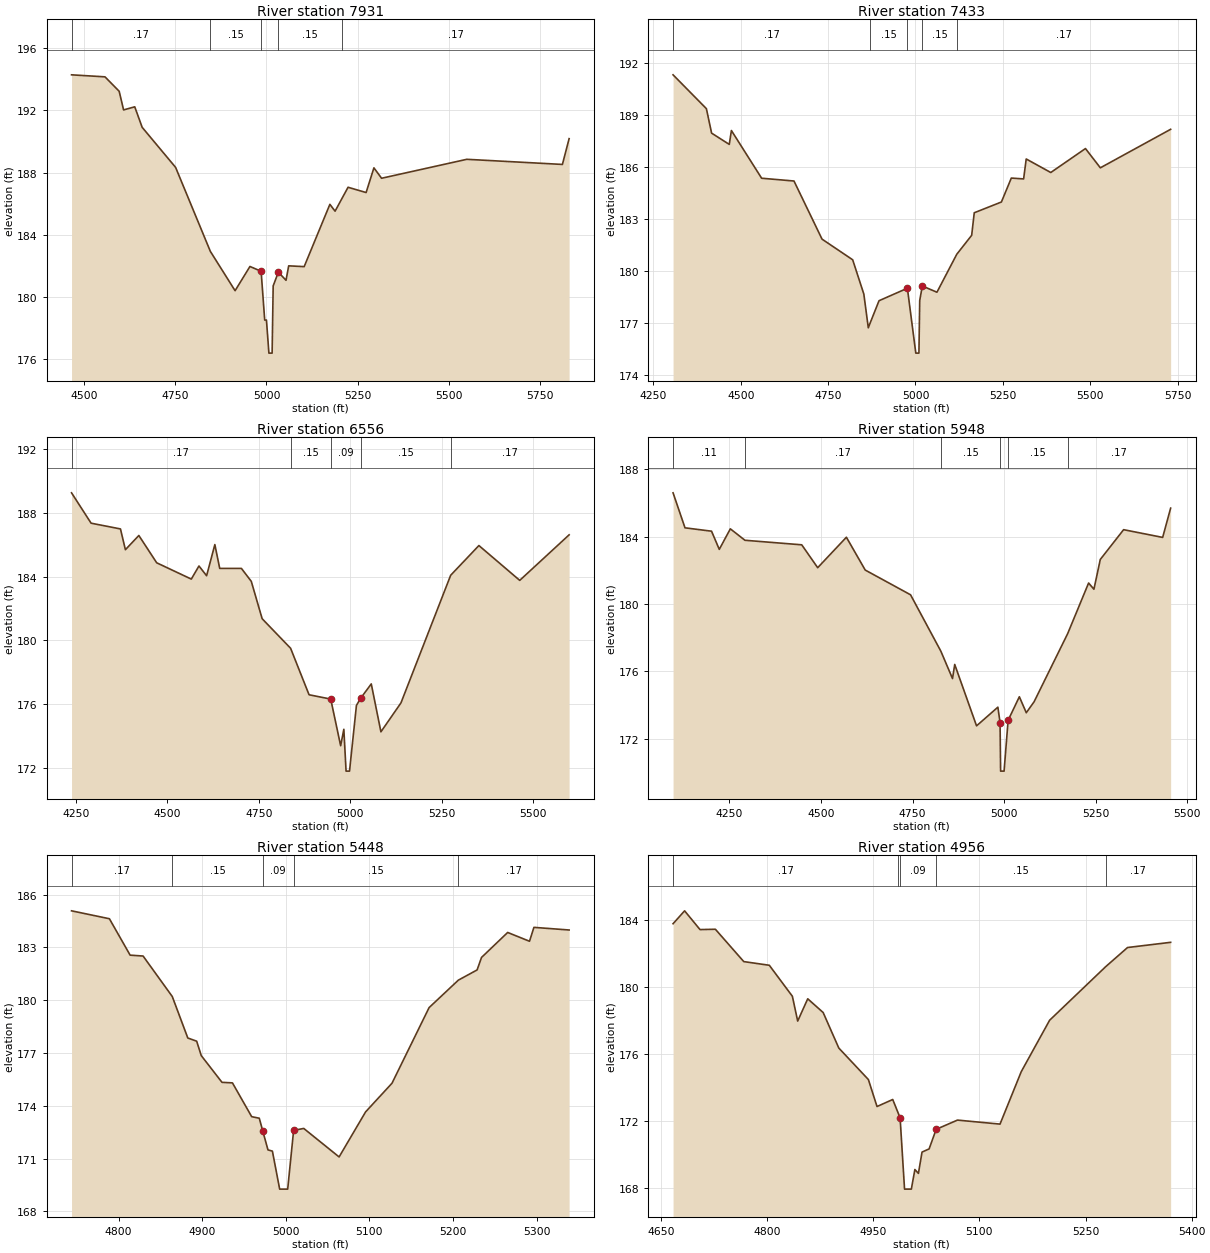
Type RM Length L Ch R = 1 ,7931    ,498,498,498
BEGIN DESCRIPTION:
LAKE CREEK TRIBUTARY NO. 3 11.0
END DESCRIPTION:
XS GIS Cut Line= 3
      3768117.85     10091811.08       3768018.1     10091286.69
      3767447.94     10090685.03
#Sta/Elev= 30
  4466.2  194.29  4557.8  194.16  4596.7  193.23  4608.7  192.03  4639.3  192.23
  4659.6  190.91  4751.2  188.33  4846.4  182.92  4914.1  180.39  4954.8  181.95
  4985.4  181.64  4995.2   178.5    5000   178.5  5006.7  176.37  5015.5  176.37
  5018.4   180.7  5032.6  181.58  5053.6  181.06  5060.9  181.99  5103.3  181.94
  5173.7  185.95  5187.9  185.51  5207.1  186.34  5223.5  187.05  5272.9  186.71
  5294.3   188.3  5315.3  187.63  5548.7  188.85  5810.5  188.52  5828.9  190.18
#Mann= 5 ,-1 , 0
  4466.2     .17       0  4846.4     .15       0  4985.4     .09       0
  5032.6     .15       0  5207.1     .17       0
Bank Sta=4985.4,5032.6
XS Rating Curve= 0 ,0
Exp/Cntr=0.3,0.1

Type RM Length L Ch R = 1 ,7433    ,877,877,877
BEGIN DESCRIPTION:
LAKE CREEK TRIBUTARY NO. 3 10.0
END DESCRIPTION:
XS GIS Cut Line= 4
      3768238.56     10091574.61      3768509.42     10091183.96
       3768403.1     10090993.04      3767862.06      10090502.5
#Sta/Elev= 30
  4306.1  191.32  4401.5  189.37  4416.4  187.96    4467  187.31  4473.1  188.11
  4559.6  185.36  4652.2   185.2  4732.5  181.85  4820.2  180.66  4852.2  178.68
  4864.9  176.74  4870.9  177.05  4895.6   178.3  4976.8  179.02  5000.9  175.28
  5009.8  175.28  5012.1  178.31  5019.5  179.15  5061.4  178.79  5118.2  180.98
  5160.8  182.07  5168.2  183.37  5245.9  183.99  5274.3  185.37  5309.5  185.32
  5316.9  186.47  5387.2  185.69  5486.5  187.07  5529.1  185.96  5730.3  188.18
#Mann= 5 ,-1 , 0
  4306.1     .17       0  4870.9     .15       0  4976.8     .06       0
  5019.5     .15       0  5118.2     .17       0
Bank Sta=4976.8,5019.5
XS Rating Curve= 0 ,0
Exp/Cntr=0.3,0.1

Type RM Length L Ch R = 1 ,6556    ,608,608,608
BEGIN DESCRIPTION:
LAKE CREEK TRIBUTARY NO. 3 9.0
END DESCRIPTION:
XS GIS Cut Line= 3
      3769598.28     10090845.57      3768978.52      10090410.7
      3768384.82     10090311.75
#Sta/Elev= 30
  4238.8  189.24  4292.2  187.34  4372.4  186.98  4385.9  185.68  4422.6  186.57
  4471.4  184.86  4565.9  183.84  4586.8  184.66  4607.7  184.05  4630.2     186
  4643.5  184.51  4702.7  184.51  4729.7   183.7  4759.4  181.36  4837.1  179.51
  4887.5   176.6  4946.7  176.33  4973.8  173.41  4982.5  174.44  4988.6  171.82
    4998  171.82  5016.9  175.93  5028.1  176.37  5057.4  177.28  5083.8  174.28
  5138.5  176.09  5274.3  184.08  5351.4  185.94  5462.9  183.76  5597.8  186.61
#Mann= 5 ,-1 , 0
  4238.8     .17       0  4837.1     .15       0  4946.7     .09       0
  5028.1     .15       0  5274.3     .17       0
Bank Sta=4946.7,5028.1
XS Rating Curve= 0 ,0
Exp/Cntr=0.3,0.1

Type RM Length L Ch R = 1 ,5948    ,500,500,500
BEGIN DESCRIPTION:
LAKE CREEK TRIBUTARY NO. 3 8.0
END DESCRIPTION:
XS GIS Cut Line= 3
       3769822.3     10090392.48      3769064.72     10089899.23
      3768637.34     10089744.02
#Sta/Elev= 30
    4096  186.61  4128.6  184.53  4201.1  184.33  4222.2  183.25  4252.4  184.47
  4292.3  183.79  4447.4  183.52  4490.9  182.16  4569.3  183.97  4620.7  182.02
  4744.5  180.55  4827.2   177.2  4859.1  175.57  4865.1  176.41  4924.7  172.76
  4982.9  173.87  4988.9  172.96  4990.4  170.07  4999.9  170.07  5010.9  173.09
  5041.6  174.49  5060.5  173.54  5081.8  174.19  5173.5  178.24  5230.7  181.25
  5245.2  180.88  5262.6  182.65  5326.3  184.42  5432.9  183.96  5454.7   185.7
#Mann= 6 ,-1 , 0
    4096     .11       0  4292.3     .17       0  4827.2     .15       0
  4988.9     .09       0  5010.9     .15       0  5173.5     .17       0
Bank Sta=4988.9,5010.9
XS Rating Curve= 0 ,0
Exp/Cntr=0.3,0.1

Type RM Length L Ch R = 1 ,5448    ,492,492,492
BEGIN DESCRIPTION:
LAKE CREEK TRIBUTARY NO. 3 7.0
END DESCRIPTION:
XS GIS Cut Line= 3
      3769517.89     10089561.09      3769278.21     10089470.29
       3768957.3     10089361.03
#Sta/Elev= 30
  4743.7  185.08    4789  184.63  4813.8  182.56  4829.3  182.51  4864.2  180.21
  4882.8  177.85  4893.4  177.67  4898.9  176.85  4923.7  175.33  4936.2   175.3
  4959.2  173.38  4968.3  173.29 4972.44172.5735  4978.7  171.49    4984  171.42
  4992.7  169.26  5002.3  169.26  5009.4   172.6  5021.5  172.71  5063.8  171.09
  5095.5  173.65  5127.1  175.28  5171.5  179.58  5206.5  181.14  5228.9  181.72
  5234.2  182.43  5265.5  183.85  5291.6  183.35  5296.9  184.14    5339  183.99
#Mann= 5 ,-1 , 0
  4743.7     .17       0  4864.2     .15       0 4972.44     .09       0
  5009.4     .15       0  5206.5     .17       0
Bank Sta=4972.44,5009.4
XS Rating Curve= 0 ,0
Exp/Cntr=0.3,0.1

Type RM Length L Ch R = 1 ,4956    ,585,585,585
BEGIN DESCRIPTION:
LAKE CREEK TRIBUTARY NO. 3 6.0
END DESCRIPTION:
XS GIS Cut Line= 3
      3769742.89     10089186.09      3769436.84     10089055.35
      3769067.05     10089074.76
#Sta/Elev= 30
  4667.2  183.77  4683.5  184.54  4705.3  183.42    4727  183.44  4767.1  181.51
  4803.2  181.29  4835.8  179.44  4843.3  177.96  4857.5  179.29  4879.3  178.47
  4901.4  176.35  4943.2  174.47  4955.4  172.86  4977.6  173.28  4985.4  172.46
    4988  172.19  4994.3  167.93  5003.9  167.93  5008.9   169.1  5013.9  168.87
    5019  170.14    5029  170.33    5039   171.5  5069.1  172.05  5129.2  171.81
  5159.2  174.94  5199.3  178.01  5278.6  181.21  5309.4  182.35  5370.3  182.66
#Mann= 5 ,-1 , 0
  4667.2     .17       0  4985.4     .15       0    4988     .09       0
    5039     .15       0  5278.6     .17       0
Bank Sta=4988,5039
XS Rating Curve= 0 ,0
Exp/Cntr=0.3,0.1

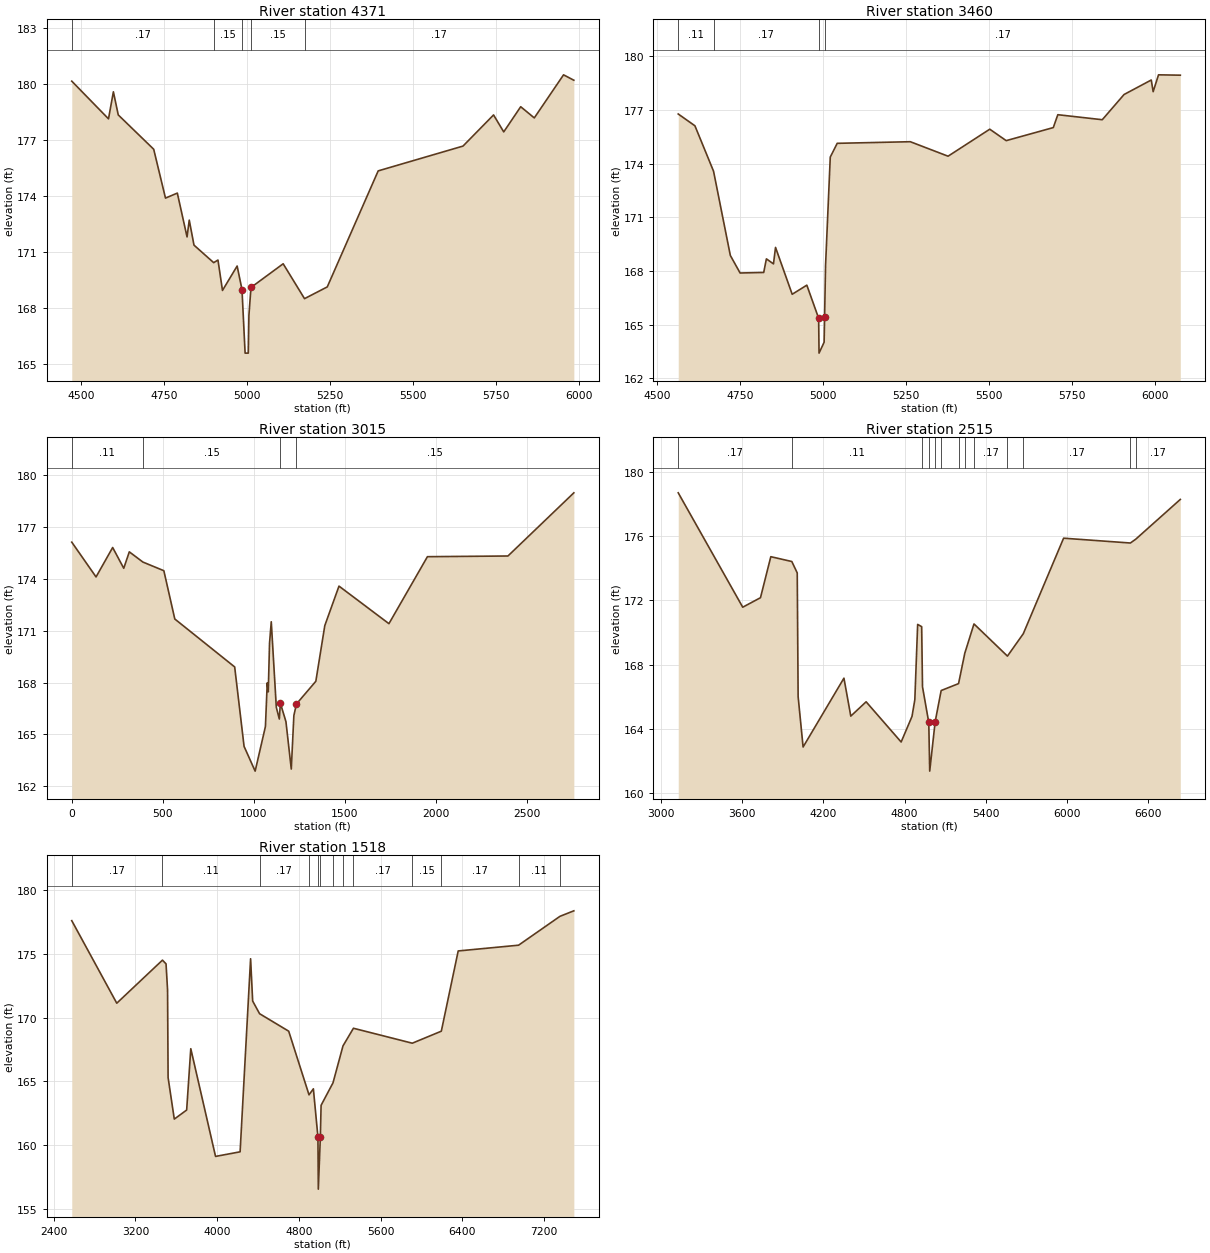
Type RM Length L Ch R = 1 ,4371    ,911,911,911
BEGIN DESCRIPTION:
Mapping XS 97796741
END DESCRIPTION:
XS GIS Cut Line= 3
      3769746.75     10088947.16      3769379.57     10088441.95
      3768511.28     10088259.97
#Sta/Elev= 30
  4471.5  180.16  4582.1  178.14  4596.8  179.59  4611.5  178.35  4718.2  176.51
  4753.7  173.89  4789.3  174.16  4818.6  171.81  4825.2  172.71  4839.5  171.37
  4898.8  170.43  4911.7  170.57  4925.3  168.94  4969.4  170.25    4984  168.99
  4993.4  165.58    5003  165.58  5004.9  167.61  5011.1   169.1    5108  170.37
  5172.3   168.5  5240.8  169.13  5394.1  175.35  5649.5  176.68  5741.5  178.35
  5772.1  177.44  5823.2  178.79  5864.1  178.19  5952.2   180.5  5983.2  180.21
#Mann= 5 ,-1 , 0
  4471.5     .17       0  4898.8     .15       0    4984     .09       0
  5011.1     .15       0  5172.3     .17       0
Bank Sta=4984,5011.1
XS Rating Curve= 0 ,0
Exp/Cntr=0.3,0.1

Type RM Length L Ch R = 1 ,3460    ,445,445,445
BEGIN DESCRIPTION:
LAKE CREEK TRIBUTARY NO. 3 5.0
END DESCRIPTION:
XS GIS Cut Line= 4
      3769692.88     10088136.11      3769436.51     10087782.58
      3769217.75     10087532.91      3768563.14      10087886.2
#Sta/Elev= 30
  4563.3  176.77  4613.6  176.11  4669.7  173.57  4720.3  168.86  4749.7  167.88
  4820.8  167.91  4828.9  168.67  4850.2  168.39  4856.4  169.31  4906.6  166.69
  4950.7   167.2  4986.3  165.35  4987.5   163.4  5002.8  164.01  5004.2 165.407
  5007.1   168.3  5021.3  174.36  5042.2  175.13  5262.4  175.22  5376.2  174.41
  5501.8  175.92  5551.3  175.28  5693.2  176.01  5706.8  176.73  5840.7  176.45
  5906.4  177.86  5988.3  178.67    5994  178.02  6010.2  178.96  6075.8  178.94
#Mann= 4 ,-1 , 0
  4563.3     .11       0  4669.7     .17       0  4986.3     .09       0
  5004.2     .17       0
Bank Sta=4986.3,5004.2
XS Rating Curve= 0 ,0
Exp/Cntr=0.3,0.1

Type RM Length L Ch R = 1 ,3015    ,500,500,500
BEGIN DESCRIPTION:
LAKE CREEK TRIBUTARY NO. 3 4.0
END DESCRIPTION:
XS GIS Cut Line= 5
      3770118.45     10088852.48      3769985.35     10088074.35
      3769796.61      10087709.9      3769446.92     10087308.96
      3768551.09     10087808.96
#Sta/Elev= 30
       0  176.11   133.3   174.1   224.6   175.8   285.5   174.6   315.9  175.55
   390.5  174.96   505.6  174.46   565.7  171.67   894.5   168.9   946.1  164.31
  1006.9  162.88  1063.4  165.46  1073.3  167.98  1078.9  167.46  1085.9  170.27
  1095.4  171.51  1123.2  166.56  1139.7  165.89  1145.3  166.81    1176  165.74
  1205.3     163  1219.5  166.09  1233.7  166.76  1340.1  168.07  1389.4  171.29
  1467.3  173.57  1741.5   171.4  1952.9  175.27    2395  175.31  2756.8  178.96
#Mann= 4 ,-1 , 0
       0     .11       0   390.5     .15       0  1145.3     .09       0
  1233.7     .15       0
Bank Sta=1145.3,1233.7
XS Rating Curve= 0 ,0
Exp/Cntr=0.3,0.1

Type RM Length L Ch R = 1 ,2515    ,997,997,997
BEGIN DESCRIPTION:
LAKE CREEK TRIBUTARY NO. 3 3.0
END DESCRIPTION:
XS GIS Cut Line= 5
      3770467.76     10089163.07      3770586.53     10088316.43
      3770002.15     10087483.52      3769613.59     10087131.87
      3768472.97     10087782.91
#Sta/Elev= 30
  3127.6  178.68  3604.2  171.57  3735.3  172.16  3811.7  174.71  3966.9  174.41
  4006.9   173.7  4013.5  166.01  4050.2  162.88    4352  167.16  4402.6   164.8
  4515.9  165.69  4774.7  163.19  4854.9  164.78  4875.8  165.82  4896.7   170.5
  4926.3  170.36  4932.5  166.62 4978.86164.4031  4985.8  161.38    5026  164.45
  5070.4  166.39  5198.9  166.82    5245  168.71  5312.9  170.53  5560.1  168.53
  5677.1  169.92  5975.1  175.86  6468.5  175.56  6508.4   175.8  6837.4  178.27
#Mann= 13 ,-1 , 0
  3127.6     .17       0  3966.9     .11       0  4926.3     .17       0
 4978.86     .09       0    5026     .17       0  5070.4     .15       0
  5198.9     .17       0    5245     .15       0  5312.9     .17       0
  5560.1     .15       0  5677.1     .17       0  6468.5     .11       0
  6508.4     .17       0
#Block Obstruct= 2 , 0
         4916.44  171.19
Bank Sta=4978.86,5026
XS Rating Curve= 0 ,0
Exp/Cntr=0.3,0.1

Type RM Length L Ch R = 1 ,1518    ,0,0,0
BEGIN DESCRIPTION:
LAKE CREEK TRIBUTARY NO. 3 1.0
END DESCRIPTION:
XS GIS Cut Line= 5
      3770561.51     10089215.16      3770845.91     10087204.39
      3770484.67     10087049.07      3769825.97     10086837.99
      3768301.93     10087798.01
#Sta/Elev= 30
    2576  177.58  3016.7  171.12  3464.1  174.49  3499.2   174.2  3514.1  172.16
  3519.4   165.3    3580  162.05  3701.2  162.76  3741.6  167.56    3984  159.13
  4224.6  159.49  4327.3   174.6  4347.5  171.29  4415.1   170.3  4700.5  168.93
  4899.4  163.95  4942.1  164.42  4986.7  160.65  4990.5  156.57 5010.33160.6386
  5017.7  163.13  5134.4  164.89  5232.2  167.78  5334.5  169.16  5910.8  167.99
  6195.1  168.93  6360.4  175.21  6951.6  175.66    7357  177.92  7492.9  178.35
#Mann= 13 ,-1 , 0
    2576     .17       0  3464.1     .11       0  4415.1     .17       0
  4899.4     .15       0  4986.7     .09       0 5010.33     .15       0
  5134.4     .17       0  5232.2     .15       0  5334.5     .17       0
  5910.8     .15       0  6195.1     .17       0  6951.6     .11       0
    7357     .17       0
#Block Obstruct= 2 , 0
         4328.84  174.61
Bank Sta=4986.7,5010.33
XS Rating Curve= 0 ,0
Exp/Cntr=0.3,0.1

Chan Stop Cuts=-1
Use User Specified Reach Order=0
Composite Channel Slope=5