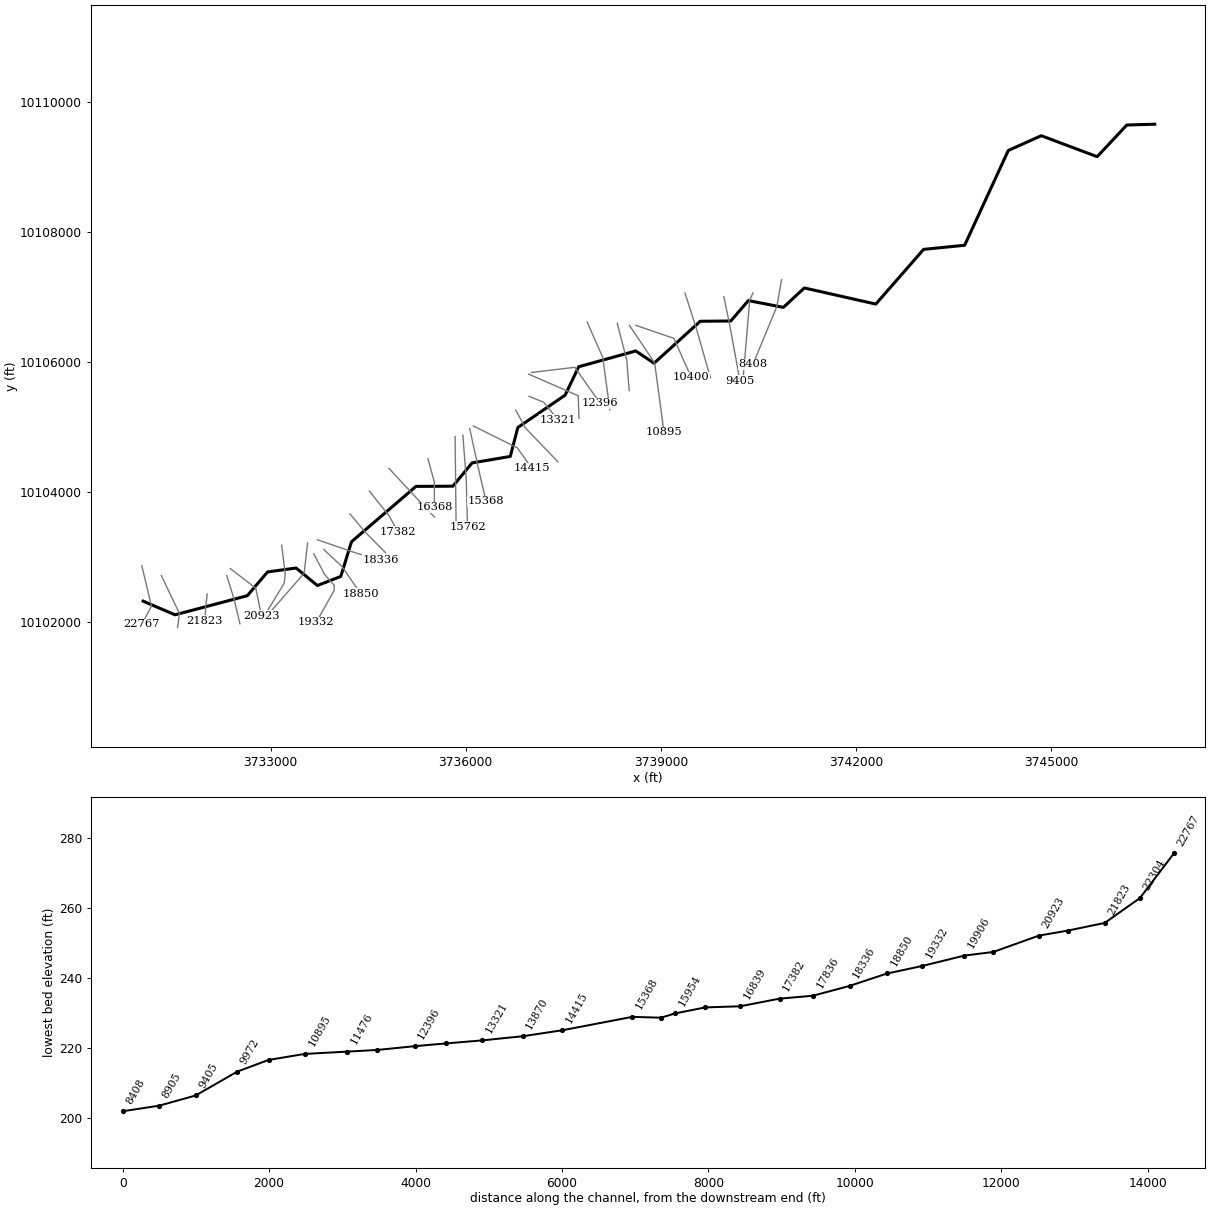
--- LAKE CREEK TRIBUTARY NO 4.prj (project) ---

Proj Title=LAKE CREEK TRIBUTARY NO 4 Base Level Engineering
Current Plan=p01
Default Exp/Contr=0.3,0.1
English Units
Geom File=g01
Flow File=f01
Plan File=p01
Y Axis Title=Elevation
X Axis Title(PF)=Main Channel Distance
X Axis Title(XS)=Station
BEGIN DESCRIPTION:
LAKE CREEK TRIBUTARY NO 4
END DESCRIPTION:
DSS Export Rating Curves= 0
DSS Export Rating Curve Sorted= 0
DSS Export Volume Flow Curves= 0
DXF OffsetX= 0
DXF OffsetY= 0
DXF ScaleX= 1
DXF ScaleY= 10

--- LAKE CREEK TRIBUTARY NO 4.p01 (plan) ---

Plan Title=Multiple Run
Short Identifier=Multiple
Geom File=g01
Flow File=f01
Subcritical Flow
K Sum by GR= 0
Std Step Tol= 0.01
Critical Tol= 0.01
Num of Std Step Trials= 20
Max Error Tol= 0.3
Flow Tol Ratio= 0.001
Split Flow NTrial= 30
Split Flow Tol= 0.02
Split Flow Ratio= 0.02
Log Output Level= 0
Friction Slope Method= 1
Unsteady Friction Slope Method= 2
Unsteady Bridges Friction Slope Method= 1
Parabolic Critical Depth
Global Vel Dist=  1 , 1 , 1
Global Log Level= 0
CheckData=True
Encroach Param= -1, 0, 0, 0
BEGIN DESCRIPTION:
Multiple Run
END DESCRIPTION:

--- LAKE CREEK TRIBUTARY NO 4.f01 (steady flow) ---

Flow Title=Multiple
Program Version=4.10
Number of Profiles= 7
Profile Names=10-year,25-year,50-year,1pct_min,100-year,1pct_plu,500-year
River Rch & RM=LAKE CREEK TRIBU,Reach-1         ,22767
    1004    1401    1934     878    2652    8009    5151
River Rch & RM=LAKE CREEK TRIBU,Reach-1         ,18850
    1236    1731    2392    1085    3276    9893    6362
River Rch & RM=LAKE CREEK TRIBU,Reach-1         ,11888
    1678    2370    3295    1501    4533   13689    8879
River Rch & RM=LAKE CREEK TRIBU,Reach-1         ,6495
    2017    2875    4020    1841    5561   16794   11015
River Rch & RM=LAKE CREEK TRIBU,Reach-1         ,4513
    2086    2969    4148    1897    5729   17301   11314
Boundary for River Rch & Prof#=LAKE CREEK TRIBU,Reach-1         , 1
Up Type= 0
Dn Type= 3
Dn Slope=0.005
Boundary for River Rch & Prof#=LAKE CREEK TRIBU,Reach-1         , 2
Up Type= 0
Dn Type= 3
Dn Slope=0.005
Boundary for River Rch & Prof#=LAKE CREEK TRIBU,Reach-1         , 3
Up Type= 0
Dn Type= 3
Dn Slope=0.005
Boundary for River Rch & Prof#=LAKE CREEK TRIBU,Reach-1         , 4
Up Type= 0
Dn Type= 3
Dn Slope=0.005
Boundary for River Rch & Prof#=LAKE CREEK TRIBU,Reach-1         , 5
Up Type= 0
Dn Type= 3
Dn Slope=0.005
Boundary for River Rch & Prof#=LAKE CREEK TRIBU,Reach-1         , 6
Up Type= 0
Dn Type= 3
Dn Slope=0.005
Boundary for River Rch & Prof#=LAKE CREEK TRIBU,Reach-1         , 7
Up Type= 0
Dn Type= 3
Dn Slope=0.005
DSS Import GetInterval= 0
DSS Import GetPeak= 0
DSS Import FillOption= 0

--- LAKE CREEK TRIBUTARY NO 4.g01 (geometry) ---

Geom Title=Existing Conditions
Program Version=4.10

River Reach=LAKE CREEK TRIBU,Reach-1
Reach XY= 30
      3731038.23     10102316.84      3731527.87      10102106.3
      3732640.54     10102400.24      3732951.66       10102766.
      3733390.83     10102826.35      3733718.64     10102556.96
      3734078.23     10102696.84      3734242.69     10103230.29
      3735234.65     10104082.78      3735801.92     10104085.82
      3736097.52     10104444.01      3736685.18     10104543.76
      3736801.63       10104989.       3737528.5     10105486.72
      3737737.47     10105924.04      3738615.14     10106167.17
      3738896.71     10105978.36      3739606.65     10106624.03
      3740076.65     10106628.38       3740347.1     10106942.28
      3740885.85       10106838.      3741208.23     10107136.84
      3742307.45     10106888.73      3743042.72     10107730.55
      3743673.96     10107793.99      3744345.07     10109252.67
       3744852.6     10109480.28      3745712.18     10109157.11
      3746168.18     10109644.76      3746598.23     10109656.84

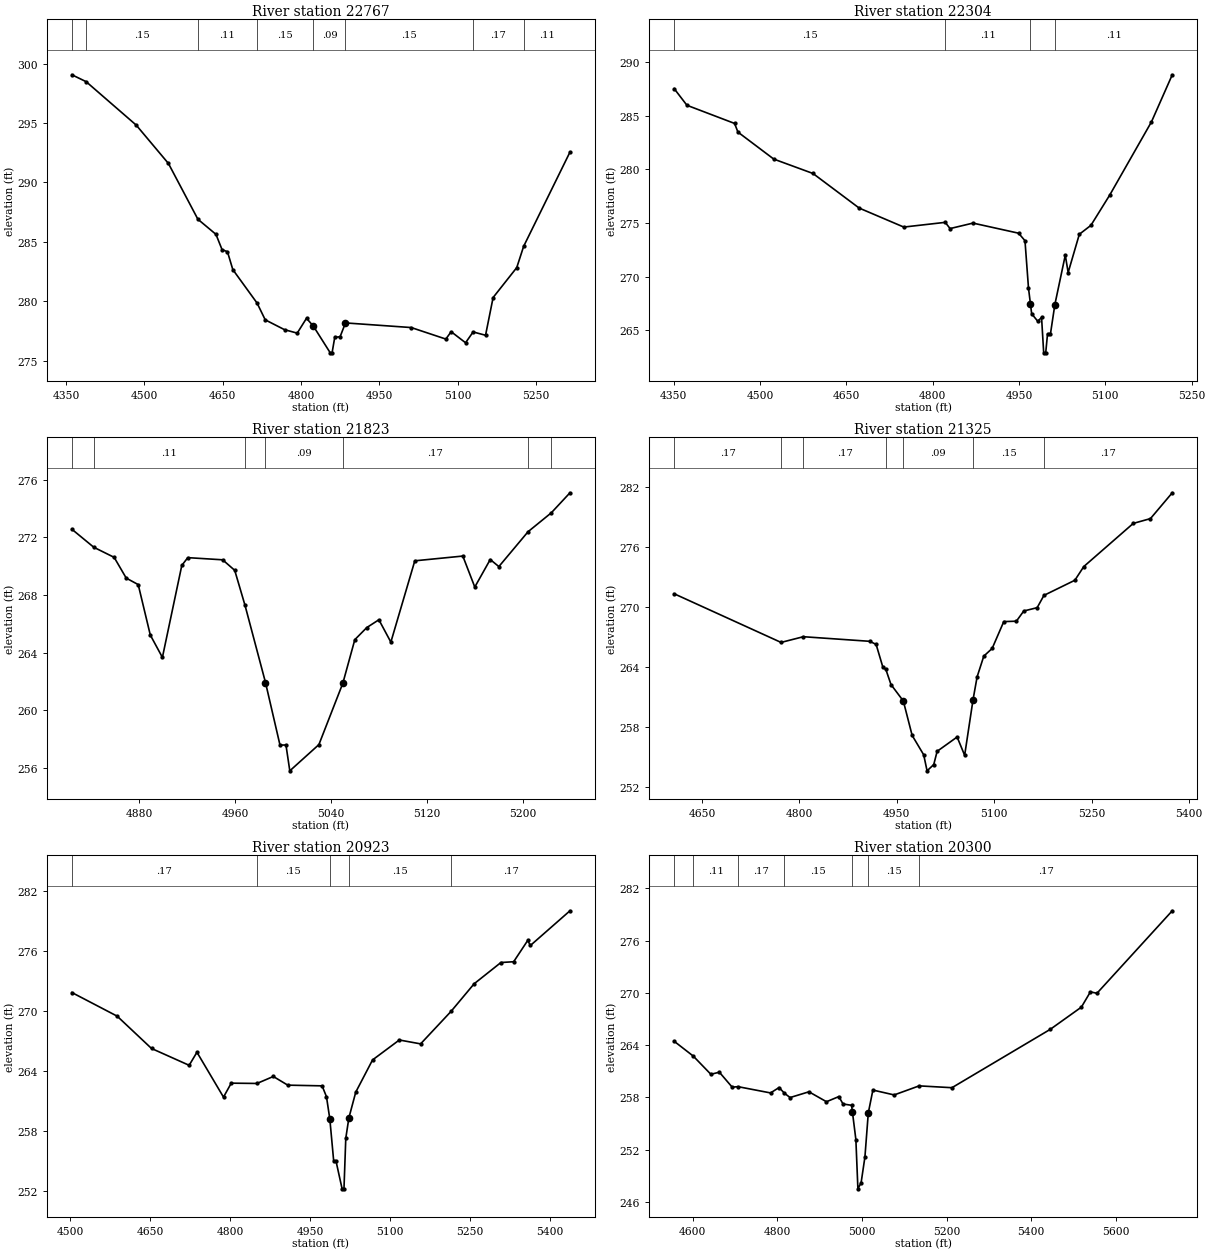
Type RM Length L Ch R = 1 ,22767   ,463,463,463
BEGIN DESCRIPTION:
LAKE CREEK TRIBUTARY NO. 4 43.0
END DESCRIPTION:
XS GIS Cut Line= 3
      3731017.86     10102861.03       3731166.3     10102239.51
      3731017.87      10101961.1
#Sta/Elev= 30
    4361  299.07  4388.3  298.49  4484.3  294.83    4546   291.6  4602.5   286.9
  4637.1  285.63  4648.8  284.34  4659.1  284.17  4669.4  282.66  4715.9  279.84
  4731.5  278.43  4768.5   277.6  4792.8  277.31  4810.6  278.56  4823.6  277.91
  4856.1  275.65  4859.6  275.65  4864.7  276.95    4875  277.01  4885.3  278.17
  5011.3  277.78  5077.6  276.81  5087.8  277.43  5115.4   276.5  5129.9  277.41
  5153.7  277.13  5168.2  280.31  5213.5  282.83  5226.7  284.62  5315.5  292.56
#Mann= 8 ,-1 , 0
    4361     .11       0  4388.3     .15       0  4602.5     .11       0
  4715.9     .15       0  4823.6     .09       0  4885.3     .15       0
  5129.9     .17       0  5226.7     .11       0
Bank Sta=4823.6,4885.3
XS Rating Curve= 0 ,0
Exp/Cntr=0.3,0.1

Type RM Length L Ch R = 1 ,22304   ,481,481,481
BEGIN DESCRIPTION:
LAKE CREEK TRIBUTARY NO. 4 42.0
END DESCRIPTION:
XS GIS Cut Line= 3
      3731317.85     10102711.08      3731597.07     10102125.33
      3731567.86     10101911.11
#Sta/Elev= 30
  4351.1  287.51  4373.3  285.96    4456  284.27  4461.9  283.46  4524.1  280.95
  4592.2  279.61  4672.4  276.39  4749.9  274.62  4821.9  275.06  4830.3  274.48
  4870.1  274.99  4949.3  274.05  4960.4  273.35  4966.5  268.94 4969.86  267.48
    4972  266.55  4982.6  265.85  4989.2  266.21  4992.9  262.91  4996.4  262.91
  4999.6  264.69  5004.7  264.69  5012.3267.4087  5030.4     272  5035.4  270.39
  5054.8  273.95  5074.9  274.78  5107.7  277.61  5180.1  284.42  5216.2   288.8
#Mann= 4 ,-1 , 0
  4351.1     .15       0  4821.9     .11       0 4969.86     .07       0
  5012.3     .11       0
Bank Sta=4969.86,5012.3
XS Rating Curve= 0 ,0
Exp/Cntr=0.3,0.1

Type RM Length L Ch R = 1 ,21823   ,498,498,498
BEGIN DESCRIPTION:
LAKE CREEK TRIBUTARY NO. 4 41.0
END DESCRIPTION:
XS GIS Cut Line= 3
      3732023.29     10102426.16      3732003.47     10102250.88
      3731988.57     10102011.74
#Sta/Elev= 30
  4823.6  272.56  4841.9  271.31  4858.9  270.61    4869  269.17    4879  268.72
  4889.1  265.22  4899.2  263.67  4915.4  270.05  4920.4  270.59  4949.5  270.44
  4959.6  269.71  4968.2  267.28  4985.3 261.928  4997.4  257.59  5002.4  257.59
  5005.6   255.8  5029.9  257.62  5049.9  261.88  5059.9   264.9  5069.9  265.74
    5080  266.28    5090  264.73    5110  270.37  5150.1   270.7  5160.1  268.55
    5173  270.46  5180.2  269.97  5204.6  272.39    5224   273.7  5239.6  275.09
#Mann= 7 ,-1 , 0
  4823.6     .15       0  4841.9     .11       0  4968.2     .17       0
  4985.3     .09       0  5049.9     .17       0  5204.6     .11       0
    5224     .17       0
Bank Sta=4985.3,5049.9
XS Rating Curve= 0 ,0
Exp/Cntr=0.3,0.1

Type RM Length L Ch R = 1 ,21325   ,402,402,402
BEGIN DESCRIPTION:
LAKE CREEK TRIBUTARY NO. 4 40.0
END DESCRIPTION:
XS GIS Cut Line= 3
      3732324.93     10102708.33      3732441.29     10102332.84
      3732526.75     10101968.33
#Sta/Elev= 30
  4606.9  271.32  4771.6  266.46    4806  267.03  4908.4  266.57  4918.1  266.26
  4928.6  263.96    4933  263.78    4941  262.25    4960  260.61  4973.6  257.17
  4991.4  255.23  4996.6  253.63  5006.9  254.26  5012.1  255.58  5042.9  257.01
  5054.5  255.18  5067.4260.7263  5073.7  263.02    5084  265.09  5096.9  265.86
  5114.8  268.54  5134.2  268.58  5145.6   269.6  5166.2  269.93  5176.7  271.16
  5224.3  272.67  5238.1  274.04  5314.3  278.35  5340.8  278.83  5374.4  281.41
#Mann= 7 ,-1 , 0
  4606.9     .17       0  4771.6     .15       0    4806     .17       0
    4933     .15       0    4960     .09       0  5067.4     .15       0
  5176.7     .17       0
Bank Sta=4960,5067.4
XS Rating Curve= 0 ,0
Exp/Cntr=0.3,0.1

Type RM Length L Ch R = 1 ,20923   ,623,623,623
BEGIN DESCRIPTION:
LAKE CREEK TRIBUTARY NO. 4 39.0
END DESCRIPTION:
XS GIS Cut Line= 3
      3732377.03     10102818.98      3732769.82     10102517.34
      3732858.78      10102087.7
#Sta/Elev= 30
  4503.3  271.86  4588.2  269.49  4652.6  266.25  4723.2  264.56  4737.8  265.87
  4787.6  261.37  4802.1  262.77  4850.4  262.74    4881  263.44  4908.1  262.57
  4972.5   262.5  4980.7  261.41    4987  259.16  4994.2  254.97  4998.5  254.97
    5010  252.17  5013.5  252.17  5016.9  257.24  5022.7259.2871  5035.6  261.87
  5067.1   265.1  5117.3   267.1  5157.2  266.71  5214.3  269.97  5257.6  272.74
  5307.8  274.87  5331.7  274.95    5358  277.08  5363.1  276.58  5437.3  280.06
#Mann= 5 ,-1 , 0
  4503.3     .17       0  4850.4     .15       0    4987     .09       0
  5022.7     .15       0  5214.3     .17       0
Bank Sta=4987,5022.7
XS Rating Curve= 0 ,0
Exp/Cntr=0.3,0.1

Type RM Length L Ch R = 1 ,20300   ,394,394,394
BEGIN DESCRIPTION:
LAKE CREEK TRIBUTARY NO. 4 38.0
END DESCRIPTION:
XS GIS Cut Line= 4
      3733169.12     10103177.09      3733223.38     10102738.69
      3733208.19     10102591.13      3732902.51     10102090.34
#Sta/Elev= 30
  4556.4  264.44  4601.5  262.74  4643.1  260.65  4663.2  260.89  4693.5  259.17
  4707.1  259.23  4784.1  258.51  4804.3  259.13  4816.8  258.48  4830.3  257.98
  4874.8  258.64  4916.3   257.5  4945.4  258.09  4955.4  257.24  4975.6  257.09
  4977.7256.2729  4985.7  253.16  4990.5   247.5  4998.1   248.2  5007.1  251.16
 5015.03256.2063  5025.9  258.84  5076.2  258.28  5135.2  259.32  5212.7  259.11
    5445  265.81  5518.5  268.36  5539.8  270.11  5555.3  269.95  5733.2  279.42
#Mann= 7 ,-1 , 0
  4556.4     .17       0  4601.5     .11       0  4707.1     .17       0
  4816.8     .15       0  4977.7     .09       0 5015.03     .15       0
  5135.2     .17       0
Bank Sta=4977.7,5015.03
XS Rating Curve= 0 ,0
Exp/Cntr=0.3,0.1

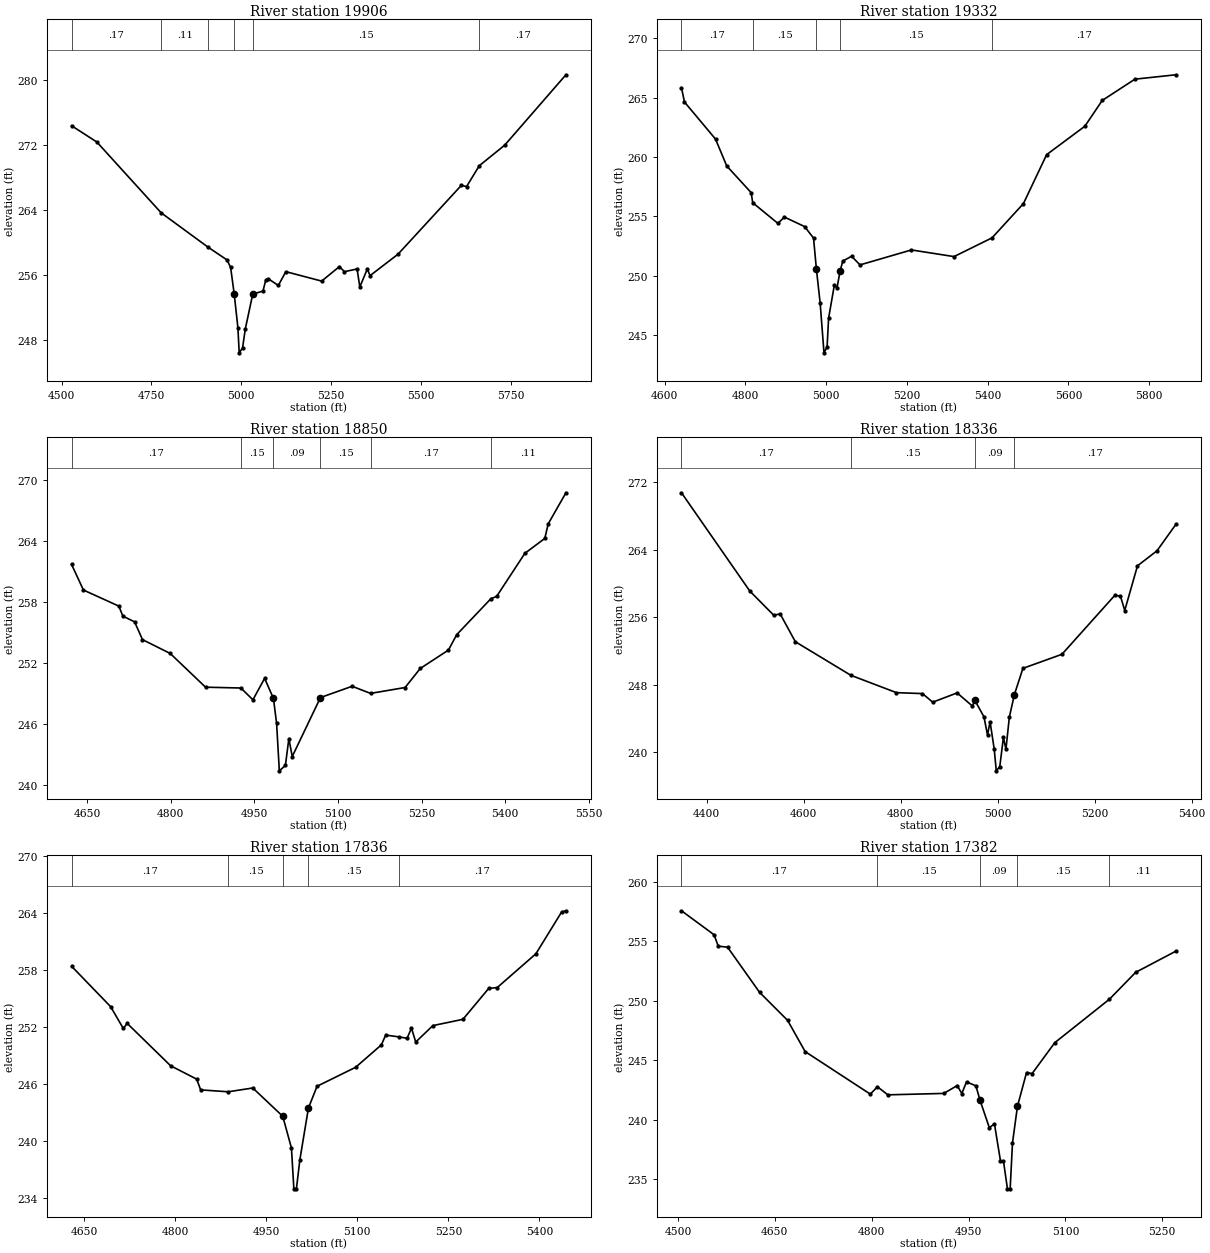
Type RM Length L Ch R = 1 ,19906   ,574,574,574
BEGIN DESCRIPTION:
LAKE CREEK TRIBUTARY NO. 4 37.0
END DESCRIPTION:
XS GIS Cut Line= 3
      3733567.86     10103211.11      3733514.18     10102745.21
      3732917.87      10102061.1
#Sta/Elev= 30
  4527.5  274.42    4598  272.41    4777   263.7  4908.3  259.45  4960.4   257.9
  4970.4  256.98  4980.5  253.66  4990.6  249.57  4994.3  246.47  5003.6  247.07
  5011.2   249.4    5032   253.7  5060.5  254.07  5068.1  255.42  5074.8   255.6
  5103.2  254.76  5124.1  256.46  5223.8   255.3  5273.2  257.08  5287.4  256.46
  5322.5  256.79  5330.1  254.58    5351  256.79  5358.6  255.97  5436.5  258.61
    5613  267.09  5627.3  266.93  5662.8   269.5  5733.6  272.03    5904  280.69
#Mann= 6 ,-1 , 0
  4527.5     .17       0    4777     .11       0  4908.3     .15       0
  4980.5     .09       0    5032     .15       0  5662.8     .17       0
Bank Sta=4980.5,5032
XS Rating Curve= 0 ,0
Exp/Cntr=0.3,0.1

Type RM Length L Ch R = 1 ,19332   ,482,482,482
BEGIN DESCRIPTION:
LAKE CREEK TRIBUTARY NO. 4 36.0
END DESCRIPTION:
XS GIS Cut Line= 5
      3733661.72     10103046.89      3733828.05     10102729.43
      3733978.59     10102558.57      3733974.25     10102478.28
      3733700.79     10101992.13
#Sta/Elev= 30
  4641.6  265.85  4648.9  264.65  4725.9  261.52  4753.6  259.26  4814.1  257.01
    4818  256.16  4880.3  254.42  4896.5  254.95  4946.5  254.15  4968.6  253.18
  4975.6   250.6    4985   247.7  4994.5  243.51  5002.2  244.01  5005.9  246.43
  5020.1  249.21  5026.8  248.99  5034.3  250.39    5041  251.24  5062.8  251.65
  5083.7  250.92    5211  252.18  5316.5  251.62  5410.7   253.2  5488.5  256.09
  5545.9  260.21  5640.4   262.6  5683.7  264.78  5764.6  266.57  5865.9  266.94
#Mann= 5 ,-1 , 0
  4641.6     .17       0    4818     .15       0  4975.6     .09       0
  5034.3     .15       0  5410.7     .17       0
Bank Sta=4975.6,5034.3
XS Rating Curve= 0 ,0
Exp/Cntr=0.3,0.1

Type RM Length L Ch R = 1 ,18850   ,514,514,514
BEGIN DESCRIPTION:
LAKE CREEK TRIBUTARY NO. 4 35.0
END DESCRIPTION:
XS GIS Cut Line= 3
      3733817.84     10103111.08      3734095.77     10102849.37
      3734383.65      10102433.8
#Sta/Elev= 30
  4621.9  261.66  4643.2  259.14  4706.7  257.56    4714  256.57    4735  256.01
  4749.2  254.26  4798.9   252.9  4862.4  249.58  4925.8   249.5  4947.4  248.34
  4968.4  250.45 4984.25248.4735  4989.9  246.02  4994.8  241.35  5005.7  241.88
  5011.9  244.52    5018  242.76  5068.6  248.56  5125.4  249.67  5158.6  248.97
  5220.6  249.55  5247.7  251.42  5298.3  253.23  5313.2  254.75  5374.6  258.29
  5384.8  258.51  5435.5  262.75  5471.3  264.22  5477.4  265.65  5509.2  268.71
#Mann= 6 ,-1 , 0
  4621.9     .17       0  4925.8     .15       0 4984.25     .09       0
  5068.6     .15       0  5158.6     .17       0  5374.6     .11       0
Bank Sta=4984.25,5068.6
XS Rating Curve= 0 ,0
Exp/Cntr=0.3,0.1

Type RM Length L Ch R = 1 ,18336   ,500,500,500
BEGIN DESCRIPTION:
LAKE CREEK TRIBUTARY NO. 4 34.0
END DESCRIPTION:
XS GIS Cut Line= 3
      3733717.87     10103261.07      3734334.64     10103049.95
      3734689.69     10102955.89
#Sta/Elev= 30
  4348.1  270.77  4488.9  259.12  4538.3  256.25  4551.5  256.41  4582.8  253.11
  4697.2  249.13  4791.3  247.07  4844.9  246.96    4866  245.94  4916.4  247.04
  4947.7  245.49    4953  246.15  4971.7   244.2    4979  242.04  4984.3  243.62
  4992.8  240.39  4997.1   237.8  5004.3   238.3  5011.8  241.76    5017  240.36
    5024  244.16  5034.4  246.84    5052  249.95  5132.5  251.62  5241.3   258.6
  5253.1  258.52  5261.9  256.81  5288.2  262.11  5328.4  263.89  5367.3  267.02
#Mann= 4 ,-1 , 0
  4348.1     .17       0  4697.2     .15       0    4953     .09       0
  5034.4     .17       0
Bank Sta=4953,5034.4
XS Rating Curve= 0 ,0
Exp/Cntr=0.3,0.1

Type RM Length L Ch R = 1 ,17836   ,454,454,454
BEGIN DESCRIPTION:
LAKE CREEK TRIBUTARY NO. 4 33.0
END DESCRIPTION:
XS GIS Cut Line= 3
      3734217.88     10103661.04      3734455.98     10103376.79
      3734767.87     10103061.06
#Sta/Elev= 30
  4629.2  258.44  4693.6  254.18  4714.4  251.89  4720.9  252.42  4792.4  247.96
  4835.4  246.55  4841.9  245.42  4887.4  245.22  4927.8  245.62  4977.2  242.64
  4991.5   239.3  4995.5     235  4999.7     235  5005.4  238.07  5019.5  243.51
  5033.7   245.8  5097.3   247.8  5139.7  250.16  5146.8  251.19  5168.7     251
  5182.1  250.85  5189.3  251.93  5196.3  250.46  5224.6  252.19  5274.1  252.85
  5316.5   256.1  5330.7   256.2  5394.3  259.75  5436.7  264.15  5443.8  264.28
#Mann= 5 ,-1 , 0
  4629.2     .17       0  4887.4     .15       0  4977.2     .09       0
  5019.5     .15       0  5168.7     .17       0
Bank Sta=4977.2,5019.5
XS Rating Curve= 0 ,0
Exp/Cntr=0.3,0.1

Type RM Length L Ch R = 1 ,17382   ,543,543,543
BEGIN DESCRIPTION:
LAKE CREEK TRIBUTARY NO. 4 32.0
END DESCRIPTION:
XS GIS Cut Line= 3
      3734517.84     10104011.09      3734824.94     10103624.11
      3734954.98      10103385.7
#Sta/Elev= 30
  4505.4  257.57  4555.9  255.55  4562.3  254.59  4576.7  254.51  4626.4   250.7
  4669.7  248.35  4696.9  245.72  4797.8  242.14  4808.8  242.76    4825  242.08
  4911.6   242.2  4932.4  242.86  4939.5  242.19  4946.8  243.17  4961.3  242.84
  4967.6  241.65  4982.1  239.32  4990.1  239.63  4999.4  236.52    5004  236.52
  5010.2  234.17  5014.4  234.17    5018  238.03  5025.7  241.12  5039.8  243.96
  5048.4  243.87  5083.5  246.47    5168  250.12  5208.8  252.39    5271  254.17
#Mann= 5 ,-1 , 0
  4505.4     .17       0  4808.8     .15       0  4967.6     .09       0
  5025.7     .15       0    5168     .11       0
Bank Sta=4967.6,5025.7
XS Rating Curve= 0 ,0
Exp/Cntr=0.3,0.1

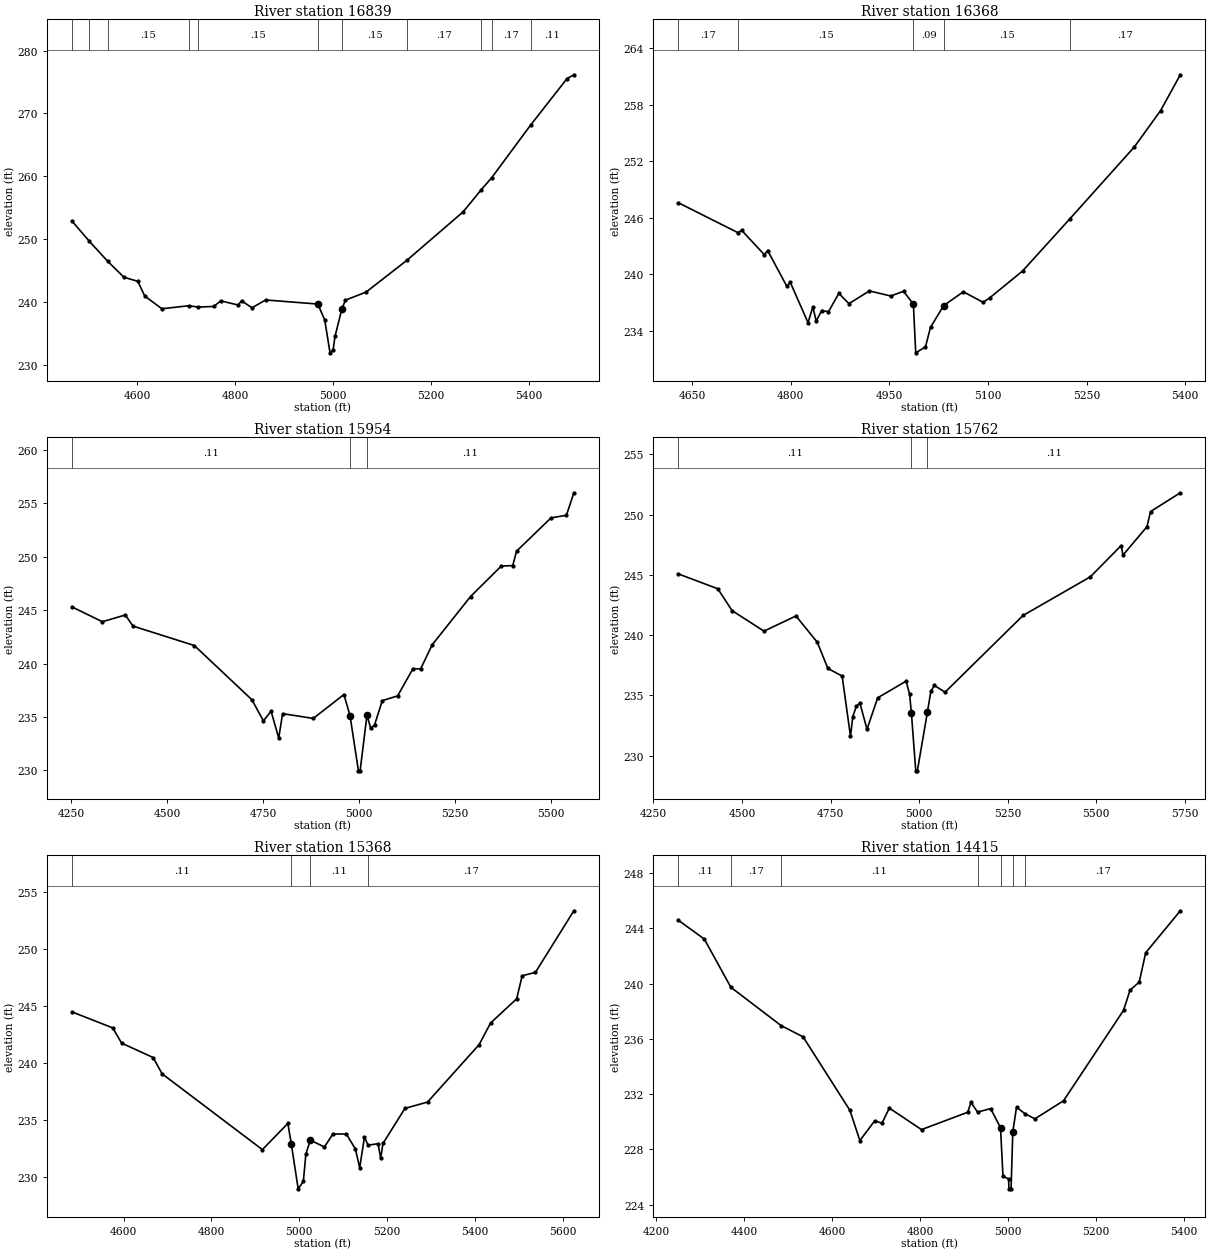
Type RM Length L Ch R = 1 ,16839   ,471,471,471
BEGIN DESCRIPTION:
LAKE CREEK TRIBUTARY NO. 4 31.0
END DESCRIPTION:
XS GIS Cut Line= 3
      3734817.88     10104361.04       3735181.3     10103969.92
      3735517.87     10103611.05
#Sta/Elev= 30
  4466.1  252.92  4501.8  249.69  4539.1  246.53  4572.3  243.99  4600.7  243.34
  4614.9     241    4650  238.98  4704.5  239.46  4724.7  239.25    4756  239.35
  4770.2  240.24  4805.9  239.57  4812.7  240.25  4834.2  239.14  4862.1  240.38
  4968.6  239.73  4982.8   237.2  4993.6  231.98    5000  232.48  5003.8  234.59
  5017.9  238.98  5025.2  240.35  5067.3  241.63  5150.9  246.69  5265.6  254.37
  5302.8   257.9  5323.8  259.77  5403.8  268.18    5478  275.54    5492  276.15
#Mann= 11 ,-1 , 0
  4466.1     .15       0  4501.8     .17       0  4539.1     .15       0
  4704.5     .17       0  4724.7     .15       0  4968.6     .09       0
  5017.9     .15       0  5150.9     .17       0  5302.8     .11       0
  5323.8     .17       0  5403.8     .11       0
Bank Sta=4968.6,5017.9
XS Rating Curve= 0 ,0
Exp/Cntr=0.3,0.1

Type RM Length L Ch R = 1 ,16368   ,414,414,414
BEGIN DESCRIPTION:
LAKE CREEK TRIBUTARY NO. 4 30.0
END DESCRIPTION:
XS GIS Cut Line= 3
      3735417.84     10104511.12      3735517.21     10104151.46
      3735517.85     10103761.09
#Sta/Elev= 30
  4629.1  247.59  4719.3  244.43  4725.4  244.66  4759.7  242.09  4764.9  242.52
    4794  238.73  4799.2  239.16  4826.3  234.87  4833.6  236.55  4838.7  235.03
    4847  236.16  4857.4  236.03  4873.1  237.98  4888.5  236.89  4919.6  238.24
  4952.1   237.7  4971.5   238.2  4986.5  236.85  4990.1  231.67  5004.9   232.3
  5012.6  234.38  5032.6  236.68  5062.6  238.15  5092.6  237.03  5102.6   237.5
  5152.6  240.35  5224.5  245.88  5322.6  253.51  5362.6  257.37  5392.6  261.17
#Mann= 5 ,-1 , 0
  4629.1     .17       0  4719.3     .15       0  4986.5     .09       0
  5032.6     .15       0  5224.5     .17       0
Bank Sta=4986.5,5032.6
XS Rating Curve= 0 ,0
Exp/Cntr=0.3,0.1

Type RM Length L Ch R = 1 ,15954   ,192,192,192
BEGIN DESCRIPTION:
Mapping XS 635f6f34
END DESCRIPTION:
XS GIS Cut Line= 2
      3735836.22     10104850.26      3735851.42     10103541.65
#Sta/Elev= 30
  4251.9  245.31  4331.1  243.92  4391.1  244.55  4411.1  243.51  4571.1  241.69
  4721.1  236.61  4751.1  234.63  4771.1  235.54  4791.1  233.02  4801.1  235.31
  4881.1  234.86  4961.1   237.1 4977.03235.1099  4998.9  229.95  5003.3  229.95
  5021.1  235.16  5031.1  233.92  5041.1  234.27  5061.1  236.53  5101.1  236.97
  5141.1  239.52  5161.1   239.5  5191.2  241.76  5291.2  246.28  5371.2  249.13
  5401.2  249.18  5411.2  250.53  5501.2  253.65  5541.2  253.89  5560.6     256
#Mann= 3 , 0 , 0
  4251.9     .11       0 4977.03     .06       0  5021.1     .11       0
Bank Sta=4977.03,5021.1
XS Rating Curve= 0 ,0
Exp/Cntr=0.3,0.1

Type RM Length L Ch R = 1 ,15762   ,394,394,394
BEGIN DESCRIPTION:
LAKE CREEK TRIBUTARY NO. 4 29.0
END DESCRIPTION:
XS GIS Cut Line= 3
      3735955.58     10104871.97      3736007.67     10104197.03
       3736027.2     10103457.03
#Sta/Elev= 30
  4320.4  245.08  4431.6  243.85  4471.7  242.04    4562  240.33  4652.3  241.59
  4712.5  239.41  4742.5  237.23  4782.7   236.6  4806.3  231.59  4812.8  233.24
  4822.8  234.08  4832.8  234.36  4852.9  232.18    4883  234.79  4963.2  236.18
  4973.2  235.09 4978.25 233.525  4990.6  228.73  4995.1  228.73  5023.3  233.58
  5033.3  235.35  5043.3  235.82  5073.3  235.26  5293.4  241.63  5483.5  244.84
  5570.7  247.44  5575.7  246.64  5643.5  249.01  5653.5  250.26  5737.6  251.82
#Mann= 3 , 0 , 0
  4320.4     .11       0 4978.25     .06       0  5023.3     .11       0
Bank Sta=4978.25,5023.3
XS Rating Curve= 0 ,0
Exp/Cntr=0.3,0.1

Type RM Length L Ch R = 1 ,15368   ,953,953,953
BEGIN DESCRIPTION:
LAKE CREEK TRIBUTARY NO. 4 28.0
END DESCRIPTION:
XS GIS Cut Line= 3
      3736061.92     10104971.75       3736170.9     10104465.65
      3736311.47     10103856.36
#Sta/Elev= 30
  4482.3  244.48  4575.1  243.08  4595.5  241.74  4667.1  240.48  4687.6  239.05
    4916   232.4    4974   234.7  4981.9  232.88  4997.5  228.96  5009.3  229.61
    5015  232.01  5025.2  233.23  5057.2  232.63  5076.5  233.77  5107.3  233.77
  5127.9  232.44  5137.6  230.81  5148.4   233.5  5156.7  232.79  5179.2  232.92
  5185.5  231.66  5190.6  232.94  5240.7  236.02  5292.1  236.57  5409.6  241.61
  5435.7  243.51  5495.1  245.63  5507.6  247.65  5537.8  247.95  5625.3  253.35
#Mann= 4 ,-1 , 0
  4482.3     .11       0  4981.9     .07       0  5025.2     .11       0
  5156.7     .17       0
Bank Sta=4981.9,5025.2
XS Rating Curve= 0 ,0
Exp/Cntr=0.3,0.1

Type RM Length L Ch R = 1 ,14415   ,545,545,545
BEGIN DESCRIPTION:
LAKE CREEK TRIBUTARY NO. 4 27.0
END DESCRIPTION:
XS GIS Cut Line= 3
      3736117.89     10105011.05      3736791.09      10104678.8
      3737017.87     10104361.05
#Sta/Elev= 30
    4251  244.59  4309.9  243.23  4370.2  239.74  4484.7  236.96  4534.4  236.15
    4641  230.82  4663.5  228.64  4697.1  230.06  4713.9   229.9  4730.5  230.99
  4803.7  229.43  4908.9  230.69    4916  231.41    4931   230.7  4960.9  230.95
  4983.3  229.57  4988.9  226.06  5001.7  225.85  5002.5  225.14  5007.3  225.14
  5011.2  229.27  5019.7  231.05  5039.4  230.57  5061.5  230.21  5126.6  231.52
    5263  238.07  5277.8  239.53  5298.7  240.12  5313.4  242.24  5392.1  245.28
#Mann= 7 ,-1 , 0
    4251     .11       0  4370.2     .17       0  4484.7     .11       0
    4931     .15       0  4983.3     .09       0  5011.2     .15       0
  5039.4     .17       0
Bank Sta=4983.3,5011.2
XS Rating Curve= 0 ,0
Exp/Cntr=0.3,0.1

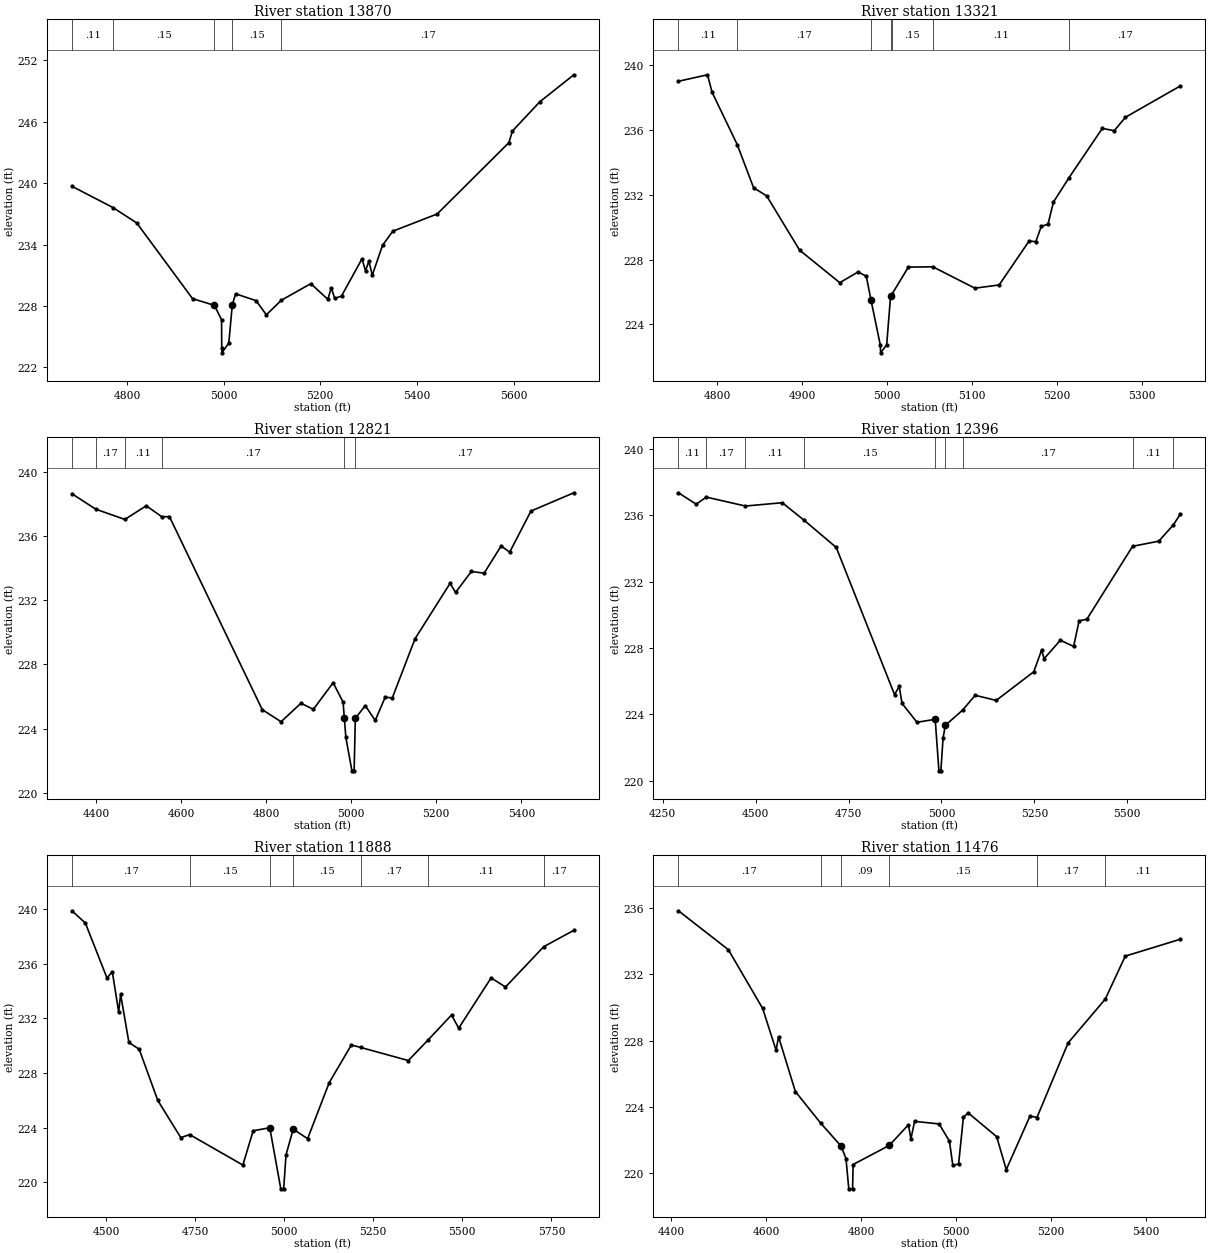
Type RM Length L Ch R = 1 ,13870   ,549,549,549
BEGIN DESCRIPTION:
LAKE CREEK TRIBUTARY NO. 4 26.0
END DESCRIPTION:
XS GIS Cut Line= 3
      3736767.84      10105261.1      3736915.92      10104984.1
      3737417.85     10104461.08
#Sta/Elev= 30
  4685.9  239.68    4771   237.6  4820.1   236.1  4935.5  228.72  4980.8  228.06
  4995.6  226.66    4996  223.93  4996.4  223.43  5010.6  224.39  5017.8   228.1
  5024.7  229.19  5067.2  228.52  5088.3  227.14  5119.3  228.56  5180.4  230.18
  5215.6  228.65  5222.8  229.78  5229.8  228.74  5243.9  228.97  5286.4  232.61
  5293.6  231.43  5300.5  232.37  5307.7  231.01  5328.8  233.92  5350.2   235.3
    5442  236.98  5590.5  243.94  5597.7  245.07  5654.3  247.92  5724.9  250.56
#Mann= 5 ,-1 , 0
  4685.9     .11       0    4771     .15       0  4980.8     .09       0
  5017.8     .15       0  5119.3     .17       0
Bank Sta=4980.8,5017.8
XS Rating Curve= 0 ,0
Exp/Cntr=0.3,0.1

Type RM Length L Ch R = 1 ,13321   ,500,500,500
BEGIN DESCRIPTION:
LAKE CREEK TRIBUTARY NO. 4 25.0
END DESCRIPTION:
XS GIS Cut Line= 3
      3736971.24     10105468.72       3737196.9     10105379.75
      3737417.83      10105111.1
#Sta/Elev= 30
  4754.6  239.01  4788.8  239.41  4794.2  238.33  4823.8   235.1    4843  232.44
  4858.5  231.93  4897.1  228.59  4944.4  226.58  4965.9  227.24  4975.6  226.98
    4981  225.54    4992  222.75  4992.5  222.25  4999.6  222.75  5004.2  225.77
  5005.8  225.87  5025.1  227.54  5053.9  227.56  5103.3  226.24  5131.9  226.44
  5167.1  229.15    5175  229.11  5181.5  230.06  5189.3  230.18  5195.8  231.56
  5214.1  233.06  5253.2   236.1  5267.3  235.96  5280.5  236.79    5345  238.72
#Mann= 7 ,-1 , 0
  4754.6     .11       0  4823.8     .17       0    4981     .09       0
  5004.2     .17       0  5005.8     .15       0  5053.9     .11       0
  5214.1     .17       0
Bank Sta=4981,5004.2
XS Rating Curve= 0 ,0
Exp/Cntr=0.3,0.1

Type RM Length L Ch R = 1 ,12821   ,425,425,425
BEGIN DESCRIPTION:
LAKE CREEK TRIBUTARY NO. 4 24.0
END DESCRIPTION:
XS GIS Cut Line= 3
      3736967.81     10105811.09      3737730.76     10105477.41
      3737741.61     10105130.21
#Sta/Elev= 30
  4343.4  238.63  4399.2  237.67  4467.7  237.03  4518.1  237.88  4554.6   237.2
  4572.7   237.2  4790.9  225.18  4835.1  224.43  4881.9  225.58    4911   225.2
  4957.5  226.86  4980.9  225.65 4983.81 224.665  4987.4  223.45  5001.7  221.37
  5006.9  221.37  5009.7  224.64  5033.1  225.43  5056.5  224.51  5079.9  225.96
  5096.6  225.91  5150.1   229.6  5232.5  233.05  5245.4  232.48  5282.5  233.79
  5312.5  233.68  5352.6  235.38  5372.6  234.99  5422.6  237.55  5523.5  238.69
#Mann= 6 ,-1 , 0
  4343.4     .11       0  4399.2     .17       0  4467.7     .11       0
  4554.6     .17       0 4983.81     .09       0  5009.7     .17       0
Bank Sta=4983.81,5009.7
XS Rating Curve= 0 ,0
Exp/Cntr=0.3,0.1

Type RM Length L Ch R = 1 ,12396   ,508,508,508
BEGIN DESCRIPTION:
LAKE CREEK TRIBUTARY NO. 4 23.0
END DESCRIPTION:
XS GIS Cut Line= 3
      3737010.31     10105835.49      3737678.67     10105915.78
      3738067.86     10105361.06
#Sta/Elev= 30
    4292  237.37  4339.9  236.68  4367.1  237.11  4472.3  236.57  4571.5  236.77
  4629.9  235.72  4716.8  234.07  4873.7  225.19  4886.3  225.69  4893.8  224.66
  4934.1  223.52  4983.1   223.7  4993.1  220.59  4998.3  220.59  5004.4  222.59
  5010.5  223.34  5056.7  224.25  5090.6  225.15  5147.3  224.84  5248.4  226.57
  5269.3  227.87  5276.3  227.36  5319.9  228.47  5355.6   228.1  5370.4  229.64
  5391.3  229.74  5514.3  234.14  5584.8  234.45  5623.2  235.41  5642.8  236.08
#Mann= 9 ,-1 , 0
    4292     .11       0  4367.1     .17       0  4472.3     .11       0
  4629.9     .15       0  4983.1     .09       0  5010.5     .15       0
  5056.7     .17       0  5514.3     .11       0  5623.2     .17       0
Bank Sta=4983.1,5010.5
XS Rating Curve= 0 ,0
Exp/Cntr=0.3,0.1

Type RM Length L Ch R = 1 ,11888   ,412,412,412
BEGIN DESCRIPTION:
LAKE CREEK TRIBUTARY NO. 4 22.0
END DESCRIPTION:
XS GIS Cut Line= 3
      3737867.85     10106611.08      3738107.79     10106066.38
      3738217.85     10105261.07
#Sta/Elev= 30
  4404.8  239.87  4442.5  238.97  4503.1  234.95    4518  235.41  4535.9  232.46
  4541.3  233.76  4564.6  230.23  4593.4  229.74  4645.6  225.99  4710.1  223.27
  4735.1  223.49  4884.3  221.26  4913.1  223.77  4959.8  223.99  4990.7  219.52
  4998.7  219.52  5005.4  222.01  5025.5  223.89  5065.9  223.19  5126.5  227.29
  5188.6  230.05  5214.4  229.87  5348.5  228.91  5403.3   230.4  5469.6  232.24
  5489.8  231.28  5580.7  234.96    5621  234.29  5728.2  237.24  5812.8  238.44
#Mann= 7 ,-1 , 0
  4404.8     .17       0  4735.1     .15       0  4959.8     .09       0
  5025.5     .15       0  5214.4     .17       0  5403.3     .11       0
  5728.2     .17       0
Bank Sta=4959.8,5025.5
XS Rating Curve= 0 ,0
Exp/Cntr=0.3,0.1

Type RM Length L Ch R = 1 ,11476   ,581,581,581
BEGIN DESCRIPTION:
LAKE CREEK TRIBUTARY NO. 4 21.0
END DESCRIPTION:
XS GIS Cut Line= 3
      3738330.58     10106592.88      3738476.42     10106030.36
      3738514.55      10105555.4
#Sta/Elev= 30
    4415  235.84  4520.2  233.49  4592.5  229.94  4620.8  227.41    4626  228.23
  4661.4  224.92  4714.5  223.02  4757.8  221.62  4768.1  220.87    4774  219.04
    4782  219.04  4783.1  220.51  4859.1  221.66  4899.7  222.91  4904.9  222.06
  4912.7  223.12  4964.4  222.96  4986.1  221.92  4993.2  220.46  5005.4  220.54
  5015.5  223.36  5025.5  223.63  5085.7  222.19  5105.8   220.2  5155.9  223.44
  5170.5  223.35  5236.2  227.86  5314.4   230.5  5356.6   233.1  5472.6  234.12
#Mann= 6 ,-1 , 0
    4415     .17       0  4714.5     .15       0  4757.8     .09       0
  4859.1     .15       0  5170.5     .17       0  5314.4     .11       0
Bank Sta=4757.8,4859.1
XS Rating Curve= 0 ,0
Exp/Cntr=0.3,0.1

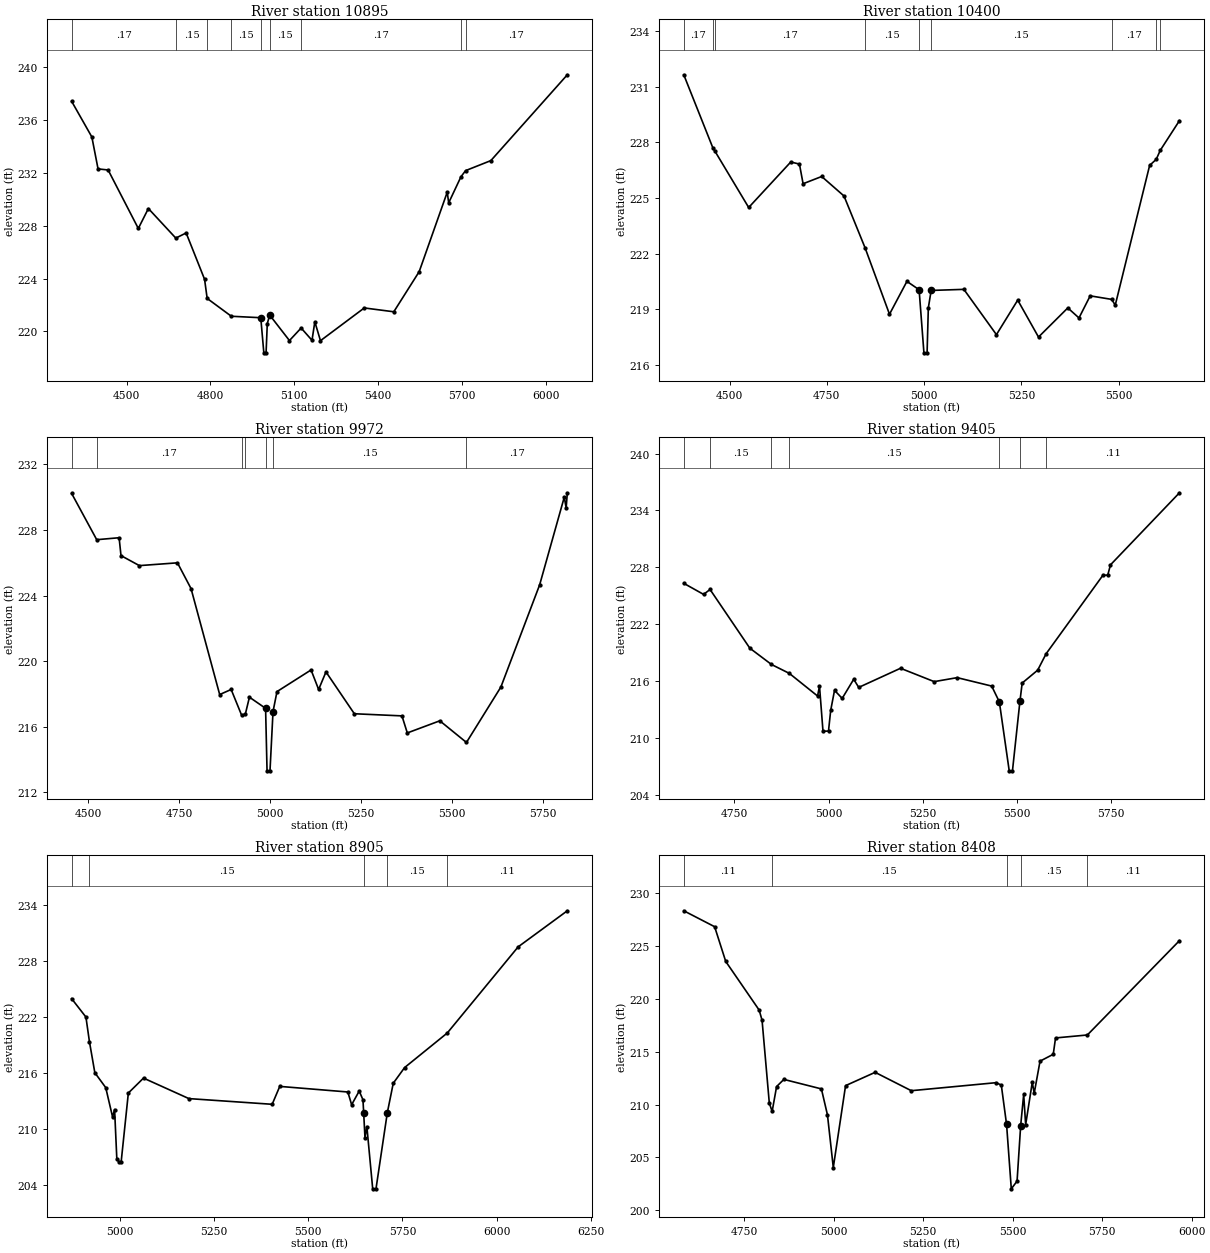
Type RM Length L Ch R = 1 ,10895   ,495,495,495
BEGIN DESCRIPTION:
LAKE CREEK TRIBUTARY NO. 4 20.0
END DESCRIPTION:
XS GIS Cut Line= 3
      3738517.85     10106561.08      3738906.24     10105983.04
      3739049.32     10104915.89
#Sta/Elev= 30
  4303.6  237.43  4375.9  234.73  4398.1  232.31  4434.1  232.23  4542.1   227.8
  4578.1  229.31  4676.2  227.07  4713.2  227.46  4779.1  223.95  4788.4   222.5
  4874.9  221.15  4980.1  221.04  4991.1  218.38  4999.1  218.38  5003.5   220.6
  5012.1  221.24  5082.7  219.31  5124.5  220.26  5163.4  219.33  5173.5  220.73
  5193.7   219.3  5350.4  221.78    5456  221.49  5546.8  224.53  5647.2  230.55
  5652.3  229.74  5696.1  231.71  5712.7  232.18  5803.2  232.94  6076.7  239.44
#Mann= 9 ,-1 , 0
  4303.6     .17       0  4676.2     .15       0  4788.4     .17       0
  4874.9     .15       0  4980.1     .09       0  5012.1     .15       0
  5124.5     .17       0  5696.1     .11       0  5712.7     .17       0
Bank Sta=4980.1,5012.1
XS Rating Curve= 0 ,0
Exp/Cntr=0.3,0.1

Type RM Length L Ch R = 1 ,10400   ,428,428,428
BEGIN DESCRIPTION:
LAKE CREEK TRIBUTARY NO. 4 19.0
END DESCRIPTION:
XS GIS Cut Line= 3
      3738617.84     10106561.08      3739202.18     10106360.83
      3739467.87     10105761.04
#Sta/Elev= 30
  4382.3  231.64  4457.1   227.7  4462.2  227.53  4549.1  224.49  4657.2  226.94
  4679.5  226.83  4688.9  225.77  4736.7  226.16    4794  225.11  4848.1  222.32
  4910.9  218.74  4955.7  220.51    4987  220.06  4999.4  216.66  5007.5  216.66
  5010.7  219.08 5017.97220.0216    5102  220.08  5185.7  217.64  5240.4   219.5
  5293.8  217.51  5369.1  219.08  5397.8  218.54  5426.6  219.73  5481.8  219.54
    5491  219.23  5579.4  226.76  5596.2  227.08  5606.7  227.57    5656  229.17
#Mann= 9 ,-1 , 0
  4382.3     .17       0  4457.1     .15       0  4462.2     .17       0
  4848.1     .15       0    4987     .09       0 5017.97     .15       0
  5481.8     .17       0  5596.2     .15       0  5606.7     .17       0
Bank Sta=4987,5017.97
XS Rating Curve= 0 ,0
Exp/Cntr=0.3,0.1

Type RM Length L Ch R = 1 ,9972    ,567,567,567
BEGIN DESCRIPTION:
LAKE CREEK TRIBUTARY NO. 4 18.0
END DESCRIPTION:
XS GIS Cut Line= 3
      3739372.23     10107058.19      3739538.92     10106540.78
      3739764.12     10105754.28
#Sta/Elev= 30
  4455.1  230.23    4524  227.41  4585.5  227.53  4590.7  226.44  4641.2  225.83
  4745.8     226  4783.1  224.43  4861.8  217.97  4893.3  218.28  4921.9  216.72
  4932.2  216.77  4943.5  217.81  4987.9  217.13  4991.9  213.32    5000  213.32
  5008.3  216.93  5019.2  218.15  5112.8  219.47  5133.6  218.28  5153.8  219.35
  5231.7   216.8  5362.5  216.67  5377.2  215.63  5466.5  216.37  5539.7  215.05
  5634.3  218.43  5740.8  224.66  5808.4     230  5813.6  229.35  5816.8  230.27
#Mann= 7 ,-1 , 0
  4455.1     .11       0    4524     .17       0  4921.9     .11       0
  4932.2     .15       0  4987.9     .09       0  5008.3     .15       0
  5539.7     .17       0
Bank Sta=4987.9,5008.3
XS Rating Curve= 0 ,0
Exp/Cntr=0.3,0.1

Type RM Length L Ch R = 1 ,9405    ,500,500,500
BEGIN DESCRIPTION:
LAKE CREEK TRIBUTARY NO. 4 17.0
END DESCRIPTION:
XS GIS Cut Line= 3
      3739969.47     10107002.57      3740048.63     10106626.81
      3740217.84     10105711.12
#Sta/Elev= 30
    4616  226.31  4668.6  225.14  4685.7  225.66  4791.3  219.46  4848.7  217.74
  4896.1   216.8    4971  214.41  4976.1  215.46  4985.4  210.69    5000  210.71
  5005.8  212.89    5016  215.01  5036.3  214.16  5066.9  216.18  5080.2  215.32
  5191.1  217.34  5280.4  215.93  5341.4  216.35    5433  215.46  5453.3  213.79
  5479.5  206.51  5488.1  206.51  5507.9213.8514  5513.9  215.78    5555  217.14
  5577.5  218.88  5727.9  227.15  5740.9  227.18  5748.2  228.26  5931.2  235.87
#Mann= 7 ,-1 , 0
    4616     .17       0  4685.7     .15       0  4848.7     .17       0
  4896.1     .15       0  5453.3     .09       0  5507.9     .15       0
  5577.5     .11       0
Bank Sta=5453.3,5507.9
XS Rating Curve= 0 ,0
Exp/Cntr=0.3,0.1

Type RM Length L Ch R = 1 ,8905    ,497,497,497
BEGIN DESCRIPTION:
LAKE CREEK TRIBUTARY NO. 4 16.0
END DESCRIPTION:
XS GIS Cut Line= 3
      3740417.83     10107061.03      3740367.47     10106944.33
      3740267.86     10105761.12
#Sta/Elev= 30
  4872.9  223.99  4910.8  222.02  4920.1  219.38  4934.4  216.05  4963.3  214.45
  4981.4  211.31  4986.8   212.1  4992.7  206.83  4999.1  206.43  5004.1  206.43
  5023.3  213.87  5063.5  215.47  5183.9  213.27  5404.7  212.66  5424.8  214.58
  5605.4  213.98  5615.4  212.61  5635.5  214.08  5645.5  213.14 5647.35211.7262
  5650.8  209.09  5655.8  210.27  5671.3  203.59    5680  203.59 5710.03211.7536
  5725.8  214.92  5755.9   216.6  5869.1  220.31    6057  229.55  6187.4  233.42
#Mann= 5 ,-1 , 0
  4872.9     .11       0  4920.1     .15       0 5647.35     .09       0
 5710.03     .15       0  5869.1     .11       0
Bank Sta=5647.35,5710.03
XS Rating Curve= 0 ,0
Exp/Cntr=0.3,0.1

Type RM Length L Ch R = 1 ,8408    ,497,497,497
BEGIN DESCRIPTION:
LAKE CREEK TRIBUTARY NO. 4 15.0
END DESCRIPTION:
XS GIS Cut Line= 3
      3740858.37     10107266.51      3740786.71     10106853.89
      3740417.85     10105961.08
#Sta/Elev= 30
  4581.2  228.36  4667.4  226.85  4698.4  223.56  4791.8  218.95  4799.9  217.99
  4820.2  210.12  4828.1  209.35  4840.5   211.7  4860.8  212.38  4965.7  211.48
  4982.6  209.02  4998.9  204.03  5033.2  211.79  5115.8  213.05  5216.8  211.31
  5453.7  212.07  5468.3  211.84    5483  208.11  5496.2  202.01  5512.3  202.74
  5522.4  208.01  5530.8  210.95  5536.3  208.08  5554.8  212.11  5560.2  211.07
  5576.5  214.11  5613.4  214.76  5619.8  216.31  5708.7  216.59    5966  225.53
#Mann= 5 ,-1 , 0
  4581.2     .11       0  4828.1     .15       0    5483     .09       0
  5522.4     .15       0  5708.7     .11       0
Bank Sta=5483,5522.4
XS Rating Curve= 0 ,0
Exp/Cntr=0.3,0.1