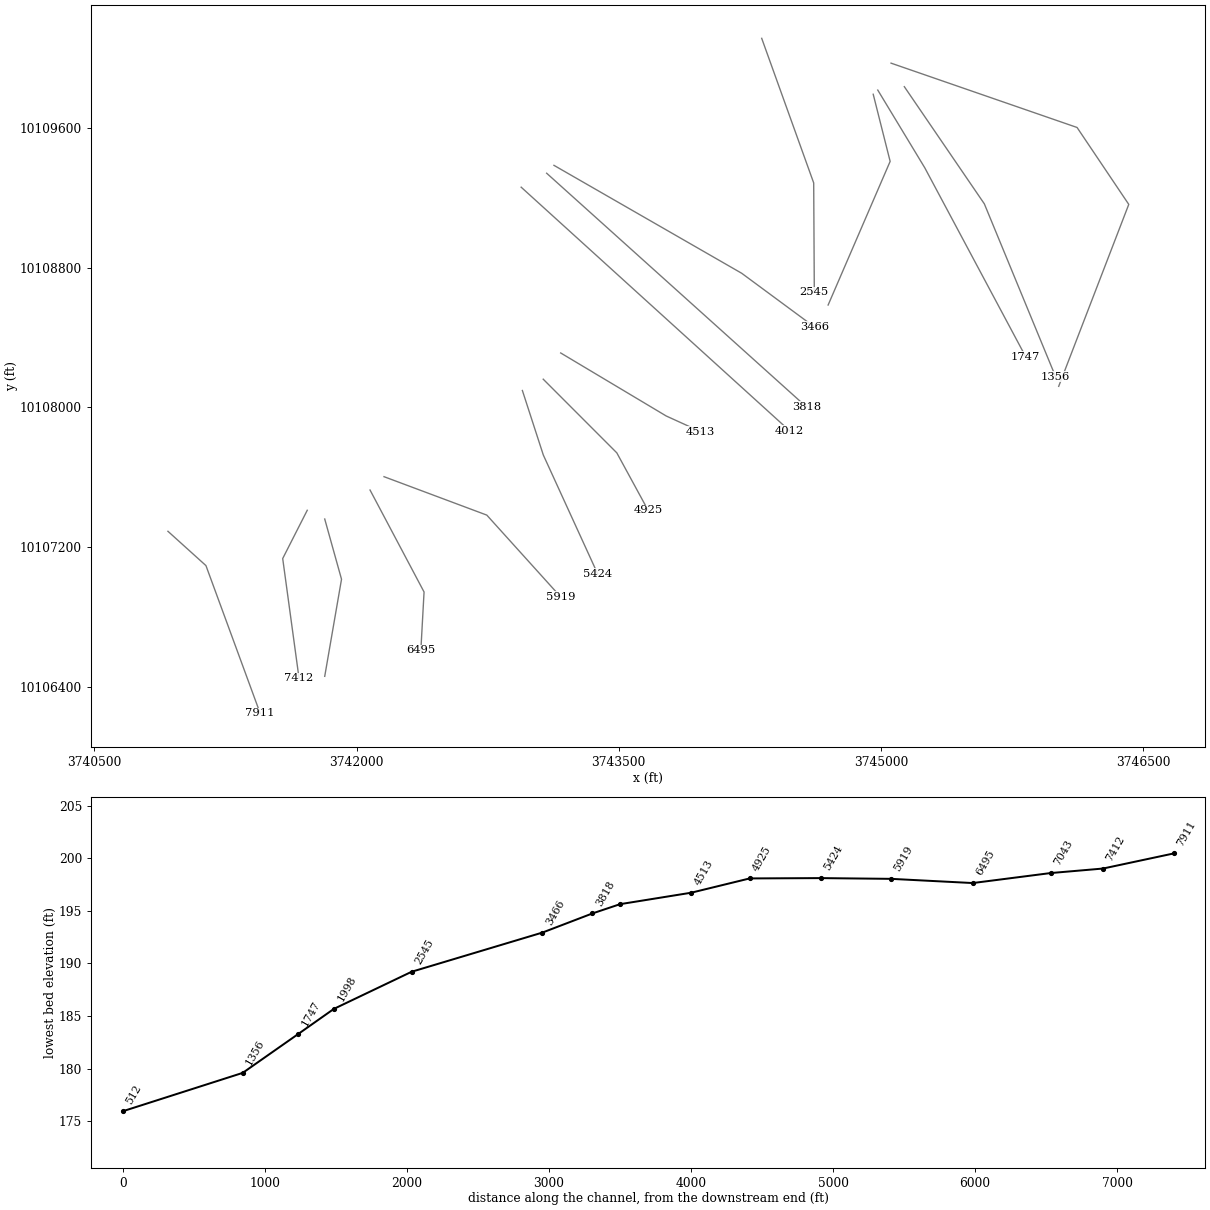
HEC-RAS study LAKE CREEK TRIBUTARY NO 4.prj: LAKE CREEK TRIBUTARY NO 4 Base Level Engineering

--- LAKE CREEK TRIBUTARY NO 4.g01 (geometry) --- (continued)

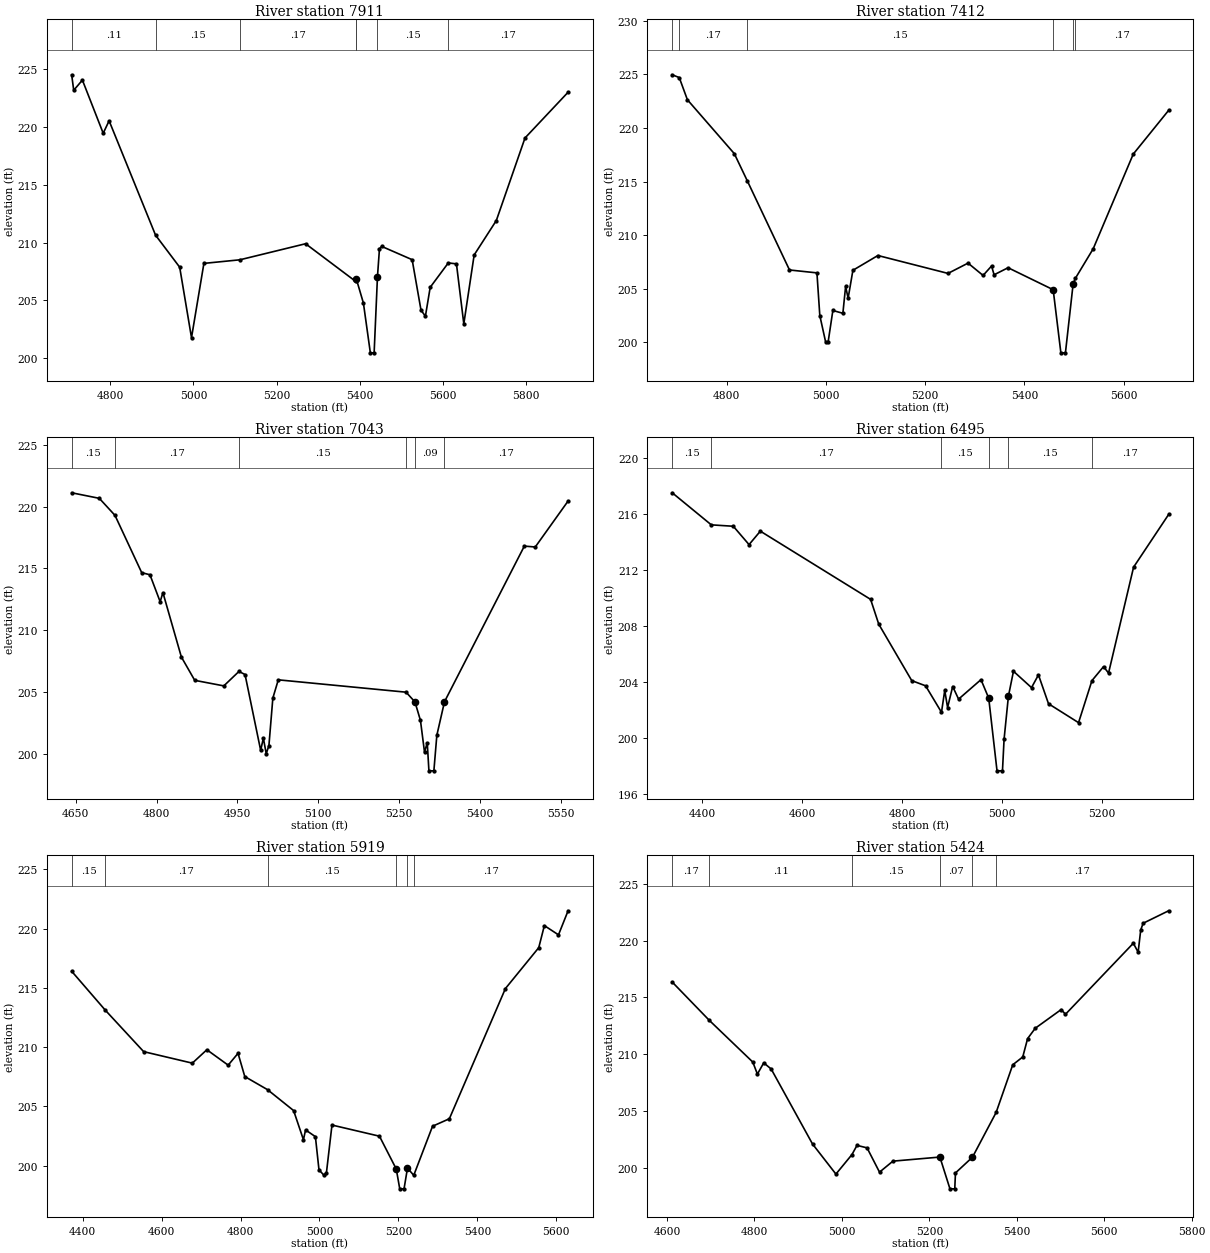
Type RM Length L Ch R = 1 ,7911    ,499,499,499
BEGIN DESCRIPTION:
LAKE CREEK TRIBUTARY NO. 4 14.0
END DESCRIPTION:
XS GIS Cut Line= 3
      3740920.86     10107290.78       3741138.3     10107094.55
      3741448.64     10106249.11
#Sta/Elev= 30
  4707.1  224.53    4712  223.19  4732.9  224.07  4782.9  219.47  4797.1  220.55
  4908.8  210.65  4966.8  207.88  4995.2  201.78    5025  208.21  5111.5  208.52
  5269.5  209.91  5389.6  206.66  5391.5  206.86  5408.5  204.78  5425.2  200.47
  5434.3  200.47 5442.31207.0605  5447.1  209.47  5452.5  209.68  5525.7  208.53
    5547  204.16  5557.6  203.64  5569.1  206.14  5612.6  208.25  5632.2  208.17
  5649.9  202.98  5674.8  208.94  5728.1  211.92    5797  219.06  5900.6  223.02
#Mann= 7 ,-1 , 0
  4707.1     .11       0  4908.8     .15       0  5111.5     .17       0
  5389.6     .15       0  5391.5     .09       0 5442.31     .15       0
  5612.6     .17       0
Bank Sta=5391.5,5442.31
XS Rating Curve= 0 ,0
Exp/Cntr=0.3,0.1

Type RM Length L Ch R = 1 ,7412    ,369,369,369
BEGIN DESCRIPTION:
LAKE CREEK TRIBUTARY NO. 4 13.0
END DESCRIPTION:
XS GIS Cut Line= 3
      3741717.85     10107411.06       3741577.4     10107134.92
      3741670.86     10106450.48
#Sta/Elev= 30
  4690.2  224.97  4704.4  224.71  4720.8  222.64  4815.4  217.61  4841.4  215.09
  4926.6  206.76  4981.9  206.49  4987.7  202.51  4999.4  200.05  5004.5  200.05
    5014  202.98  5034.2  202.72  5039.7  205.22  5044.8  204.13  5054.4  206.73
  5104.8  208.11  5246.1  206.44  5286.5   207.4  5316.8  206.25  5333.9  207.13
    5339  206.31  5367.2  206.97  5458.1  204.92  5473.6  199.03  5482.8  199.03
  5498.4  205.49  5502.7  205.97  5538.8  208.74  5619.5  217.57  5690.8  221.65
#Mann= 6 ,-1 , 0
  4690.2     .11       0  4704.4     .17       0  4841.4     .15       0
  5458.1     .09       0  5498.4     .15       0  5502.7     .17       0
Bank Sta=5458.1,5498.4
XS Rating Curve= 0 ,0
Exp/Cntr=0.3,0.1

Type RM Length L Ch R = 1 ,7043    ,548,548,548
BEGIN DESCRIPTION:
LAKE CREEK TRIBUTARY NO. 4 12.0
END DESCRIPTION:
XS GIS Cut Line= 3
      3741817.85     10107361.07      3741913.92     10107016.47
      3741817.85     10106461.05
#Sta/Elev= 30
  4642.5  221.12  4693.8  220.67  4722.9  219.29  4772.5  214.65  4787.8  214.48
  4806.7   212.3  4811.9  213.03  4846.1  207.82  4870.9  205.93  4924.9  205.48
    4953  206.65  4964.3   206.4  4993.3  200.26  4998.3  201.25  5003.6  199.99
  5008.6  200.64  5015.9  204.49    5026  205.97  5263.2  204.97  5279.7  204.18
  5289.9  202.68  5297.4  200.12  5302.5  200.87  5305.6   198.6  5314.8   198.6
  5320.3  201.48  5334.5204.1951  5482.7   216.8    5503  216.73  5563.9  220.45
#Mann= 6 ,-1 , 0
  4642.5     .15       0  4722.9     .17       0    4953     .15       0
  5263.2     .17       0  5279.7     .09       0  5334.5     .17       0
Bank Sta=5279.7,5334.5
XS Rating Curve= 0 ,0
Exp/Cntr=0.3,0.1

Type RM Length L Ch R = 1 ,6495    ,576,576,576
BEGIN DESCRIPTION:
LAKE CREEK TRIBUTARY NO. 4 11.0
END DESCRIPTION:
XS GIS Cut Line= 3
      3742077.11      10107526.9      3742386.14     10106943.56
      3742367.85      10106611.1
#Sta/Elev= 30
  4339.7   217.5  4417.9  215.21  4461.9  215.11  4493.4   213.8    4516  214.76
  4736.6  209.89  4752.9  208.12  4818.9  204.09  4846.6  203.72  4878.4  201.83
  4884.9  203.39  4890.6  202.17  4900.8  203.67  4912.6  202.77  4957.4  204.16
  4972.9  202.84  4989.5  197.65  5000.4  197.65  5003.6   199.9  5012.3  202.98
  5022.4  204.76  5058.5  203.59  5072.4   204.5  5092.5  202.44  5152.6  201.09
  5179.4  204.09  5202.6  205.09  5212.6  204.63  5262.7  212.19  5332.8  215.95
#Mann= 6 ,-1 , 0
  4339.7     .15       0  4417.9     .17       0  4878.4     .15       0
  4972.9     .09       0  5012.3     .15       0  5179.4     .17       0
Bank Sta=4972.9,5012.3
XS Rating Curve= 0 ,0
Exp/Cntr=0.3,0.1

Type RM Length L Ch R = 1 ,5919    ,495,495,495
BEGIN DESCRIPTION:
LAKE CREEK TRIBUTARY NO. 4 10.0
END DESCRIPTION:
XS GIS Cut Line= 3
      3742157.01     10107603.26      3742745.06     10107383.45
      3743167.23     10106915.95
#Sta/Elev= 30
  4372.2   216.4  4457.3  213.12  4554.6  209.62  4677.9  208.65  4714.7  209.78
  4768.7  208.48  4793.7  209.48  4810.8  207.52  4868.6  206.41  4934.5  204.65
  4959.4  202.19  4964.8  203.02  4989.7  202.45  4998.8  199.65  5010.8  199.22
  5017.5  199.36  5031.7  203.43    5152  202.49  5194.6  199.72  5203.4  198.05
  5214.3  198.05    5223   199.8  5238.9  199.19  5286.5  203.33  5329.1  203.96
  5471.1  214.94  5555.6  218.39  5569.8  220.25  5605.6  219.47  5629.9   221.5
#Mann= 6 ,-1 , 0
  4372.2     .15       0  4457.3     .17       0  4868.6     .15       0
  5194.6     .09       0    5223     .15       0  5238.9     .17       0
Bank Sta=5194.6,5223
XS Rating Curve= 0 ,0
Exp/Cntr=0.3,0.1

Type RM Length L Ch R = 1 ,5424    ,499,499,499
BEGIN DESCRIPTION:
LAKE CREEK TRIBUTARY NO. 4 9.0
END DESCRIPTION:
XS GIS Cut Line= 3
      3742948.63     10108096.35      3743068.39     10107727.29
      3743379.21     10107047.69
#Sta/Elev= 30
    4612  216.34  4696.7  212.97  4796.3  209.29  4806.8  208.23  4821.3  209.22
  4838.3  208.68  4932.9  202.07  4986.4  199.42  5023.1  201.14  5034.6  201.95
  5057.6  201.73  5086.1  199.59  5116.8  200.56  5224.2  200.92  5247.2  198.12
  5258.2  198.12  5259.8  199.52  5298.7  200.91  5352.8  204.85  5390.8  209.05
  5413.7  209.74  5424.8  211.36  5442.3  212.27  5501.7  213.92  5511.4   213.5
  5666.6  219.76  5677.6  218.97  5683.5  220.93    5689  221.52  5747.3  222.62
#Mann= 6 ,-1 , 0
    4612     .17       0  4696.7     .11       0  5023.1     .15       0
  5224.2     .07       0  5298.7     .15       0  5352.8     .17       0
Bank Sta=5224.2,5298.7
XS Rating Curve= 0 ,0
Exp/Cntr=0.3,0.1

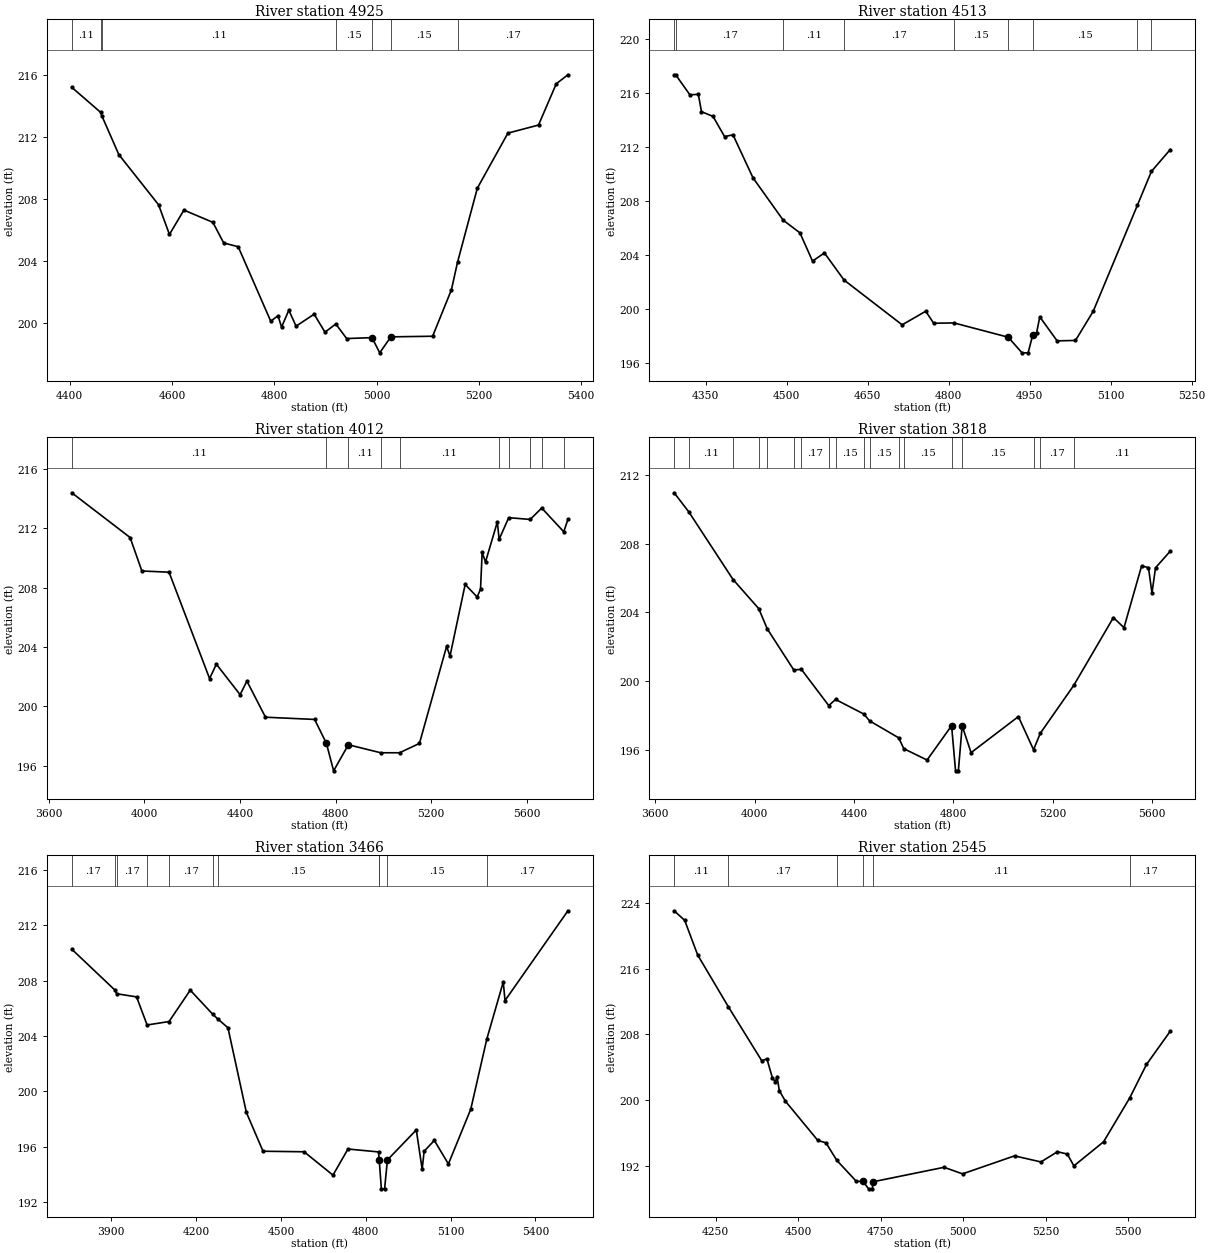
Type RM Length L Ch R = 1 ,4925    ,412,412,412
BEGIN DESCRIPTION:
LAKE CREEK TRIBUTARY NO. 4 8.0
END DESCRIPTION:
XS GIS Cut Line= 3
      3743067.85     10108161.07      3743488.86     10107739.63
      3743667.87     10107411.03
#Sta/Elev= 30
  4404.3   215.2  4460.7  213.59  4463.4  213.34  4496.2  210.87    4574  207.63
  4595.2  205.72  4623.5  207.29  4680.1   206.5  4701.3  205.17  4729.6  204.93
  4793.2  200.13  4807.4  200.48  4814.4  199.75  4828.6  200.84  4842.7  199.81
  4878.1  200.58  4899.3  199.42  4920.4  199.95  4941.7  199.01  4991.2  199.07
  5006.3  198.09    5028  199.12  5109.7  199.16  5146.4  202.15  5158.4  203.93
  5197.1   208.7  5256.9  212.25  5316.7  212.77  5351.4  215.43  5374.2  216.01
#Mann= 7 ,-1 , 0
  4404.3     .11       0  4460.7     .17       0  4463.4     .11       0
  4920.4     .15       0  4991.2     .09       0    5028     .15       0
  5158.4     .17       0
Bank Sta=4991.2,5028
XS Rating Curve= 0 ,0
Exp/Cntr=0.3,0.1

Type RM Length L Ch R = 1 ,4513    ,501,501,501
BEGIN DESCRIPTION:
LAKE CREEK TRIBUTARY NO. 4 7.0
END DESCRIPTION:
XS GIS Cut Line= 3
      3743167.81     10108311.09      3743771.55      10107950.5
      3743967.82     10107861.09
#Sta/Elev= 30
  4291.4  217.38  4294.6  217.36  4320.6  215.89  4336.2  215.93    4342  214.64
  4363.4  214.29  4384.8  212.79  4400.4  212.92  4437.4  209.73  4493.4  206.58
  4524.4  205.64  4547.7  203.54  4569.7  204.15    4606  202.14  4713.7  198.81
  4757.4  199.82    4772  198.93  4809.8  198.95  4910.2  197.89  4935.7  196.73
    4947  196.73  4955.4  198.04  4962.7  198.22  4968.6   199.4  5000.7  197.62
  5034.7  197.65  5067.5  199.81  5149.4  207.69  5175.3   210.2  5210.3  211.83
#Mann= 9 ,-1 , 0
  4291.4     .11       0  4294.6     .17       0  4493.4     .11       0
    4606     .17       0  4809.8     .15       0  4910.2     .09       0
  4955.4     .15       0  5149.4     .11       0  5175.3     .17       0
Bank Sta=4910.2,4955.4
XS Rating Curve= 0 ,0
Exp/Cntr=0.3,0.1

Type RM Length L Ch R = 1 ,4012    ,194,194,194
BEGIN DESCRIPTION:
Mapping XS 9969d760
END DESCRIPTION:
XS GIS Cut Line= 2
      3742941.71     10109259.51      3744478.56      10107864.9
#Sta/Elev= 30
  3696.9  214.41  3940.8  211.39  3990.1  209.13  4103.7  209.05  4273.3  201.87
  4301.7  202.84    4401  200.78  4429.4   201.7  4507.1  199.26  4712.6  199.11
  4761.9   197.5  4792.1  195.64  4853.8   197.4  4989.1  196.86  5067.8  196.86
  5151.1  197.49  5264.7  204.04  5278.9  203.39  5342.4  208.22  5392.4  207.38
  5406.6   207.9  5413.4  210.38  5427.5  209.74  5476.9  212.44  5484.5  211.27
  5524.5  212.73  5614.4  212.61  5662.6  213.38  5754.7  211.78  5772.2  212.61
#Mann= 10 ,-1 , 0
  3696.9     .11       0  4761.9     .09       0  4853.8     .11       0
  4989.1     .15       0  5067.8     .11       0  5484.5     .17       0
  5524.5     .11       0  5614.4     .17       0  5662.6     .11       0
  5754.7     .17       0
Bank Sta=4761.9,4853.8
XS Rating Curve= 0 ,0
Exp/Cntr=0.3,0.1

Type RM Length L Ch R = 1 ,3818    ,352,352,352
BEGIN DESCRIPTION:
Mapping XS 6d947068
END DESCRIPTION:
XS GIS Cut Line= 2
      3743087.53     10109339.38      3744573.28     10108002.91
#Sta/Elev= 30
  3675.8  210.96  3734.7  209.85  3913.4   205.9  4016.6  204.21  4050.9  203.03
  4157.6  200.64  4188.4  200.67  4298.6  198.56  4325.9  198.92  4439.6  198.07
  4463.3  197.67  4580.5  196.68  4600.8  196.05  4694.6  195.39  4793.3  197.39
  4809.3  194.76  4820.6  194.76  4835.9  197.38  4871.8  195.82  5062.4  197.92
  5123.4  195.99  5150.7  196.95  5285.4  199.74  5445.1  203.69  5487.7   203.1
  5558.7   206.7  5586.3   206.6  5600.5  205.12  5614.7  206.59  5674.2  207.56
#Mann= 18 ,-1 , 0
  3675.8     .17       0  3734.7     .11       0  3913.4     .17       0
  4016.6     .11       0  4050.9     .17       0  4157.6     .11       0
  4188.4     .17       0  4298.6     .11       0  4325.9     .15       0
  4439.6     .11       0  4463.3     .15       0  4580.5     .11       0
  4600.8     .15       0  4793.3     .09       0  4835.9     .15       0
  5123.4     .11       0  5150.7     .17       0  5285.4     .11       0
Bank Sta=4793.3,4835.9
XS Rating Curve= 0 ,0
Exp/Cntr=0.3,0.1

Type RM Length L Ch R = 1 ,3466    ,921,921,921
BEGIN DESCRIPTION:
LAKE CREEK TRIBUTARY NO. 4 6.0
END DESCRIPTION:
XS GIS Cut Line= 3
      3743129.24      10109384.5      3744203.64     10108766.83
      3744617.82      10108461.1
#Sta/Elev= 30
  3760.7  210.27  3912.4  207.33  3919.7  207.05  3989.8  206.82    4027  204.79
  4104.6  205.04  4179.5  207.31  4259.8  205.55  4276.2  205.24  4312.8  204.59
  4377.9  198.47  4436.8  195.66    4582  195.62  4684.1  193.93  4737.2  195.82
  4845.1  195.61 4847.64195.0359  4855.2  192.94  4866.6  192.94  4876.7  195.03
  4978.7   197.2  4999.5  194.35  5006.4  195.66  5042.5  196.44  5092.2  194.74
  5171.3   198.7  5228.1  203.78  5286.2   207.9  5292.4  206.56  5514.8  213.05
#Mann= 11 ,-1 , 0
  3760.7     .17       0  3912.4     .11       0  3919.7     .17       0
    4027     .11       0  4104.6     .17       0  4259.8     .11       0
  4276.2     .15       0  4845.1     .12       0 4847.64     .09       0
  4876.7     .15       0  5228.1     .17       0
Bank Sta=4847.64,4876.7
XS Rating Curve= 0 ,0
Exp/Cntr=0.3,0.1

Type RM Length L Ch R = 1 ,2545    ,547,547,547
BEGIN DESCRIPTION:
LAKE CREEK TRIBUTARY NO. 4 5.0
END DESCRIPTION:
XS GIS Cut Line= 3
      3744317.85     10110111.09       3744615.3     10109283.83
      3744618.78     10108658.85
#Sta/Elev= 30
    4124  223.02  4155.9  221.86  4195.5  217.63  4288.6  211.33  4389.7  204.78
  4405.2  205.02  4421.6  202.74  4430.6   202.2  4435.9  202.86  4442.8  201.15
  4461.3  199.87  4559.7  195.09  4584.2  194.81    4617  192.68  4676.6  190.11
  4696.4  190.14  4713.4  189.21  4724.8  189.21  4727.2  190.07  4942.3  191.83
  4998.3  191.03  5155.9  193.22  5235.9  192.48  5285.9  193.72  5315.9  193.44
  5335.9     192  5425.9  194.93  5505.2  200.27  5555.9  204.33  5628.1  208.38
#Mann= 6 ,-1 , 0
    4124     .11       0  4288.6     .17       0    4617     .11       0
  4696.4     .09       0  4727.2     .11       0  5505.2     .17       0
Bank Sta=4696.4,4727.2
XS Rating Curve= 0 ,0
Exp/Cntr=0.3,0.1

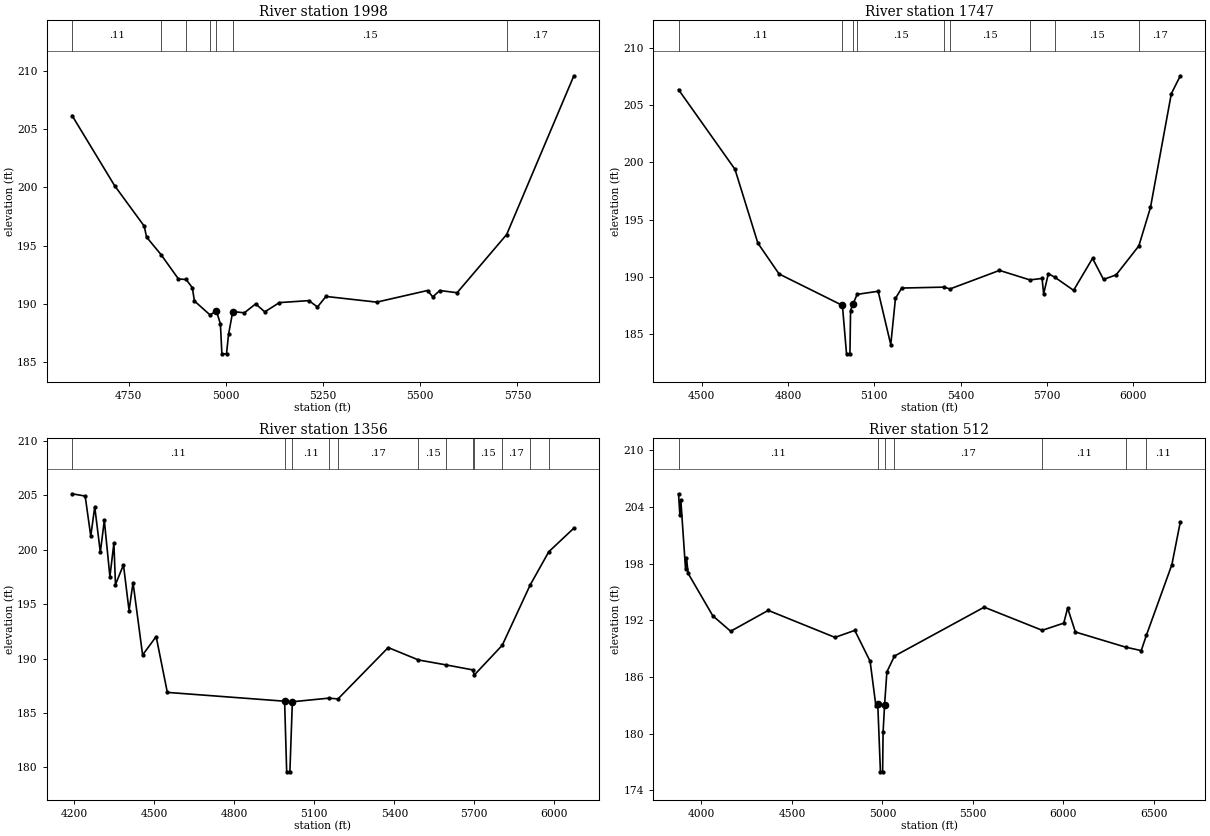
Type RM Length L Ch R = 1 ,1998    ,251,251,251
BEGIN DESCRIPTION:
LAKE CREEK TRIBUTARY NO. 4 4.0
END DESCRIPTION:
XS GIS Cut Line= 3
       3744955.8     10109791.16      3745052.68     10109407.09
      3744697.85     10108585.32
#Sta/Elev= 30
  4603.9  206.19  4713.4  200.15  4789.6  196.67  4795.5  195.73  4832.8  194.22
  4877.7  192.12  4897.3  192.08  4913.4  191.37  4918.7  190.23  4958.9  189.03
  4975.3  189.37  4985.6  188.25  4989.4  185.68  5001.3  185.68  5006.6  187.37
  5017.4  189.32  5047.3  189.21  5076.3  189.98  5099.8  189.29  5137.3  190.09
  5213.5  190.26  5235.3  189.71  5257.2  190.62  5387.8  190.13  5518.5  191.13
  5532.1  190.58  5550.1  191.13  5594.7  190.94  5722.2  195.95  5895.1  209.61
#Mann= 7 ,-1 , 0
  4603.9     .11       0  4832.8     .17       0  4897.3     .11       0
  4958.9     .15       0  4975.3     .07       0  5017.4     .15       0
  5722.2     .17       0
Bank Sta=4975.3,5017.4
XS Rating Curve= 0 ,0
Exp/Cntr=0.3,0.1

Type RM Length L Ch R = 1 ,1747    ,391,391,391
BEGIN DESCRIPTION:
LAKE CREEK TRIBUTARY NO. 4 3.0
END DESCRIPTION:
XS GIS Cut Line= 3
      3744981.85     10109815.04      3745250.93     10109370.19
      3745828.17      10108289.5
#Sta/Elev= 30
  4419.2  206.34  4615.5  199.39  4695.1  192.95  4768.8  190.26 4989.16187.5158
  5003.4  183.29  5015.3  183.29  5017.5  187.07  5025.6  187.63  5040.5  188.48
  5113.4  188.75  5157.3  184.09  5173.6  188.13  5195.5  189.03    5343  189.11
  5363.1  188.95  5535.4  190.57  5641.2  189.74  5683.4  189.87    5689  188.52
  5705.3  190.29  5728.6  189.96  5793.1  188.83    5859  191.62  5897.2  189.78
  5941.1  190.18  6020.1  192.71  6060.5  196.06    6133  205.99  6164.3  207.55
#Mann= 9 ,-1 , 0
  4419.2     .11       0 4989.16     .07       0  5025.6     .11       0
  5040.5     .15       0    5343     .17       0  5363.1     .15       0
  5641.2     .17       0  5728.6     .15       0  6020.1     .17       0
Bank Sta=4989.16,5025.6
XS Rating Curve= 0 ,0
Exp/Cntr=0.3,0.1

Type RM Length L Ch R = 1 ,1356    ,844,844,844
BEGIN DESCRIPTION:
LAKE CREEK TRIBUTARY NO. 4 2.0
END DESCRIPTION:
XS GIS Cut Line= 3
      3745133.76     10109834.57      3745591.64     10109164.03
       3745999.3     10108175.22
#Sta/Elev= 30
  4191.6  205.14  4240.7  204.93  4261.7  201.25  4276.6  203.94  4297.6  199.76
  4312.5   202.7  4333.5  197.52  4348.4   200.6  4354.4   196.8  4384.3  198.61
  4405.3  194.41  4420.2  196.98  4456.1  190.33  4506.9  192.02  4548.8  186.89
  4988.5  186.08  4996.3  179.59  5008.3  179.59  5017.6  186.03  5153.8  186.36
  5188.7  186.29    5377  191.01  5490.5  189.87  5595.2  189.41  5693.7  188.96
  5699.9  188.49  5804.6  191.22  5909.3  196.76  5979.3  199.82  6073.1  201.98
#Mann= 12 ,-1 , 0
  4191.6     .11       0  4988.5     .06       0  5017.6     .11       0
  5153.8     .15       0  5188.7     .17       0  5490.5     .15       0
  5595.2     .17       0  5693.7     .11       0  5699.9     .15       0
  5804.6     .17       0  5909.3     .15       0  5979.3     .11       0
Bank Sta=4988.5,5017.6
XS Rating Curve= 0 ,0
Exp/Cntr=0.3,0.1

Type RM Length L Ch R = 1 ,512     ,0,0,0
BEGIN DESCRIPTION:
LAKE CREEK TRIBUTARY NO. 4 1.0
END DESCRIPTION:
XS GIS Cut Line= 4
      3745057.81     10109969.14      3746122.07     10109601.08
      3746417.85     10109161.07      3746016.98     10108120.18
#Sta/Elev= 30
  3873.9  205.39  3881.3  203.11  3886.5  204.75  3912.4  197.46  3917.7  198.63
  3926.8  196.96    4063  192.47  4161.8  190.83  4369.4  193.04  4738.1  190.18
  4847.4  190.92  4932.1  187.65  4963.8  182.96  4974.4  183.11  4989.1  175.94
  5001.2  175.94  5003.7  180.12  5012.1  183.04  5024.7  186.52  5066.5   188.2
  5562.3  193.38  5882.8  190.93  6001.7  191.69  6023.1  193.29    6066  190.75
    6343  189.15  6429.7  188.78  6458.4  190.42  6598.9  197.88  6645.6  202.42
#Mann= 7 ,-1 , 0
  3873.9     .11       0  4974.4     .06       0  5012.1     .11       0
  5066.5     .17       0  5882.8     .11       0    6343     .15       0
  6458.4     .11       0
Bank Sta=4974.4,5012.1
XS Rating Curve= 0 ,0
Exp/Cntr=0.3,0.1

Chan Stop Cuts=-1
Use User Specified Reach Order=0
Composite Channel Slope=5