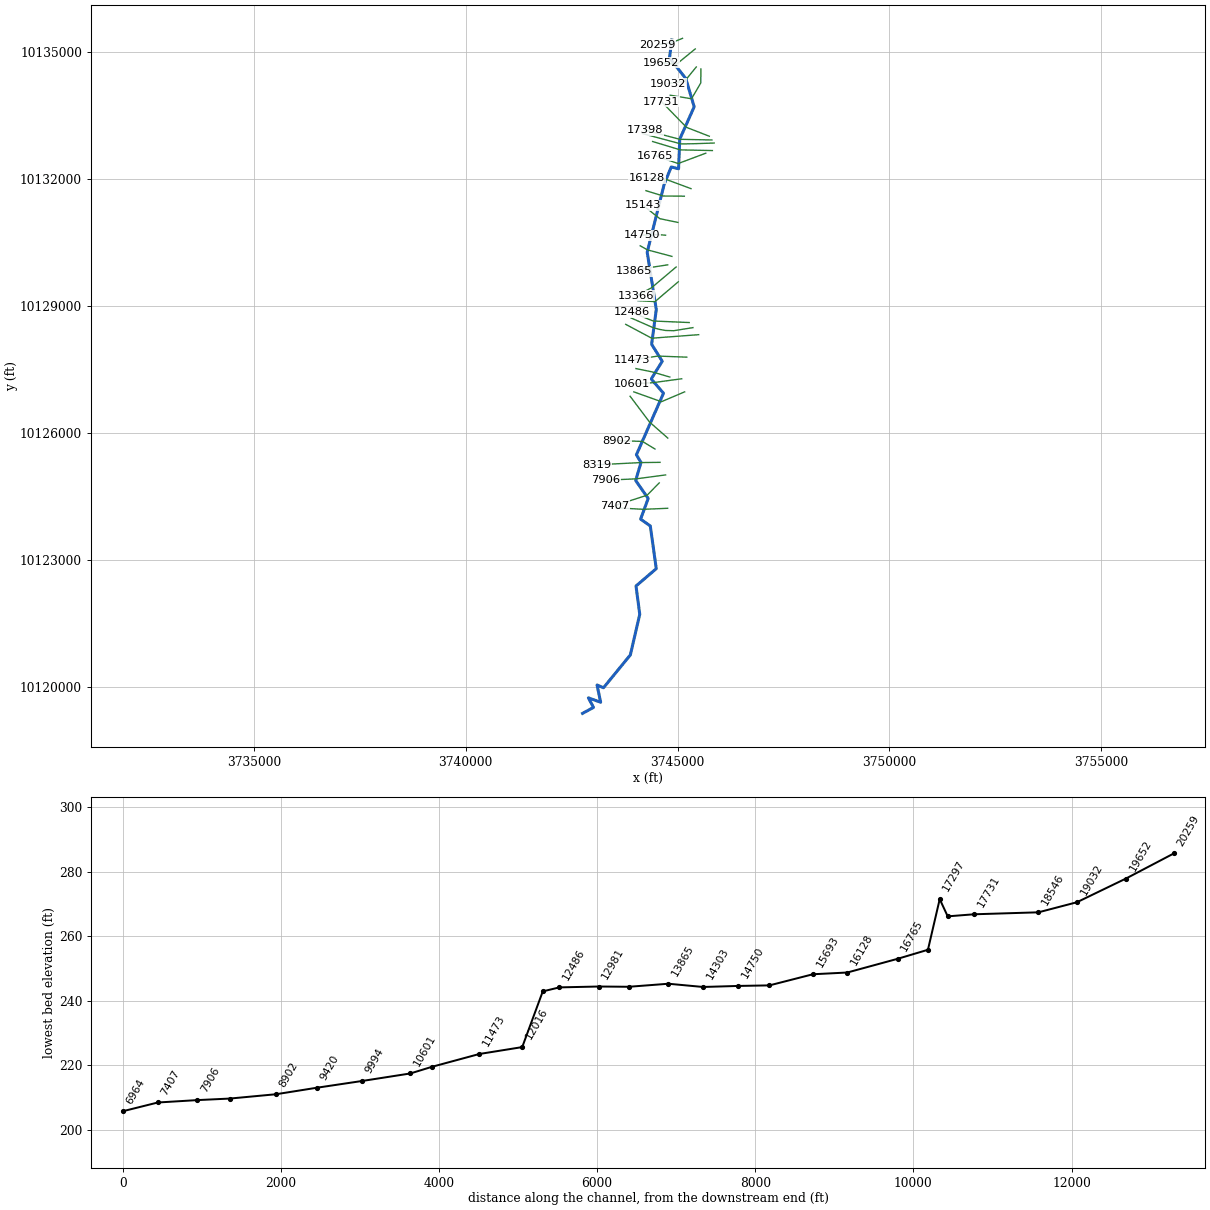
--- LAKE CREEK TRIBUTARY NO 5.prj (project) ---

Proj Title=LAKE CREEK TRIBUTARY NO 5 Base Level Engineering
Current Plan=p01
Default Exp/Contr=0.3,0.1
English Units
Geom File=g01
Flow File=f01
Plan File=p01
Y Axis Title=Elevation
X Axis Title(PF)=Main Channel Distance
X Axis Title(XS)=Station
BEGIN DESCRIPTION:
LAKE CREEK TRIBUTARY NO 5
END DESCRIPTION:
DSS Export Rating Curves= 0
DSS Export Rating Curve Sorted= 0
DSS Export Volume Flow Curves= 0
DXF OffsetX= 0
DXF OffsetY= 0
DXF ScaleX= 1
DXF ScaleY= 10

--- LAKE CREEK TRIBUTARY NO 5.p01 (plan) ---

Plan Title=Multiple Run
Short Identifier=Multiple
Geom File=g01
Flow File=f01
Subcritical Flow
K Sum by GR= 0
Std Step Tol= 0.01
Critical Tol= 0.01
Num of Std Step Trials= 20
Max Error Tol= 0.3
Flow Tol Ratio= 0.001
Split Flow NTrial= 30
Split Flow Tol= 0.02
Split Flow Ratio= 0.02
Log Output Level= 0
Friction Slope Method= 1
Unsteady Friction Slope Method= 2
Unsteady Bridges Friction Slope Method= 1
Parabolic Critical Depth
Global Vel Dist=  1 , 1 , 1
Global Log Level= 0
CheckData=True
Encroach Param= -1, 0, 0, 0
BEGIN DESCRIPTION:
Multiple Run
END DESCRIPTION:

--- LAKE CREEK TRIBUTARY NO 5.f01 (steady flow) ---

Flow Title=Multiple
Program Version=4.10
Number of Profiles= 7
Profile Names=10-year,25-year,50-year,1pct_min,100-year,1pct_plu,500-year
River Rch & RM=LAKE CREEK TRIBU,Reach-1         ,20259
     622     850    1156     518    1565    4726    2964
River Rch & RM=LAKE CREEK TRIBU,Reach-1         ,17297
     890    1241    1712     777    2348    7091    4561
River Rch & RM=LAKE CREEK TRIBU,Reach-1         ,14750
    1014    1417    1955     887    2678    8087    5196
River Rch & RM=LAKE CREEK TRIBU,Reach-1         ,12016
    1254    1761    2438    1108    3346   10105    6522
River Rch & RM=LAKE CREEK TRIBU,Reach-1         ,6964
    1453    2051    2851    1299    3923   11847    7692
River Rch & RM=LAKE CREEK TRIBU,Reach-1         ,2995
    1471    2075    2880    1311    3959   11956    7742
Boundary for River Rch & Prof#=LAKE CREEK TRIBU,Reach-1         , 1
Up Type= 0
Dn Type= 3
Dn Slope=0.005
Boundary for River Rch & Prof#=LAKE CREEK TRIBU,Reach-1         , 2
Up Type= 0
Dn Type= 3
Dn Slope=0.005
Boundary for River Rch & Prof#=LAKE CREEK TRIBU,Reach-1         , 3
Up Type= 0
Dn Type= 3
Dn Slope=0.005
Boundary for River Rch & Prof#=LAKE CREEK TRIBU,Reach-1         , 4
Up Type= 0
Dn Type= 3
Dn Slope=0.005
Boundary for River Rch & Prof#=LAKE CREEK TRIBU,Reach-1         , 5
Up Type= 0
Dn Type= 3
Dn Slope=0.005
Boundary for River Rch & Prof#=LAKE CREEK TRIBU,Reach-1         , 6
Up Type= 0
Dn Type= 3
Dn Slope=0.005
Boundary for River Rch & Prof#=LAKE CREEK TRIBU,Reach-1         , 7
Up Type= 0
Dn Type= 3
Dn Slope=0.005
DSS Import GetInterval= 0
DSS Import GetPeak= 0
DSS Import FillOption= 0

--- LAKE CREEK TRIBUTARY NO 5.g01 (geometry) ---

Geom Title=Existing Conditions
Program Version=4.10

River Reach=LAKE CREEK TRIBU,Reach-1
Reach XY= 30
      3744863.82     10135271.52      3744810.77     10134846.83
      3745194.61     10134362.06      3745393.05     10133694.29
      3745052.87     10132932.03      3745024.52     10132229.62
      3744851.28     10132273.72      3744684.34     10131864.24
      3744284.31     10130257.82      3744498.23     10128906.84
      3744388.35      10128084.7      3744638.76     10127684.04
      3744378.66     10127264.84      3744668.26     10126928.99
      3744029.18     10125474.33       3744137.9     10125295.47
      3744012.76     10124866.31      3744307.44     10124442.45
      3744128.51      10123954.8      3744356.84     10123794.35
      3744498.04     10122784.89      3744019.54     10122374.49
      3744108.14     10121707.02      3743885.95      10120746.9
       3743252.6     10119971.83      3743100.27     10120037.17
      3743185.14     10119629.75      3742895.82      10119733.4
      3743016.23      10119507.7      3742758.23     10119366.84

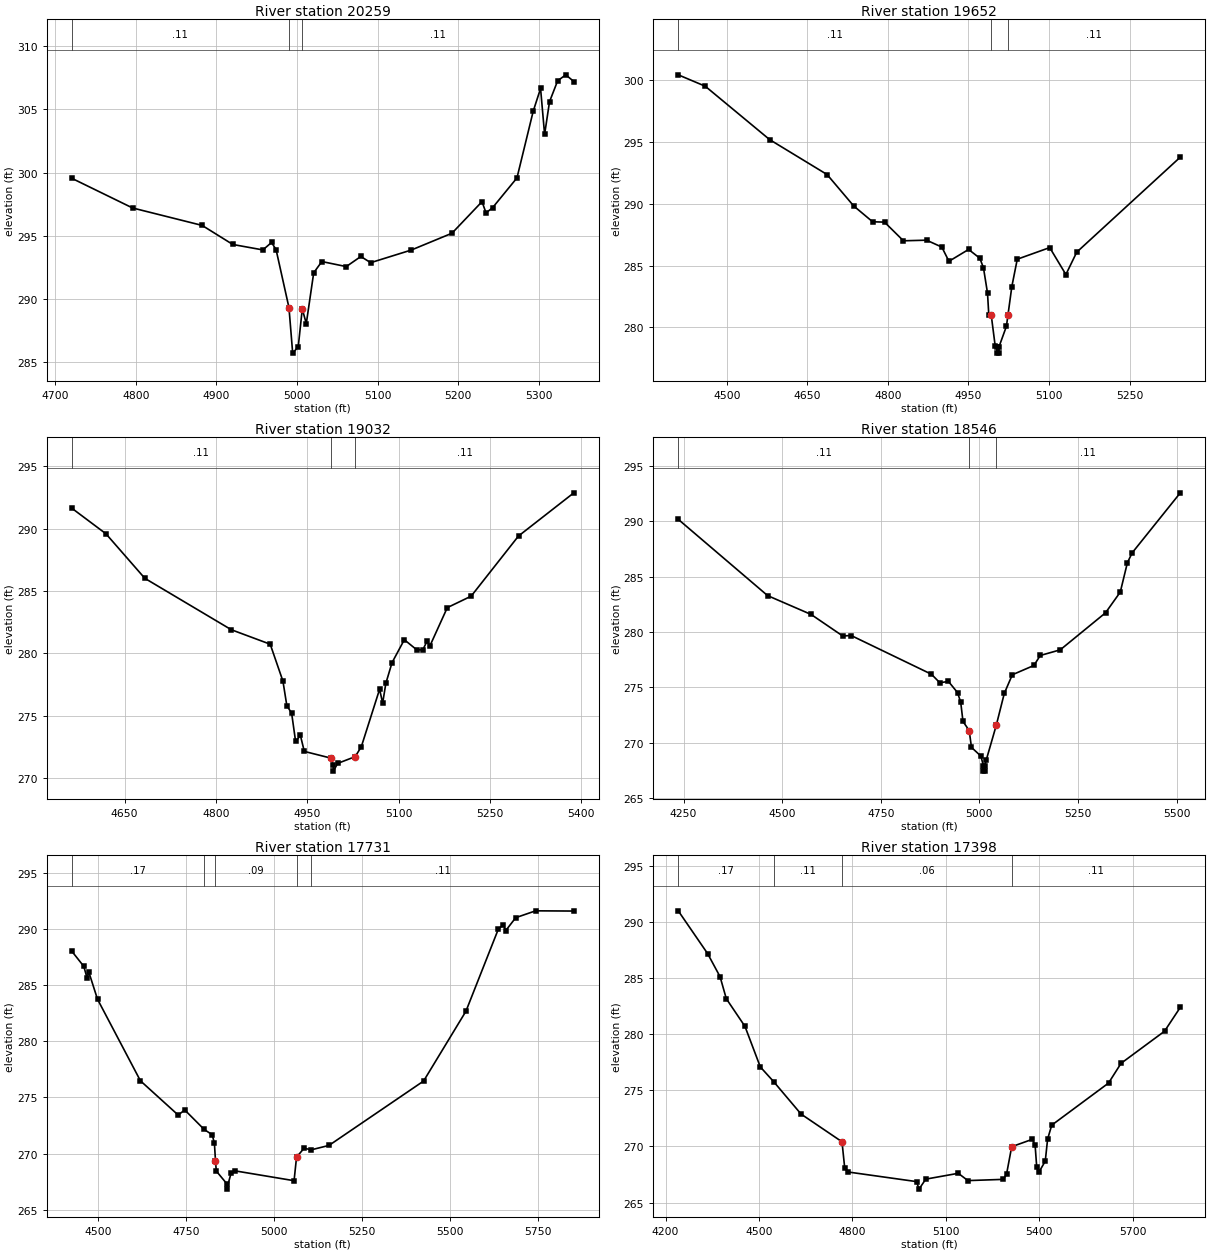
Type RM Length L Ch R = 1 ,20259   ,607,607,607
BEGIN DESCRIPTION:
LAKE CREEK TRIBUTARY NO. 5 39.0
END DESCRIPTION:
XS GIS Cut Line= 3
      3745117.85     10135311.07      3744861.05     10135207.41
       3744517.9     10135161.08
#Sta/Elev= 30
  4720.4  299.55  4795.9   297.2  4882.2  295.82  4920.3  294.31  4957.6  293.88
  4968.4  294.47    4974   293.9    4990  289.31  4994.6  285.71  5001.5  286.21
  5006.5   289.2  5011.5  288.05  5020.7  292.07  5030.8  292.96  5061.1  292.56
  5079.2  293.36  5091.4  292.87  5141.8  293.87  5192.3   295.2  5229.6   297.7
  5234.6  296.81  5242.7  297.22    5273  299.58  5293.2  304.87  5302.3  306.66
  5307.3  303.02  5313.4  305.61  5323.5  307.27  5333.6  307.74  5343.6  307.21
#Mann= 3 , 0 , 0
  4720.4     .11       0    4990     .06       0  5006.5     .11       0
Bank Sta=4990,5006.5
XS Rating Curve= 0 ,0
Exp/Cntr=0.3,0.1

Type RM Length L Ch R = 1 ,19652   ,620,620,620
BEGIN DESCRIPTION:
LAKE CREEK TRIBUTARY NO. 5 38.0
END DESCRIPTION:
XS GIS Cut Line= 3
      3745417.82     10135061.05      3744969.13     10134694.39
      3744616.28     10134734.76
#Sta/Elev= 30
  4409.8  300.43    4460  299.51  4579.9  295.19  4686.9  292.36  4736.4  289.82
  4771.6  288.54  4793.8  288.51    4829     287  4872.1  287.05  4900.5  286.49
  4913.7  285.34  4950.3   286.3  4971.2  285.59    4978  284.81  4985.5  282.77
  4987.9     281  4992.4     281  4999.8  278.49  5002.8  278.41  5003.1  277.91
  5006.6  277.91  5006.8  278.41  5020.7  280.08  5023.6281.0045  5030.8   283.3
  5040.9  285.51  5101.3  286.45  5131.4  284.27  5151.6  286.08  5344.4  293.77
#Mann= 3 , 0 , 0
  4409.8     .11       0  4992.4     .06       0  5023.6     .11       0
Bank Sta=4992.4,5023.6
XS Rating Curve= 0 ,0
Exp/Cntr=0.3,0.1

Type RM Length L Ch R = 1 ,19032   ,486,486,486
BEGIN DESCRIPTION:
LAKE CREEK TRIBUTARY NO. 5 37.0
END DESCRIPTION:
XS GIS Cut Line= 3
      3745442.34     10134634.53      3745166.26     10134295.91
      3744781.85     10134244.03
#Sta/Elev= 30
  4563.1  291.64  4619.2  289.59  4683.1  286.02  4825.2   281.9  4889.1  280.74
    4910  277.78  4916.4  275.82  4924.3  275.21  4930.8  272.95  4938.7  273.43
  4945.1  272.15  4988.2  271.62  4992.7  271.07  4992.9  270.57  4999.9  271.19
  5028.7  271.73  5038.8  272.53  5068.8  277.13  5073.8  276.02  5079.1  277.61
  5089.2  279.26  5109.4   281.1  5129.6   280.3  5139.7  280.28  5146.5  280.96
  5151.6  280.62    5180  283.67  5219.2  284.59    5297  289.41  5387.9  292.87
#Mann= 3 , 0 , 0
  4563.1     .11       0  4988.2     .06       0  5028.7     .11       0
Bank Sta=4988.2,5028.7
XS Rating Curve= 0 ,0
Exp/Cntr=0.3,0.1

Type RM Length L Ch R = 1 ,18546   ,815,815,815
BEGIN DESCRIPTION:
LAKE CREEK TRIBUTARY NO. 5 36.0
END DESCRIPTION:
XS GIS Cut Line= 4
      3745551.72     10134587.63      3745548.74     10134257.34
      3745330.05     10133883.28      3744827.73     10133967.87
#Sta/Elev= 30
  4236.4  290.16    4463  283.28  4573.3  281.58  4653.4  279.64  4674.9  279.68
  4878.3  276.19  4899.7  275.42  4921.5  275.54  4944.6  274.53  4952.6  273.66
  4958.4  271.93  4974.1  271.11  4979.9  269.59  5003.7  268.81  5010.1  267.95
  5010.3  267.45  5013.8  267.45  5014.1  267.95  5017.1  268.42  5042.8  271.59
  5063.1  274.46  5083.4  276.14  5138.2  276.98  5154.3  277.88    5205  278.39
  5319.8  281.73  5357.2   283.6  5375.3  286.26  5387.6  287.15  5509.4  292.55
#Mann= 3 , 0 , 0
  4236.4     .11       0  4974.1     .06       0  5042.8     .11       0
Bank Sta=4974.1,5042.8
XS Rating Curve= 0 ,0
Exp/Cntr=0.3,0.1

Type RM Length L Ch R = 1 ,17731   ,333,333,333
BEGIN DESCRIPTION:
LAKE CREEK TRIBUTARY NO. 5 35.0
END DESCRIPTION:
XS GIS Cut Line= 3
      3745749.63     10132999.11      3745213.18     10133207.44
      3744619.77     10133816.47
#Sta/Elev= 30
  4426.4  288.02  4460.5  286.67  4469.5  285.67  4474.9  286.15  4499.5  283.74
  4621.4  276.48  4728.7  273.43  4747.1  273.89  4802.5  272.15  4825.2  271.68
  4831.5  270.91  4834.5  269.37  4836.8  268.45  4866.1  267.34  4866.4  266.84
  4878.9  268.27  4891.3  268.46  5057.7  267.59  5064.7  269.68    5086  270.48
  5106.7  270.34  5156.8  270.73  5425.5  276.46  5545.7  282.67  5637.5  289.96
  5651.7  290.39  5658.8  289.85  5687.1     291  5743.7  291.61  5852.2  291.59
#Mann= 5 ,-1 , 0
  4426.4     .17       0  4802.5     .11       0  4834.5     .09       0
  5064.7     .15       0  5106.7     .11       0
Bank Sta=4834.5,5064.7
XS Rating Curve= 0 ,0
Exp/Cntr=0.3,0.1

Type RM Length L Ch R = 1 ,17398   ,101,101,101
BEGIN DESCRIPTION:
LAKE CREEK TRIBUTARY NO. 5 34.0
END DESCRIPTION:
XS GIS Cut Line= 3
       3745812.1     10132910.57      3745051.72     10132926.19
      3744228.84     10133144.94
#Sta/Elev= 30
  4240.7     291    4335  287.19    4375  285.13    4395  283.17    4455   280.7
  4504.2  277.09  4546.7  275.79    4635  272.89 4766.44  270.42  4775.1  268.11
  4785.1  267.73  5005.8  266.87  5013.8   266.2  5035.4  267.09  5139.8  267.61
  5170.8  266.96  5284.6  267.07    5295  267.56  5311.3  269.98  5377.7  270.64
  5386.5  270.11  5391.6   268.2  5398.4   267.7  5419.1  268.69  5426.6  270.65
  5439.8   271.9  5622.2  275.65  5662.4  277.41    5802  280.27  5852.7   282.4
#Mann= 4 ,-1 , 0
  4240.7     .17       0  4546.7     .11       0 4766.44     .06       0
  5311.3     .11       0
Bank Sta=4766.44,5311.3
XS Rating Curve= 0 ,0
Exp/Cntr=0.3,0.1

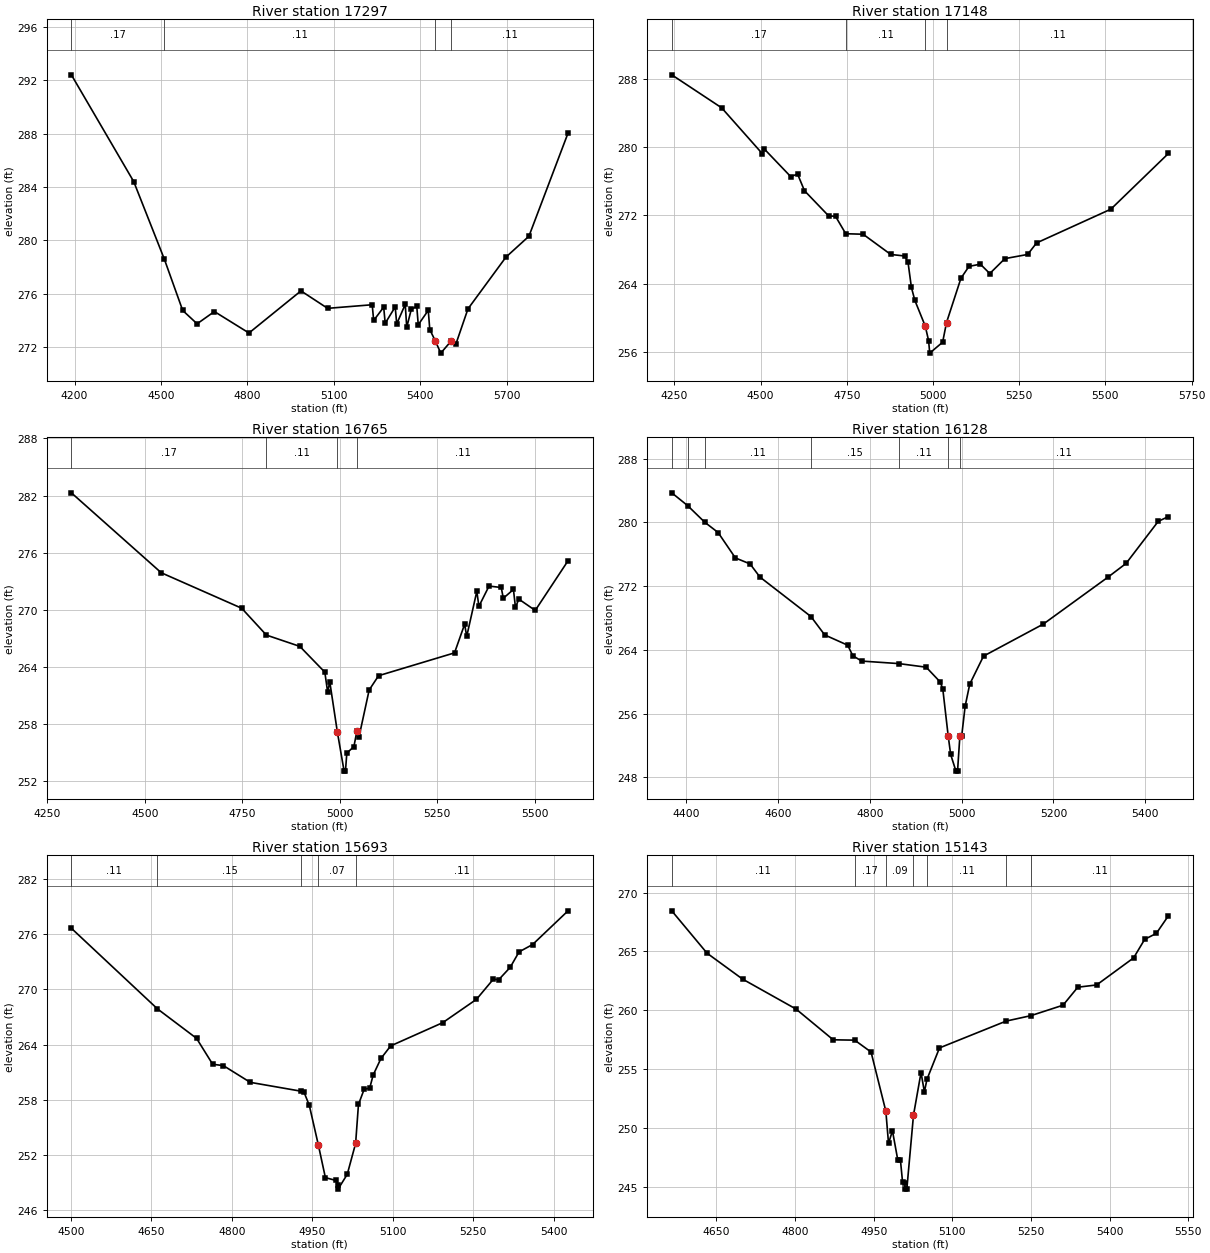
Type RM Length L Ch R = 1 ,17297   ,149,149,149
BEGIN DESCRIPTION:
Mapping XS 7a1c61e6
END DESCRIPTION:
XS GIS Cut Line= 4
      3745864.24     10132837.65      3745379.84     10132822.03
      3745082.97     10132816.82      3744172.22     10133061.42
#Sta/Elev= 30
    4189  292.42  4405.5  284.41    4512  278.58  4575.6  274.74  4625.6  273.74
  4685.6  274.66  4805.7  273.05  4986.2  276.21  5078.8   274.9  5233.6  275.17
  5238.7  273.99  5273.5  274.99  5278.7  273.78  5313.5  275.01  5318.7  273.73
  5348.3   275.2  5353.5  273.48  5369.3  274.82  5388.3  275.06  5393.5  273.67
  5428.3  274.75  5433.5  273.31  5452.2  272.48  5471.7  271.54  5508.3  272.46
  5524.7  272.25  5566.1  274.86  5697.9  278.74  5777.8  280.31  5913.6  288.05
#Mann= 4 ,-1 , 0
    4189     .17       0    4512     .11       0  5452.2     .06       0
  5508.3     .11       0
Bank Sta=5452.2,5508.3
XS Rating Curve= 0 ,0
Exp/Cntr=0.3,0.1

Type RM Length L Ch R = 1 ,17148   ,383,383,383
BEGIN DESCRIPTION:
LAKE CREEK TRIBUTARY NO. 5 33.0
END DESCRIPTION:
XS GIS Cut Line= 3
      3745822.55     10132660.57      3745067.34     10132676.19
      3744411.97     10132873.85
#Sta/Elev= 30
  4242.7  288.47  4387.4   284.6  4505.6  279.21  4510.6  279.79  4587.5  276.54
  4607.5  276.83  4627.5  274.88  4697.5  271.93  4717.5  271.88  4747.1  269.84
  4797.5  269.78  4877.5  267.41  4917.5  267.23  4927.5  266.54  4937.5  263.54
  4947.5  262.02  4977.6  259.01  4987.3  257.31  4990.6  255.84    5028  257.12
  5039.3  259.43  5081.1  264.62  5104.4  266.01  5137.4  266.27  5164.7  265.17
  5208.5  266.92  5274.5  267.41  5300.4  268.76  5515.8  272.72  5682.6  279.25
#Mann= 4 ,-1 , 0
  4242.7     .17       0  4747.1     .11       0  4977.6     .06       0
  5039.3     .11       0
Bank Sta=4977.6,5039.3
XS Rating Curve= 0 ,0
Exp/Cntr=0.3,0.1

Type RM Length L Ch R = 1 ,16765   ,637,637,637
BEGIN DESCRIPTION:
LAKE CREEK TRIBUTARY NO. 5 32.0
END DESCRIPTION:
XS GIS Cut Line= 3
      3745666.29     10132598.06      3745015.26     10132353.28
      3744468.34     10132540.79
#Sta/Elev= 30
  4311.7  282.29  4542.2  273.89  4748.5  270.16  4811.8  267.34  4897.6  266.15
  4961.7  263.44    4969  261.32  4974.3  262.45  4993.8  257.16  5011.1  253.04
  5014.6  253.04  5018.1  254.94  5036.2  255.61  5044.1  257.28  5049.4  256.65
  5075.4  261.57  5099.6  263.07  5294.3  265.47  5320.3  268.49  5325.5  267.19
  5351.5  271.94  5356.8  270.36  5382.8  272.49  5414.1  272.34  5419.4  271.21
  5445.4  272.13  5450.6  270.24  5459.1  271.12  5501.3  269.93  5585.4  275.15
#Mann= 4 ,-1 , 0
  4311.7     .17       0  4811.8     .11       0  4993.8     .06       0
  5044.1     .11       0
Bank Sta=4993.8,5044.1
XS Rating Curve= 0 ,0
Exp/Cntr=0.3,0.1

Type RM Length L Ch R = 1 ,16128   ,435,435,435
BEGIN DESCRIPTION:
LAKE CREEK TRIBUTARY NO. 5 31.0
END DESCRIPTION:
XS GIS Cut Line= 3
      3745317.86     10131761.07      3744725.29     10131980.78
       3744275.7     10132009.53
#Sta/Elev= 30
    4368  283.71  4402.5  282.11  4439.9  280.02    4469  278.73  4506.7  275.54
  4538.7  274.79  4560.2  273.14  4671.3  268.19  4701.4  265.88  4751.5  264.59
  4762.6  263.27  4781.9   262.6  4863.4  262.28  4922.6  261.83  4953.5  259.95
  4958.8  259.07  4970.4253.2564  4975.9  250.88  4987.4  248.79  4990.9  248.79
    4996  253.23    5000  253.23  5007.4  256.92  5017.5  259.71  5047.5  263.22
  5177.8  267.24  5318.1   273.1  5358.2  274.85  5428.3  280.13  5450.5  280.73
#Mann= 7 ,-1 , 0
    4368     .11       0  4402.5     .17       0  4439.9     .11       0
  4671.3     .15       0  4863.4     .11       0  4970.4     .06       0
    4996     .11       0
Bank Sta=4970.4,4996
XS Rating Curve= 0 ,0
Exp/Cntr=0.3,0.1

Type RM Length L Ch R = 1 ,15693   ,550,550,550
BEGIN DESCRIPTION:
LAKE CREEK TRIBUTARY NO. 5 30.0
END DESCRIPTION:
XS GIS Cut Line= 3
      3745161.07     10131582.44      3744662.29     10131587.05
      3744254.81     10131712.66
#Sta/Elev= 30
  4501.2  276.66  4661.6  267.88  4734.4  264.67  4764.4  261.85  4784.4   261.7
  4834.4  259.88  4929.6  258.91  4934.4  258.83  4944.4  257.38 4961.13253.0966
  4974.4   249.5  4994.4  249.19  4997.7  248.75    4998  248.25  5015.1  249.86
  5030.7  253.23    5036  257.47  5046.5  259.11    5057  259.26  5063.4  260.68
  5077.9  262.48    5096  263.85    5193  266.38  5255.8  268.92  5287.2  271.11
  5297.3  271.06  5318.6   272.4  5335.2  274.09  5360.4  274.89  5426.4  278.56
#Mann= 5 ,-1 , 0
  4501.2     .11       0  4661.6     .15       0  4929.6     .11       0
 4961.13     .07       0  5030.7     .11       0
Bank Sta=4961.13,5030.7
XS Rating Curve= 0 ,0
Exp/Cntr=0.3,0.1

Type RM Length L Ch R = 1 ,15143   ,393,393,393
BEGIN DESCRIPTION:
LAKE CREEK TRIBUTARY NO. 5 29.0
END DESCRIPTION:
XS GIS Cut Line= 3
      3745010.03     10130962.66      3744582.97     10131051.19
      3744182.38     10131368.54
#Sta/Elev= 30
  4564.9  268.45  4632.2  264.85  4699.9  262.65    4802   260.1  4872.8  257.49
  4913.8  257.46    4945  256.45  4973.2  251.42  4978.3  248.69  4985.8  249.76
    4996  247.27    5001  247.27    5005  245.43  5009.4   245.3  5009.7   244.8
  5013.2   244.8  5025.9  251.08  5040.3  254.71  5046.7  253.07  5051.6  254.13
  5075.5   256.8  5202.6  259.08  5249.7  259.54  5311.1  260.43  5339.3  261.96
  5375.2  262.15  5445.7  264.45  5466.9  266.03    5489  266.53  5512.1  268.03
#Mann= 7 ,-1 , 0
  4564.9     .11       0  4913.8     .17       0  4973.2     .09       0
  5025.9     .17       0  5051.6     .11       0  5202.6     .15       0
  5249.7     .11       0
Bank Sta=4973.2,5025.9
XS Rating Curve= 0 ,0
Exp/Cntr=0.3,0.1

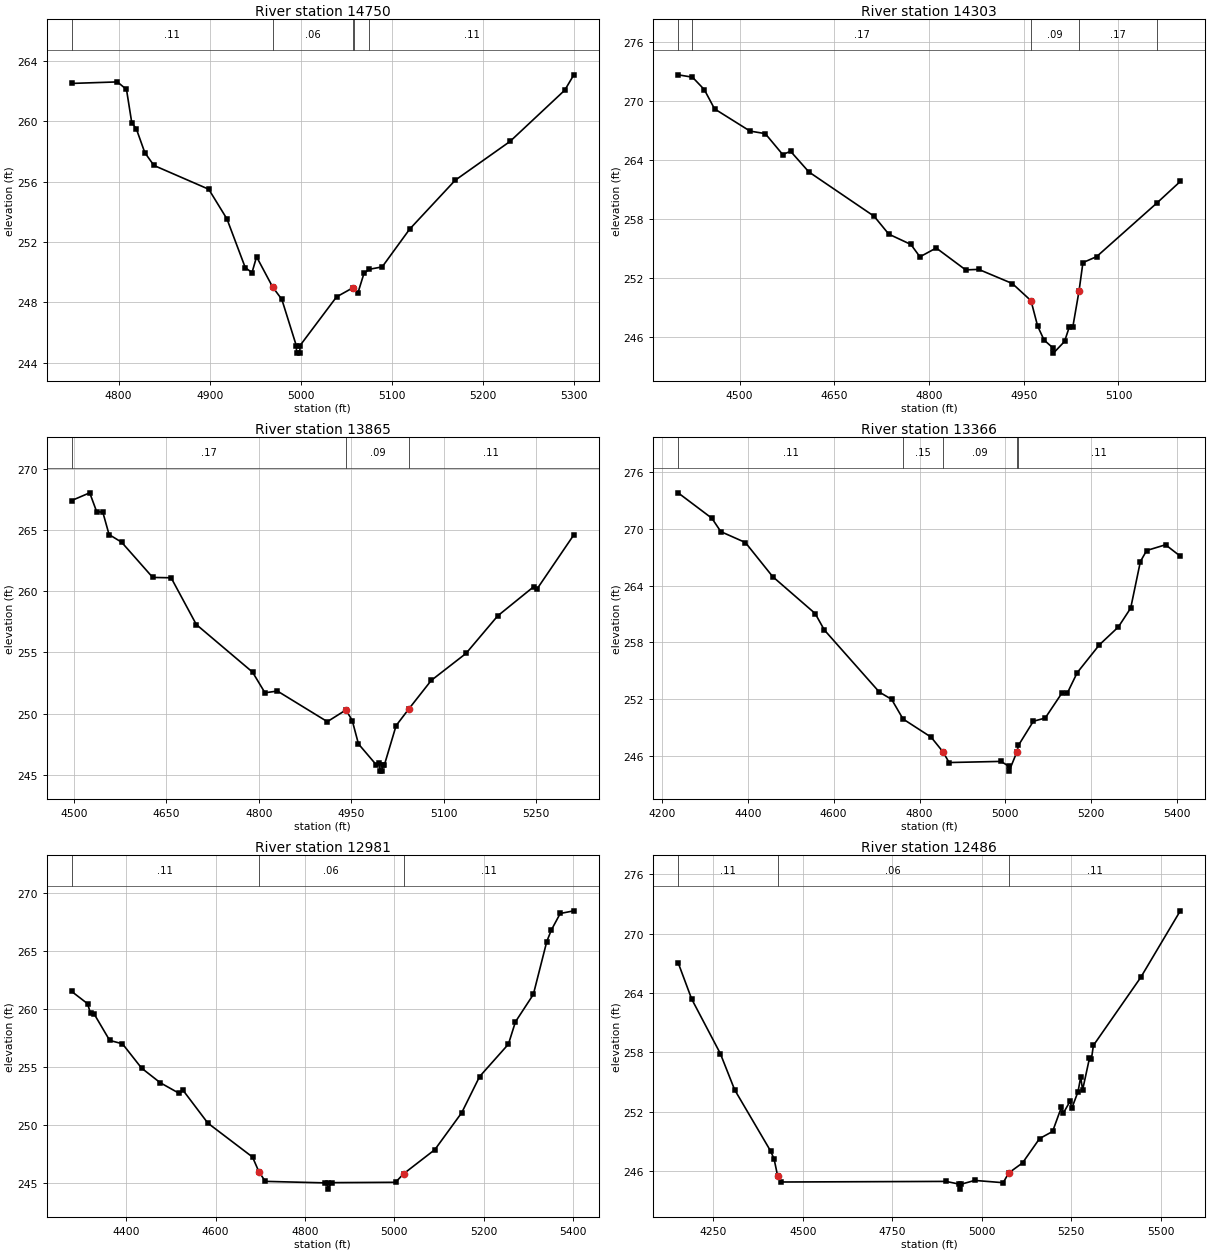
Type RM Length L Ch R = 1 ,14750   ,447,447,447
BEGIN DESCRIPTION:
LAKE CREEK TRIBUTARY NO. 5 28.0
END DESCRIPTION:
XS GIS Cut Line= 3
      3744717.89     10130661.07        3744467.      10130679.9
      3744167.89     10130661.07
#Sta/Elev= 30
  4748.4  262.52  4798.6  262.62  4808.6  262.12  4814.4  259.91  4819.4  259.51
  4828.7  257.93  4838.7  257.08  4898.9   255.5  4918.9  253.53    4939   250.3
  4946.4  249.97  4951.4  251.02  4969.1  249.01  4979.1   248.2    4995  245.13
  4995.3  244.63  4998.9  244.63  4999.1  245.13  5039.2  248.36  5057.6  248.98
  5058.7   248.9  5062.6  248.61  5069.3  249.92  5075.1  250.19  5089.3  250.35
  5119.4  252.85  5169.5   256.1  5229.6  258.67  5289.7  262.07  5299.7  263.09
#Mann= 5 ,-1 , 0
  4748.4     .11       0  4969.1     .06       0  5057.6     .11       0
  5058.7     .17       0  5075.1     .11       0
Bank Sta=4969.1,5057.6
XS Rating Curve= 0 ,0
Exp/Cntr=0.3,0.1

Type RM Length L Ch R = 1 ,14303   ,438,438,438
BEGIN DESCRIPTION:
LAKE CREEK TRIBUTARY NO. 5 27.0
END DESCRIPTION:
XS GIS Cut Line= 3
      3744867.86     10130161.07      3744290.61     10130314.52
      3744117.86     10130411.07
#Sta/Elev= 30
  4402.7  272.66  4425.4  272.42  4444.1  271.16  4460.4  269.19  4516.5  266.93
  4540.7  266.67  4568.3  264.54  4580.8  264.87  4609.7  262.77  4713.1  258.25
  4736.3  256.43  4771.3  255.38  4785.6  254.12  4811.4  255.02    4858  252.79
  4878.7  252.84  4931.9   251.4  4961.5  249.65    4972  247.06  4982.2  245.64
  4996.8  244.81    4997  244.31  5014.6   245.5    5022  246.95  5027.7  246.98
  5037.5  250.62  5043.7  253.53  5065.4  254.14  5160.6  259.59  5197.9   261.8
#Mann= 5 ,-1 , 0
  4402.7     .11       0  4425.4     .17       0  4961.5     .09       0
  5037.5     .17       0  5160.6     .11       0
Bank Sta=4961.5,5037.5
XS Rating Curve= 0 ,0
Exp/Cntr=0.3,0.1

Type RM Length L Ch R = 1 ,13865   ,499,499,499
BEGIN DESCRIPTION:
LAKE CREEK TRIBUTARY NO. 5 26.0
END DESCRIPTION:
XS GIS Cut Line= 3
      3744767.88     10129961.08      3744269.93     10129885.15
      3743967.88     10129811.08
#Sta/Elev= 30
  4496.3  267.41  4525.6  268.04  4536.8  266.51  4546.9  266.45    4557  264.63
  4577.3  264.01  4627.8  261.13  4657.7   261.1  4698.6  257.28  4789.7   253.4
  4809.9  251.71  4830.1  251.85  4911.1  249.35  4941.4  250.31  4951.5  249.44
  4961.6  247.53  4990.4  245.83  4995.5     246  4996.7  245.31  5000.4  245.31
  5000.6  245.81  5003.6  245.81  5022.7  249.03  5043.3  250.39  5079.7  252.72
    5136  254.92  5187.5  257.99  5246.1  260.38  5251.2  260.18    5311  264.61
#Mann= 3 , 0 , 0
  4496.3     .17       0  4941.4     .09       0  5043.3     .11       0
Bank Sta=4941.4,5043.3
XS Rating Curve= 0 ,0
Exp/Cntr=0.3,0.1

Type RM Length L Ch R = 1 ,13366   ,385,385,385
BEGIN DESCRIPTION:
LAKE CREEK TRIBUTARY NO. 5 25.0
END DESCRIPTION:
XS GIS Cut Line= 3
      3744967.87     10129911.09      3744385.66     10129419.02
      3744025.68     10129228.28
#Sta/Elev= 30
  4237.7  273.84  4316.3  271.15  4337.2  269.73  4394.3  268.58  4458.1  264.96
  4556.9  261.06  4578.2  259.32  4706.4  252.74    4735  251.97  4761.6  249.89
  4826.9  247.97  4854.7  246.41  4868.9  245.28  4989.8   245.4  5008.3  244.87
  5008.6  244.37  5026.7  246.39  5030.4   247.1  5065.1  249.65  5092.7  249.99
  5131.1   252.6  5144.6  252.67  5167.3   254.8    5219  257.75    5263  259.63
  5291.8  261.63  5314.4  266.56    5329  267.73    5373  268.34  5407.4  267.13
#Mann= 5 ,-1 , 0
  4237.7     .11       0  4761.6     .15       0  4854.7     .09       0
  5026.7     .15       0  5030.4     .11       0
Bank Sta=4854.7,5026.7
XS Rating Curve= 0 ,0
Exp/Cntr=0.3,0.1

Type RM Length L Ch R = 1 ,12981   ,495,495,495
BEGIN DESCRIPTION:
LAKE CREEK TRIBUTARY NO. 5 24.0
END DESCRIPTION:
XS GIS Cut Line= 3
      3745017.82     10129561.04      3744468.39     10129092.86
      3744067.37     10129113.69
#Sta/Elev= 30
    4278  261.52  4313.6  260.46  4320.2  259.62  4327.9   259.6  4363.1  257.29
  4391.6     257  4434.4   254.9  4476.1  253.64    4519  252.71  4526.7  253.01
  4582.7  250.15  4682.6  247.22  4696.9  245.95  4711.2  245.12  4845.1  244.99
  4850.6  244.95  4850.9  244.45  4859.4  245.01  5002.6  245.04  5020.4  245.77
  5090.5  247.86  5150.6  251.05  5190.6  254.17  5255.1  256.97  5270.7  258.89
  5310.8  261.26  5340.8  265.82  5350.9  266.81  5370.9  268.25  5401.4  268.48
#Mann= 3 , 0 , 0
    4278     .11       0  4696.9     .06       0  5020.4     .11       0
Bank Sta=4696.9,5020.4
XS Rating Curve= 0 ,0
Exp/Cntr=0.3,0.1

Type RM Length L Ch R = 1 ,12486   ,210,210,210
BEGIN DESCRIPTION:
LAKE CREEK TRIBUTARY NO. 5 23.0
END DESCRIPTION:
XS GIS Cut Line= 3
      3745275.69     10128598.07      3744426.72     10128634.53
      3743911.97     10128837.31
#Sta/Elev= 30
  4151.7  267.08  4189.6   263.4  4269.6  257.89  4309.7  254.22  4409.8  248.05
  4419.8  247.23  4429.8   245.5  4439.8   244.9  4900.2  244.96  4937.8  244.68
  4938.2  244.18  4942.7  244.68  4980.3  245.06  5059.8  244.83  5075.5  245.82
  5113.9  246.83  5161.5  249.29  5197.9  250.01  5222.3  252.44  5227.6  251.85
  5246.6  253.05    5252   252.4  5268.9  254.03  5276.4   255.5  5281.8  254.22
  5300.8   257.4  5306.2  257.29  5311.9  258.71  5444.2  265.59  5554.7  272.32
#Mann= 3 , 0 , 0
  4151.7     .11       0  4429.8     .06       0  5075.5     .11       0
Bank Sta=4429.8,5075.5
XS Rating Curve= 0 ,0
Exp/Cntr=0.3,0.1

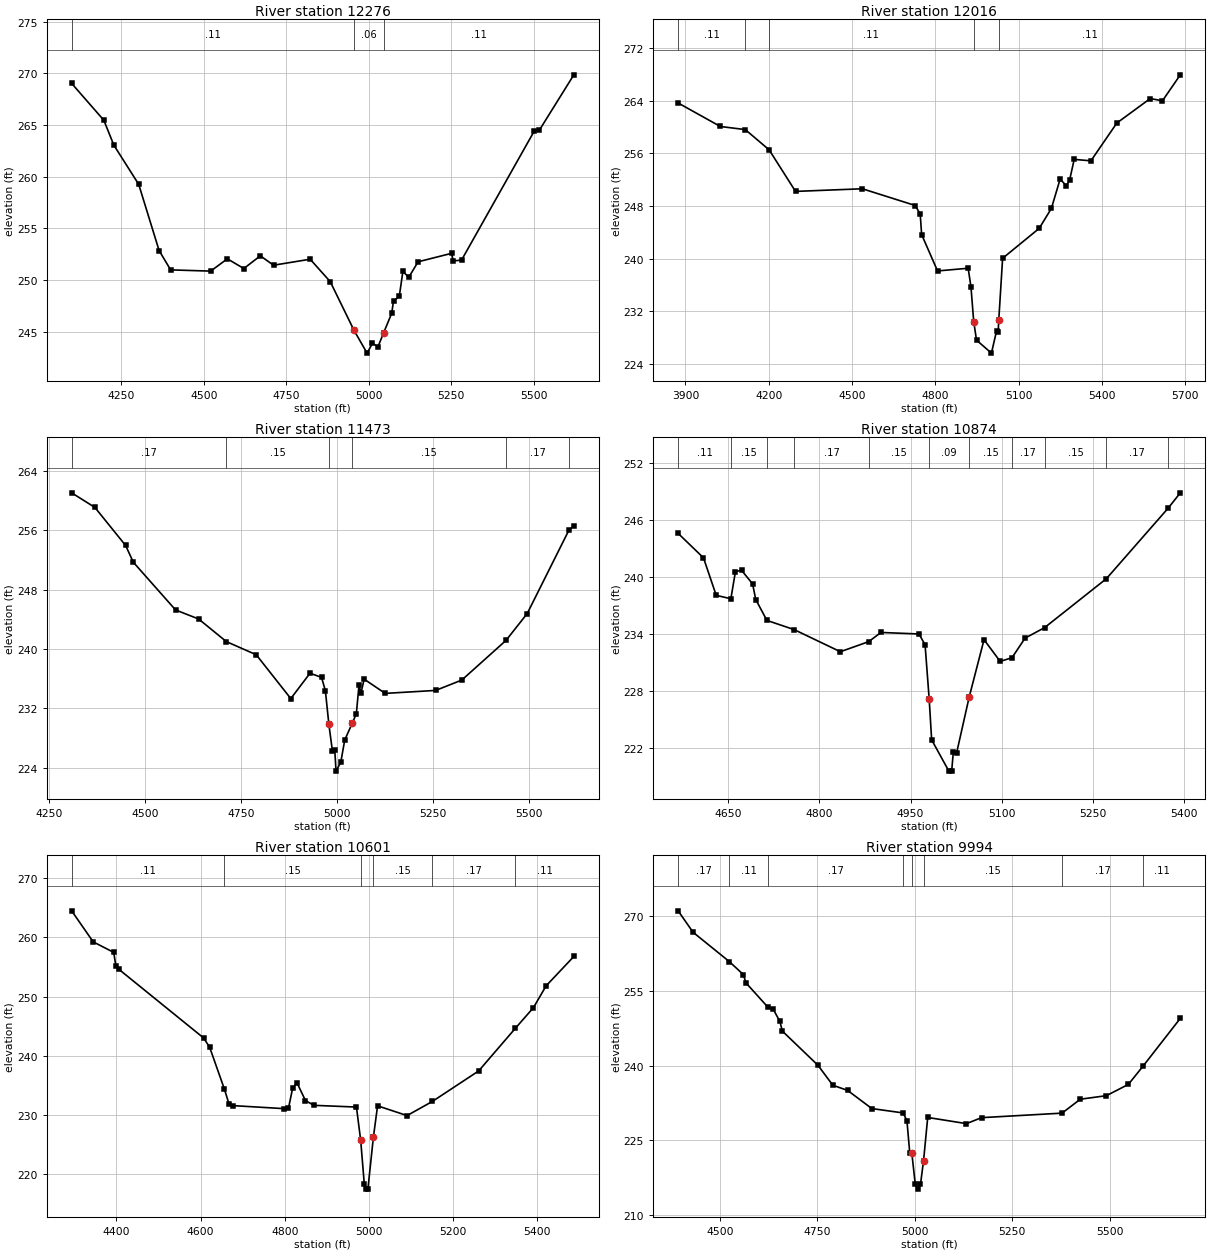
Type RM Length L Ch R = 1 ,12276   ,260,260,260
BEGIN DESCRIPTION:
Mapping XS 720cab44
END DESCRIPTION:
XS GIS Cut Line= 6
      3745364.23     10128478.28      3744911.09     10128405.36
      3744718.39     10128410.57      3744572.55     10128436.61
      3744421.51     10128478.28      3743903.27     10128706.23
#Sta/Elev= 30
  4099.2  269.02  4196.8  265.46  4227.2  263.05  4302.6  259.26  4364.4  252.86
  4399.4  250.99  4520.9  250.87  4571.4  252.06  4621.4  251.12  4671.5  252.35
  4711.5  251.44  4822.6  252.02  4883.5  249.85  4955.8  245.13  4995.2  242.94
  5011.4  243.88  5028.4  243.57  5045.7  244.92  5069.9   246.8  5075.4  247.98
  5092.8  248.42  5103.9  250.86  5121.4  250.26  5149.9  251.77  5251.4  252.59
  5256.7  251.85  5281.8  251.94  5502.7  264.44  5517.8   264.5  5622.3  269.85
#Mann= 3 , 0 , 0
  4099.2     .11       0  4955.8     .06       0  5045.7     .11       0
Bank Sta=4955.8,5045.7
XS Rating Curve= 0 ,0
Exp/Cntr=0.3,0.1

Type RM Length L Ch R = 1 ,12016   ,543,543,543
BEGIN DESCRIPTION:
LAKE CREEK TRIBUTARY NO. 5 22.0
END DESCRIPTION:
XS GIS Cut Line= 3
      3745499.59     10128311.61      3744390.26     10128228.28
      3743775.98     10128556.24
#Sta/Elev= 30
  3873.6  263.63  4025.8  260.06  4115.5  259.59  4201.4  256.52  4296.5  250.21
  4537.2  250.61  4727.7  248.07  4745.6  246.77  4750.7  243.66    4808  238.14
  4918.3  238.55  4928.3  235.76  4938.3  230.46  4948.4  227.64  5002.1  225.67
  5020.5  229.02  5026.2  228.83 5028.47230.6489  5042.4  240.06  5174.1   244.6
  5218.1  247.63  5249.5  252.08  5272.2  251.05  5283.9  251.97  5300.2  255.07
  5360.4  254.85  5453.9  260.59  5574.2   264.3  5618.1  263.96  5682.4   267.9
#Mann= 5 ,-1 , 0
  3873.6     .11       0  4115.5     .17       0  4201.4     .11       0
  4938.3     .07       0 5028.47     .11       0
Bank Sta=4938.3,5028.47
XS Rating Curve= 0 ,0
Exp/Cntr=0.3,0.1

Type RM Length L Ch R = 1 ,11473   ,599,599,599
BEGIN DESCRIPTION:
LAKE CREEK TRIBUTARY NO. 5 21.0
END DESCRIPTION:
XS GIS Cut Line= 3
      3745218.39     10127780.36      3744536.09      10127806.4
      3743917.89     10127711.08
#Sta/Elev= 30
  4309.4  261.05    4370  259.08    4450  253.95  4470.1  251.69  4580.1  245.26
  4640.2  244.04  4712.5  240.99  4790.3  239.22  4880.3  233.31  4930.4  236.73
  4960.4  236.17  4970.4  234.38  4979.5  229.84  4988.8  226.22  4994.9  226.35
  4998.2  223.53  5010.6  224.74  5020.8  227.72    5041  230.06  5051.1  231.28
  5058.1  235.19  5063.1  234.05  5071.4  235.93  5126.3  234.01  5257.7  234.41
  5325.9  235.81  5441.1  241.16  5496.3  244.78  5604.7     256  5617.7  256.64
#Mann= 6 ,-1 , 0
  4309.4     .17       0  4712.5     .15       0  4979.5     .09       0
    5041     .15       0  5441.1     .17       0  5604.7     .11       0
Bank Sta=4979.5,5041
XS Rating Curve= 0 ,0
Exp/Cntr=0.3,0.1

Type RM Length L Ch R = 1 ,10874   ,273,273,273
BEGIN DESCRIPTION:
LAKE CREEK TRIBUTARY NO. 5 20.0
END DESCRIPTION:
XS GIS Cut Line= 3
       3744817.9     10127311.06      3744403.19     10127432.06
      3744017.81     10127511.08
#Sta/Elev= 30
    4568  244.61  4609.7  242.03  4630.6  238.08  4654.7  237.72  4662.2  240.58
  4672.2  240.72  4690.4  239.29  4695.6  237.64  4713.9  235.44  4758.7  234.47
  4834.7  232.14  4881.2   233.2  4901.4  234.17  4963.9  234.01  4973.9  232.87
 4980.64227.1737  4984.7  222.86    5013  219.56  5017.6  219.56  5020.4   221.6
  5025.9  221.52  5046.3  227.34  5070.8  233.41  5097.3  231.12  5116.8  231.51
  5138.2  233.57  5170.4  234.68    5272  239.84  5373.5  247.27  5393.4  248.88
#Mann= 11 ,-1 , 0
    4568     .11       0  4654.7     .15       0  4713.9     .11       0
  4758.7     .17       0  4881.2     .15       0 4980.64     .09       0
  5046.3     .15       0  5116.8     .17       0  5170.4     .15       0
    5272     .17       0  5373.5     .11       0
Bank Sta=4980.64,5046.3
XS Rating Curve= 0 ,0
Exp/Cntr=0.3,0.1

Type RM Length L Ch R = 1 ,10601   ,607,607,607
BEGIN DESCRIPTION:
LAKE CREEK TRIBUTARY NO. 5 19.0
END DESCRIPTION:
XS GIS Cut Line= 3
      3745098.61     10127269.95      3744405.89     10127176.19
      3743912.01      10127150.2
#Sta/Elev= 30
  4293.5   264.5  4344.7  259.26  4393.5  257.48  4398.6  255.16  4405.3  254.65
  4607.1  243.03  4621.4  241.48  4656.3  234.44  4667.6  231.87  4677.7   231.6
  4798.8  231.09  4808.9  231.18    4819  234.64  4829.1  235.46  4849.3  232.44
  4869.5  231.65  4970.4  231.36  4980.5  225.73    4989  218.39  4992.9   217.5
  4997.6   217.5  5010.6  226.23  5020.6  231.57  5090.7  229.92  5150.9  232.31
  5260.9  237.46  5348.1  244.66  5391.1  248.15  5421.2  251.83  5487.1  256.79
#Mann= 6 ,-1 , 0
  4293.5     .11       0  4656.3     .15       0  4980.5     .09       0
  5010.6     .15       0  5150.9     .17       0  5348.1     .11       0
Bank Sta=4980.5,5010.6
XS Rating Curve= 0 ,0
Exp/Cntr=0.3,0.1

Type RM Length L Ch R = 1 ,9994    ,574,574,574
BEGIN DESCRIPTION:
LAKE CREEK TRIBUTARY NO. 5 18.0
END DESCRIPTION:
XS GIS Cut Line= 3
      3745167.89     10126961.09      3744619.43     10126728.28
       3743967.9     10126961.06
#Sta/Elev= 30
  4393.4  271.14  4431.7  266.83  4524.6  260.94  4560.8  258.31  4567.3  256.66
  4623.7  251.76  4637.2  251.36  4654.2  248.92  4660.9  246.94  4751.9  240.09
  4790.1  236.07    4828  235.03  4890.1  231.38  4970.4   230.5  4980.1  228.94
  4987.4  222.41  4992.7  222.41  5001.5  216.13  5007.3  215.18  5014.9  216.15
  5022.8  220.93  5033.4  229.59  5132.8  228.35  5171.4  229.55  5377.9  230.46
  5424.7  233.26  5491.6  233.97  5547.9  236.24  5586.6  240.01  5681.1  249.52
#Mann= 8 ,-1 , 0
  4393.4     .17       0  4524.6     .11       0  4623.7     .17       0
  4970.4     .15       0  4992.7     .09       0  5022.8     .15       0
  5377.9     .17       0  5586.6     .11       0
Bank Sta=4992.7,5022.8
XS Rating Curve= 0 ,0
Exp/Cntr=0.3,0.1

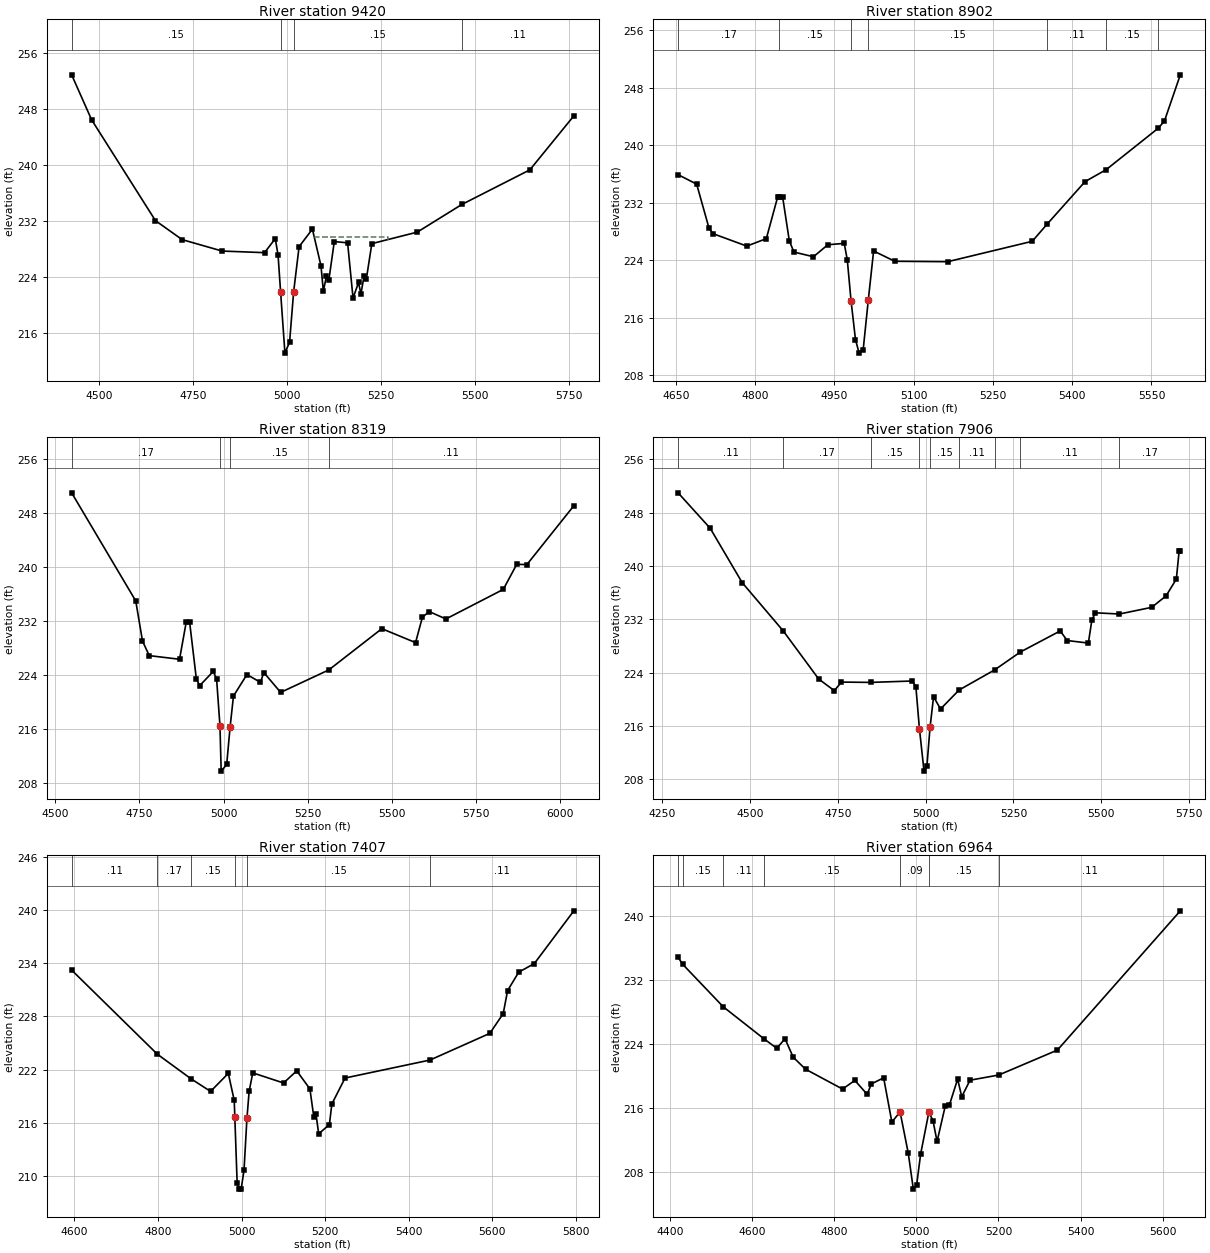
Type RM Length L Ch R = 1 ,9420    ,518,518,518
BEGIN DESCRIPTION:
LAKE CREEK TRIBUTARY NO. 5 17.0
END DESCRIPTION:
XS GIS Cut Line= 3
       3744770.5     10125868.88      3744338.18     10126249.11
      3743880.77     10126857.25
#Sta/Elev= 30
    4426  252.83  4479.2   246.4  4649.1     232  4720.2  229.29  4826.5  227.66
  4939.4  227.43  4967.9  229.43  4975.4  227.11  4982.1  221.86  4993.7  213.08
  5006.1  214.67  5016.8   221.8  5031.4  228.29  5066.8  230.79  5089.7  225.54
  5095.9  221.95  5104.2  224.03  5110.5  223.48  5125.1  229.02  5160.5  228.83
    5175  220.94  5189.6  223.17  5195.9  221.54  5204.2  224.04  5210.4  223.66
    5225  228.72  5345.8  230.36  5464.5  234.31  5645.7  239.26  5762.7  246.97
#Mann= 4 ,-1 , 0
    4426     .15       0  4982.1     .09       0  5016.8     .15       0
  5464.5     .11       0
#XS Ineff= 1 ,-1
 5069.81 5267.92  229.65
Permanent Ineff=
       F
Bank Sta=4982.1,5016.8
XS Rating Curve= 0 ,0
Exp/Cntr=0.3,0.1

Type RM Length L Ch R = 1 ,8902    ,583,583,583
BEGIN DESCRIPTION:
LAKE CREEK TRIBUTARY NO. 5 16.0
END DESCRIPTION:
XS GIS Cut Line= 3
      3744467.86     10125611.07      3744172.12      10125789.9
      3743567.89     10125811.07
#Sta/Elev= 30
  4654.4  235.89  4689.5  234.57  4712.8  228.46  4720.4  227.68  4784.4  225.95
  4821.3  226.99  4842.6  232.74  4845.9  232.73  4852.3  232.72  4864.8  226.68
  4873.6  225.12  4910.5  224.47  4937.7  226.14  4968.7  226.33  4974.5  224.04
  4981.6  218.34    4990  212.94  4996.9  211.06  5004.6  211.56  5014.3  218.49
  5024.3  225.27  5064.3  223.84  5164.4  223.78  5324.5  226.62    5352  228.96
  5424.5  234.93  5464.2  236.58    5563  242.36  5574.6  243.36  5604.6  249.78
#Mann= 7 ,-1 , 0
  4654.4     .17       0  4845.9     .15       0  4981.6     .09       0
  5014.3     .15       0    5352     .11       0  5464.2     .15       0
    5563     .11       0
Bank Sta=4981.6,5014.3
XS Rating Curve= 0 ,0
Exp/Cntr=0.3,0.1

Type RM Length L Ch R = 1 ,8319    ,413,413,413
BEGIN DESCRIPTION:
LAKE CREEK TRIBUTARY NO. 5 15.0
END DESCRIPTION:
XS GIS Cut Line= 3
      3744588.14     10125295.99      3744140.26     10125290.78
      3743098.57     10125238.69
#Sta/Elev= 30
  4549.1  251.04  4739.4  234.99  4759.4  229.04  4779.4  226.87  4869.4  226.33
  4889.4  231.89  4899.4  231.82  4919.4  223.36  4929.4  222.42  4969.4  224.52
  4979.4  223.42  4989.4  216.44    4993  209.72  5009.4  210.71  5019.4  216.22
  5029.5  220.87  5069.5  224.06  5109.6   222.9  5119.6  224.36  5169.6  221.41
  5312.7  224.75    5470  230.87  5570.1   228.8  5590.2  232.54  5610.2  233.42
  5660.2  232.31  5830.5   236.7  5870.5  240.43  5900.5  240.38    6040  249.12
#Mann= 4 ,-1 , 0
  4549.1     .17       0  4989.4     .09       0  5019.4     .15       0
  5312.7     .11       0
Bank Sta=4989.4,5019.4
XS Rating Curve= 0 ,0
Exp/Cntr=0.3,0.1

Type RM Length L Ch R = 1 ,7906    ,499,499,499
BEGIN DESCRIPTION:
LAKE CREEK TRIBUTARY NO. 5 14.0
END DESCRIPTION:
XS GIS Cut Line= 3
      3744718.34      10124999.1      3744020.43     10124905.93
      3743296.53     10124874.11
#Sta/Elev= 30
  4295.9  250.99  4387.2  245.67    4478  237.53    4595  230.27  4695.8  223.06
  4740.3  221.31  4760.5   222.6  4843.3  222.55  4962.2  222.76  4972.3   221.9
  4982.4  215.61  4995.5  209.24  5003.8  210.05  5012.6  215.81  5022.6  220.38
  5042.6  218.57  5095.3  221.41  5196.2  224.42  5269.9  227.12  5382.9  230.27
    5403  228.83    5463  228.45    5473  231.91    5483  232.99  5551.4  232.81
  5643.2  233.81  5684.1  235.53  5713.3  238.05  5721.4  242.33  5724.6  242.33
#Mann= 9 ,-1 , 0
  4295.9     .11       0    4595     .17       0  4843.3     .15       0
  4982.4     .09       0  5012.6     .15       0  5095.3     .11       0
  5196.2     .15       0  5269.9     .11       0  5551.4     .17       0
Bank Sta=4982.4,5012.6
XS Rating Curve= 0 ,0
Exp/Cntr=0.3,0.1

Type RM Length L Ch R = 1 ,7407    ,443,443,443
BEGIN DESCRIPTION:
LAKE CREEK TRIBUTARY NO. 5 13.0
END DESCRIPTION:
XS GIS Cut Line= 3
      3744567.86     10124811.08      3744283.48     10124520.61
      3743527.07      10124275.6
#Sta/Elev= 30
  4593.5  233.22  4798.5  223.73  4879.2  220.95  4925.9  219.53  4968.3  221.56
  4982.5  218.52 4983.95216.5871  4989.5  209.19  4993.4   208.5    4999   208.5
  5005.9  210.62  5012.9  216.49  5018.2  219.55  5026.9  221.62  5100.5  220.48
  5132.1  221.85  5163.6  219.81  5172.9  216.64  5178.2  216.95  5184.6  214.74
  5210.2  215.79  5216.1  218.11  5247.7  221.04    5451  223.07  5594.1  226.08
  5626.1  228.31  5636.6  230.91  5663.3  232.99  5700.6  233.96  5795.1  239.91
#Mann= 6 ,-1 , 0
  4593.5     .11       0  4798.5     .17       0  4879.2     .15       0
 4983.95     .09       0  5012.9     .15       0    5451     .11       0
Bank Sta=4983.95,5012.9
XS Rating Curve= 0 ,0
Exp/Cntr=0.3,0.1

Type RM Length L Ch R = 1 ,6964    ,606,606,606
BEGIN DESCRIPTION:
LAKE CREEK TRIBUTARY NO. 5 12.0
END DESCRIPTION:
XS GIS Cut Line= 3
      3744767.88     10124211.07      3744192.34     10124186.61
      3743546.53     10124223.07
#Sta/Elev= 30
  4420.1  234.85  4431.5  233.97  4530.1  228.65  4628.7  224.66  4660.3  223.45
  4680.4  224.65  4700.4  222.33  4730.4  220.83  4820.5  218.34  4850.5  219.42
  4880.5  217.68  4890.6  218.98  4920.6  219.75  4940.6   214.2  4960.6  215.47
  4980.6  210.28  4992.9  205.79  5000.9  206.29  5010.7   210.2  5030.7  215.43
  5040.7  214.38  5050.7  211.77  5070.8  216.26  5080.8  216.35  5100.8  219.59
  5110.8  217.37  5130.9  219.45  5200.9   220.1  5343.8  223.23    5643  240.69
#Mann= 7 ,-1 , 0
  4420.1     .11       0  4431.5     .15       0  4530.1     .11       0
  4628.7     .15       0  4960.6     .09       0  5030.7     .15       0
  5200.9     .11       0
Bank Sta=4960.6,5030.7
XS Rating Curve= 0 ,0
Exp/Cntr=0.3,0.1