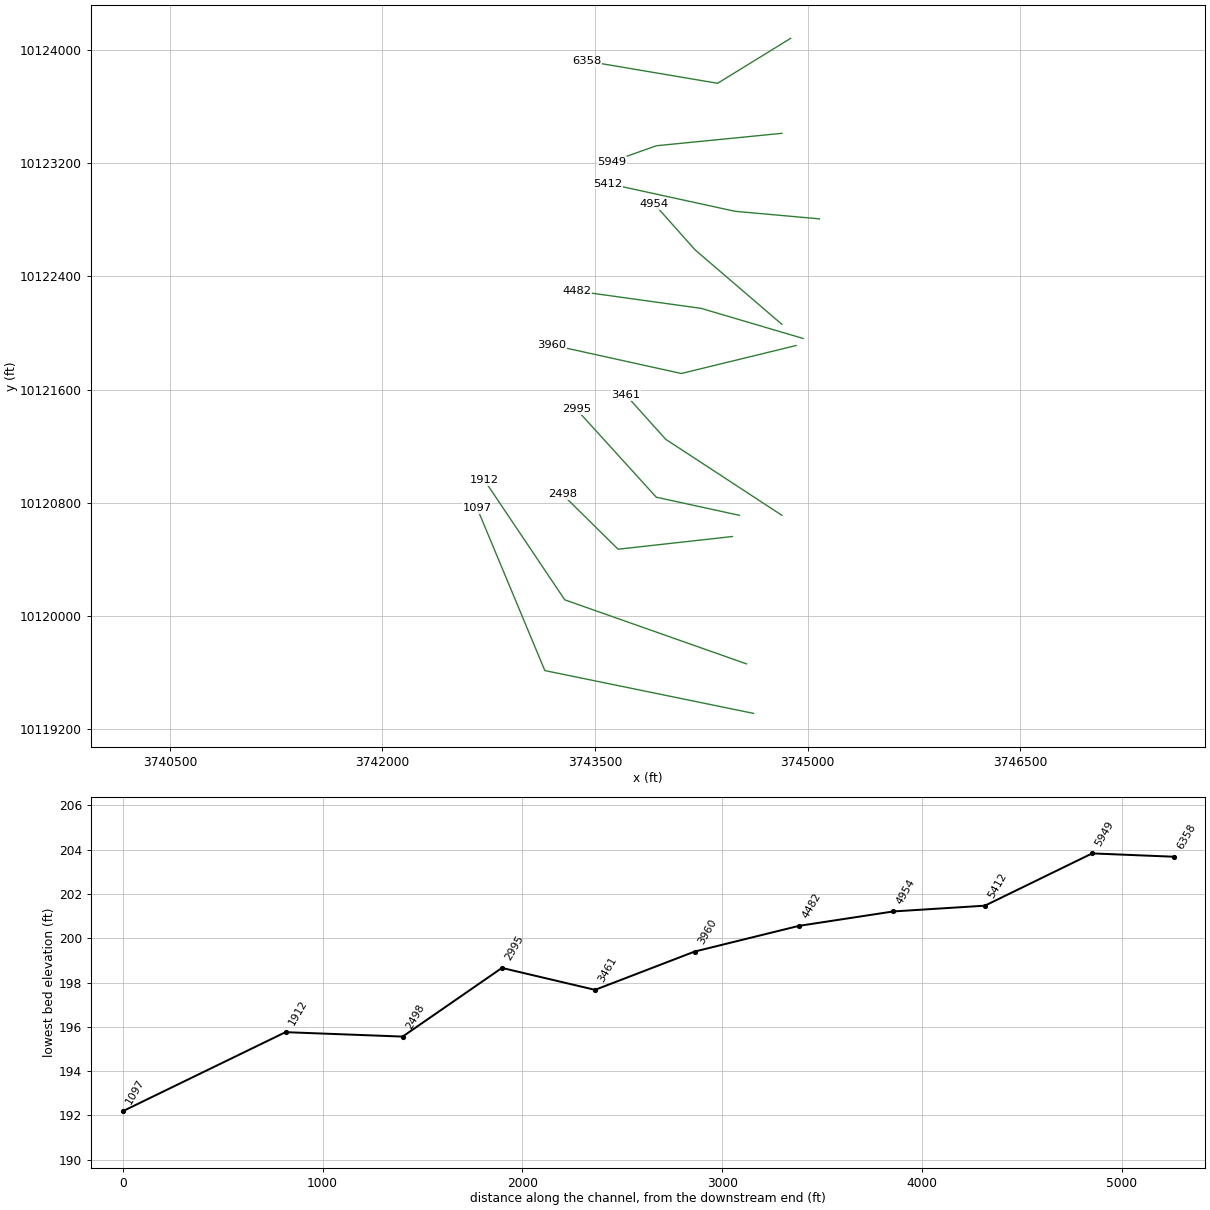
HEC-RAS study LAKE CREEK TRIBUTARY NO 5.prj: LAKE CREEK TRIBUTARY NO 5 Base Level Engineering

--- LAKE CREEK TRIBUTARY NO 5.g01 (geometry) --- (continued)

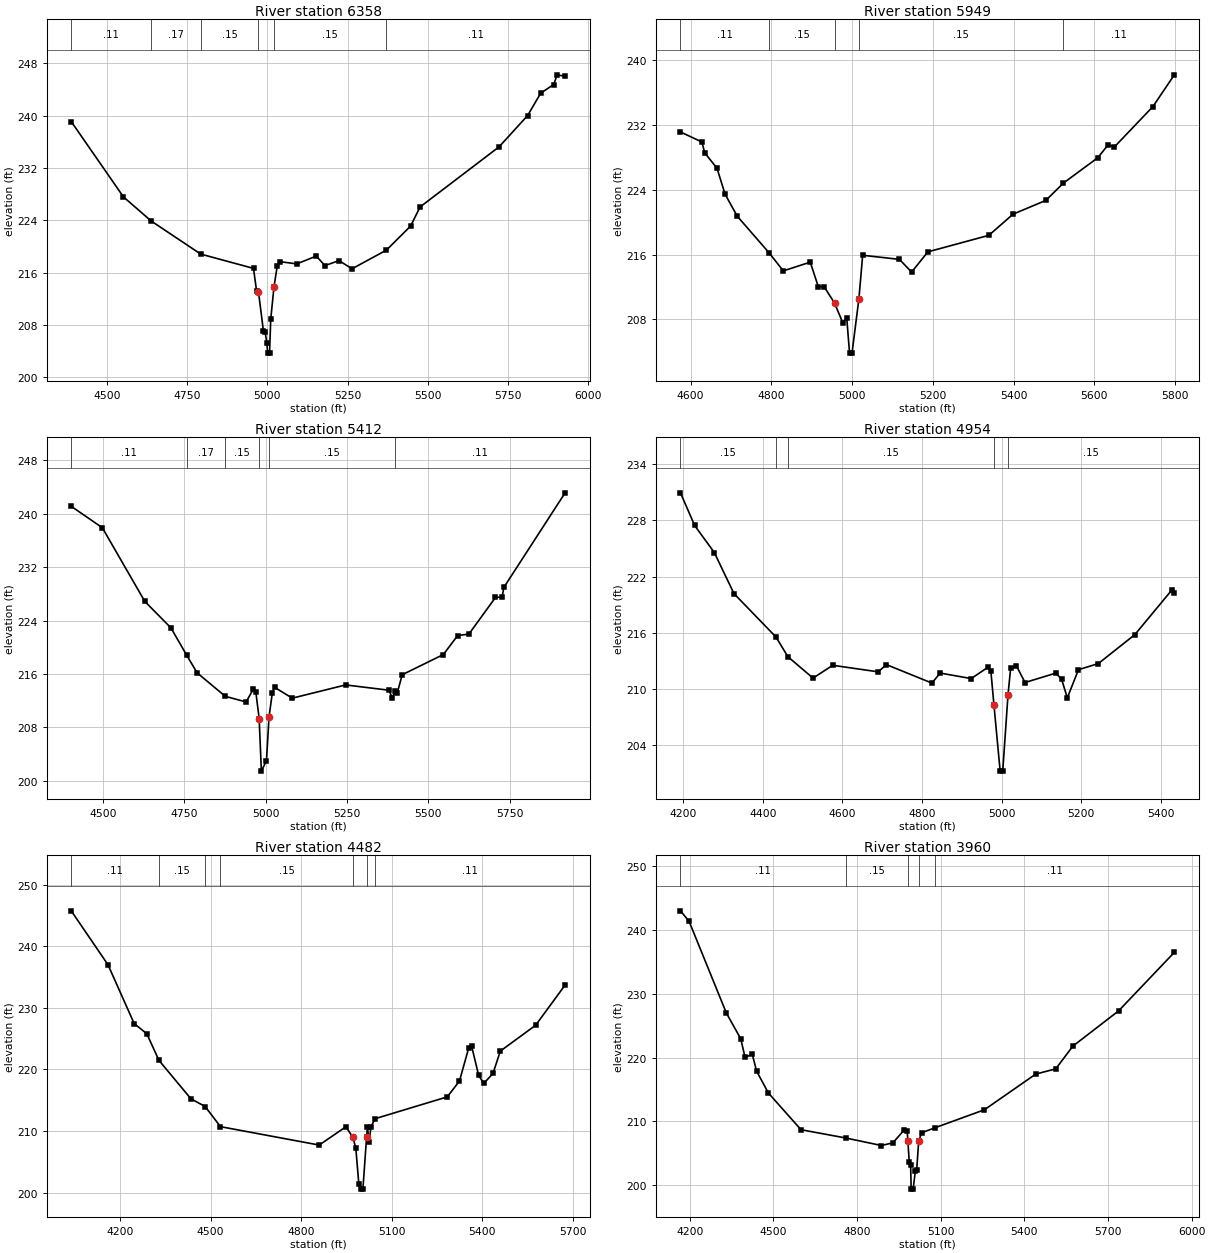
Type RM Length L Ch R = 1 ,6358    ,409,409,409
BEGIN DESCRIPTION:
LAKE CREEK TRIBUTARY NO. 5 11.0
END DESCRIPTION:
XS GIS Cut Line= 3
      3744879.87     10124082.46      3744364.22     10123764.74
      3743442.64     10123920.94
#Sta/Elev= 30
  4388.3   239.1  4551.1  227.58  4637.4   223.9  4792.1  218.83  4956.8  216.64
  4966.2  213.25  4972.2   213.1  4987.6  207.12  4992.7  206.95  4998.7  205.21
  5000.7  203.68  5006.8  203.68  5010.6   208.9  5020.7  213.81  5030.9  217.04
    5041  217.66  5091.7  217.33  5152.6  218.52  5179.7  217.07  5223.6  217.83
  5264.1  216.58  5371.5  219.44  5446.7  223.11  5476.4  226.04  5722.9  235.24
  5811.8  240.02  5852.4  243.43    5893  244.77  5903.9  246.25  5928.7  246.02
#Mann= 6 ,-1 , 0
  4388.3     .11       0  4637.4     .17       0  4792.1     .15       0
  4972.2     .09       0  5020.7     .15       0  5371.5     .11       0
Bank Sta=4972.2,5020.7
XS Rating Curve= 0 ,0
Exp/Cntr=0.3,0.1

Type RM Length L Ch R = 1 ,5949    ,537,537,537
BEGIN DESCRIPTION:
LAKE CREEK TRIBUTARY NO. 5 10.0
END DESCRIPTION:
XS GIS Cut Line= 3
      3744817.88     10123411.07      3743932.13     10123323.19
      3743617.84     10123211.07
#Sta/Elev= 30
  4574.7  231.13  4627.7  229.89    4635  228.54  4665.2  226.65  4685.3  223.44
  4715.4  220.73  4794.5   216.2  4829.5  213.98  4896.3  215.06  4916.4  212.01
  4930.3  212.05  4956.6     210  4976.7   207.6  4986.7  208.17  4993.7  203.83
  4999.8  203.83  5016.9  210.56  5026.2  215.91  5117.4   215.4  5147.5  213.83
  5187.7  216.33  5338.9  218.37  5398.8  220.98    5480  222.68  5523.7  224.82
  5608.9  227.95  5634.4  229.54  5649.8  229.27  5745.4  234.26  5798.5  238.18
#Mann= 5 ,-1 , 0
  4574.7     .11       0  4794.5     .15       0  4956.6     .09       0
  5016.9     .15       0  5523.7     .11       0
Bank Sta=4956.6,5016.9
XS Rating Curve= 0 ,0
Exp/Cntr=0.3,0.1

Type RM Length L Ch R = 1 ,5412    ,458,458,458
BEGIN DESCRIPTION:
LAKE CREEK TRIBUTARY NO. 5 9.0
END DESCRIPTION:
XS GIS Cut Line= 3
        3745083.      10122806.4      3744488.09      10122859.8
       3743588.9     10123056.25
#Sta/Elev= 30
  4402.7   241.1  4498.2   237.9  4628.8  226.87  4709.1  222.91  4757.1  218.85
  4789.4  216.19  4875.9  212.67    4940  211.82  4961.7   213.7  4970.1  213.27
  4980.2  209.34    4987  201.47  5002.7  203.04  5010.5  209.57  5020.7  213.19
  5027.6  214.01  5082.1  212.39  5245.9  214.37    5379  213.58  5389.2  212.45
  5398.8  213.48  5404.4  213.15  5419.9   215.9  5546.3  218.92  5590.2  221.76
  5624.6  221.97  5706.5  227.47    5727  227.52  5732.1  228.96  5920.4  243.12
#Mann= 6 ,-1 , 0
  4402.7     .11       0  4757.1     .17       0  4875.9     .15       0
  4980.2     .09       0  5010.5     .15       0  5398.8     .11       0
Bank Sta=4980.2,5010.5
XS Rating Curve= 0 ,0
Exp/Cntr=0.3,0.1

Type RM Length L Ch R = 1 ,4954    ,472,472,472
BEGIN DESCRIPTION:
LAKE CREEK TRIBUTARY NO. 5 8.0
END DESCRIPTION:
XS GIS Cut Line= 3
      3744817.82      10122061.1      3744205.91     10122586.93
      3743917.88     10122911.04
#Sta/Elev= 30
  4193.2  230.95  4228.8  227.46  4278.2  224.57  4327.6  220.18  4432.9  215.55
  4463.2  213.43  4526.2  211.15  4575.6  212.52  4689.7  211.82  4710.6  212.59
  4824.7  210.62  4845.5  211.69  4923.4   211.1  4966.2  212.33  4972.8   211.9
  4980.5  208.29  4996.1  201.21  5002.6  201.21  5015.9  209.39  5022.6  212.26
  5036.8  212.48  5058.6  210.68  5136.4  211.69  5150.6  211.01  5164.8  209.04
  5192.8  212.05  5242.6   212.7  5334.5   215.8  5426.5  220.52  5433.6  220.21
#Mann= 5 ,-1 , 0
  4193.2     .15       0  4432.9     .11       0  4463.2     .15       0
  4980.5     .09       0  5015.9     .15       0
Bank Sta=4980.5,5015.9
XS Rating Curve= 0 ,0
Exp/Cntr=0.3,0.1

Type RM Length L Ch R = 1 ,4482    ,522,522,522
BEGIN DESCRIPTION:
LAKE CREEK TRIBUTARY NO. 5 7.0
END DESCRIPTION:
XS GIS Cut Line= 3
      3744967.84     10121961.07      3744247.67     10122173.89
      3743371.16     10122295.75
#Sta/Elev= 30
  4038.3  245.78    4160  237.02  4246.8  227.46  4288.6  225.81  4328.8  221.49
  4434.5  215.25  4481.9  213.98  4532.6  210.71  4859.7  207.72    4948  210.69
  4970.8  209.02  4980.9  207.25    4991  201.36  4997.8  200.56  5004.4  200.56
  5016.8209.1065  5019.6  210.64  5024.7  208.21  5031.4  210.71  5044.6     212
  5283.8  215.55  5324.2  218.12  5354.5  223.42  5364.6  223.79  5387.9  219.03
  5404.9  217.74  5435.2  219.35  5459.6  222.99  5576.6  227.19  5674.2  233.72
#Mann= 7 ,-1 , 0
  4038.3     .11       0  4328.8     .15       0  4481.9     .11       0
  4532.6     .15       0  4970.8     .09       0  5016.8     .15       0
  5044.6     .11       0
Bank Sta=4970.8,5016.8
XS Rating Curve= 0 ,0
Exp/Cntr=0.3,0.1

Type RM Length L Ch R = 1 ,3960    ,499,499,499
BEGIN DESCRIPTION:
LAKE CREEK TRIBUTARY NO. 5 6.0
END DESCRIPTION:
XS GIS Cut Line= 3
      3744917.84     10121911.07      3744108.42     10121713.46
      3743192.59     10121915.72
#Sta/Elev= 30
  4166.8  242.97  4197.7  241.33  4331.5  226.96    4383  222.93  4398.5  220.01
  4424.1  220.53  4440.2  217.84  4481.9  214.46  4599.1   208.7  4759.3  207.41
  4887.3  206.23  4928.5  206.64  4969.7  208.69    4980  208.47 4982.21206.9915
  4987.1  203.72  4992.2  203.16  4994.2   199.4  5001.3   199.4  5008.9  202.17
    5014  202.44  5021.1   206.9  5031.3  208.22  5080.3  209.02  5256.6  211.82
  5440.9  217.41  5512.6  218.23  5574.1  221.79  5737.9   227.3  5937.9  236.47
#Mann= 5 ,-1 , 0
  4166.8     .11       0  4759.3     .15       0 4982.21     .09       0
  5021.1     .15       0  5080.3     .11       0
Bank Sta=4982.21,5021.1
XS Rating Curve= 0 ,0
Exp/Cntr=0.3,0.1

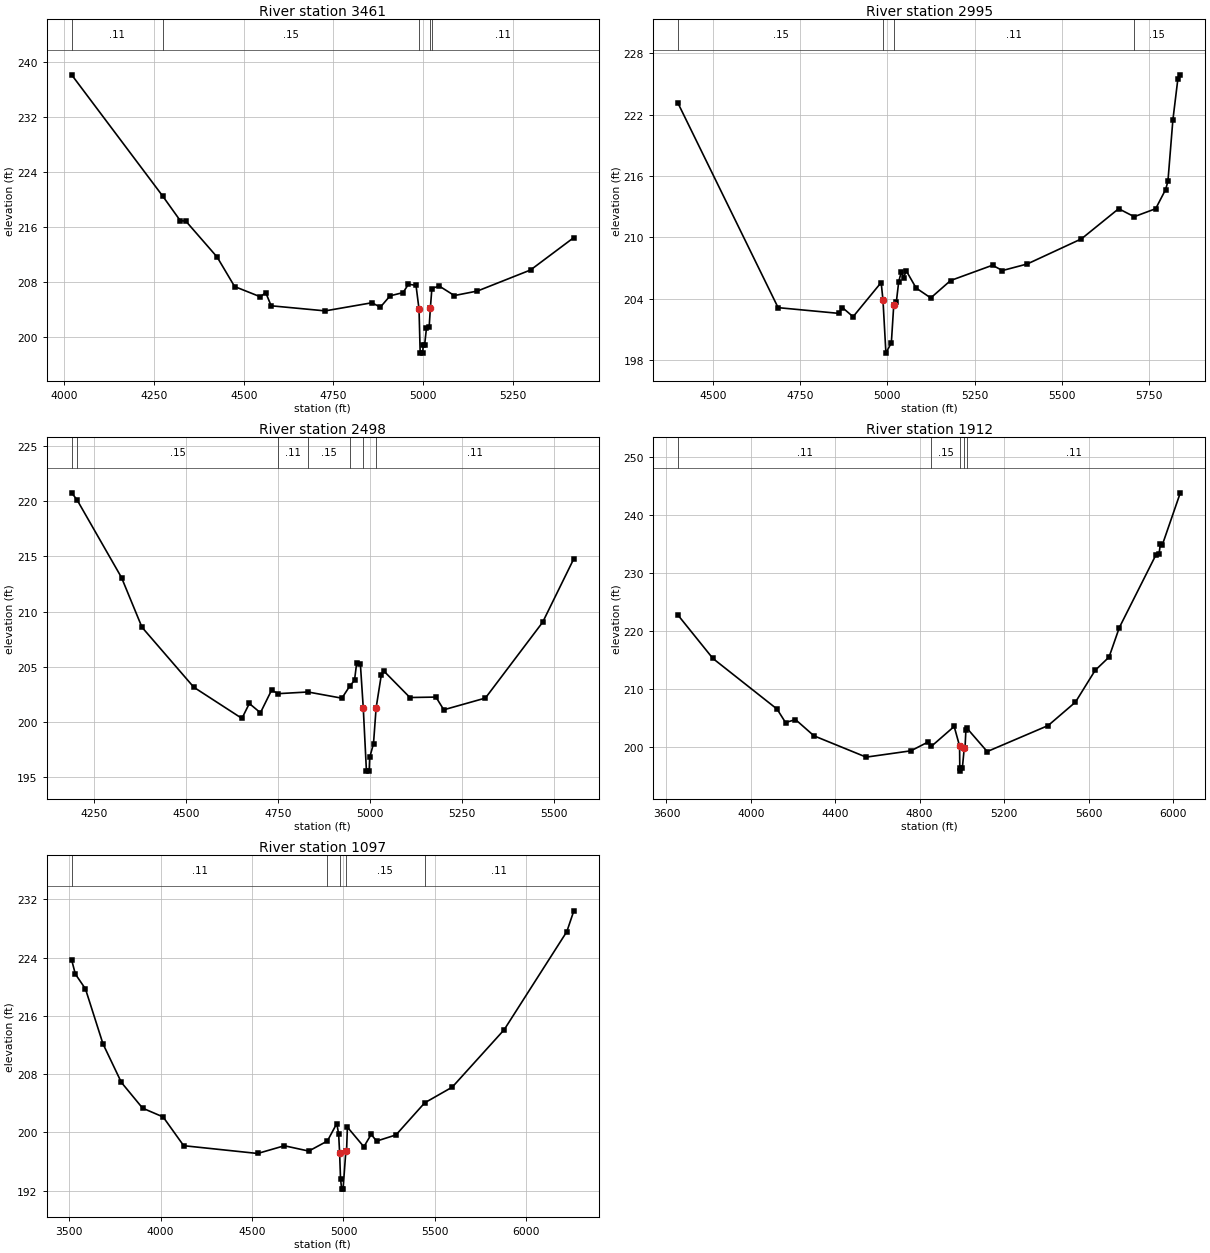
Type RM Length L Ch R = 1 ,3461    ,466,466,466
BEGIN DESCRIPTION:
LAKE CREEK TRIBUTARY NO. 5 5.0
END DESCRIPTION:
XS GIS Cut Line= 3
      3744817.88     10120711.05      3743998.26     10121248.29
      3743717.83     10121561.09
#Sta/Elev= 30
    4020  238.18  4273.3  220.57    4323  216.94  4338.1   216.9  4425.5  211.66
  4474.4  207.36  4546.1  205.87  4561.1  206.48  4576.2  204.56  4726.9  203.82
    4857     205  4880.7  204.36  4907.8  206.01    4944  206.48  4959.1  207.71
  4980.1  207.52  4988.5  204.07  4991.7  197.67  4998.8  197.67    5000  198.83
    5004  198.83  5009.3  201.34  5016.8  201.52 5020.15 204.265  5024.3  207.07
  5044.4  207.45    5087  206.05  5151.3  206.71  5299.3  209.77  5420.1  214.49
#Mann= 5 ,-1 , 0
    4020     .11       0  4273.3     .15       0  4988.5     .09       0
 5020.15     .15       0  5024.3     .11       0
Bank Sta=4988.5,5020.15
XS Rating Curve= 0 ,0
Exp/Cntr=0.3,0.1

Type RM Length L Ch R = 1 ,2995    ,497,497,497
BEGIN DESCRIPTION:
LAKE CREEK TRIBUTARY NO. 5 4.0
END DESCRIPTION:
XS GIS Cut Line= 3
      3744517.81     10120711.08      3743931.82     10120839.06
      3743367.87     10121461.05
#Sta/Elev= 30
  4400.2  223.09  4686.8  203.11  4860.8  202.55    4871  203.12  4901.7  202.22
  4982.2  205.57  4987.4  203.84  4995.8  198.66  5011.4  199.68  5018.2  203.33
  5025.6  203.64  5032.4  205.63  5039.8  206.61  5046.5  206.04    5054  206.72
  5082.4  205.03  5124.3  204.06    5181  205.76  5301.3  207.26  5329.7  206.74
  5400.7  207.38  5556.2  209.84  5662.9  212.79  5707.4  212.01    5769  212.79
  5797.4  214.66  5804.1  215.47  5818.3  221.47  5832.5  225.46  5839.6  225.89
#Mann= 4 ,-1 , 0
  4400.2     .15       0  4987.4     .09       0  5018.2     .11       0
  5707.4     .15       0
Bank Sta=4987.4,5018.2
XS Rating Curve= 0 ,0
Exp/Cntr=0.3,0.1

Type RM Length L Ch R = 1 ,2498    ,586,586,586
BEGIN DESCRIPTION:
LAKE CREEK TRIBUTARY NO. 5 3.0
END DESCRIPTION:
XS GIS Cut Line= 3
      3744467.81     10120561.07      3743662.49     10120471.37
      3743267.87     10120861.06
#Sta/Elev= 30
  4189.7  220.74  4204.4   220.1  4325.3  213.07  4380.8  208.58  4521.7  203.15
  4652.5  200.33  4672.6  201.68  4702.8  200.84    4733  202.88  4751.5  202.57
    4832  202.72  4924.2  202.16  4945.7  203.26  4958.5  203.78  4964.4  205.36
  4974.5  205.22 4982.28201.2757  4990.9  195.56  4998.3  195.56  4999.8   196.8
  5010.1  198.05  5017.2  201.28  5031.4  204.28  5038.4  204.61  5109.1  202.22
  5179.8  202.26  5201.1  201.11  5314.2  202.17  5469.8  209.03  5554.6  214.78
#Mann= 7 ,-1 , 0
  4189.7     .11       0  4204.4     .15       0  4751.5     .11       0
    4832     .15       0  4945.7     .11       0 4982.28     .07       0
  5017.2     .11       0
Bank Sta=4982.28,5017.2
XS Rating Curve= 0 ,0
Exp/Cntr=0.3,0.1

Type RM Length L Ch R = 1 ,1912    ,815,815,815
BEGIN DESCRIPTION:
LAKE CREEK TRIBUTARY NO. 5 2.0
END DESCRIPTION:
XS GIS Cut Line= 3
       3744567.9     10119661.06      3743286.09     10120113.69
      3742717.88     10120961.03
#Sta/Elev= 30
  3655.4  222.69  3820.2  215.23  4124.2  206.48  4164.5  204.15  4211.6  204.67
  4299.1  201.86  4546.5  198.18  4758.4  199.27  4839.8  200.79  4855.3  200.04
  4963.5  203.48  4989.1   200.1  4990.1  196.26  4990.6  195.76  5002.3  196.32
  5011.2  199.73  5014.8  199.73  5019.1  202.89  5023.6  203.19    5120  199.14
  5408.9  203.64  5538.3  207.69  5631.4  213.17  5697.4  215.47  5746.1  220.57
  5919.5  233.13  5934.5  233.36  5940.5  234.99  5949.5  234.82    6035  243.85
#Mann= 5 ,-1 , 0
  3655.4     .11       0  4855.3     .15       0  4989.1     .09       0
  5011.2     .15       0  5023.6     .11       0
Bank Sta=4989.1,5011.2
XS Rating Curve= 0 ,0
Exp/Cntr=0.3,0.1

Type RM Length L Ch R = 1 ,1097    ,0,0,0
BEGIN DESCRIPTION:
LAKE CREEK TRIBUTARY NO. 5 1.0
END DESCRIPTION:
XS GIS Cut Line= 3
      3744617.81     10119311.08      3743145.47     10119613.69
      3742667.86     10120761.04
#Sta/Elev= 30
  3513.7   223.7  3533.7  221.76  3589.2  219.71  3684.8  212.17  3785.5  206.86
  3901.6  203.32  4013.9  202.11  4126.2  198.16  4530.7  197.09  4676.7  198.15
  4810.2  197.42  4911.8   198.8  4963.3   201.2  4973.5  199.79  4978.8  197.22
  4983.9   193.6  4990.2  192.19  4997.8  192.19    5013  197.41  5016.8  197.41
  5021.5  200.71  5111.5  198.01  5151.6  199.72  5180.8  198.79    5287  199.64
  5444.1  204.05  5594.8  206.21  5878.7   214.1  6221.2  227.58  6259.6  230.44
#Mann= 5 ,-1 , 0
  3513.7     .11       0  4911.8     .15       0  4978.8     .09       0
    5013     .15       0  5444.1     .11       0
Bank Sta=4978.8,5013
XS Rating Curve= 0 ,0
Exp/Cntr=0.3,0.1

Chan Stop Cuts=-1
Use User Specified Reach Order=0
Composite Channel Slope=5