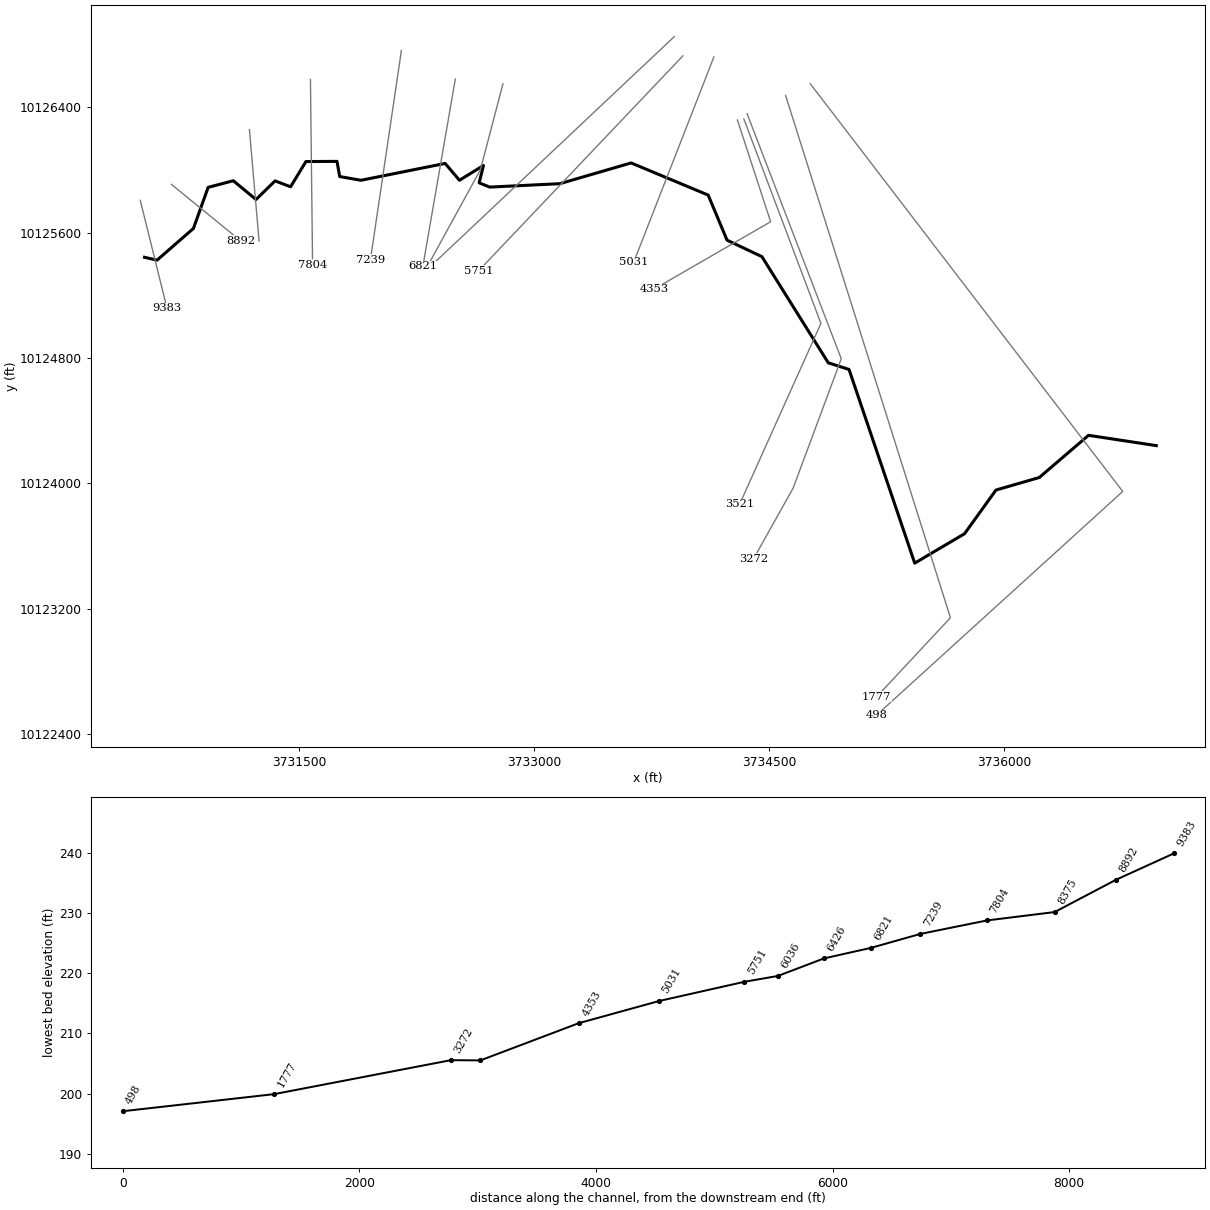
--- LAKE CREEK TRIBUTARY NO 6.prj (project) ---

Proj Title=LAKE CREEK TRIBUTARY NO 6 Base Level Engineering
Current Plan=p01
Default Exp/Contr=0.3,0.1
English Units
Geom File=g01
Flow File=f01
Plan File=p01
Y Axis Title=Elevation
X Axis Title(PF)=Main Channel Distance
X Axis Title(XS)=Station
BEGIN DESCRIPTION:
LAKE CREEK TRIBUTARY NO 6
END DESCRIPTION:
DSS Export Rating Curves= 0
DSS Export Rating Curve Sorted= 0
DSS Export Volume Flow Curves= 0
DXF OffsetX= 0
DXF OffsetY= 0
DXF ScaleX= 1
DXF ScaleY= 10

--- LAKE CREEK TRIBUTARY NO 6.p01 (plan) ---

Plan Title=Multiple Run
Short Identifier=Multiple
Geom File=g01
Flow File=f01
Subcritical Flow
K Sum by GR= 0
Std Step Tol= 0.01
Critical Tol= 0.01
Num of Std Step Trials= 20
Max Error Tol= 0.3
Flow Tol Ratio= 0.001
Split Flow NTrial= 30
Split Flow Tol= 0.02
Split Flow Ratio= 0.02
Log Output Level= 0
Friction Slope Method= 1
Unsteady Friction Slope Method= 2
Unsteady Bridges Friction Slope Method= 1
Parabolic Critical Depth
Global Vel Dist=  1 , 1 , 1
Global Log Level= 0
CheckData=True
Encroach Param= -1, 0, 0, 0
BEGIN DESCRIPTION:
Multiple Run
END DESCRIPTION:

--- LAKE CREEK TRIBUTARY NO 6.f01 (steady flow) ---

Flow Title=Multiple
Program Version=4.10
Number of Profiles= 7
Profile Names=10-year,25-year,50-year,1pct_min,100-year,1pct_plu,500-year
River Rch & RM=LAKE CREEK TRIBU,Reach-1         ,9383
     345     454     601     264     797    2407    1440
River Rch & RM=LAKE CREEK TRIBU,Reach-1         ,8892
     780    1066    1449     647    1955    5904    3683
Boundary for River Rch & Prof#=LAKE CREEK TRIBU,Reach-1         , 1
Up Type= 0
Dn Type= 3
Dn Slope=0.005
Boundary for River Rch & Prof#=LAKE CREEK TRIBU,Reach-1         , 2
Up Type= 0
Dn Type= 3
Dn Slope=0.005
Boundary for River Rch & Prof#=LAKE CREEK TRIBU,Reach-1         , 3
Up Type= 0
Dn Type= 3
Dn Slope=0.005
Boundary for River Rch & Prof#=LAKE CREEK TRIBU,Reach-1         , 4
Up Type= 0
Dn Type= 3
Dn Slope=0.005
Boundary for River Rch & Prof#=LAKE CREEK TRIBU,Reach-1         , 5
Up Type= 0
Dn Type= 3
Dn Slope=0.005
Boundary for River Rch & Prof#=LAKE CREEK TRIBU,Reach-1         , 6
Up Type= 0
Dn Type= 3
Dn Slope=0.005
Boundary for River Rch & Prof#=LAKE CREEK TRIBU,Reach-1         , 7
Up Type= 0
Dn Type= 3
Dn Slope=0.005
DSS Import GetInterval= 0
DSS Import GetPeak= 0
DSS Import FillOption= 0

--- LAKE CREEK TRIBUTARY NO 6.g01 (geometry) ---

Geom Title=Existing Conditions
Program Version=4.10

River Reach=LAKE CREEK TRIBU,Reach-1
Reach XY= 30
       3730515.1     10125442.19      3730594.96     10125424.13
       3730826.9     10125626.21      3730920.83     10125888.37
      3731081.24     10125930.55      3731226.04     10125810.76
      3731347.39     10125929.51      3731446.87     10125892.01
      3731544.26     10126052.95       3731742.7     10126053.99
      3731759.72     10125957.33      3731895.35     10125933.46
      3732432.46     10126040.88       3732523.6     10125933.46
       3732676.6     10126027.86      3732649.47     10125917.19
      3732716.75     10125890.06       3733163.8     10125911.76
      3733618.44     10126044.14      3734109.98     10125839.06
      3734230.42     10125551.52      3734452.86     10125446.27
      3734876.04     10124769.18      3735008.41     10124726.86
       3735427.4     10123491.62       3735745.1     10123679.12
      3735945.62     10123957.77      3736221.67     10124037.63
       3736535.9     10124306.73      3736968.32     10124241.11

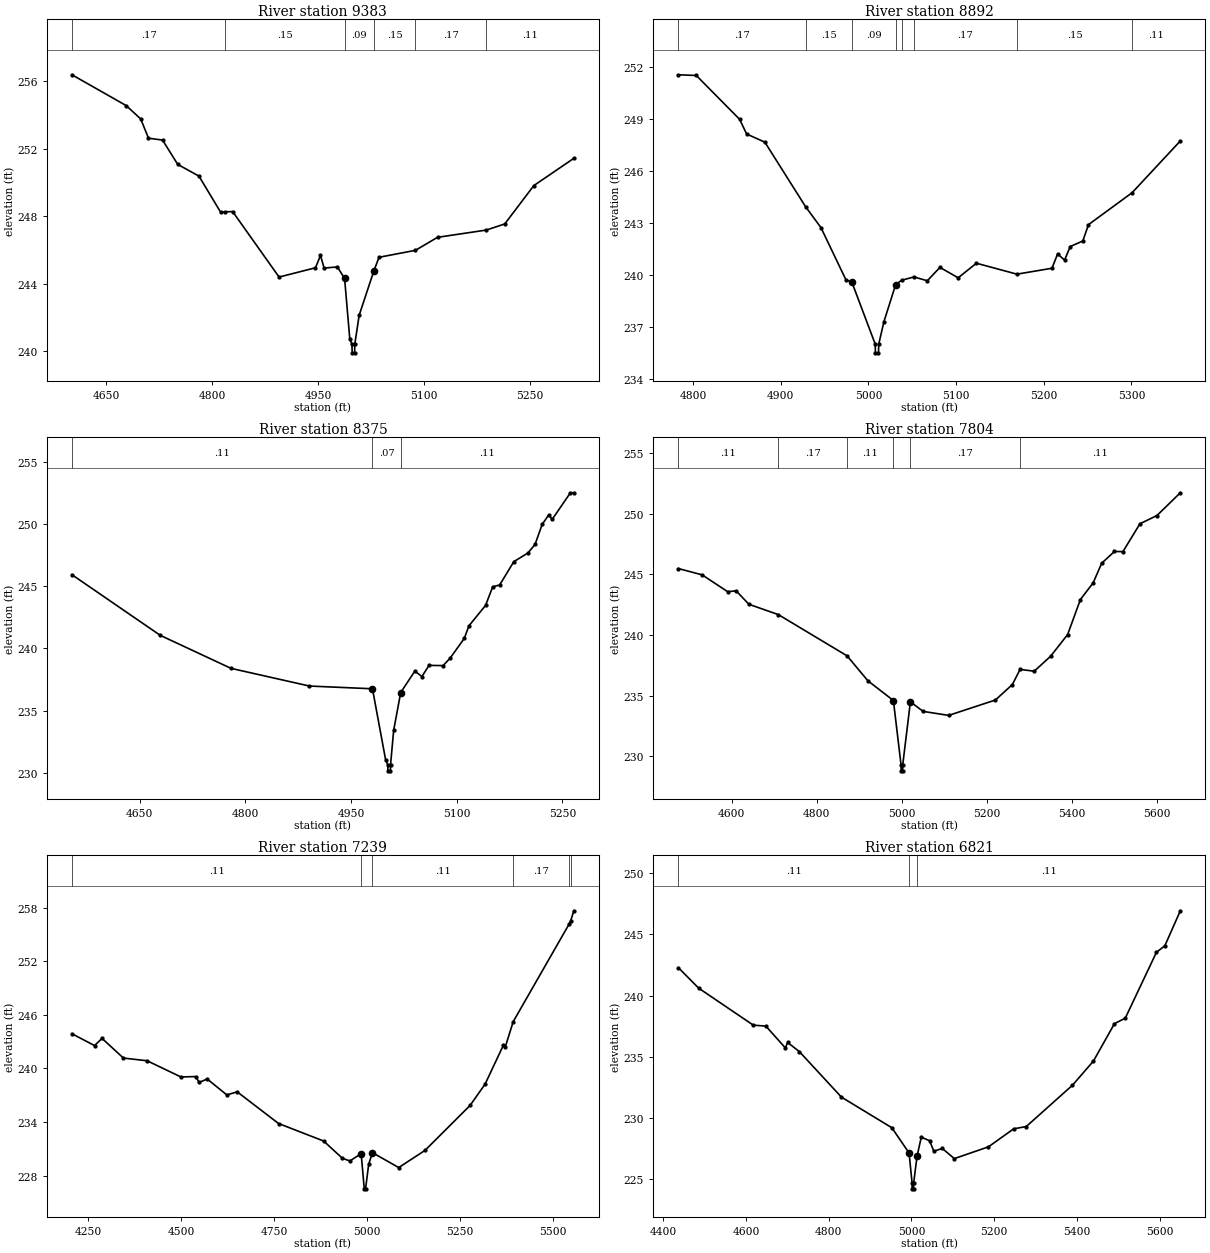
Type RM Length L Ch R = 1 ,9383    ,491,491,491
BEGIN DESCRIPTION:
LAKE CREEK TRIBUTARY NO. 6 2.0
END DESCRIPTION:
XS GIS Cut Line= 2
      3730487.89     10125805.54      3730658.53     10125116.15
#Sta/Elev= 30
  4601.5  256.36  4678.2  254.54  4698.8  253.75  4709.8  252.61  4729.7   252.5
  4751.2  251.06  4781.2  250.37  4812.1  248.22  4818.7  248.26  4828.9  248.27
  4894.6   244.4  4946.1  244.95  4953.2  245.68  4958.3  244.93    4977     245
  4987.3  244.32  4994.6  240.76  4997.7  240.42    4998  239.92  5001.5  239.92
  5001.7  240.42  5007.9  242.14  5028.5  244.74    5036  245.57  5087.5  245.98
  5118.8  246.75  5187.9  247.18  5213.9  247.54  5255.1  249.81  5311.7  251.42
#Mann= 6 ,-1 , 0
  4601.5     .17       0  4818.7     .15       0  4987.3     .09       0
  5028.5     .15       0  5087.5     .17       0  5187.9     .11       0
Bank Sta=4987.3,5028.5
XS Rating Curve= 0 ,0
Exp/Cntr=0.3,0.1

Type RM Length L Ch R = 1 ,8892    ,517,517,517
BEGIN DESCRIPTION:
Mapping XS 88ec27c2
END DESCRIPTION:
XS GIS Cut Line= 2
      3730685.83     10125907.95      3731129.53     10125546.16
#Sta/Elev= 30
  4783.2  251.53  4803.6  251.49  4853.1  248.96    4861  248.12  4881.8  247.65
  4928.3  243.93  4945.8  242.73  4974.5   239.7  4980.9  239.61  5007.7  236.02
  5007.9  235.52  5011.4  235.52  5011.7  236.02  5017.6  237.31    5031  239.45
  5037.8   239.7  5051.9  239.89  5067.1  239.67  5081.5  240.44  5102.3  239.84
  5123.1  240.68  5169.3  240.05  5209.3  240.39  5215.7  241.21  5223.7  240.86
  5230.1  241.64  5244.5  241.96  5250.9   242.9  5300.7  244.74  5355.7  247.72
#Mann= 8 ,-1 , 0
  4783.2     .17       0  4928.3     .15       0  4980.9     .09       0
    5031     .15       0  5037.8     .11       0  5051.9     .17       0
  5169.3     .15       0  5300.7     .11       0
Bank Sta=4980.9,5031
XS Rating Curve= 0 ,0
Exp/Cntr=0.3,0.1

Type RM Length L Ch R = 1 ,8375    ,571,571,571
BEGIN DESCRIPTION:
Mapping XS 3386131f
END DESCRIPTION:
XS GIS Cut Line= 2
      3731184.14     10126256.04      3731245.57     10125546.19
#Sta/Elev= 30
  4553.7  245.92  4679.1  241.05  4779.5   238.4  4890.8  236.98  4980.3  236.76
    4999  231.05    5002  230.67  5002.3  230.17  5005.8  230.17    5006  230.67
  5010.4  233.42  5020.4  236.46  5040.5  238.18  5050.5  237.74  5060.6  238.64
  5080.6  238.62  5090.7  239.23  5110.7  240.81  5117.2  241.81  5140.9  243.46
  5150.9  244.94  5160.9   245.1    5181  246.97  5201.1  247.67  5211.1  248.35
  5221.2  249.96  5230.4  250.71  5235.5  250.37  5261.3   252.5  5266.2   252.5
#Mann= 3 ,-1 , 0
  4553.7     .11       0  4980.3     .07       0  5020.4     .11       0
Bank Sta=4980.3,5020.4
XS Rating Curve= 0 ,0
Exp/Cntr=0.3,0.1

Type RM Length L Ch R = 1 ,7804    ,565,565,565
BEGIN DESCRIPTION:
Mapping XS 373d8439
END DESCRIPTION:
XS GIS Cut Line= 2
      3731573.22     10126576.86      3731586.87     10125396.03
#Sta/Elev= 30
  4475.1  245.49  4530.9  244.97  4590.9  243.58  4610.9  243.65  4640.9  242.54
    4710  241.69  4871.9  238.28  4920.9  236.22  4980.9  234.59  4998.9  229.28
  4999.2  228.78  5002.7  228.78  5002.9  229.28  5020.9  234.48  5050.9  233.69
  5110.9  233.36  5220.9  234.63  5260.9  235.91    5279  237.16  5312.3  237.01
  5350.9  238.25  5390.9  240.04  5420.9  242.93  5450.9  244.31    5471  245.93
    5501   246.9    5521  246.89    5561  249.19    5601  249.87    5656  251.75
#Mann= 6 ,-1 , 0
  4475.1     .11       0    4710     .17       0  4871.9     .11       0
  4980.9     .07       0  5020.9     .17       0    5279     .11       0
Bank Sta=4980.9,5020.9
XS Rating Curve= 0 ,0
Exp/Cntr=0.3,0.1

Type RM Length L Ch R = 1 ,7239    ,418,418,418
BEGIN DESCRIPTION:
Mapping XS d5a91863
END DESCRIPTION:
XS GIS Cut Line= 2
      3732153.43     10126761.23      3731955.68     10125424.68
#Sta/Elev= 30
  4205.6  243.88  4266.4  242.56  4286.6  243.36  4344.2  241.16  4407.9  240.86
  4498.9  239.05  4539.4  239.09  4547.8  238.43  4569.7  238.82  4622.4  237.04
  4650.5  237.38  4761.7  233.84  4883.1  231.88  4933.6  229.95  4953.8  229.65
  4984.1  230.47  4992.5  226.53    4996  226.53  5004.4  229.28  5014.5  230.58
  5085.2  228.91    5156  230.83  5277.3  235.86  5317.7  238.24  5367.1  242.61
  5372.2  242.42  5393.5  245.24  5544.2  256.17  5547.7  256.46  5556.7  257.64
#Mann= 6 ,-1 , 0
  4205.6     .11       0  4984.1     .07       0  5014.5     .11       0
  5393.5     .17       0  5544.2     .11       0  5547.7     .17       0
Bank Sta=4984.1,5014.5
XS Rating Curve= 0 ,0
Exp/Cntr=0.3,0.1

Type RM Length L Ch R = 1 ,6821    ,395,395,395
BEGIN DESCRIPTION:
Mapping XS c8bc762c
END DESCRIPTION:
XS GIS Cut Line= 2
      3732497.32     10126579.32      3732290.27     10125384.22
#Sta/Elev= 30
  4436.8  242.27  4485.8   240.6  4617.7  237.58  4648.1   237.5  4695.5  235.71
  4700.6  236.17  4729.3  235.41  4830.8   231.7  4952.6   229.2  4994.2  227.14
  5001.4  224.71  5001.6  224.21  5005.1  224.21  5005.4  224.71  5013.5  226.88
  5023.7  228.43  5043.8  228.14  5054.1  227.28  5074.4  227.51  5103.6  226.68
    5186  227.64  5246.9  229.11  5277.4   229.3    5389  232.67  5439.8  234.65
  5490.5   237.7  5516.7  238.15    5592  243.53  5612.3  244.06  5649.7  246.92
#Mann= 3 ,-1 , 0
  4436.8     .11       0  4994.2     .06       0  5013.5     .11       0
Bank Sta=4994.2,5013.5
XS Rating Curve= 0 ,0
Exp/Cntr=0.3,0.1

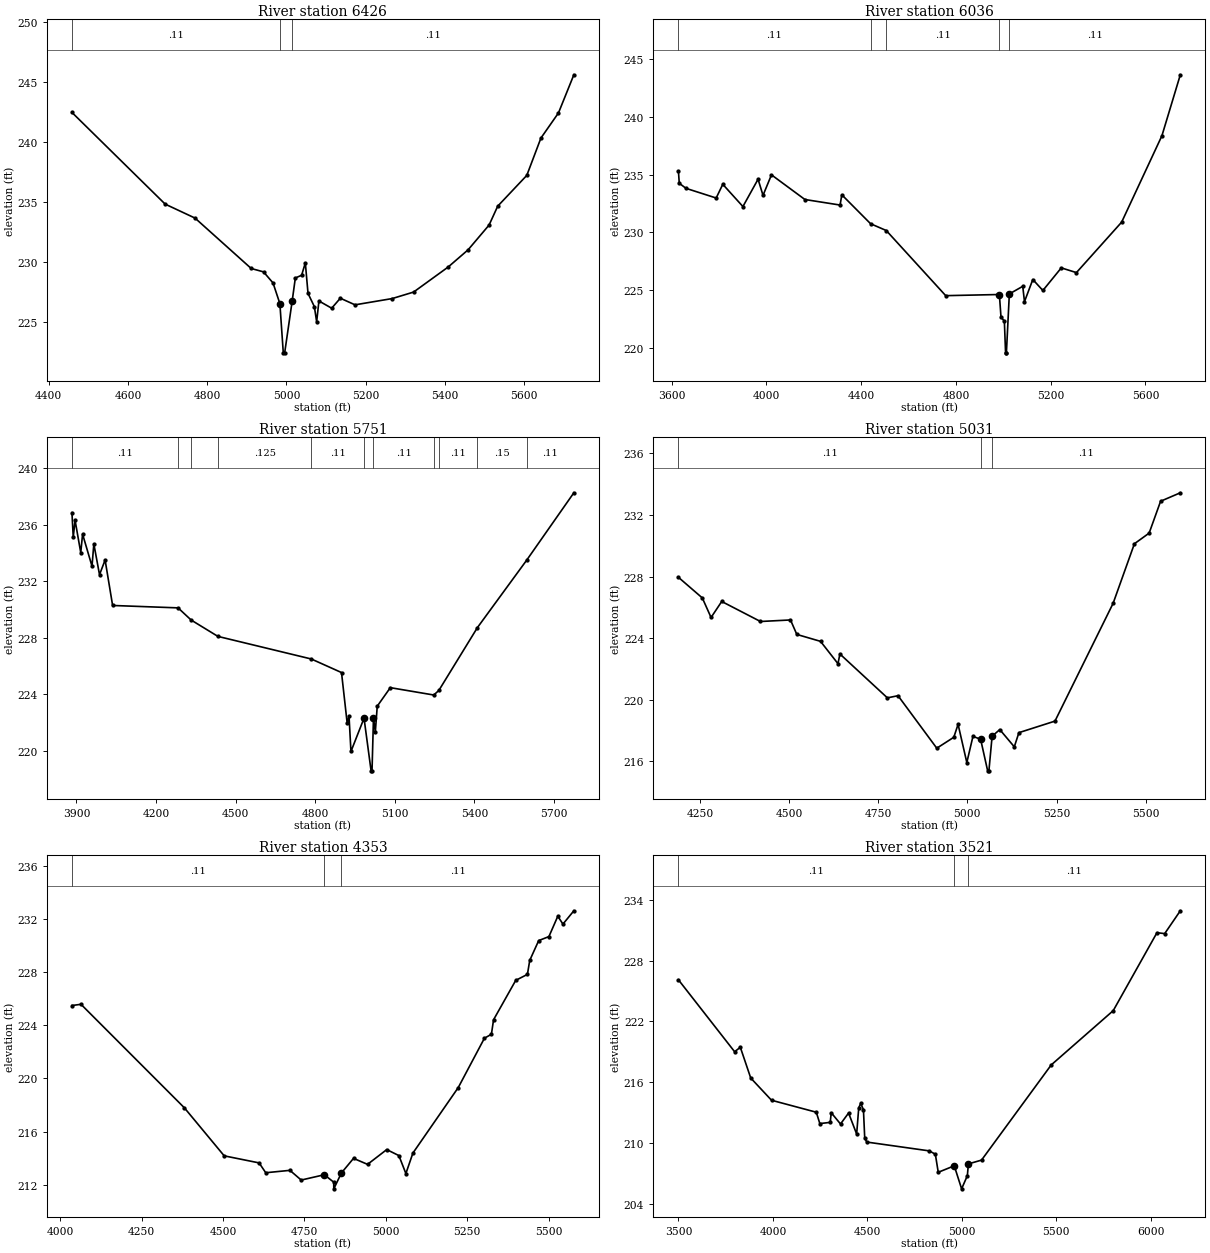
Type RM Length L Ch R = 1 ,6426    ,390,390,390
BEGIN DESCRIPTION:
Mapping XS f4745357
END DESCRIPTION:
XS GIS Cut Line= 3
      3732801.04     10126548.57      3732657.39     10126000.66
      3732320.82     10125387.03
#Sta/Elev= 30
  4458.7  242.45  4693.9  234.83  4769.2  233.67    4911  229.48    4942   229.2
    4966  228.28  4983.3  226.56  4991.9  222.47  4995.4  222.47  5014.4  226.79
  5022.3  228.69  5038.2  228.92  5047.5  229.95  5054.3  227.41  5070.3  226.31
  5076.1  225.05  5081.8  226.78    5114  226.18  5135.8  227.01  5172.9  226.46
  5266.6  226.98  5320.6  227.52  5407.8   229.6  5458.1  231.03  5511.1  233.09
  5532.9  234.66  5606.3  237.22  5641.9  240.32  5686.2  242.41    5725  245.58
#Mann= 3 , 0 , 0
  4458.7     .11       0  4983.3     .06       0  5014.4     .11       0
Bank Sta=4983.3,5014.4
XS Rating Curve= 0 ,0
Exp/Cntr=0.3,0.1

Type RM Length L Ch R = 1 ,6036    ,285,285,285
BEGIN DESCRIPTION:
Mapping XS 0c613c8f
END DESCRIPTION:
XS GIS Cut Line= 2
      3733894.04     10126849.92      3732352.13      10125396.7
#Sta/Elev= 30
  3628.5  235.33  3632.1  234.26  3660.4  233.82  3787.9  232.98  3815.8  234.17
  3900.8  232.24  3964.7  234.61  3985.7  233.21  4021.3  234.99  4162.5  232.85
    4311  232.37  4318.3  233.26  4439.7  230.75  4505.9  230.16  4756.9  224.51
  4983.4  224.61  4990.3  222.65  5004.5   222.3  5009.6  219.55  5013.1  219.55
  5025.5  224.66  5082.1  225.32  5089.4  223.99  5124.6  225.91  5167.1  224.96
  5244.8  226.92  5308.7  226.51  5499.7  230.89  5669.6  238.38  5747.3  243.67
#Mann= 5 ,-1 , 0
  3628.5     .11       0  4439.7    .125       0  4505.9     .11       0
  4983.4     .07       0  5025.5     .11       0
Bank Sta=4983.4,5025.5
XS Rating Curve= 0 ,0
Exp/Cntr=0.3,0.1

Type RM Length L Ch R = 1 ,5751    ,720,720,720
BEGIN DESCRIPTION:
Mapping XS 81a44a64
END DESCRIPTION:
XS GIS Cut Line= 2
      3733948.63     10126727.03      3732645.41     10125355.58
#Sta/Elev= 30
  3882.9  236.85  3887.8  235.12  3894.7  236.31  3916.1  234.02    3923  235.33
  3958.5  233.06  3965.4  234.64  3986.8  232.46  4007.9   233.5  4036.2  230.28
  4282.9  230.11  4332.1  229.25  4433.1  228.09  4785.1  226.49    4899  225.53
  4920.4  221.94  4927.3  222.45  4934.6  219.94  4983.9   222.3  5010.5  218.57
    5014  218.57  5019.5  222.32  5026.4  221.31  5033.7  223.15    5083  224.46
  5246.7  223.94  5265.8  224.26  5411.5  228.72  5596.7  233.48  5774.8  238.26
#Mann= 11 ,-1 , 0
  3882.9     .11       0  4282.9    .125       0  4332.1     .11       0
  4433.1    .125       0  4785.1     .11       0  4983.9     .07       0
  5019.5     .11       0  5246.7     .15       0  5265.8     .11       0
  5411.5     .15       0  5596.7     .11       0
Bank Sta=4983.9,5019.5
XS Rating Curve= 0 ,0
Exp/Cntr=0.3,0.1

Type RM Length L Ch R = 1 ,5031    ,678,678,678
BEGIN DESCRIPTION:
Mapping XS 9846d2b8
END DESCRIPTION:
XS GIS Cut Line= 2
      3734146.59     10126720.19      3733634.66     10125409.63
#Sta/Elev= 30
    4190  227.95    4257  226.61  4281.5  225.34  4311.4  226.38    4420  225.08
  4504.2  225.18  4521.9  224.24  4588.4  223.79  4637.3  222.34  4642.7  222.97
  4775.8  220.12  4805.6  220.26  4914.3  216.85    4962  217.56    4974   218.4
  4998.5  215.92  5015.7  217.62  5037.2  217.43  5056.9  215.38  5060.4  215.38
  5069.4  217.63  5090.9  218.06  5131.6  216.94  5144.5  217.86  5245.6  218.61
  5408.6  226.26  5468.3  230.13  5509.6  230.82  5541.7  232.89    5597  233.44
#Mann= 3 , 0 , 0
    4190     .11       0  5037.2     .06       0  5069.4     .11       0
Bank Sta=5037.2,5069.4
XS Rating Curve= 0 ,0
Exp/Cntr=0.3,0.1

Type RM Length L Ch R = 1 ,4353    ,832,832,832
BEGIN DESCRIPTION:
Mapping XS d6e151db
END DESCRIPTION:
XS GIS Cut Line= 3
      3734296.78     10126317.51      3734508.39     10125669.03
      3733764.36     10125238.99
#Sta/Elev= 30
  4036.1  225.48  4063.9  225.57  4381.4  217.79  4503.7  214.18  4610.9  213.65
  4631.3  212.91  4705.6  213.09  4740.2  212.36  4811.3  212.76  4840.1   212.2
  4840.3   211.7  4863.6  212.89  4900.9  213.99    4944  213.54  5002.9  214.65
  5040.2   214.2  5061.7  212.85  5083.3  214.39  5222.5  219.31  5302.9  223.02
  5324.4  223.32    5331  224.41  5399.1  227.37    5435  227.82  5442.1  228.87
  5469.6  230.36    5501  230.66  5528.3  232.19  5544.1   231.6  5577.6   232.6
#Mann= 3 , 0 , 0
  4036.1     .11       0  4811.3     .06       0  4863.6     .11       0
Bank Sta=4811.3,4863.6
XS Rating Curve= 0 ,0
Exp/Cntr=0.3,0.1

Type RM Length L Ch R = 1 ,3521    ,249,249,249
BEGIN DESCRIPTION:
Mapping XS 1feaa209
END DESCRIPTION:
XS GIS Cut Line= 3
      3734337.72     10126324.37      3734829.21     10125020.56
      3734310.45     10123867.01
#Sta/Elev= 30
  3499.6  226.11  3797.3  219.02  3827.5  219.46  3882.6  216.43  3992.7  214.24
  4229.8  213.06  4248.6  211.94  4303.6  212.06    4309  213.01  4358.1   211.9
  4400.8  212.98  4443.6  210.91  4454.6  213.49  4464.9  213.93  4479.5  213.32
  4486.3  210.53    4497  210.12  4828.3  209.25  4860.4  208.92  4875.7  207.14
  4960.5  207.78  4999.5  205.51  5029.9  206.81  5035.4  207.97  5104.9  208.34
  5474.1  217.72  5802.5  223.07  6034.1  230.75    6075  230.66  6157.8  232.91
#Mann= 3 , 0 , 0
  3499.6     .11       0  4960.5     .06       0  5035.4     .11       0
Bank Sta=4960.5,5035.4
XS Rating Curve= 0 ,0
Exp/Cntr=0.3,0.1

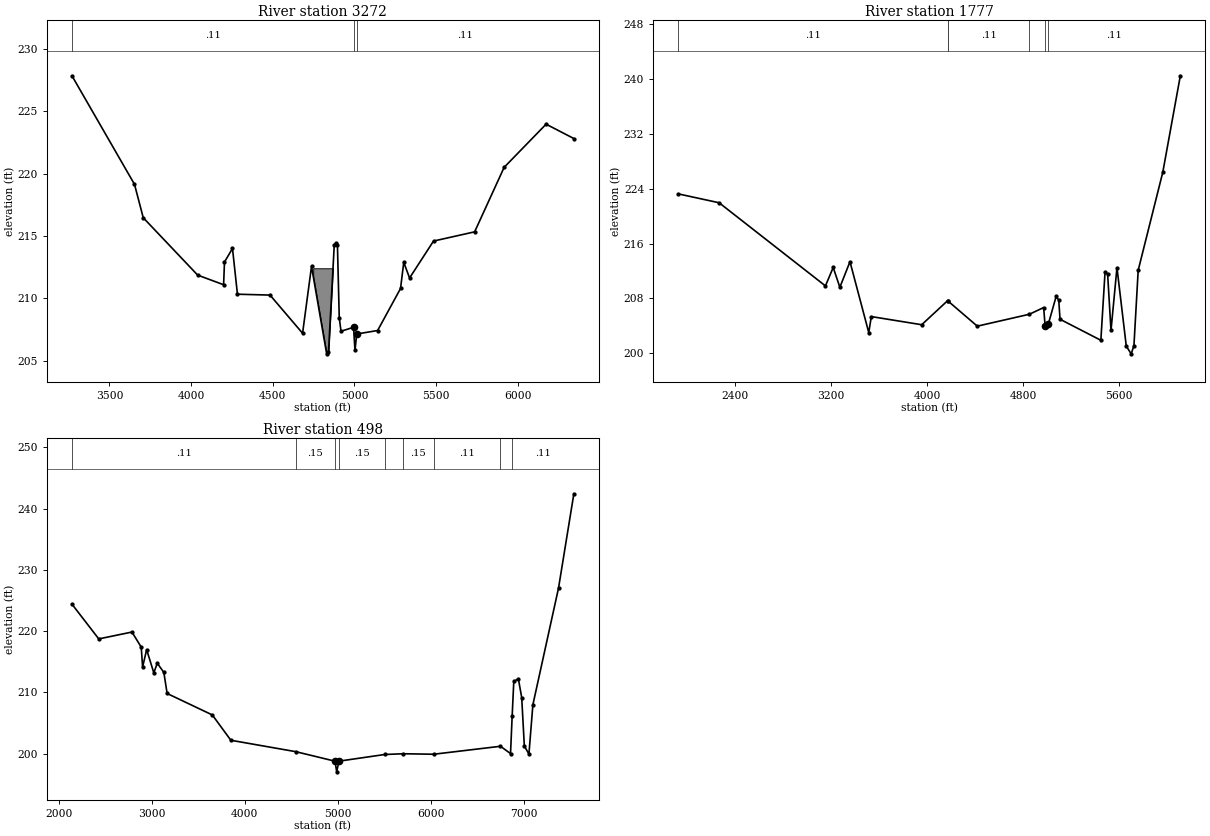
Type RM Length L Ch R = 1 ,3272    ,1495,1495,1495
BEGIN DESCRIPTION:
Mapping XS d11c8ece
END DESCRIPTION:
XS GIS Cut Line= 4
      3734358.23     10126358.42       3734958.9     10124795.31
      3734651.73     10123969.36      3734399.19     10123518.88
#Sta/Elev= 30
  3270.9  227.84  3653.7  219.14  3707.3  216.46  4040.6  211.86  4199.2  211.09
  4204.6  212.91  4253.6     214  4283.9  210.33  4483.3  210.26  4682.6   207.2
  4737.3  212.56  4830.1  205.55  4841.2  205.67  4876.6   214.3  4885.7  214.42
  4895.9   214.3  4907.1  208.44  4917.8  207.36  4994.7  207.68  5003.3  205.82
    5014  207.14    5142  207.42  5282.2  210.79  5301.9  212.88  5337.6  211.63
    5484  214.59  5735.8  215.33  5916.4   220.5  6173.2  223.96  6343.1  222.81
#Mann= 3 , 0 , 0
  3270.9     .11       0  4994.7     .06       0    5014     .11       0
#Block Obstruct= 1 ,-1
 4747.64 4872.64  212.41
Bank Sta=4994.7,5014
XS Rating Curve= 0 ,0
Exp/Cntr=0.3,0.1

Type RM Length L Ch R = 1 ,1777    ,1279,1279,1279
BEGIN DESCRIPTION:
Mapping XS 7f444f45
END DESCRIPTION:
XS GIS Cut Line= 3
      3734603.94     10126474.53      3735655.15     10123143.42
      3735184.15     10122638.28
#Sta/Elev= 30
  1926.2  223.25  2265.4  221.96  3151.7  209.82  3216.4  212.51    3272  209.62
  3356.3  213.35  3512.8  203.01  3534.2  205.34  3954.2  204.15  4170.1  207.66
  4170.2  207.66  4417.5  203.94  4851.7  205.68  4970.8  206.66  4983.1  203.91
  5010.2  204.28  5074.9  208.29  5096.6  207.74  5107.1  204.95  5447.5  201.88
  5482.6  211.89  5504.1  211.51    5532  203.31  5581.8  212.48  5659.5  201.02
  5700.2   199.9  5723.2  201.08  5758.7   212.1  5963.8  226.42  6109.9   240.5
#Mann= 6 ,-1 , 0
  1926.2     .11       0  4170.1     .17       0  4170.2     .11       0
  4851.7     .15       0  4983.1     .09       0  5010.2     .11       0
#Block Obstruct= 2 , 0
                         5495.96          212.21
Bank Sta=4983.1,5010.2
XS Rating Curve= 0 ,0
Exp/Cntr=0.3,0.1

Type RM Length L Ch R = 1 ,498     ,0,0,0
BEGIN DESCRIPTION:
LAKE CREEK TRIBUTARY NO. 6 1.0
END DESCRIPTION:
XS GIS Cut Line= 3
      3734760.98     10126549.55      3736754.14     10123948.88
      3735184.13     10122522.22
#Sta/Elev= 30
  2142.8  224.41  2431.2  218.74  2788.4  219.86  2888.1  217.39  2902.6  214.15
  2946.2  216.99  3023.1  213.21  3060.4  214.77  3131.1  213.28  3166.4  209.84
  3652.4  206.34  3851.8  202.21  4550.1  200.35  4971.4   198.8  4990.5  197.06
  5013.5   198.8  5508.1  199.89  5704.8  200.01  6033.1  199.93  6751.5  201.23
  6859.7  200.04  6877.4   206.2  6894.8   211.8  6944.1  212.23    6980  209.18
  7008.3  201.25  7057.7  199.97  7100.2  208.01  7375.9  227.03  7540.8  242.41
#Mann= 9 ,-1 , 0
  2142.8     .11       0  4550.1     .15       0  4971.4     .09       0
  5013.5     .15       0  5508.1     .11       0  5704.8     .15       0
  6033.1     .11       0  6751.5     .15       0  6877.4     .11       0
Bank Sta=4971.4,5013.5
XS Rating Curve= 0 ,0
Exp/Cntr=0.3,0.1

Chan Stop Cuts=-1
Use User Specified Reach Order=0
Composite Channel Slope=5