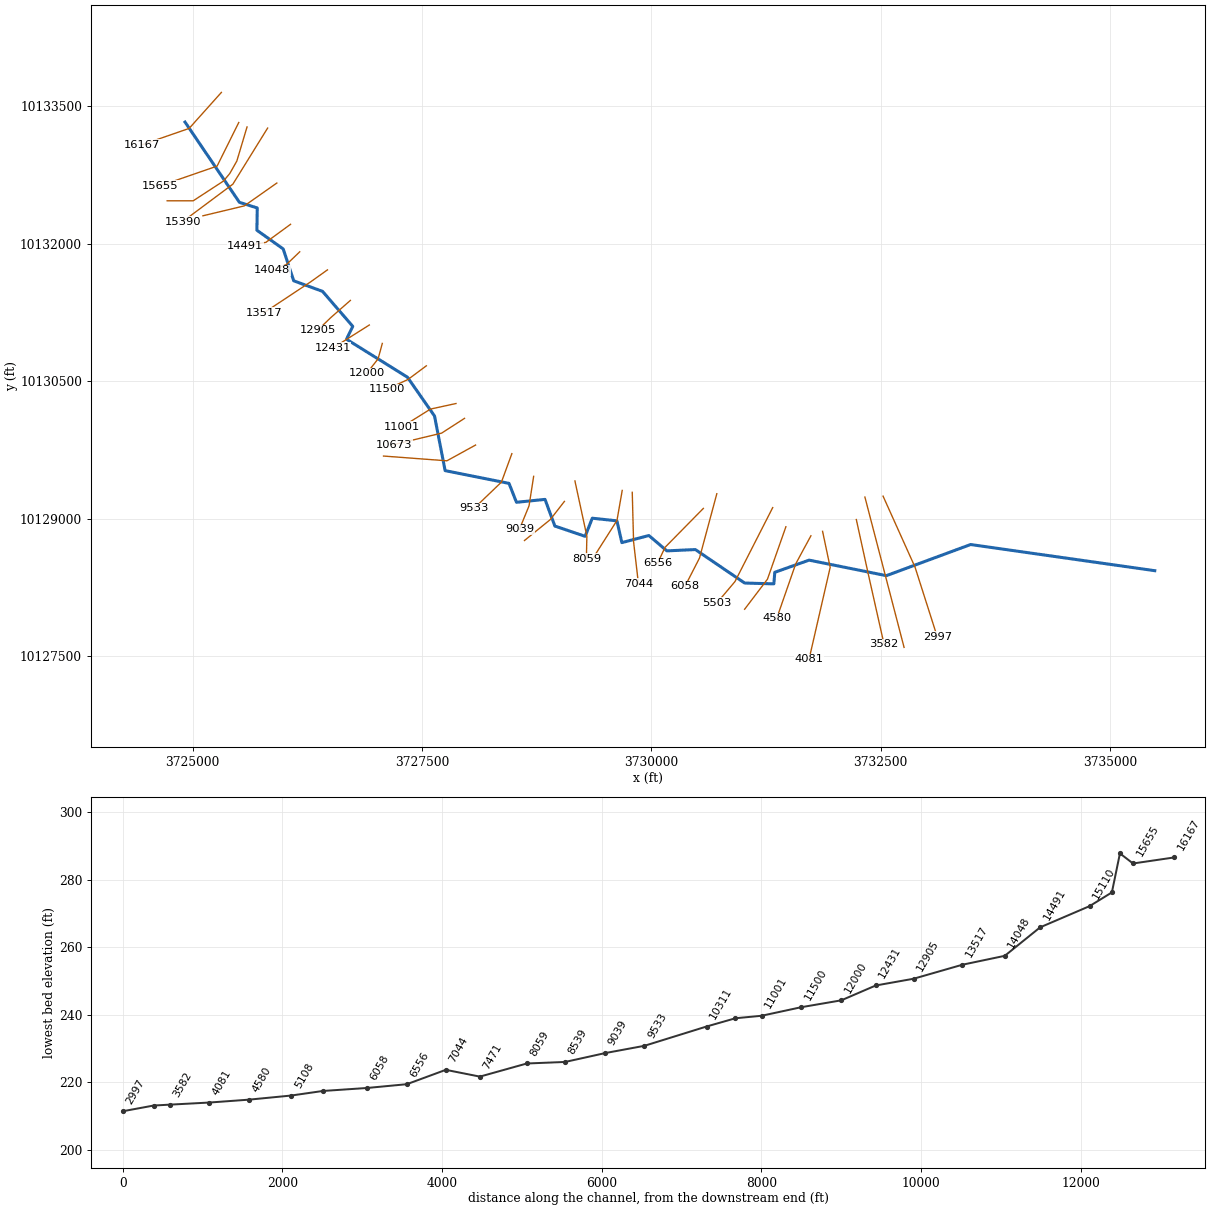
--- LAKE CREEK TRIBUTARY NO 7.prj (project) ---

Proj Title=LAKE CREEK TRIBUTARY NO 7 Base Level Engineering
Current Plan=p01
Default Exp/Contr=0.3,0.1
English Units
Geom File=g01
Flow File=f01
Plan File=p01
Y Axis Title=Elevation
X Axis Title(PF)=Main Channel Distance
X Axis Title(XS)=Station
BEGIN DESCRIPTION:
LAKE CREEK TRIBUTARY NO 7
END DESCRIPTION:
DSS Export Rating Curves= 0
DSS Export Rating Curve Sorted= 0
DSS Export Volume Flow Curves= 0
DXF OffsetX= 0
DXF OffsetY= 0
DXF ScaleX= 1
DXF ScaleY= 10

--- LAKE CREEK TRIBUTARY NO 7.p01 (plan) ---

Plan Title=Multiple Run
Short Identifier=Multiple
Geom File=g01
Flow File=f01
Subcritical Flow
K Sum by GR= 0
Std Step Tol= 0.01
Critical Tol= 0.01
Num of Std Step Trials= 20
Max Error Tol= 0.3
Flow Tol Ratio= 0.001
Split Flow NTrial= 30
Split Flow Tol= 0.02
Split Flow Ratio= 0.02
Log Output Level= 0
Friction Slope Method= 1
Unsteady Friction Slope Method= 2
Unsteady Bridges Friction Slope Method= 1
Parabolic Critical Depth
Global Vel Dist=  1 , 1 , 1
Global Log Level= 0
CheckData=True
Encroach Param= -1, 0, 0, 0
BEGIN DESCRIPTION:
Multiple Run
END DESCRIPTION:

--- LAKE CREEK TRIBUTARY NO 7.f01 (steady flow) ---

Flow Title=Multiple
Program Version=4.10
Number of Profiles= 7
Profile Names=10-year,25-year,50-year,1pct_min,100-year,1pct_plu,500-year
River Rch & RM=LAKE CREEK TRIBU,Reach-1         ,16167
     125     151     189      78     237     716     382
River Rch & RM=LAKE CREEK TRIBU,Reach-1         ,15491
     781    1074    1467     660    1992    6016    3793
River Rch & RM=LAKE CREEK TRIBU,Reach-1         ,7044
     780    1061    1436     638    1928    5822    3598
Boundary for River Rch & Prof#=LAKE CREEK TRIBU,Reach-1         , 1
Up Type= 0
Dn Type= 3
Dn Slope=0.005
Boundary for River Rch & Prof#=LAKE CREEK TRIBU,Reach-1         , 2
Up Type= 0
Dn Type= 3
Dn Slope=0.005
Boundary for River Rch & Prof#=LAKE CREEK TRIBU,Reach-1         , 3
Up Type= 0
Dn Type= 3
Dn Slope=0.005
Boundary for River Rch & Prof#=LAKE CREEK TRIBU,Reach-1         , 4
Up Type= 0
Dn Type= 3
Dn Slope=0.005
Boundary for River Rch & Prof#=LAKE CREEK TRIBU,Reach-1         , 5
Up Type= 0
Dn Type= 3
Dn Slope=0.005
Boundary for River Rch & Prof#=LAKE CREEK TRIBU,Reach-1         , 6
Up Type= 0
Dn Type= 3
Dn Slope=0.005
Boundary for River Rch & Prof#=LAKE CREEK TRIBU,Reach-1         , 7
Up Type= 0
Dn Type= 3
Dn Slope=0.005
DSS Import GetInterval= 0
DSS Import GetPeak= 0
DSS Import FillOption= 0

--- LAKE CREEK TRIBUTARY NO 7.g01 (geometry) ---

Geom Title=Existing Conditions
Program Version=4.10

River Reach=LAKE CREEK TRIBU,Reach-1
Reach XY= 30
      3724917.35     10133325.98      3725510.15     10132450.66
      3725704.56     10132389.28      3725700.84     10132146.06
      3725987.42     10131942.08      3726102.14     10131594.44
      3726416.29     10131479.25      3726745.83     10131097.45
      3726677.64     10130957.03      3727342.53     10130542.33
      3727637.49     10130118.52      3727752.77     10129523.39
      3728449.15     10129384.38      3728530.69     10129177.97
      3728841.79     10129209.67      3728949.02     10128918.87
       3729279.2     10128806.61      3729357.24     10129004.32
      3729625.77     10128975.53       3729679.7     10128738.11
      3729974.11      10128815.4      3730170.46     10128648.05
      3730480.91     10128662.24      3731018.31     10128296.97
      3731336.75      10128288.1      3731346.62      10128413.9
       3731720.6     10128546.95      3732563.11     10128377.46
      3733481.79     10128717.19       3735489.4     10128431.66

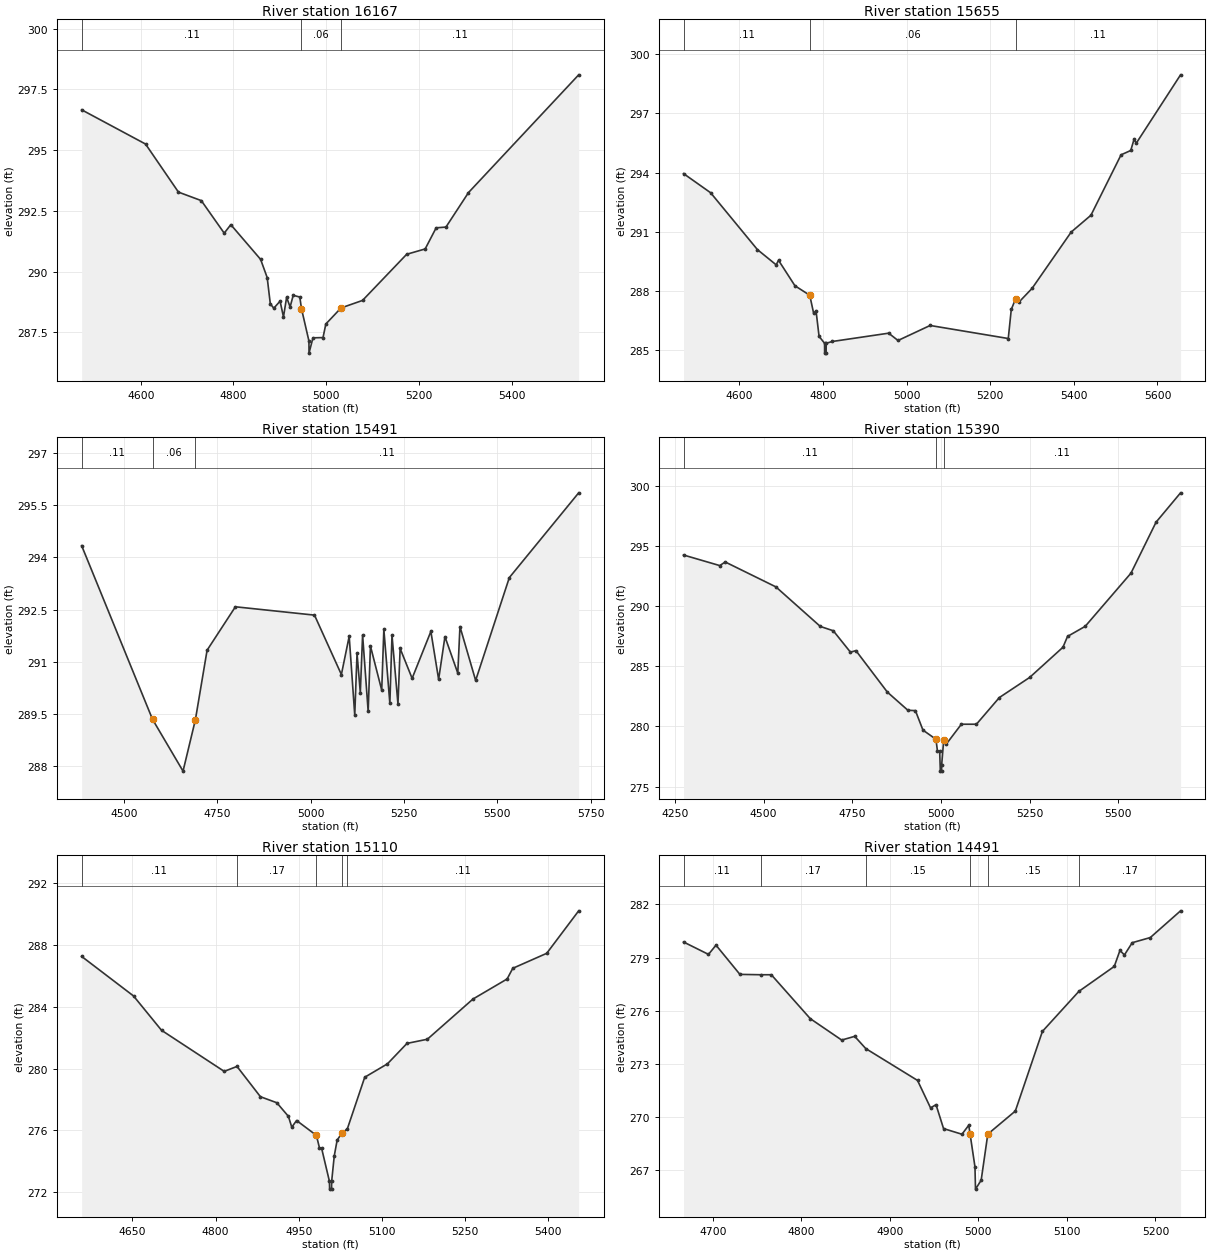
Type RM Length L Ch R = 1 ,16167   ,512,512,512
BEGIN DESCRIPTION:
LAKE CREEK TRIBUTARY NO. 7 32.0
END DESCRIPTION:
XS GIS Cut Line= 3
      3725313.66     10133649.94      3724961.91     10133256.98
      3724447.39     10133078.48
#Sta/Elev= 30
  4472.6  296.66  4610.4  295.25  4681.4  293.27  4730.7  292.92  4780.1  291.58
  4794.3  291.93  4858.6   290.5  4872.8  289.75  4879.5  288.67    4887  288.49
  4900.6  288.78  4907.9  288.13  4914.7  288.94  4922.2  288.54  4928.9  289.02
  4943.1  288.95 4946.69288.4762  4962.8  287.14    4963  286.64  4971.5  287.27
  4993.2  287.28  4999.3  287.84    5032   288.5  5078.4  288.81  5173.6  290.71
  5213.5  290.93  5237.2   291.8  5258.3  291.83  5306.9  293.25  5544.6   298.1
#Mann= 3 , 0 , 0
  4472.6     .11       0 4946.69     .06       0    5032     .11       0
Bank Sta=4946.69,5032
XS Rating Curve= 0 ,0
Exp/Cntr=0.3,0.1

Type RM Length L Ch R = 1 ,15655   ,164,164,164
BEGIN DESCRIPTION:
Mapping XS 7e0491d3
END DESCRIPTION:
XS GIS Cut Line= 3
      3725502.93      10133321.5      3725266.83     10132845.84
       3724645.3     10132630.55
#Sta/Elev= 30
  4466.5  293.95  4531.3  292.98  4643.3   290.1  4688.1  289.33  4693.7  289.56
    4733  288.27  4768.4  287.79  4777.8  286.87  4783.4  287.01  4790.7  285.71
  4803.8  285.36    4804  284.86  4807.5  284.86  4807.8  285.36  4822.6  285.45
  4957.1  285.87  4979.5   285.5  5056.3  286.26  5243.2   285.6  5250.4  287.07
    5261  287.62  5269.1  287.45  5300.2  288.14  5393.7  290.99  5440.9  291.84
    5513   294.9  5536.2  295.12  5544.1  295.69  5549.4  295.49  5655.3  298.95
#Mann= 3 , 0 , 0
  4466.5     .11       0  4768.4     .06       0    5261     .11       0
Bank Sta=4768.4,5261
XS Rating Curve= 0 ,0
Exp/Cntr=0.3,0.1

Type RM Length L Ch R = 1 ,15491   ,101,101,101
BEGIN DESCRIPTION:
Mapping XS 378b449c
END DESCRIPTION:
XS GIS Cut Line= 6
      3725593.22     10133272.89      3725482.11     10132901.39
      3725405.72     10132765.98      3725336.28     10132682.64
      3725006.42     10132467.36      3724722.31     10132467.34
#Sta/Elev= 30
  4386.9  294.34  4576.7  289.34  4658.4  287.85  4691.5  289.33  4722.8  291.33
  4798.6  292.58  5010.4  292.34  5082.4  290.63  5103.3  291.73  5118.2  289.46
  5124.3  291.24  5133.1  290.11  5139.2  291.77  5154.1  289.57  5160.2  291.45
  5190.4  290.18  5196.1  291.93  5212.2   289.8  5217.9  291.76  5233.9  289.78
  5239.7  291.38  5271.8  290.52    5322  291.87  5342.8  290.49  5359.7  291.72
  5394.1  290.67  5399.9  292.01  5441.9  290.46  5532.1  293.42  5717.8  295.86
#Mann= 3 , 0 , 0
  4386.9     .11       0  4576.7     .06       0  4691.5     .11       0
Bank Sta=4576.7,4691.5
XS Rating Curve= 0 ,0
Exp/Cntr=0.3,0.1

Type RM Length L Ch R = 1 ,15390   ,280,280,280
BEGIN DESCRIPTION:
LAKE CREEK TRIBUTARY NO. 7 31.0
END DESCRIPTION:
XS GIS Cut Line= 3
      3725817.83     10133261.03      3725438.71     10132648.79
      3724892.33     10132241.17
#Sta/Elev= 30
  4274.1  294.25  4376.3  293.37  4391.7  293.67  4534.6   291.6  4659.9  288.31
  4696.5  287.95  4744.9  286.17  4760.3   286.3    4849  282.85  4906.9  281.34
  4928.1  281.31  4949.4  279.69    4986  278.93  4990.3  277.94  4996.5  277.94
  4998.4  276.28  5001.9  276.28  5002.1  276.78  5007.8  278.83  5014.7  278.51
  5057.7  280.18  5100.2  280.18  5164.9   282.4  5250.3  284.07  5344.2  286.58
  5357.1  287.48    5407  288.32    5536  292.74  5606.8  296.98  5675.9  299.42
#Mann= 3 , 0 , 0
  4274.1     .11       0    4986     .06       0  5007.8     .11       0
Bank Sta=4986,5007.8
XS Rating Curve= 0 ,0
Exp/Cntr=0.3,0.1

Type RM Length L Ch R = 1 ,15110   ,619,619,619
BEGIN DESCRIPTION:
LAKE CREEK TRIBUTARY NO. 7 30.0
END DESCRIPTION:
XS GIS Cut Line= 3
      3725917.87     10132661.09      3725563.71     10132411.81
      3725112.16     10132303.72
#Sta/Elev= 30
  4558.2  287.26  4651.9   284.7  4702.4  282.48  4815.6  279.82  4838.7  280.14
    4881  278.18  4910.6  277.79  4931.5  276.91  4937.6  276.21  4946.3  276.64
    4982  275.68  4987.6  274.87  4991.3  274.87  5005.6   272.7  5005.9   272.2
  5009.4   272.2  5009.6   272.7  5014.3  274.35  5019.5  275.37  5028.2  275.83
  5037.9   276.1  5069.3  279.44  5110.4  280.31  5145.6  281.63  5182.4   281.9
  5264.7   284.5  5326.4   285.8  5336.6  286.49  5397.9  287.46  5455.6  290.21
#Mann= 5 ,-1 , 0
  4558.2     .11       0  4838.7     .17       0    4982     .09       0
  5028.2     .17       0  5037.9     .11       0
Bank Sta=4982,5028.2
XS Rating Curve= 0 ,0
Exp/Cntr=0.3,0.1

Type RM Length L Ch R = 1 ,14491   ,443,443,443
BEGIN DESCRIPTION:
LAKE CREEK TRIBUTARY NO. 7 29.0
END DESCRIPTION:
XS GIS Cut Line= 3
      3726067.86     10132211.08      3725799.02     10132014.24
      3725574.14     10131974.31
#Sta/Elev= 30
  4666.8  279.88    4695  279.18  4703.5   279.7  4730.5  278.05  4753.8  278.03
    4766  278.03    4810  275.55  4845.5  274.34  4860.2  274.55  4872.7  273.86
  4931.2  272.06  4945.9  270.51  4952.1  270.69  4960.6  269.34  4981.4  269.02
  4989.1  269.53  4990.6269.0264  4996.1  267.18  4996.7  265.92  5003.1  266.42
  5010.6269.0268  5041.7  270.33  5072.3  274.83  5113.5  277.09  5153.5   278.5
  5159.9   279.4    5165  279.15  5173.8  279.84  5194.2  280.13  5228.4  281.64
#Mann= 6 ,-1 , 0
  4666.8     .11       0  4753.8     .17       0  4872.7     .15       0
  4990.6     .09       0  5010.6     .15       0  5113.5     .17       0
Bank Sta=4990.6,5010.6
XS Rating Curve= 0 ,0
Exp/Cntr=0.3,0.1

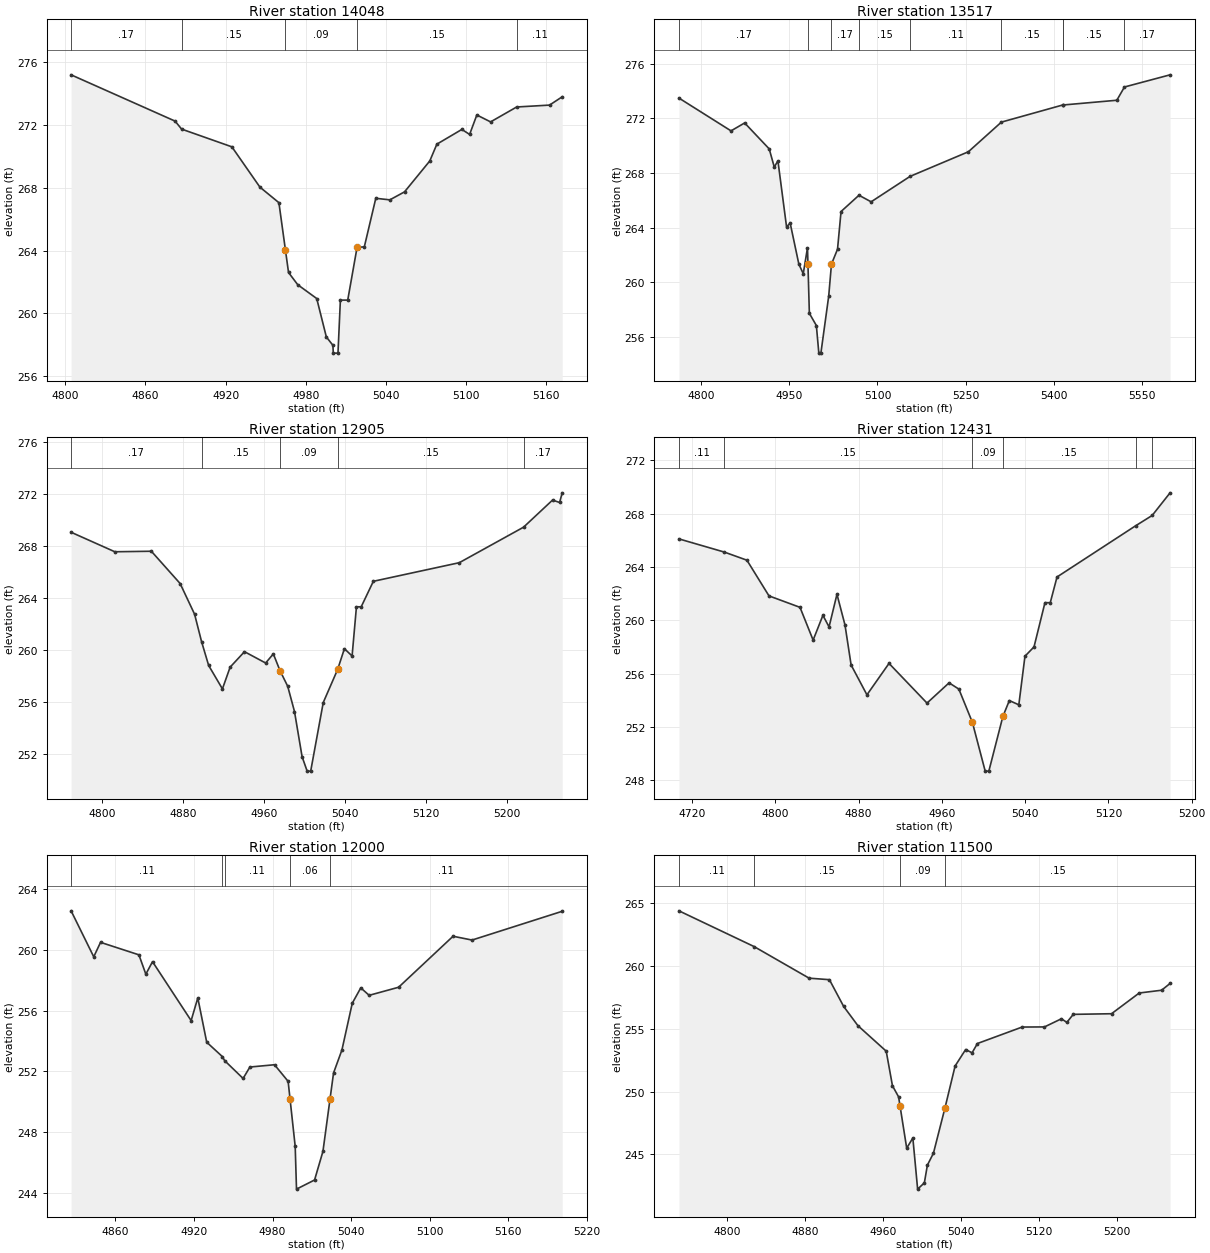
Type RM Length L Ch R = 1 ,14048   ,531,531,531
BEGIN DESCRIPTION:
LAKE CREEK TRIBUTARY NO. 7 28.0
END DESCRIPTION:
XS GIS Cut Line= 3
      3726167.83     10131911.05      3726022.04     10131771.18
      3725867.88     10131711.08
#Sta/Elev= 30
  4804.4  275.21  4882.2  272.26  4887.1  271.75  4924.7  270.62  4945.7  268.05
  4959.9  267.06  4964.8264.0316  4967.1  262.61    4974  261.83  4988.2  260.95
  4995.4   258.5  5000.3  257.97  5000.6  257.47  5004.1  257.47  5005.9  260.85
  5011.4  260.85  5018.4  264.22  5023.8  264.24  5032.4  267.34  5042.9  267.24
  5053.9  267.75  5072.8  269.72  5078.1  270.79  5096.8  271.73  5102.6  271.41
    5108  272.65  5118.3  272.21  5137.8  273.16  5162.4  273.28  5171.9  273.81
#Mann= 5 ,-1 , 0
  4804.4     .17       0  4887.1     .15       0  4964.8     .09       0
  5018.4     .15       0  5137.8     .11       0
Bank Sta=4964.8,5018.4
XS Rating Curve= 0 ,0
Exp/Cntr=0.3,0.1

Type RM Length L Ch R = 1 ,13517   ,612,612,612
BEGIN DESCRIPTION:
LAKE CREEK TRIBUTARY NO. 7 27.0
END DESCRIPTION:
XS GIS Cut Line= 3
      3726469.93     10131713.87      3726287.67     10131583.68
      3725777.97     10131245.62
#Sta/Elev= 30
  4762.2  273.49  4850.8  271.09    4874  271.67  4915.8  269.77  4924.4  268.44
  4930.6   268.9  4945.3  264.06  4951.4  264.35  4966.2  261.34  4973.7  260.64
  4980.9  262.54  4981.7261.3396  4984.1  257.74    4996  256.85  5000.2  254.83
  5003.7  254.83    5017     259  5021.7261.3423    5032  262.43    5038  265.19
  5068.5  266.38  5089.2   265.9  5155.4  267.76  5254.6  269.56  5310.8  271.73
  5414.9  272.98    5415  272.98  5507.2  273.33  5520.2   274.3  5597.8  275.19
#Mann= 9 ,-1 , 0
  4762.2     .17       0  4981.7     .09       0  5021.7     .17       0
  5068.5     .15       0  5155.4     .11       0  5310.8     .15       0
  5414.9     .17       0    5415     .15       0  5520.2     .17       0
Bank Sta=4981.7,5021.7
XS Rating Curve= 0 ,0
Exp/Cntr=0.3,0.1

Type RM Length L Ch R = 1 ,12905   ,474,474,474
BEGIN DESCRIPTION:
LAKE CREEK TRIBUTARY NO. 7 26.0
END DESCRIPTION:
XS GIS Cut Line= 3
      3726719.95     10131380.55      3726506.42     10131193.06
       3726361.7     10131053.51
#Sta/Elev= 30
  4769.7  269.03  4812.9  267.53    4849  267.57  4877.4  265.09  4891.7  262.73
  4898.6  260.62  4905.6  258.79  4919.2  256.99  4926.8  258.66    4941  259.85
  4961.9  258.98  4969.5  259.68  4976.1  258.39  4983.7  257.19  4990.4  255.25
  4997.9  251.78  5002.9  250.67  5006.4  250.67  5018.8  255.94  5033.1   258.5
  5039.7  260.08  5047.3  259.52  5051.6   263.3  5056.3   263.3  5068.3  265.26
  5153.2  266.69  5216.7  269.42  5245.3   271.5  5252.3  271.32  5254.9  272.06
#Mann= 5 ,-1 , 0
  4769.7     .17       0  4898.6     .15       0  4976.1     .09       0
  5033.1     .15       0  5216.7     .17       0
Bank Sta=4976.1,5033.1
XS Rating Curve= 0 ,0
Exp/Cntr=0.3,0.1

Type RM Length L Ch R = 1 ,12431   ,431,431,431
BEGIN DESCRIPTION:
LAKE CREEK TRIBUTARY NO. 7 25.0
END DESCRIPTION:
XS GIS Cut Line= 3
      3726926.22     10131112.13      3726626.29     10130922.71
      3726526.14     10130862.09
#Sta/Elev= 30
  4707.4  266.11    4751  265.12  4772.7  264.51  4793.9  261.83  4823.7  260.97
  4836.3  258.51  4845.7  260.37  4851.6   259.5  4859.2  261.95  4866.9  259.65
  4872.8  256.64    4888   254.4  4909.2  256.76  4945.7  253.78  4966.9   255.3
  4976.3  254.83  4989.3  252.33  5001.6  248.67  5005.1  248.67  5018.6  252.78
  5024.8  253.97  5033.9  253.65  5039.8   257.3  5048.5     258    5059  261.32
  5064.1  261.32  5070.6  263.25    5146  267.09    5162  267.87  5179.2  269.57
#Mann= 6 ,-1 , 0
  4707.4     .11       0    4751     .15       0  4989.3     .09       0
  5018.6     .15       0    5146     .17       0    5162     .15       0
Bank Sta=4989.3,5018.6
XS Rating Curve= 0 ,0
Exp/Cntr=0.3,0.1

Type RM Length L Ch R = 1 ,12000   ,500,500,500
BEGIN DESCRIPTION:
LAKE CREEK TRIBUTARY NO. 7 24.0
END DESCRIPTION:
XS GIS Cut Line= 3
      3727067.85     10130911.07       3727022.2     10130743.27
      3726897.97     10130584.87
#Sta/Elev= 30
  4826.1  262.55  4843.4  259.53  4848.6  260.48  4877.9  259.66  4883.2  258.39
  4888.3  259.21  4917.8  255.34  4922.9  256.83  4929.7  253.92  4941.6  252.98
  4943.4  252.71  4957.5  251.54  4962.7  252.29  4981.5  252.44  4991.9  251.35
 4993.34250.2114  4997.3  247.08  4998.3  244.27  5012.1  244.87  5018.5  246.75
  5023.9250.1832  5026.6   251.9    5033  253.41  5040.9  256.48  5047.4  257.49
  5053.8     257  5076.3  257.53  5117.9  260.88  5132.4  260.63  5201.3  262.52
#Mann= 5 ,-1 , 0
  4826.1     .11       0  4941.6     .15       0  4943.4     .11       0
 4993.34     .06       0  5023.9     .11       0
Bank Sta=4993.34,5023.9
XS Rating Curve= 0 ,0
Exp/Cntr=0.3,0.1

Type RM Length L Ch R = 1 ,11500   ,499,499,499
BEGIN DESCRIPTION:
LAKE CREEK TRIBUTARY NO. 7 23.0
END DESCRIPTION:
XS GIS Cut Line= 3
      3727548.11     10130667.04      3727348.43     10130518.11
      3727117.87     10130411.08
#Sta/Elev= 30
  4750.9  264.39  4827.8  261.55  4884.3  259.03  4905.1  258.91  4919.7  256.78
  4934.3  255.25  4963.3  253.22  4969.7  250.47    4976  249.58  4977.5248.8426
  4984.3   245.5  4990.6  246.31  4995.5  242.24  5002.4  242.74  5005.5  244.15
  5011.7   245.1  5023.6248.7271  5033.9  252.04  5044.7  253.35  5051.3  253.09
  5056.8  253.83  5102.6  255.14  5125.5  255.15  5142.9   255.8  5148.4  255.51
    5155  256.15  5194.2   256.2  5222.6  257.85  5245.5  258.07  5254.2  258.61
#Mann= 4 ,-1 , 0
  4750.9     .11       0  4827.8     .15       0  4977.5     .09       0
  5023.6     .15       0
Bank Sta=4977.5,5023.6
XS Rating Curve= 0 ,0
Exp/Cntr=0.3,0.1

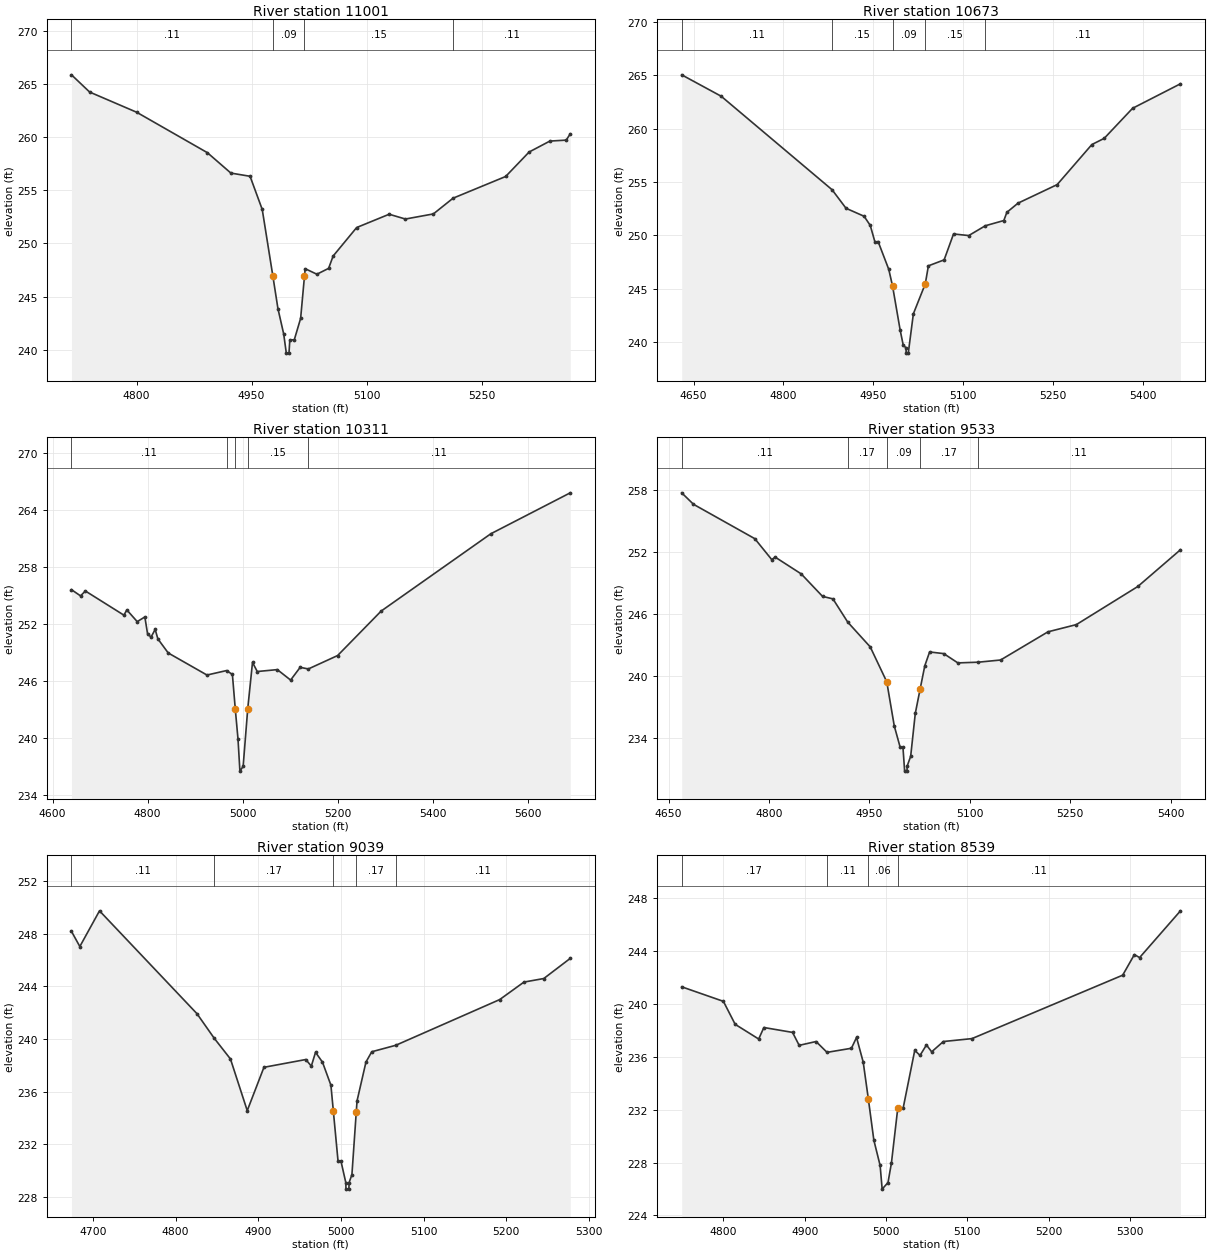
Type RM Length L Ch R = 1 ,11001   ,328,328,328
BEGIN DESCRIPTION:
LAKE CREEK TRIBUTARY NO. 7 22.0
END DESCRIPTION:
XS GIS Cut Line= 3
      3727871.04     10130255.57      3727592.58     10130194.86
      3727282.69     10130000.49
#Sta/Elev= 30
    4715  265.86  4738.7  264.24  4800.1  262.34  4892.3  258.54    4923  256.62
    4948  256.32  4963.9   253.2  4977.8246.9202  4984.4  243.87  4991.9  241.49
  4995.3  239.69  4998.8  239.69  4999.9  240.94  5005.7  240.94    5014  242.96
    5019246.9177  5019.9  247.63  5035.2  247.11  5050.5  247.66  5056.4  248.82
  5087.1   251.5  5129.5  252.75  5150.7   252.3  5187.2  252.78  5212.9  254.26
  5281.5   256.3  5312.1   258.6  5339.2  259.63  5360.5  259.72  5365.8  260.31
#Mann= 4 ,-1 , 0
    4715     .11       0  4977.8     .09       0    5019     .15       0
  5212.9     .11       0
Bank Sta=4977.8,5019
XS Rating Curve= 0 ,0
Exp/Cntr=0.3,0.1

Type RM Length L Ch R = 1 ,10673   ,362,362,362
BEGIN DESCRIPTION:
LAKE CREEK TRIBUTARY NO. 7 21.0
END DESCRIPTION:
XS GIS Cut Line= 3
      3727964.77     10130094.11      3727714.75     10129932.64
      3727193.97     10129807.65
#Sta/Elev= 30
  4630.1  265.06  4696.1  263.05  4881.3  254.28  4904.6  252.54  4934.8  251.79
  4945.1  250.93  4953.1  249.34  4958.2  249.42    4976  246.81  4982.4245.2226
  4995.1  241.09  5000.2  239.69  5004.8  239.45  5005.1  238.95  5008.6  238.95
  5017.1  242.64    5037  245.45  5042.2  247.14  5068.5   247.7  5084.2  250.13
  5109.6  249.98  5137.3   250.9  5168.2  251.39  5173.3  252.16  5191.9  253.02
  5257.3  254.76  5315.3  258.52  5335.9   259.1  5383.3  261.92  5463.3  264.22
#Mann= 5 ,-1 , 0
  4630.1     .11       0  4881.3     .15       0  4982.4     .09       0
    5037     .15       0  5137.3     .11       0
Bank Sta=4982.4,5037
XS Rating Curve= 0 ,0
Exp/Cntr=0.3,0.1

Type RM Length L Ch R = 1 ,10311   ,778,778,778
BEGIN DESCRIPTION:
LAKE CREEK TRIBUTARY NO. 7 20.0
END DESCRIPTION:
XS GIS Cut Line= 3
      3728084.52     10129802.42      3727772.04     10129630.56
      3727081.12     10129682.51
#Sta/Elev= 30
  4639.7  255.59  4658.7  254.94    4669  255.45    4750  252.91  4756.2  253.46
    4778  252.23  4794.1  252.72  4799.8  250.94  4807.1   250.6  4815.8  251.41
  4821.5  250.41  4843.3  248.93  4924.8  246.61    4966  247.08  4978.3  246.67
  4984.4  243.01  4990.1  239.87  4994.1   236.5  5000.9     237  5010.6  243.08
  5020.6  247.94  5030.6  246.98  5072.8  247.18  5100.8  246.08  5120.9  247.42
  5138.1  247.25  5199.7  248.66  5291.3  253.34    5522  261.47  5689.2  265.78
#Mann= 5 ,-1 , 0
  4639.7     .11       0    4966     .15       0  4984.4     .09       0
  5010.6     .15       0  5138.1     .11       0
Bank Sta=4984.4,5010.6
XS Rating Curve= 0 ,0
Exp/Cntr=0.3,0.1

Type RM Length L Ch R = 1 ,9533    ,494,494,494
BEGIN DESCRIPTION:
LAKE CREEK TRIBUTARY NO. 7 19.0
END DESCRIPTION:
XS GIS Cut Line= 3
      3728480.37     10129708.66      3728366.72     10129398.31
      3728067.87     10129111.09
#Sta/Elev= 30
  4669.5  257.73  4687.1  256.62  4778.7  253.29  4803.9  251.27  4809.2   251.5
    4848  249.88  4879.9   247.7  4895.4  247.46  4917.5  245.21  4951.1  242.81
  4975.8  239.43    4987  235.16  4995.9  233.07    5000  233.07  5002.5  230.78
    5006  230.78  5006.3  231.28  5011.5  232.21  5018.4  236.37  5025.7  238.75
  5032.6  240.98  5039.8  242.32  5060.9  242.16    5082  241.26  5112.6  241.33
  5145.8  241.54  5216.6  244.27    5259  244.97  5350.8  248.66  5414.5  252.22
#Mann= 5 ,-1 , 0
  4669.5     .11       0  4917.5     .17       0  4975.8     .09       0
  5025.7     .17       0  5112.6     .11       0
Bank Sta=4975.8,5025.7
XS Rating Curve= 0 ,0
Exp/Cntr=0.3,0.1

Type RM Length L Ch R = 1 ,9039    ,500,500,500
BEGIN DESCRIPTION:
LAKE CREEK TRIBUTARY NO. 7 18.0
END DESCRIPTION:
XS GIS Cut Line= 3
      3728717.85     10129461.08      3728667.58     10129139.08
       3728562.4      10128882.4
#Sta/Elev= 30
  4674.1  248.18  4684.2  247.03    4708  249.74  4825.9  241.93  4846.7  240.07
  4866.4  238.49  4886.7  234.57  4906.9  237.86  4957.5  238.45  4964.2  237.95
  4969.3     239  4977.7  238.25  4987.9   236.5 4990.84234.5344  4996.5  230.75
    5000  230.75  5005.9  229.11  5006.1  228.61  5009.6  228.61  5009.9  229.11
  5013.3  229.71  5018.6234.4972  5019.5  235.31  5030.3  238.26  5037.3  239.04
  5066.3  239.53    5192     243  5221.4  244.33  5245.4   244.6  5277.4  246.13
#Mann= 5 ,-1 , 0
  4674.1     .11       0  4846.7     .17       0 4990.84     .09       0
  5018.6     .17       0  5066.3     .11       0
Bank Sta=4990.84,5018.6
XS Rating Curve= 0 ,0
Exp/Cntr=0.3,0.1

Type RM Length L Ch R = 1 ,8539    ,480,480,480
BEGIN DESCRIPTION:
LAKE CREEK TRIBUTARY NO. 7 17.0
END DESCRIPTION:
XS GIS Cut Line= 3
      3729053.29     10129187.85      3728899.29     10128989.26
      3728617.87     10128761.09
#Sta/Elev= 30
  4748.7   241.3    4800   240.2  4814.5  238.46  4843.4  237.35  4849.8  238.22
  4885.1  237.85  4893.2  236.87    4914  237.16  4927.5  236.34  4957.5  236.65
  4963.8  237.47    4972   235.6  4978.3  232.82  4985.1  229.69  4992.8  227.78
  4995.3  225.99  5002.5  226.49  5006.7  227.96  5014.6  232.16  5021.1  232.11
  5035.4  236.49  5041.9  236.11  5049.8   236.9  5056.2  236.38  5070.6  237.16
  5105.8  237.38  5291.2  242.18  5305.6  243.74    5312  243.51  5362.3  247.05
#Mann= 4 ,-1 , 0
  4748.7     .17       0  4927.5     .11       0  4978.3     .06       0
  5014.6     .11       0
Bank Sta=4978.3,5014.6
XS Rating Curve= 0 ,0
Exp/Cntr=0.3,0.1

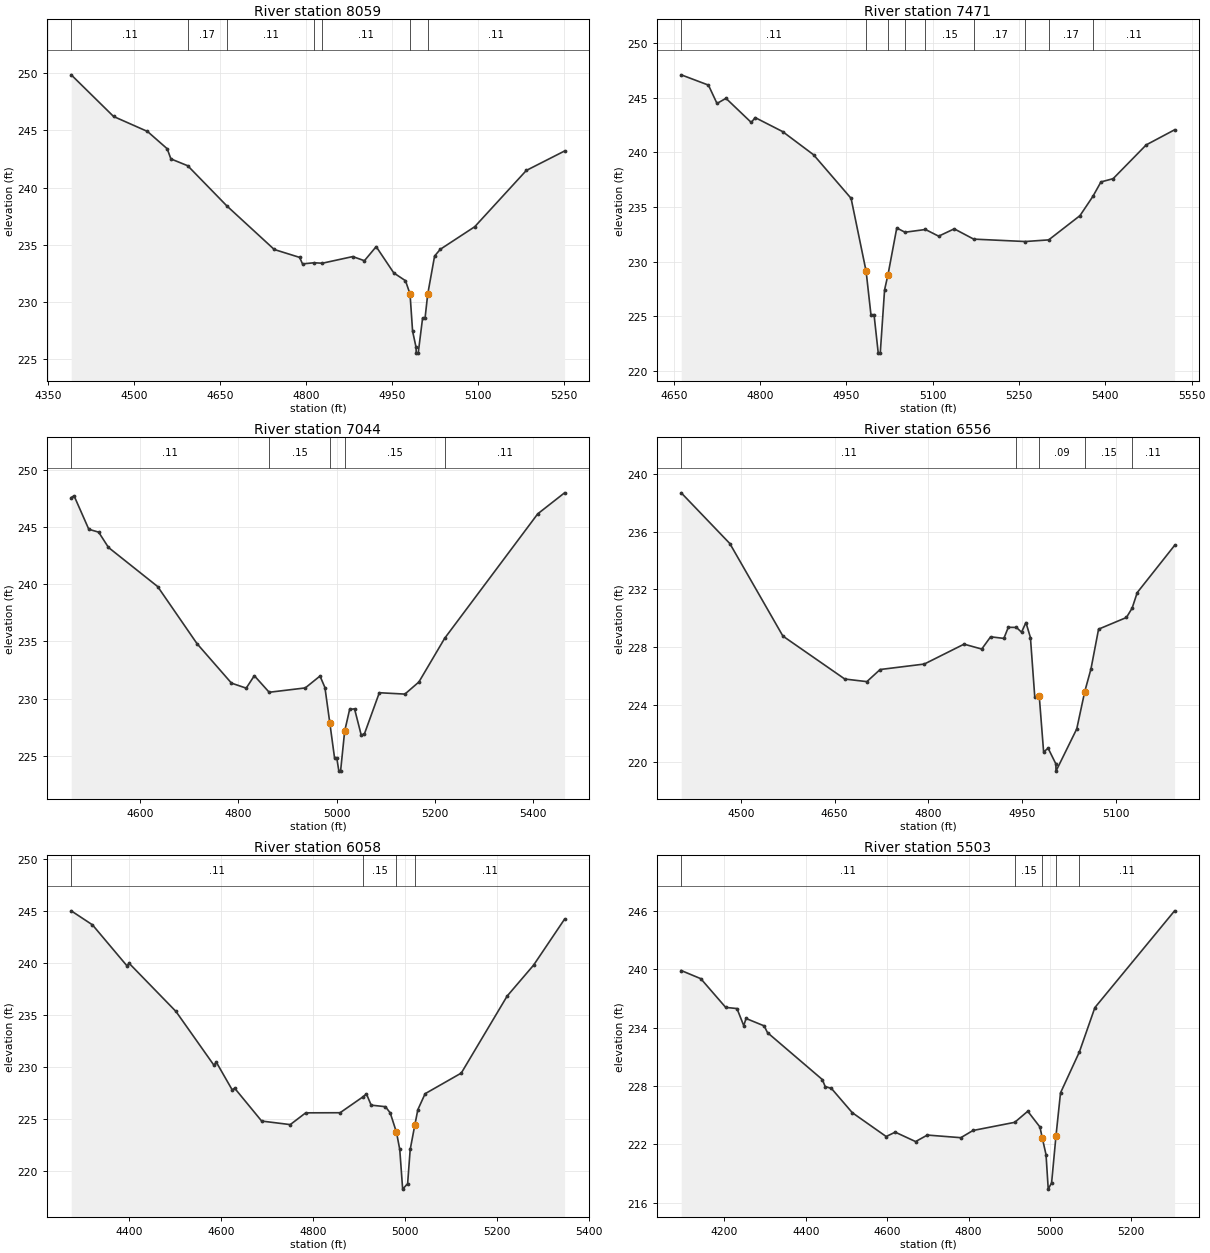
Type RM Length L Ch R = 1 ,8059    ,588,588,588
BEGIN DESCRIPTION:
LAKE CREEK TRIBUTARY NO. 7 16.0
END DESCRIPTION:
XS GIS Cut Line= 3
      3729167.85     10129411.07      3729298.08     10128807.64
      3729292.91     10128564.42
#Sta/Elev= 30
    4390  249.86  4463.9  246.22    4523  244.91  4557.4   243.4  4563.9  242.51
  4593.3  241.91  4661.5   238.4  4744.2  234.59  4788.4   233.9  4793.5  233.33
  4813.6  233.43    4828  233.39  4881.1  233.97  4901.5  233.61    4922  234.84
  4952.7  232.54  4973.1  231.86 4981.06230.6972  4985.5  227.45  4991.6  226.03
  4991.8  225.53  4995.3  225.53    5003  228.61  5007.3  228.61 5011.85230.6714
  5023.9  234.02  5033.9  234.61  5093.9  236.58  5183.9   241.5  5250.6   243.2
#Mann= 7 ,-1 , 0
    4390     .11       0  4593.3     .17       0  4661.5     .11       0
  4813.6     .15       0    4828     .11       0 4981.06     .06       0
 5011.85     .11       0
Bank Sta=4981.06,5011.85
XS Rating Curve= 0 ,0
Exp/Cntr=0.3,0.1

Type RM Length L Ch R = 1 ,7471    ,427,427,427
BEGIN DESCRIPTION:
LAKE CREEK TRIBUTARY NO. 7 15.0
END DESCRIPTION:
XS GIS Cut Line= 3
      3729683.51     10129307.67      3729626.21     10128979.52
      3729344.96     10128536.81
#Sta/Elev= 30
  4662.7   247.1    4710  246.16  4724.9  244.48  4740.5  244.95  4784.5  242.74
  4791.2  243.19  4838.9  241.91  4892.7  239.79    4958   235.8  4984.1  229.13
  4992.5  225.16  4997.9  225.16  5005.2  221.64  5008.7  221.64  5016.2  227.43
  5022.2  228.83  5037.4  233.09  5051.7   232.7  5087.3  232.95  5110.2  232.34
  5137.3  233.01  5171.1  232.07  5260.7  231.85  5301.5     232  5355.9  234.22
  5378.3  235.98  5392.3   237.3  5413.5   237.6    5471  240.69  5520.3  242.07
#Mann= 9 ,-1 , 0
  4662.7     .11       0  4984.1     .06       0  5022.2     .11       0
  5051.7     .17       0  5087.3     .15       0  5171.1     .17       0
  5260.7     .11       0  5301.5     .17       0  5378.3     .11       0
Bank Sta=4984.1,5022.2
XS Rating Curve= 0 ,0
Exp/Cntr=0.3,0.1

Type RM Length L Ch R = 1 ,7044    ,488,488,488
BEGIN DESCRIPTION:
LAKE CREEK TRIBUTARY NO. 7 14.0
END DESCRIPTION:
XS GIS Cut Line= 3
      3729792.88     10129286.86      3729807.29     10128747.05
      3729860.58     10128286.82
#Sta/Elev= 30
    4460  247.59  4465.8  247.74  4495.8  244.81  4515.8  244.56  4535.8  243.22
  4635.8   239.8  4715.9   234.8  4785.9  231.35  4815.9  230.91  4832.4     232
  4862.6  230.55    4936  230.93    4966  231.97    4976  230.96    4986  227.84
  4995.5  224.82    5000  224.82  5004.3  223.65  5007.8  223.65  5016.1  227.14
  5026.2  229.05  5036.2   229.1  5049.8   226.8  5056.4  226.92  5086.6  230.51
  5138.6  230.39  5167.1  231.45  5219.6  235.28  5408.7  246.16  5463.3     248
#Mann= 5 ,-1 , 0
    4460     .11       0  4862.6     .15       0    4986     .09       0
  5016.1     .15       0  5219.6     .11       0
Bank Sta=4986,5016.1
XS Rating Curve= 0 ,0
Exp/Cntr=0.3,0.1

Type RM Length L Ch R = 1 ,6556    ,498,498,498
BEGIN DESCRIPTION:
LAKE CREEK TRIBUTARY NO. 7 13.0
END DESCRIPTION:
XS GIS Cut Line= 3
      3730567.85     10129111.07      3730150.45     10128686.62
      3730067.86     10128511.08
#Sta/Elev= 30
  4404.7   238.7  4482.5  235.18  4567.4  228.76  4666.4  225.78  4701.7   225.6
  4722.9  226.44  4793.6  226.82  4857.2   228.2  4885.5  227.86  4899.7  228.71
  4920.9   228.6    4928  229.37    4941  229.36  4949.2  229.03  4956.2   229.7
  4963.4  228.66  4970.4   224.5  4977.5   224.6  4984.5  220.72  4991.7  220.98
  5004.1  219.89  5004.3  219.39  5037.5  222.32  5050.3  224.91  5060.3  226.49
  5072.4  229.24    5117  230.05  5126.1   230.7  5134.3  231.78    5194  235.05
#Mann= 5 ,-1 , 0
  4404.7     .11       0    4941     .15       0  4977.5     .09       0
  5050.3     .15       0  5126.1     .11       0
Bank Sta=4977.5,5050.3
XS Rating Curve= 0 ,0
Exp/Cntr=0.3,0.1

Type RM Length L Ch R = 1 ,6058    ,555,555,555
BEGIN DESCRIPTION:
LAKE CREEK TRIBUTARY NO. 7 12.0
END DESCRIPTION:
XS GIS Cut Line= 3
      3730714.75     10129271.18      3730526.13     10128570.32
      3730367.85     10128261.07
#Sta/Elev= 30
  4274.2  245.01  4320.5  243.66  4395.2  239.74  4400.4  239.96  4502.1  235.34
  4584.6  230.18  4589.8  230.47  4624.5   227.8  4629.7  227.97  4688.5  224.81
  4750.7  224.47  4784.3   225.6  4859.1  225.61  4908.3  227.12  4916.4  227.42
  4926.7  226.34  4957.8  226.19  4968.2  225.59  4981.8  223.72  4988.9  222.08
  4995.2  218.27    5006  218.79  5011.6  222.08  5021.6  224.41  5028.2   225.9
  5044.1  227.44  5122.7  229.42  5222.5  236.82    5280  239.79  5347.4  244.21
#Mann= 4 ,-1 , 0
  4274.2     .11       0  4908.3     .15       0  4981.8     .06       0
  5021.6     .11       0
Bank Sta=4981.8,5021.6
XS Rating Curve= 0 ,0
Exp/Cntr=0.3,0.1

Type RM Length L Ch R = 1 ,5503    ,395,395,395
BEGIN DESCRIPTION:
LAKE CREEK TRIBUTARY NO. 7 11.0
END DESCRIPTION:
XS GIS Cut Line= 3
      3731324.14     10129120.16      3730912.67     10128312.85
      3730714.74     10128078.47
#Sta/Elev= 30
  4093.6  239.86  4141.8  239.02  4202.9  236.07  4230.7  235.95  4247.3  234.19
    4253  234.93  4297.4  234.17  4305.8  233.47  4440.5  228.65  4447.5  227.93
    4463  227.73  4514.2  225.24  4597.5  222.79  4619.7  223.24  4669.8  222.27
  4698.7  222.94    4781  222.67  4810.9  223.41  4913.5  224.25  4945.6  225.39
  4975.5  223.77  4981.1  222.68  4990.5  220.92  4995.9  217.38  5004.2  218.03
 5014.92222.8353  5026.1  227.28  5072.5  231.49  5110.6  236.05  5306.5     246
#Mann= 5 ,-1 , 0
  4093.6     .11       0  4913.5     .15       0  4981.1     .09       0
 5014.92     .15       0  5072.5     .11       0
Bank Sta=4981.1,5014.92
XS Rating Curve= 0 ,0
Exp/Cntr=0.3,0.1

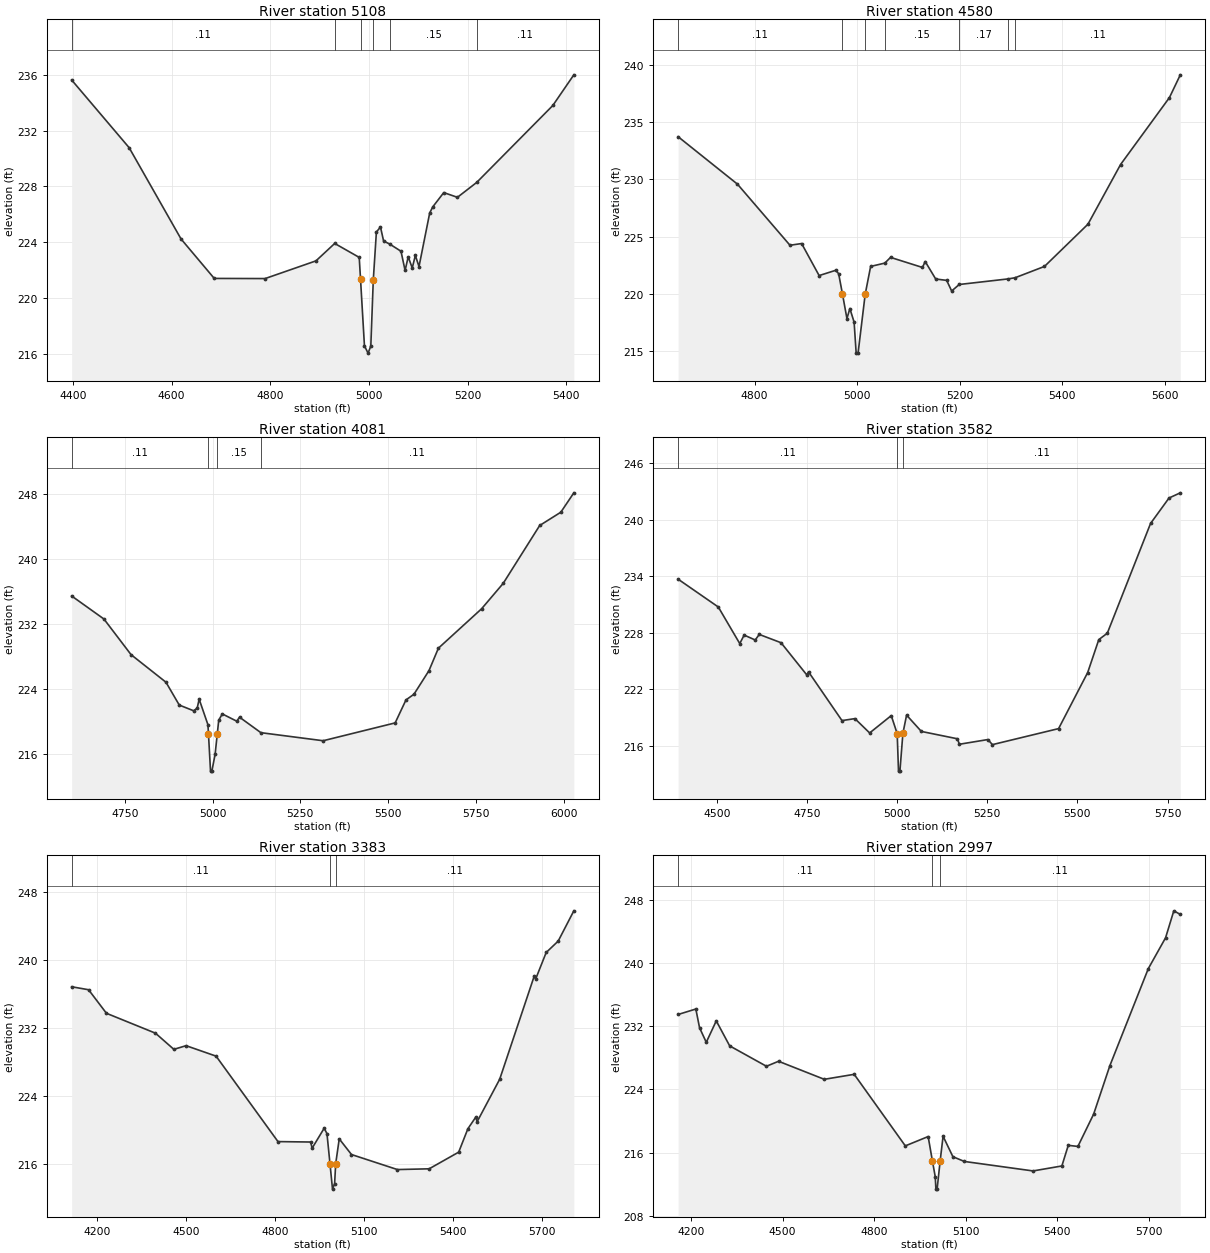
Type RM Length L Ch R = 1 ,5108    ,528,528,528
BEGIN DESCRIPTION:
LAKE CREEK TRIBUTARY NO. 7 10.0
END DESCRIPTION:
XS GIS Cut Line= 3
      3731467.86     10128911.09      3731266.83     10128338.89
      3731017.87      10128011.1
#Sta/Elev= 30
  4397.3  235.63  4513.9  230.77  4619.1  224.22  4686.4  221.39  4789.5  221.38
  4892.6  222.65  4930.6   223.9  4980.3   222.9 4982.99221.3163  4990.9  216.55
  4998.2  216.03  5003.8  216.53  5008.8  221.27  5015.1  224.72  5023.4  225.08
  5029.7  224.08  5042.8  223.84    5065  223.34  5073.3  221.96  5079.6  222.94
  5087.8  222.14  5094.1  223.04  5101.5  222.24  5123.2  226.09  5129.5  226.53
  5151.7  227.55  5179.4  227.21  5218.5  228.28  5372.8   233.8  5415.4     236
#Mann= 6 ,-1 , 0
  4397.3     .11       0  4930.6     .17       0 4982.99     .09       0
  5008.8     .17       0  5042.8     .15       0  5218.5     .11       0
Bank Sta=4982.99,5008.8
XS Rating Curve= 0 ,0
Exp/Cntr=0.3,0.1

Type RM Length L Ch R = 1 ,4580    ,499,499,499
BEGIN DESCRIPTION:
LAKE CREEK TRIBUTARY NO. 7 9.0
END DESCRIPTION:
XS GIS Cut Line= 3
      3731740.77     10128812.81      3731574.79     10128505.92
      3731367.86     10127911.09
#Sta/Elev= 30
  4651.1  233.73  4766.8  229.58  4869.1  224.24  4891.8  224.39  4925.9  221.59
  4958.2  222.05  4963.9  221.76  4971.4  219.98  4980.1  217.83  4985.8  218.71
  4994.1  217.52  4998.1  214.81  5001.8  214.81  5015.7  219.96  5026.3  222.39
  5053.9  222.68  5065.1  223.18  5127.3   222.3  5132.6  222.82  5153.1  221.29
  5174.5  221.17  5184.2  220.24  5198.9  220.81  5294.5   221.3  5307.8   221.4
  5365.1  222.39  5449.8  226.08  5513.4   231.3  5608.6  237.15  5629.8  239.14
#Mann= 7 ,-1 , 0
  4651.1     .11       0  4971.4     .06       0  5015.7     .11       0
  5053.9     .15       0  5198.9     .17       0  5294.5     .15       0
  5307.8     .11       0
Bank Sta=4971.4,5015.7
XS Rating Curve= 0 ,0
Exp/Cntr=0.3,0.1

Type RM Length L Ch R = 1 ,4081    ,499,499,499
BEGIN DESCRIPTION:
LAKE CREEK TRIBUTARY NO. 7 8.0
END DESCRIPTION:
XS GIS Cut Line= 3
      3731867.85     10128861.08      3731950.66       10128468.
       3731720.2     10127464.94
#Sta/Elev= 30
  4598.3  235.45  4690.3  232.62  4767.5  228.25  4867.1  224.86  4904.9  222.06
  4945.8  221.36    4956  221.68  4961.6  222.78  4986.6  219.65  4988.2  218.48
    4994  213.95  4997.8  213.95  5007.1  216.02 5013.16218.4853  5017.4  220.21
  5027.6  220.97  5068.7  220.08  5076.7  220.57  5137.5  218.67  5314.9  217.68
  5520.1  219.87  5550.9  222.69  5573.7  223.39  5616.5  226.29  5643.3  229.04
  5766.4  233.88    5828     237  5931.9   244.1  5992.1  245.73  6029.2  248.11
#Mann= 4 ,-1 , 0
  4598.3     .11       0  4988.2     .09       0 5013.16     .15       0
  5137.5     .11       0
Bank Sta=4988.2,5013.16
XS Rating Curve= 0 ,0
Exp/Cntr=0.3,0.1

Type RM Length L Ch R = 1 ,3582    ,199,199,199
BEGIN DESCRIPTION:
LAKE CREEK TRIBUTARY NO. 7 7.0
END DESCRIPTION:
XS GIS Cut Line= 3
      3732235.59     10128989.89      3732365.51     10128396.96
      3732537.67     10127630.56
#Sta/Elev= 30
    4393  233.68  4504.4  230.73  4563.9  226.85  4576.1  227.75  4606.8  227.23
    4618  227.82  4678.4  226.94  4749.5  223.54  4754.6  223.85  4847.4  218.68
  4883.2  218.89  4924.1  217.37    4984  219.21 5000.46217.2965  5004.1  213.32
    5008  213.32  5016.3  217.33  5026.5  219.26  5067.5  217.53  5167.6  216.75
  5172.8  216.17    5252  216.67  5264.5  216.13    5448  217.83  5528.7  223.78
  5559.5  227.27  5583.1  227.95    5703  239.59  5754.2  242.29  5785.5  242.84
#Mann= 3 ,-1 , 0
    4393     .11       0 5000.46     .07       0  5016.3     .11       0
Bank Sta=5000.46,5016.3
XS Rating Curve= 0 ,0
Exp/Cntr=0.3,0.1

Type RM Length L Ch R = 1 ,3383    ,386,386,386
BEGIN DESCRIPTION:
Mapping XS beea4072
END DESCRIPTION:
XS GIS Cut Line= 2
      3732329.34     10129234.71      3732756.17     10127595.06
#Sta/Elev= 30
  4113.3  236.86  4170.4  236.51  4230.7  233.74  4396.1   231.4  4458.1   229.5
  4499.4  229.93  4600.6   228.7  4809.4  218.65  4919.5   218.6  4924.7  217.88
  4965.2  220.22  4974.7  219.59  4985.1  215.97  4993.4  213.06  5000.5  213.72
 5004.16216.0568  5016.1  218.97  5057.4  217.13  5212.4  215.36  5319.5  215.45
  5419.1  217.41  5450.1  220.16  5476.4  221.51  5481.5     221  5557.4  225.98
  5673.8   238.1    5679  237.79  5714.3  240.89  5754.8  242.23  5807.6  245.79
#Mann= 3 , 0 , 0
  4113.3     .11       0  4985.1     .06       0 5004.16     .11       0
Bank Sta=4985.1,5004.16
XS Rating Curve= 0 ,0
Exp/Cntr=0.3,0.1

Type RM Length L Ch R = 1 ,2997    ,406,406,406
BEGIN DESCRIPTION:
LAKE CREEK TRIBUTARY NO. 7 6.0
END DESCRIPTION:
XS GIS Cut Line= 3
      3732527.24     10129245.17      3732876.21      10128469.1
      3733117.84      10127711.1
#Sta/Elev= 30
  4157.4  233.46  4215.5  234.15  4227.7  231.78  4249.7  229.94  4282.5  232.65
  4326.4  229.49    4447  226.91  4486.7  227.54  4636.6  225.26  4734.7  225.89
  4902.3  216.84  4977.2  218.02 4991.32214.8877  5000.4  212.95  5002.6  211.37
  5006.5  211.37  5016.7  214.99  5026.1  218.06  5058.3  215.47  5095.8  214.87
  5321.1  213.67  5415.6   214.3  5436.6  216.91  5468.1  216.77  5519.7  220.85
    5573  226.99    5699  239.26  5755.6  243.16  5782.6  246.57  5803.9  246.12
#Mann= 3 ,-1 , 0
  4157.4     .11       0 4991.32     .06       0  5016.7     .11       0
Bank Sta=4991.32,5016.7
XS Rating Curve= 0 ,0
Exp/Cntr=0.3,0.1