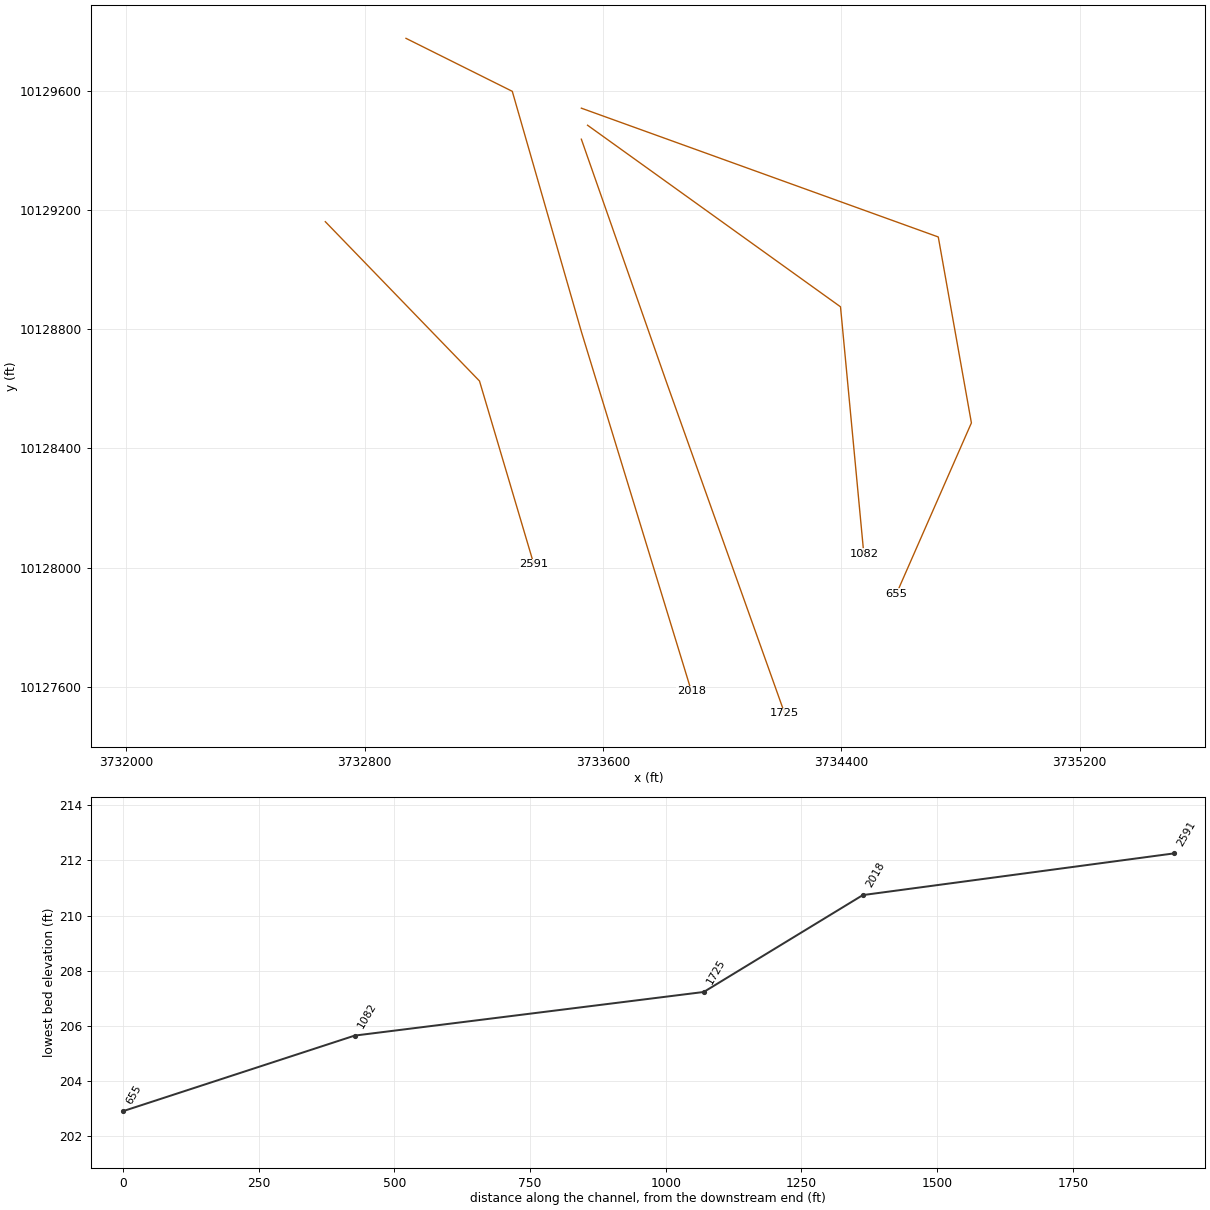
HEC-RAS study LAKE CREEK TRIBUTARY NO 7.prj: LAKE CREEK TRIBUTARY NO 7 Base Level Engineering

--- LAKE CREEK TRIBUTARY NO 7.g01 (geometry) --- (continued)

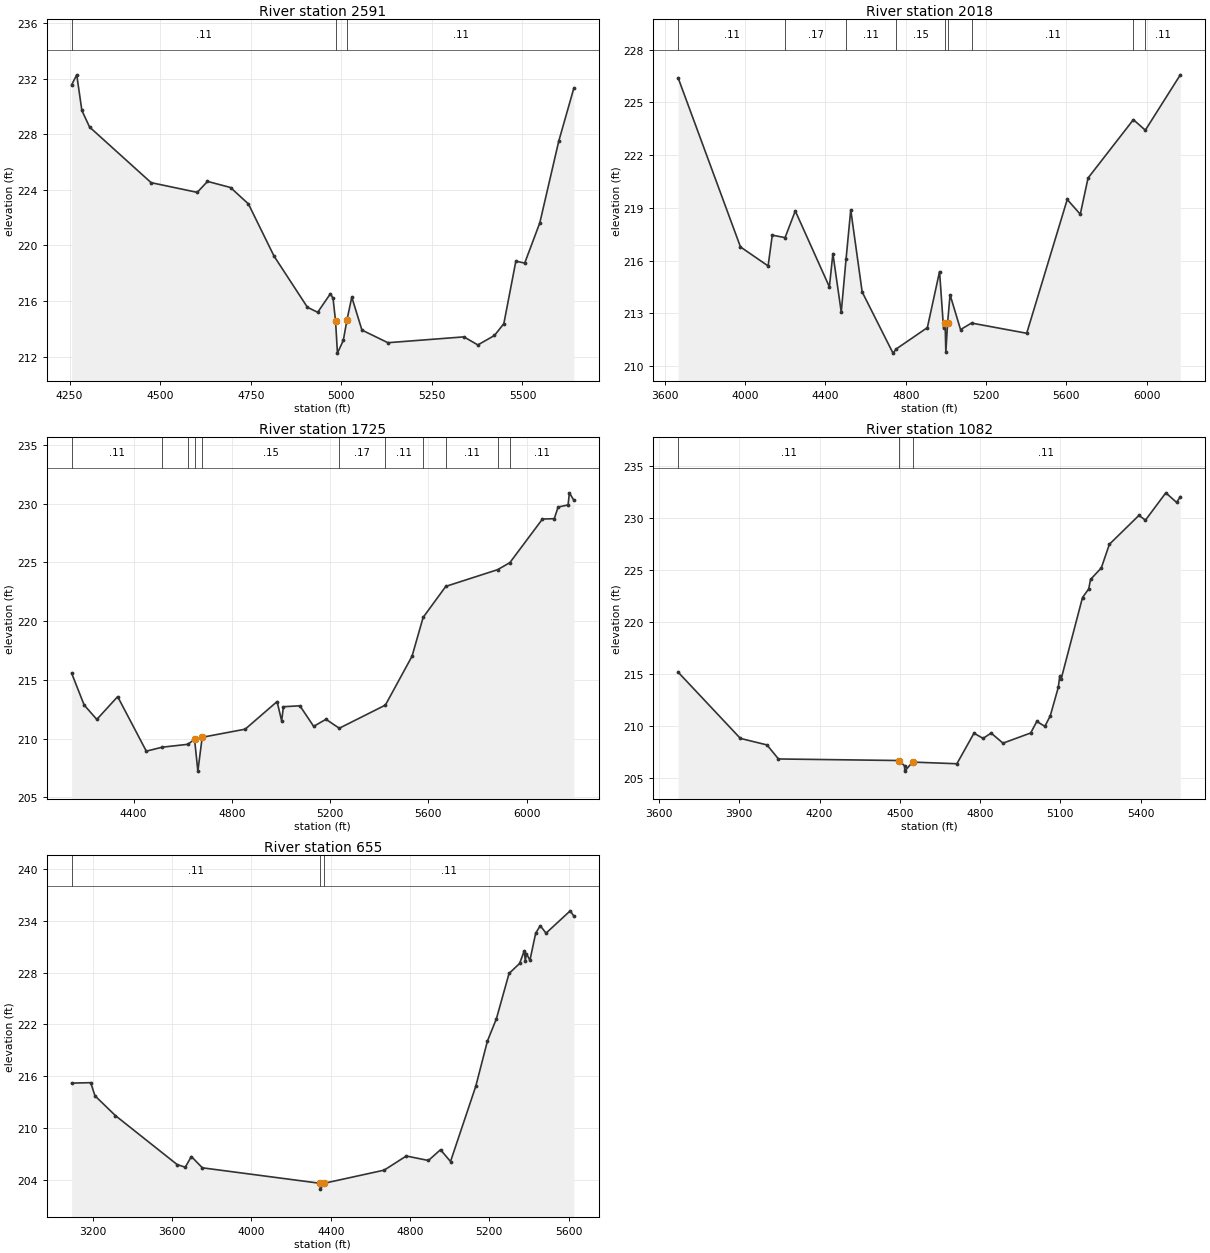
Type RM Length L Ch R = 1 ,2591    ,573,573,573
BEGIN DESCRIPTION:
LAKE CREEK TRIBUTARY NO. 7 5.0
END DESCRIPTION:
XS GIS Cut Line= 3
      3732667.87     10129161.05      3733185.39     10128626.26
      3733367.86     10128011.05
#Sta/Elev= 30
  4255.8  231.56  4269.8  232.28    4284  229.72  4305.3  228.52  4475.1  224.52
  4602.4  223.82  4630.7  224.61  4694.2  224.17  4743.6  222.99  4814.4  219.23
  4906.5  215.55  4934.8  215.19    4970  216.53  4977.2  216.19  4984.2  214.53
  4989.3  212.25  5005.4  213.16  5015.8  214.66  5028.9  216.28  5056.9  213.91
  5128.5     213  5338.4  213.42  5376.8  212.84  5422.6  213.52  5448.5  214.37
  5481.7  218.87  5506.1  218.73  5547.8  221.63    5600   227.5  5641.7  231.32
#Mann= 3 ,-1 , 0
  4255.8     .11       0  4984.2     .06       0  5015.8     .11       0
Bank Sta=4984.2,5015.8
XS Rating Curve= 0 ,0
Exp/Cntr=0.3,0.1

Type RM Length L Ch R = 1 ,2018    ,293,293,293
BEGIN DESCRIPTION:
LAKE CREEK TRIBUTARY NO. 7 4.0
END DESCRIPTION:
XS GIS Cut Line= 4
      3732938.67     10129776.41      3733295.43     10129598.55
      3733527.25     10128792.02      3733896.67     10127584.91
#Sta/Elev= 30
  3666.8   226.4  3977.3  216.78  4114.8   215.7  4135.6  217.45  4199.2  217.31
  4250.1  218.83  4419.9  214.51  4437.4   216.4    4479  213.07  4502.7  216.07
  4526.3  218.89  4583.1  214.22  4736.6  210.74  4753.1  210.98  4907.7  212.19
  4968.4  215.38  4988.1  212.17  4996.1  212.45  4999.7  210.79 5008.56  212.47
  5020.7  214.06  5072.9  212.08  5127.5  212.45  5402.3  211.87  5604.1  219.48
    5669  218.64  5707.7   220.7  5933.4  224.02  5992.8  223.42    6167  226.57
#Mann= 9 ,-1 , 0
  3666.8     .11       0  4199.2     .17       0  4502.7     .11       0
  4753.1     .15       0  4996.1     .09       0 5008.56     .15       0
  5127.5     .11       0  5933.4     .17       0  5992.8     .11       0
Bank Sta=4996.1,5008.56
XS Rating Curve= 0 ,0
Exp/Cntr=0.3,0.1

Type RM Length L Ch R = 1 ,1725    ,643,643,643
BEGIN DESCRIPTION:
LAKE CREEK TRIBUTARY NO. 7 3.0
END DESCRIPTION:
XS GIS Cut Line= 3
      3733527.25     10129437.85      3733813.71     10128620.14
      3734209.54     10127510.78
#Sta/Elev= 30
  4148.2  215.56  4199.2  212.85  4250.7  211.63  4335.5  213.57  4452.1  208.93
  4517.9  209.27  4620.6  209.51  4648.6  209.93    4662  207.23  4679.6  210.11
  4854.7   210.8  4984.5  213.15  5003.1   211.5  5010.2  212.71  5077.4  212.79
  5133.4  211.04  5183.5  211.64  5237.7  210.88  5425.4  212.85  5533.9  217.01
    5579  220.31  5671.3  222.95    5882  224.37  5932.1  224.97  6064.8  228.68
  6112.8  228.71  6128.5   229.7  6169.1  229.88  6174.4  230.91  6192.5  230.28
#Mann= 11 ,-1 , 0
  4148.2     .11       0  4517.9     .17       0  4620.6     .15       0
  4648.6     .09       0  4679.6     .15       0  5237.7     .17       0
  5425.4     .11       0    5579     .17       0  5671.3     .11       0
    5882     .17       0  5932.1     .11       0
Bank Sta=4648.6,4679.6
XS Rating Curve= 0 ,0
Exp/Cntr=0.3,0.1

Type RM Length L Ch R = 1 ,1082    ,427,427,427
BEGIN DESCRIPTION:
LAKE CREEK TRIBUTARY NO. 7 2.0
END DESCRIPTION:
XS GIS Cut Line= 3
      3733548.05     10129484.75      3734397.04     10128875.35
      3734475.17     10128047.19
#Sta/Elev= 30
  3671.5  215.17  3904.1   208.8  4003.6  208.17  4046.6  206.82  4497.3  206.67
  4518.2  206.15  4518.5  205.65  4547.6  206.52  4713.4  206.36  4777.3   209.3
  4811.3   208.8  4841.4  209.31  4885.7  208.34  4989.2  209.32  5012.1  210.43
  5042.3  209.96  5062.4  210.97  5092.5  213.72  5097.7  214.78  5102.7  214.48
  5182.9  222.35  5206.1  223.18    5213  224.09  5253.2   225.2  5283.3  227.47
  5393.8  230.25  5418.1  229.79  5494.3  232.42  5534.5   231.5  5548.4  232.05
#Mann= 3 ,-1 , 0
  3671.5     .11       0  4497.3     .06       0  4547.6     .11       0
Bank Sta=4497.3,4547.6
XS Rating Curve= 0 ,0
Exp/Cntr=0.3,0.1

Type RM Length L Ch R = 1 ,655     ,0,0,0
BEGIN DESCRIPTION:
LAKE CREEK TRIBUTARY NO. 7 1.0
END DESCRIPTION:
XS GIS Cut Line= 4
      3733527.28     10129542.01      3734725.17     10129109.73
      3734836.35     10128485.65      3734584.53     10127911.77
#Sta/Elev= 30
  3092.6   215.2  3188.9  215.25  3210.1  213.73  3313.7  211.43  3624.8  205.76
  3665.9  205.45  3696.6  206.69  3752.3  205.38  4344.9  203.59  4348.1  202.91
  4364.9  203.58  4669.5  205.11  4781.2  206.75  4892.9  206.23  4953.9  207.48
  5004.4  206.11  5131.9  214.84  5190.6  220.07  5236.2  222.68  5299.8  227.91
  5353.1  229.07  5376.3  230.53  5381.9  229.41  5387.3  230.22  5405.2  229.44
  5434.1  232.58  5457.4  233.45  5486.3  232.58  5608.5  235.17  5626.7  234.56
#Mann= 3 ,-1 , 0
  3092.6     .11       0  4344.9     .06       0  4364.9     .11       0
Bank Sta=4344.9,4364.9
XS Rating Curve= 0 ,0
Exp/Cntr=0.3,0.1

Chan Stop Cuts=-1
Use User Specified Reach Order=0
Composite Channel Slope=5