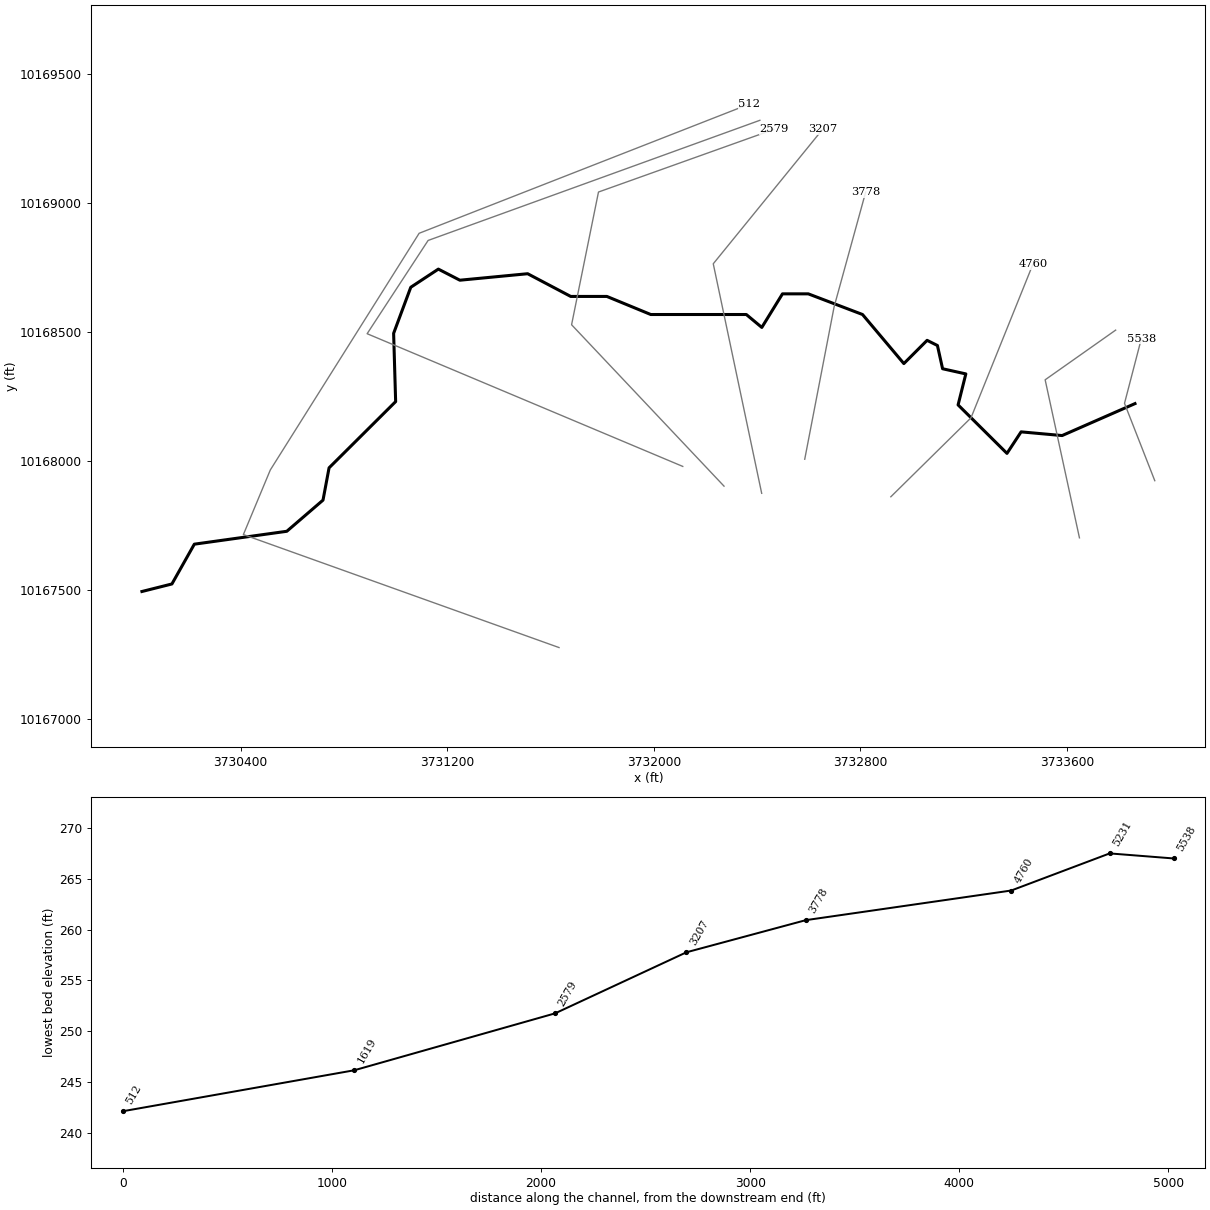
--- LAKE CREEK TRIBUTARY NO 8 1.prj (project) ---

Proj Title=LAKE CREEK TRIBUTARY NO 8 1 Base Level Engineering
Current Plan=p01
Default Exp/Contr=0.3,0.1
English Units
Geom File=g01
Flow File=f01
Plan File=p01
Y Axis Title=Elevation
X Axis Title(PF)=Main Channel Distance
X Axis Title(XS)=Station
BEGIN DESCRIPTION:
LAKE CREEK TRIBUTARY NO 8 1
END DESCRIPTION:
DSS Export Rating Curves= 0
DSS Export Rating Curve Sorted= 0
DSS Export Volume Flow Curves= 0
DXF OffsetX= 0
DXF OffsetY= 0
DXF ScaleX= 1
DXF ScaleY= 10

--- LAKE CREEK TRIBUTARY NO 8 1.p01 (plan) ---

Plan Title=Multiple Run
Short Identifier=Multiple
Geom File=g01
Flow File=f01
Subcritical Flow
K Sum by GR= 0
Std Step Tol= 0.01
Critical Tol= 0.01
Num of Std Step Trials= 20
Max Error Tol= 0.3
Flow Tol Ratio= 0.001
Split Flow NTrial= 30
Split Flow Tol= 0.02
Split Flow Ratio= 0.02
Log Output Level= 0
Friction Slope Method= 1
Unsteady Friction Slope Method= 2
Unsteady Bridges Friction Slope Method= 1
Parabolic Critical Depth
Global Vel Dist=  1 , 1 , 1
Global Log Level= 0
CheckData=True
Encroach Param= -1, 0, 0, 0
BEGIN DESCRIPTION:
Multiple Run
END DESCRIPTION:

--- LAKE CREEK TRIBUTARY NO 8 1.f01 (steady flow) ---

Flow Title=Multiple
Program Version=4.10
Number of Profiles= 7
Profile Names=10-year,25-year,50-year,1pct_min,100-year,1pct_plu,500-year
River Rch & RM=LAKE CREEK TRIBU,Reach-1         ,5538
     690     950    1298     584    1764    5327    3373
Boundary for River Rch & Prof#=LAKE CREEK TRIBU,Reach-1         , 1
Up Type= 0
Dn Type= 3
Dn Slope=0.005
Boundary for River Rch & Prof#=LAKE CREEK TRIBU,Reach-1         , 2
Up Type= 0
Dn Type= 3
Dn Slope=0.005
Boundary for River Rch & Prof#=LAKE CREEK TRIBU,Reach-1         , 3
Up Type= 0
Dn Type= 3
Dn Slope=0.005
Boundary for River Rch & Prof#=LAKE CREEK TRIBU,Reach-1         , 4
Up Type= 0
Dn Type= 3
Dn Slope=0.005
Boundary for River Rch & Prof#=LAKE CREEK TRIBU,Reach-1         , 5
Up Type= 0
Dn Type= 3
Dn Slope=0.005
Boundary for River Rch & Prof#=LAKE CREEK TRIBU,Reach-1         , 6
Up Type= 0
Dn Type= 3
Dn Slope=0.005
Boundary for River Rch & Prof#=LAKE CREEK TRIBU,Reach-1         , 7
Up Type= 0
Dn Type= 3
Dn Slope=0.005
DSS Import GetInterval= 0
DSS Import GetPeak= 0
DSS Import FillOption= 0

--- LAKE CREEK TRIBUTARY NO 8 1.g01 (geometry) ---

Geom Title=Existing Conditions
Program Version=4.10

River Reach=LAKE CREEK TRIBU,Reach-1
Reach XY= 30
      3733863.23     10168221.84      3733581.09     10168098.11
      3733422.23     10168112.43      3733367.55     10168029.09
      3733178.23     10168216.84      3733208.23     10168336.84
      3733118.23     10168356.84      3733098.23     10168446.84
      3733058.23     10168466.84      3732968.23     10168376.84
      3732808.23     10168566.84      3732598.23     10168646.84
      3732498.23     10168646.84      3732418.23     10168516.84
      3732358.23     10168566.84      3731988.23     10168566.84
      3731818.23     10168636.84      3731678.23     10168636.84
      3731511.53     10168724.79      3731249.06     10168699.67
      3731165.72     10168742.64      3731058.95     10168672.32
      3730992.55     10168493.94      3731000.36     10168229.62
      3730742.55     10167973.11      3730719.11     10167848.11
      3730578.92     10167727.45      3730220.84     10167677.53
      3730134.04     10167523.45      3730017.94     10167494.26

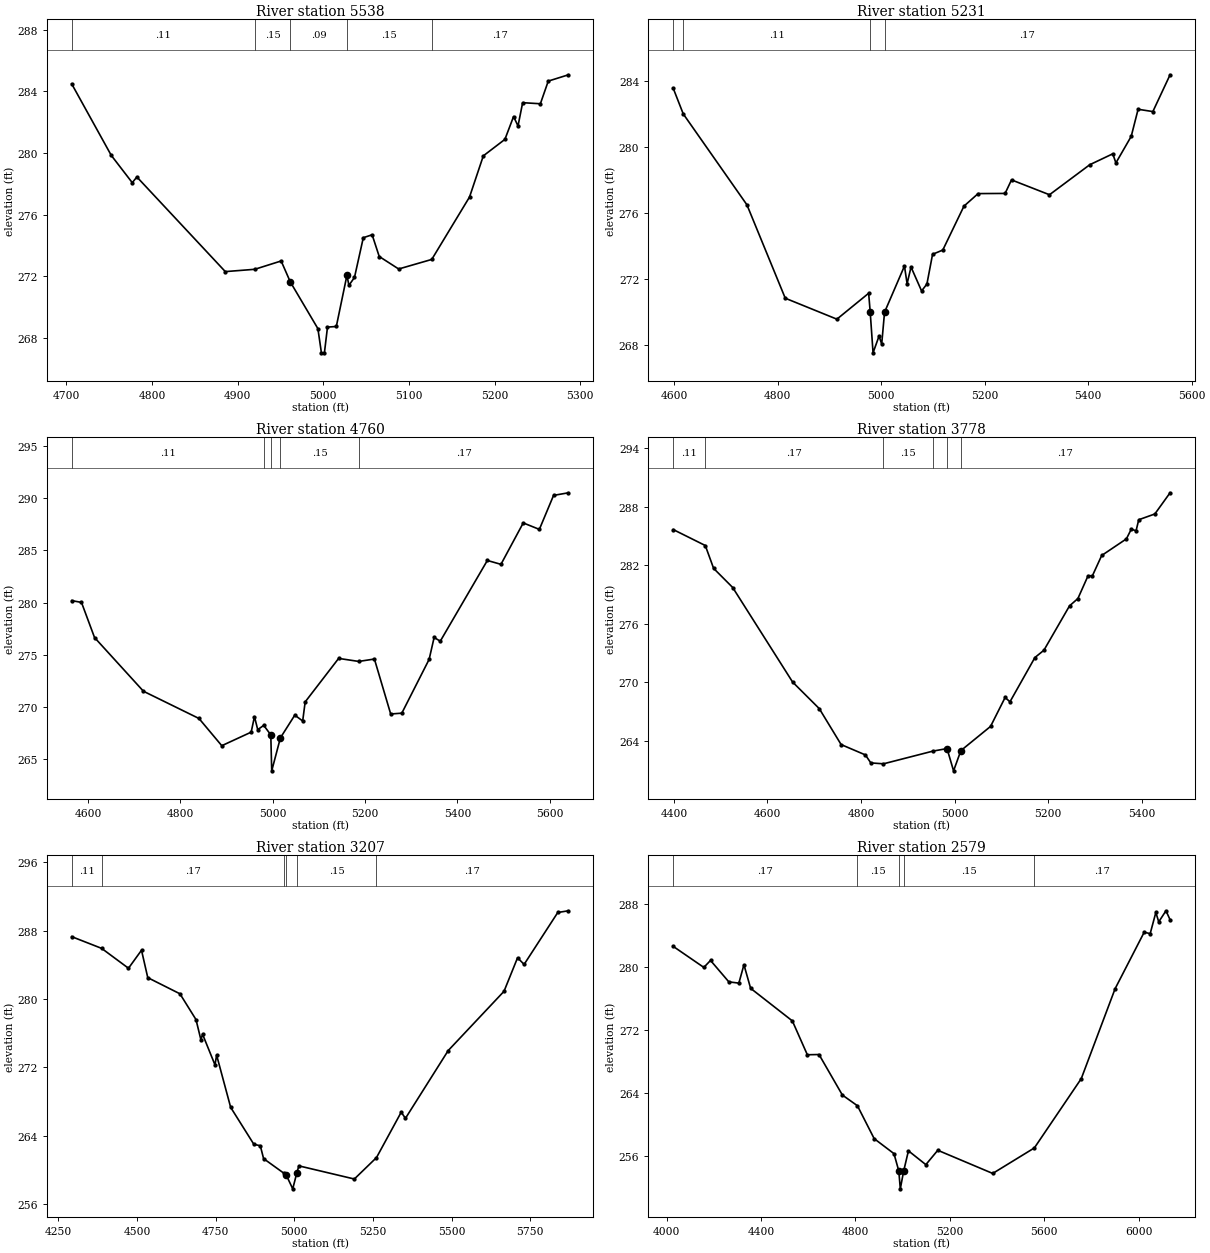
Type RM Length L Ch R = 1 ,5538    ,307,307,307
BEGIN DESCRIPTION:
LAKE CREEK TRIBUTARY NO. 8. 1 4.0
END DESCRIPTION:
XS GIS Cut Line= 3
      3733939.86     10167923.39      3733822.66     10168222.88
      3733887.76     10168472.84
#Sta/Elev= 30
  4706.3  284.48  4752.5  279.84    4777  278.07  4782.4  278.44  4885.6   272.3
    4920  272.45  4950.8  272.99  4961.5  271.63  4993.7   268.6  4997.8  267.03
  5001.3  267.03  5004.9   268.7  5015.2  268.74  5027.6  272.06  5029.9  271.41
  5036.4  271.92  5046.7   274.5    5057  274.69  5065.3  273.28    5088  272.47
  5126.6  273.09  5170.7  277.14  5186.8  279.81    5212  280.88  5222.1  282.36
  5227.3  281.75  5232.7  283.26  5253.4  283.19  5262.6  284.66  5286.2  285.07
#Mann= 5 ,-1 , 0
  4706.3     .11       0    4920     .15       0  4961.5     .09       0
  5027.6     .15       0  5126.6     .17       0
Bank Sta=4961.5,5027.6
XS Rating Curve= 0 ,0
Exp/Cntr=0.3,0.1

Type RM Length L Ch R = 1 ,5231    ,471,471,471
BEGIN DESCRIPTION:
Mapping XS 9f7f20d1
END DESCRIPTION:
XS GIS Cut Line= 3
      3733648.18     10167702.05      3733515.37     10168314.03
      3733788.36     10168506.42
#Sta/Elev= 30
  4598.1  283.55  4617.3  282.01  4740.4   276.5  4814.5  270.84  4914.3  269.57
  4975.7  271.14 4978.63270.0288  4984.2  267.53  4995.8  268.55  5000.9  268.06
  5006.4  269.99  5044.9  272.79    5050  271.72  5057.6  272.73    5078  271.28
  5088.3   271.7  5099.2   273.5    5119  273.76  5159.9  276.42  5187.3  277.18
  5239.4  277.19  5251.8  278.01  5325.2  277.11  5403.1  278.93  5447.5  279.59
  5453.6  279.04  5483.2  280.65  5496.5  282.29    5525  282.15  5558.3  284.38
#Mann= 4 ,-1 , 0
  4598.1     .17       0  4617.3     .11       0 4978.63     .06       0
  5006.4     .17       0
Bank Sta=4978.63,5006.4
XS Rating Curve= 0 ,0
Exp/Cntr=0.3,0.1

Type RM Length L Ch R = 1 ,4760    ,982,982,982
BEGIN DESCRIPTION:
LAKE CREEK TRIBUTARY NO. 8. 1 3.0
END DESCRIPTION:
XS GIS Cut Line= 3
      3732917.85     10167861.07      3733228.23     10168166.84
      3733467.84     10168761.05
#Sta/Elev= 30
  4564.3  280.19  4585.5  280.02  4613.8  276.65  4719.8   271.5  4840.1  268.89
  4889.5  266.28  4953.2  267.58  4960.3  269.07  4967.4  267.82  4980.4  268.23
  4995.7  267.32  4997.7  263.87  5016.5  267.03  5047.7  269.21  5064.8  268.65
  5070.2  270.48  5142.7  274.65  5186.2  274.36  5220.2  274.59  5255.5  269.32
  5279.6   269.4  5338.8  274.56  5349.6  276.66  5362.9   276.3  5464.9  284.04
  5494.4  283.67  5542.7  287.64  5577.6  287.02  5608.4  290.28  5640.7  290.53
#Mann= 5 ,-1 , 0
  4564.3     .11       0  4980.4     .15       0  4995.7     .09       0
  5016.5     .15       0  5186.2     .17       0
Bank Sta=4995.7,5016.5
XS Rating Curve= 0 ,0
Exp/Cntr=0.3,0.1

Type RM Length L Ch R = 1 ,3778    ,571,571,571
BEGIN DESCRIPTION:
LAKE CREEK TRIBUTARY NO. 8. 1 2.0
END DESCRIPTION:
XS GIS Cut Line= 3
       3732584.4     10168006.42      3732698.23     10168596.84
      3732820.51     10169041.12
#Sta/Elev= 30
  4398.7  285.65  4467.1  284.02  4484.9  281.68  4525.7  279.72  4653.8  270.04
  4710.8  267.32  4757.5  263.64  4809.4  262.58    4821  261.76  4848.1  261.67
  4953.8  262.97  4983.9  263.23  4997.9  260.95  5013.5  263.02    5077   265.5
  5108.1  268.46  5118.5  268.02  5171.8  272.55  5191.1   273.3  5245.8  277.84
  5263.7  278.59  5285.4  280.92  5294.8  280.93  5314.6     283  5367.4   284.7
  5377.8  285.69  5388.1  285.53  5393.8  286.66  5428.2  287.25  5460.8  289.42
#Mann= 6 ,-1 , 0
  4398.7     .11       0  4467.1     .17       0  4848.1     .15       0
  4953.8     .17       0  4983.9     .09       0  5013.5     .17       0
Bank Sta=4983.9,5013.5
XS Rating Curve= 0 ,0
Exp/Cntr=0.3,0.1

Type RM Length L Ch R = 1 ,3207    ,628,628,628
BEGIN DESCRIPTION:
Mapping XS 619deace
END DESCRIPTION:
XS GIS Cut Line= 3
      3732417.72     10167874.48      3732230.23     10168763.34
      3732653.36     10169283.57
#Sta/Elev= 30
  4292.4  287.31  4387.5  285.94  4472.9  283.61  4514.3  285.72  4534.2  282.51
  4636.4  280.62  4687.5   277.6  4703.2  275.22  4708.3  275.89  4747.9  272.29
    4753  273.44  4797.7  267.32  4871.5  262.99  4891.9  262.83  4902.3  261.32
  4967.9  259.58  4973.7  259.44    4995  257.78  5007.6259.5974  5014.5  260.47
  5190.8  258.93  5261.2  261.44  5339.7  266.75  5353.3  266.04  5489.1  273.97
  5666.5  280.91  5709.6  284.84  5730.4  284.06  5837.4  290.14  5871.4  290.34
#Mann= 6 ,-1 , 0
  4292.4     .11       0  4387.5     .17       0  4967.9     .15       0
  4973.7     .09       0  5007.6     .15       0  5261.2     .17       0
Bank Sta=4973.7,5007.6
XS Rating Curve= 0 ,0
Exp/Cntr=0.3,0.1

Type RM Length L Ch R = 1 ,2579    ,960,960,960
BEGIN DESCRIPTION:
Mapping XS 804f9b2c
END DESCRIPTION:
XS GIS Cut Line= 4
      3732271.88     10167902.25      3731681.62     10168527.22
      3731785.79     10169041.11       3732464.6     10169283.55
#Sta/Elev= 30
  4028.5  282.62  4157.9  279.95  4186.2  280.84  4263.8  278.11  4306.3  277.95
  4327.8  280.29  4356.1  277.29  4532.9  273.14  4596.4  268.83  4645.9  268.86
  4744.9   263.7  4808.6  262.34  4879.6  258.15  4963.5  256.24  4983.9  254.04
  4990.3  251.76  5004.3  253.99  5024.7   256.6  5098.5  254.84  5149.1  256.67
  5381.8  253.72  5558.3  256.97    5757  265.79  5900.4  277.24  6023.6  284.43
    6049  284.25    6073  286.95  6085.2  285.75  6115.9  287.16  6133.3  286.02
#Mann= 5 ,-1 , 0
  4028.5     .17       0  4808.6     .15       0  4983.9     .09       0
  5004.3     .15       0  5558.3     .17       0
Bank Sta=4983.9,5004.3
XS Rating Curve= 0 ,0
Exp/Cntr=0.3,0.1

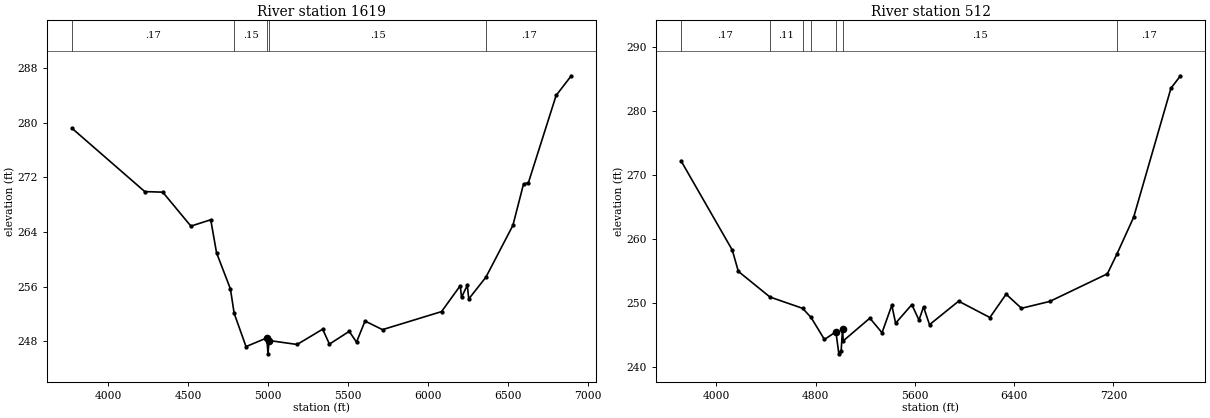
Type RM Length L Ch R = 1 ,1619    ,1107,1107,1107
BEGIN DESCRIPTION:
Mapping XS ccaca2bc
END DESCRIPTION:
XS GIS Cut Line= 4
      3732112.13     10167978.63      3730889.95      10168492.5
      3731126.06     10168853.61      3732410.75     10169318.88
#Sta/Elev= 30
  3772.7  279.18    4229  269.89  4341.4  269.81  4517.4  264.84  4641.5  265.77
  4677.7  260.94  4764.5  255.65  4787.9  252.08  4862.1  247.21  4992.3  248.48
  4999.4  246.15  5006.6   248.1  5181.7  247.52  5341.5  249.76  5383.7  247.57
  5507.4  249.44  5553.1  247.86  5606.3  250.95  5715.7  249.69  6084.9  252.33
  6201.9  256.12  6209.9  254.42  6245.9  256.18  6255.1  254.18  6362.4  257.37
    6531  264.94  6597.6     271  6628.2   271.2  6801.4  283.96  6896.3  286.84
#Mann= 5 ,-1 , 0
  3772.7     .17       0  4787.9     .15       0  4992.3     .09       0
  5006.6     .15       0  6362.4     .17       0
Bank Sta=4992.3,5006.6
XS Rating Curve= 0 ,0
Exp/Cntr=0.3,0.1

Type RM Length L Ch R = 1 ,512     ,0,0,0
BEGIN DESCRIPTION:
LAKE CREEK TRIBUTARY NO. 8. 1 1.0
END DESCRIPTION:
XS GIS Cut Line= 5
      3731633.04     10167277.21      3730410.79     10167714.72
      3730514.95     10167964.72      3731091.34     10168881.39
      3732369.15      10169381.4
#Sta/Elev= 30
  3715.4  272.25  4128.6  258.31  4177.6  254.98  4432.2  250.98  4695.4  249.21
    4763   247.8  4871.3  244.35  4963.6  245.55  4987.3  242.11  5006.1  242.62
    5017  246.04  5022.4  244.13  5237.1  247.68  5335.1   245.4    5414  249.69
  5444.6  246.89  5575.3  249.79    5633  247.38  5669.5  249.44  5717.8  246.66
  5952.2  250.33  6204.2  247.78  6334.9  251.42  6458.6  249.22  6686.5  250.29
  7150.6   254.6  7226.1  257.62  7362.2  263.42  7662.8  283.56  7739.4  285.51
#Mann= 7 ,-1 , 0
  3715.4     .17       0  4432.2     .11       0  4695.4     .17       0
    4763     .15       0  4963.6     .06       0    5017     .15       0
  7226.1     .17       0
Bank Sta=4963.6,5017
XS Rating Curve= 0 ,0
Exp/Cntr=0.3,0.1

Chan Stop Cuts=-1
Use User Specified Reach Order=0
Composite Channel Slope=5