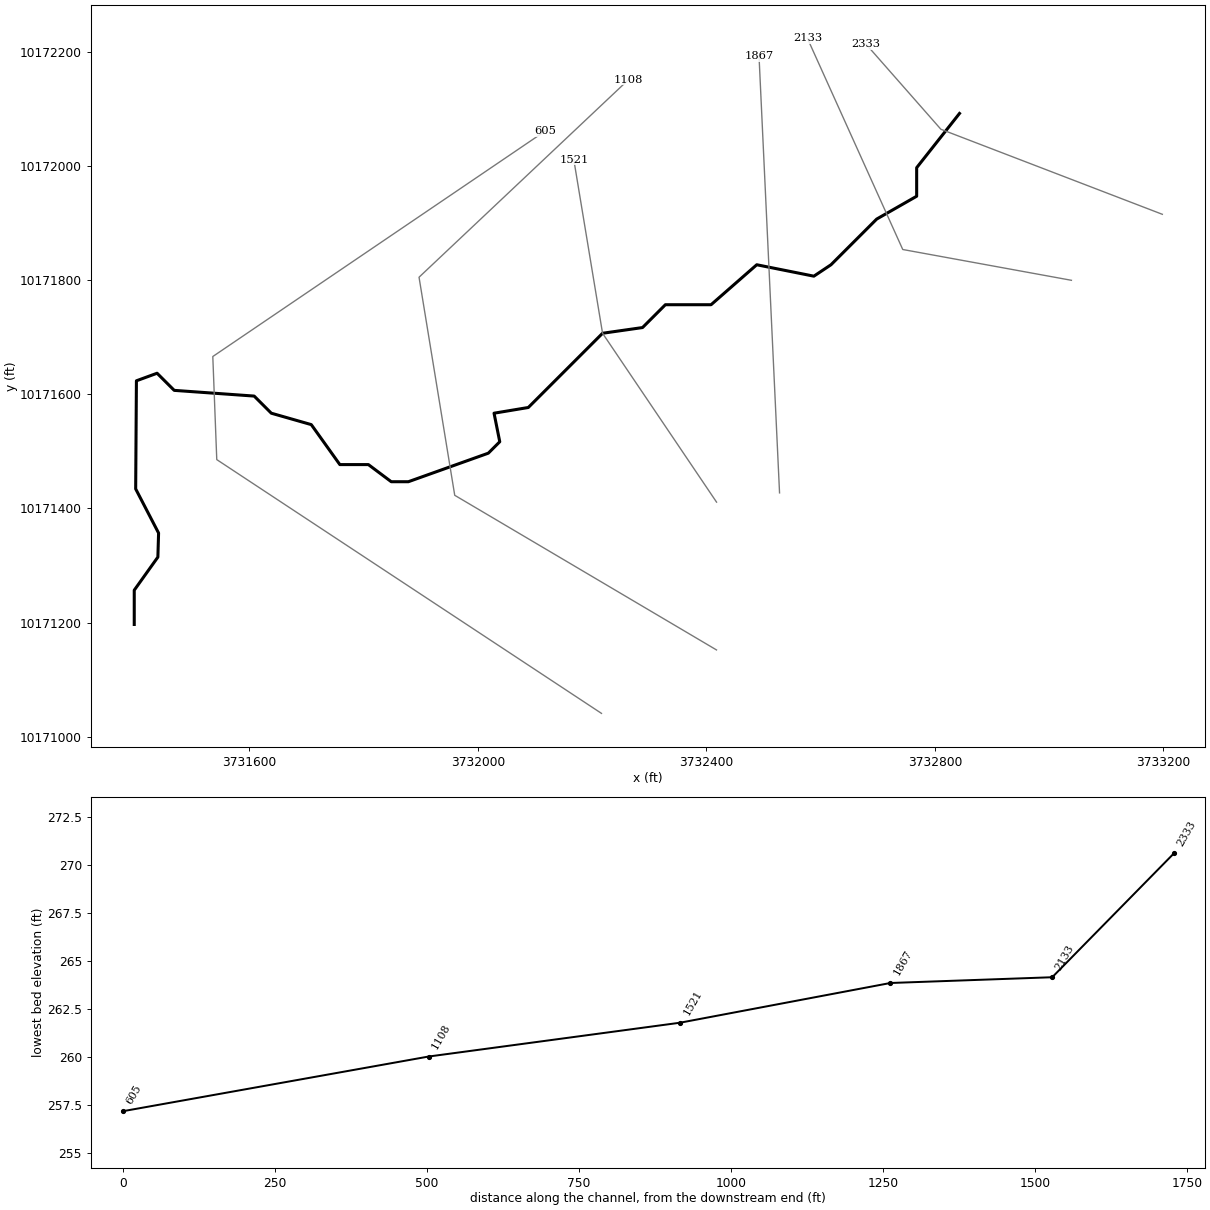
--- LAKE CREEK TRIBUTARY NO 8 2.prj (project) ---

Proj Title=LAKE CREEK TRIBUTARY NO 8 2 Base Level Engineering
Current Plan=p01
Default Exp/Contr=0.3,0.1
English Units
Geom File=g01
Flow File=f01
Plan File=p01
Y Axis Title=Elevation
X Axis Title(PF)=Main Channel Distance
X Axis Title(XS)=Station
BEGIN DESCRIPTION:
LAKE CREEK TRIBUTARY NO 8 2
END DESCRIPTION:
DSS Export Rating Curves= 0
DSS Export Rating Curve Sorted= 0
DSS Export Volume Flow Curves= 0
DXF OffsetX= 0
DXF OffsetY= 0
DXF ScaleX= 1
DXF ScaleY= 10

--- LAKE CREEK TRIBUTARY NO 8 2.p01 (plan) ---

Plan Title=Multiple Run
Short Identifier=Multiple
Geom File=g01
Flow File=f01
Subcritical Flow
K Sum by GR= 0
Std Step Tol= 0.01
Critical Tol= 0.01
Num of Std Step Trials= 20
Max Error Tol= 0.3
Flow Tol Ratio= 0.001
Split Flow NTrial= 30
Split Flow Tol= 0.02
Split Flow Ratio= 0.02
Log Output Level= 0
Friction Slope Method= 1
Unsteady Friction Slope Method= 2
Unsteady Bridges Friction Slope Method= 1
Parabolic Critical Depth
Global Vel Dist=  1 , 1 , 1
Global Log Level= 0
CheckData=True
Encroach Param= -1, 0, 0, 0
BEGIN DESCRIPTION:
Multiple Run
END DESCRIPTION:

--- LAKE CREEK TRIBUTARY NO 8 2.f01 (steady flow) ---

Flow Title=Multiple
Program Version=4.10
Number of Profiles= 7
Profile Names=10-year,25-year,50-year,1pct_min,100-year,1pct_plu,500-year
River Rch & RM=LAKE CREEK TRIBU,Reach-1         ,2333
     406     537     712     312     941    2842    1698
River Rch & RM=LAKE CREEK TRIBU,Reach-1         ,1867
     829    1150    1578     712    2150    6493    4137
Boundary for River Rch & Prof#=LAKE CREEK TRIBU,Reach-1         , 1
Up Type= 0
Dn Type= 3
Dn Slope=0.005
Boundary for River Rch & Prof#=LAKE CREEK TRIBU,Reach-1         , 2
Up Type= 0
Dn Type= 3
Dn Slope=0.005
Boundary for River Rch & Prof#=LAKE CREEK TRIBU,Reach-1         , 3
Up Type= 0
Dn Type= 3
Dn Slope=0.005
Boundary for River Rch & Prof#=LAKE CREEK TRIBU,Reach-1         , 4
Up Type= 0
Dn Type= 3
Dn Slope=0.005
Boundary for River Rch & Prof#=LAKE CREEK TRIBU,Reach-1         , 5
Up Type= 0
Dn Type= 3
Dn Slope=0.005
Boundary for River Rch & Prof#=LAKE CREEK TRIBU,Reach-1         , 6
Up Type= 0
Dn Type= 3
Dn Slope=0.005
Boundary for River Rch & Prof#=LAKE CREEK TRIBU,Reach-1         , 7
Up Type= 0
Dn Type= 3
Dn Slope=0.005
DSS Import GetInterval= 0
DSS Import GetPeak= 0
DSS Import FillOption= 0

--- LAKE CREEK TRIBUTARY NO 8 2.g01 (geometry) ---

Geom Title=Existing Conditions
Program Version=4.10

River Reach=LAKE CREEK TRIBU,Reach-1
Reach XY= 30
      3732843.23     10172091.84      3732768.23     10171996.84
      3732768.23     10171946.84      3732698.23     10171906.84
      3732618.23     10171826.84      3732588.23     10171806.84
      3732488.23     10171826.84      3732408.23     10171756.84
      3732328.23     10171756.84      3732288.23     10171716.84
      3732218.23     10171706.84      3732088.23     10171576.84
      3732028.23     10171566.84      3732038.23     10171516.84
      3732018.23     10171496.84      3731878.23     10171446.84
      3731848.23     10171446.84      3731808.23     10171476.84
      3731758.23     10171476.84      3731708.23     10171546.84
      3731638.23     10171566.84      3731608.23     10171596.84
      3731468.23     10171606.84      3731438.23     10171636.84
      3731402.04      10171623.6      3731400.74     10171434.25
      3731440.85     10171356.93      3731439.61     10171314.82
      3731398.23     10171256.84      3731398.23     10171196.84

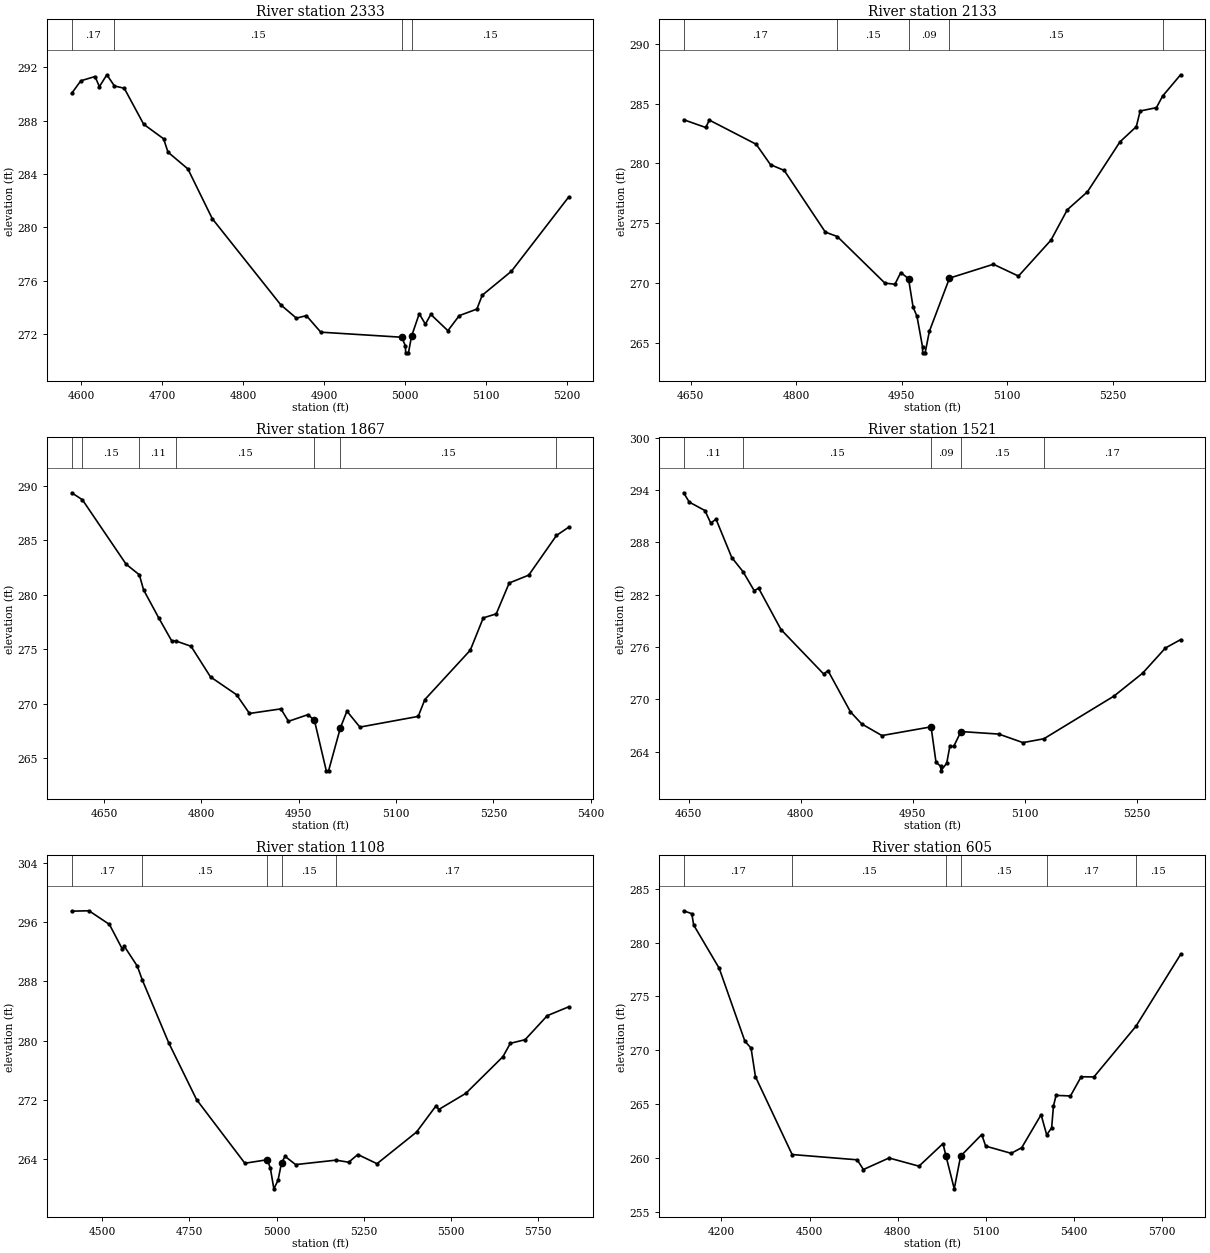
Type RM Length L Ch R = 1 ,2333    ,200,200,200
BEGIN DESCRIPTION:
LAKE CREEK TRIBUTARY NO. 8. 2 3.0
END DESCRIPTION:
XS GIS Cut Line= 3
       3733198.4      10171915.2      3732810.64     10172064.13
      3732679.68     10172213.07
#Sta/Elev= 30
  4588.4  290.06  4599.7     291  4617.2  291.32  4622.6  290.56  4631.8  291.45
  4641.2  290.61  4653.3  290.44  4677.3  287.74  4701.9  286.65  4707.3  285.65
  4731.9  284.39    4762  280.66  4846.6   274.2  4865.9   273.2  4878.2  273.39
    4896  272.15  4996.1  271.77  5000.6   271.1  5000.8   270.6  5004.3   270.6
  5008.1271.8438  5017.6  273.53  5025.2  272.75  5031.9  273.48    5053  272.26
    5067  273.39  5088.8  273.88  5095.4  274.92  5131.5  276.72  5202.1  282.28
#Mann= 4 ,-1 , 0
  4588.4     .17       0  4641.2     .15       0  4996.1     .09       0
  5008.1     .15       0
Bank Sta=4996.1,5008.1
XS Rating Curve= 0 ,0
Exp/Cntr=0.3,0.1

Type RM Length L Ch R = 1 ,2133    ,266,266,266
BEGIN DESCRIPTION:
Mapping XS d27a413d
END DESCRIPTION:
XS GIS Cut Line= 3
      3733039.21     10171799.61      3732743.87     10171853.55
      3732576.93     10172223.39
#Sta/Elev= 30
  4640.1  283.65  4671.5     283  4676.6  283.62  4743.1   281.6  4763.5  279.89
    4783  279.41  4841.4  274.25  4858.4  273.88  4926.1  269.98  4940.3  269.89
  4948.6  270.87  4959.6  270.35  4966.1  267.97  4971.6  267.21  4979.5  264.65
  4979.7  264.15  4983.2  264.15  4989.2  265.95  5017.8   270.4  5080.2  271.56
  5115.8  270.57    5162  273.58  5185.2  276.12  5213.8  277.62    5260   281.8
  5283.2  283.07  5288.7  284.38  5311.8  284.66  5320.6  285.63  5346.1  287.41
#Mann= 5 ,-1 , 0
  4640.1     .17       0  4858.4     .15       0  4959.6     .09       0
  5017.8     .15       0  5320.6     .17       0
Bank Sta=4959.6,5017.8
XS Rating Curve= 0 ,0
Exp/Cntr=0.3,0.1

Type RM Length L Ch R = 1 ,1867    ,346,346,346
BEGIN DESCRIPTION:
Mapping XS 362d07a7
END DESCRIPTION:
XS GIS Cut Line= 2
      3732528.14     10171427.29      3732492.19     10172192.54
#Sta/Elev= 30
    4600  289.34  4616.5   288.7  4683.9  282.79  4704.3  281.82  4710.8  280.44
  4733.9   277.9    4754  275.78  4761.3  275.74    4784  275.27    4814  272.46
  4854.1  270.83  4874.1  269.11  4922.5  269.53  4934.2  268.39  4964.2     269
  4974.2  268.48  4992.5  263.85    4996  263.85  5014.2  267.79  5024.3  269.32
  5044.3  267.86  5134.2  268.84  5144.4  270.38  5214.5  274.91  5234.5  277.87
  5254.5  278.24  5274.5  281.07  5304.6  281.79  5347.4  285.43  5366.1  286.18
#Mann= 7 ,-1 , 0
    4600     .11       0  4616.5     .15       0  4704.3     .11       0
  4761.3     .15       0  4974.2     .09       0  5014.2     .15       0
  5347.4     .17       0
Bank Sta=4974.2,5014.2
XS Rating Curve= 0 ,0
Exp/Cntr=0.3,0.1

Type RM Length L Ch R = 1 ,1521    ,413,413,413
BEGIN DESCRIPTION:
LAKE CREEK TRIBUTARY NO. 8. 2 2.0
END DESCRIPTION:
XS GIS Cut Line= 3
      3732417.83      10171411.1      3732218.23     10171706.84
      3732167.85      10172011.1
#Sta/Elev= 30
  4643.2   293.7  4650.7  292.63  4671.7  291.66  4679.4  290.23  4686.6  290.66
  4707.6  286.27  4722.7  284.64  4737.6  282.47  4743.6  282.74  4773.5     278
  4830.5  272.91  4836.5  273.27  4866.5  268.55  4881.5  267.17  4908.6  265.83
  4974.4  266.83    4981  262.78  4987.4  262.28  4987.6  261.78  4995.4  262.67
  4999.5  264.58  5004.7  264.58  5014.4  266.29  5065.1     266  5097.4  265.02
  5125.4  265.46  5219.4  270.37  5257.7     273  5288.1  275.88  5308.4  276.84
#Mann= 5 ,-1 , 0
  4643.2     .11       0  4722.7     .15       0  4974.4     .09       0
  5014.4     .15       0  5125.4     .17       0
Bank Sta=4974.4,5014.4
XS Rating Curve= 0 ,0
Exp/Cntr=0.3,0.1

Type RM Length L Ch R = 1 ,1108    ,503,503,503
BEGIN DESCRIPTION:
Mapping XS 0ef4744c
END DESCRIPTION:
XS GIS Cut Line= 4
      3732417.75     10171152.21       3731959.4     10171423.06
       3731896.9       10171805.      3732263.93     10172151.25
#Sta/Elev= 30
  4413.1  297.48  4462.6  297.53  4521.2  295.69  4558.2  292.36    4564  292.73
  4601.1  290.06  4615.4   288.2  4690.9  279.74  4770.9  272.06  4909.4  263.47
  4973.9  263.95  4982.5  262.77  4992.4  260.02  5004.3  261.16  5014.4  263.52
  5024.5   264.4  5054.9  263.29  5170.3  263.89  5206.9  263.61    5233  264.65
    5288  263.41  5401.3  267.68  5457.6  271.25  5464.8  270.72  5542.5   272.9
  5648.9  277.85    5670  279.65  5712.4  280.14  5775.9  283.38  5837.1  284.57
#Mann= 5 ,-1 , 0
  4413.1     .17       0  4615.4     .15       0  4973.9     .09       0
  5014.4     .15       0  5170.3     .17       0
Bank Sta=4973.9,5014.4
XS Rating Curve= 0 ,0
Exp/Cntr=0.3,0.1

Type RM Length L Ch R = 1 ,605     ,0,0,0
BEGIN DESCRIPTION:
LAKE CREEK TRIBUTARY NO. 8. 2 1.0
END DESCRIPTION:
XS GIS Cut Line= 4
      3732216.34     10171041.11      3731542.73     10171485.56
      3731535.79     10171666.11      3732117.83     10172061.06
#Sta/Elev= 30
  4071.6  282.94  4099.3  282.67  4105.7  281.62  4192.6  277.61  4279.9  270.86
    4301  270.21    4316  267.56  4440.8  260.35  4662.2  259.86  4683.3  258.96
  4770.6  260.03  4872.5  259.27  4954.2  261.36  4964.2  260.23  4992.5  257.17
  5014.2   260.2    5086   262.2  5099.5  261.13  5186.3  260.46  5222.2  260.99
  5288.1  264.04  5307.1  262.17    5324  262.83  5330.1  264.84    5339  265.83
  5388.1  265.78  5424.4  267.56  5467.8  267.54  5610.9  272.24  5762.7  278.89
#Mann= 6 ,-1 , 0
  4071.6     .17       0  4440.8     .15       0  4964.2     .06       0
  5014.2     .15       0  5307.1     .17       0  5610.9     .15       0
Bank Sta=4964.2,5014.2
XS Rating Curve= 0 ,0
Exp/Cntr=0.3,0.1

Chan Stop Cuts=-1
Use User Specified Reach Order=0
Composite Channel Slope=5