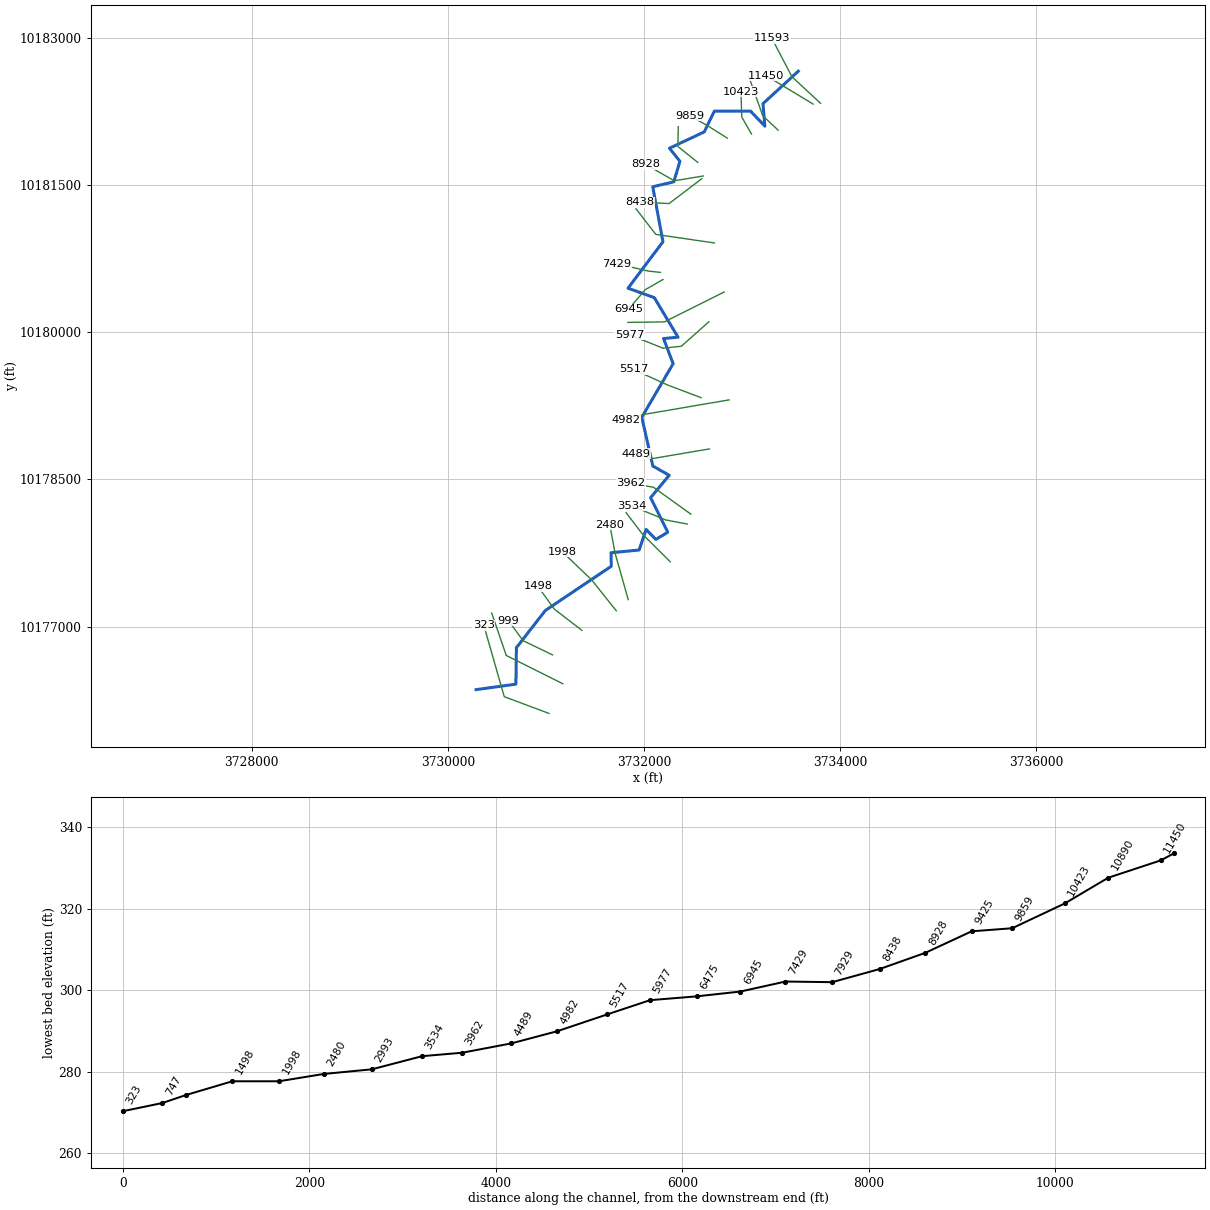
--- LAKE CREEK TRIBUTARY NO 8 4.prj (project) ---

Proj Title=LAKE CREEK TRIBUTARY NO 8 4 Base Level Engineering
Current Plan=p01
Default Exp/Contr=0.3,0.1
English Units
Geom File=g01
Flow File=f01
Plan File=p01
Y Axis Title=Elevation
X Axis Title(PF)=Main Channel Distance
X Axis Title(XS)=Station
BEGIN DESCRIPTION:
LAKE CREEK TRIBUTARY NO 8 4
END DESCRIPTION:
DSS Export Rating Curves= 0
DSS Export Rating Curve Sorted= 0
DSS Export Volume Flow Curves= 0
DXF OffsetX= 0
DXF OffsetY= 0
DXF ScaleX= 1
DXF ScaleY= 10

--- LAKE CREEK TRIBUTARY NO 8 4.p01 (plan) ---

Plan Title=Multiple Run
Short Identifier=Multiple
Geom File=g01
Flow File=f01
Subcritical Flow
K Sum by GR= 0
Std Step Tol= 0.01
Critical Tol= 0.01
Num of Std Step Trials= 20
Max Error Tol= 0.3
Flow Tol Ratio= 0.001
Split Flow NTrial= 30
Split Flow Tol= 0.02
Split Flow Ratio= 0.02
Log Output Level= 0
Friction Slope Method= 1
Unsteady Friction Slope Method= 2
Unsteady Bridges Friction Slope Method= 1
Parabolic Critical Depth
Global Vel Dist=  1 , 1 , 1
Global Log Level= 0
CheckData=True
Encroach Param= -1, 0, 0, 0
BEGIN DESCRIPTION:
Multiple Run
END DESCRIPTION:

--- LAKE CREEK TRIBUTARY NO 8 4.f01 (steady flow) ---

Flow Title=Multiple
Program Version=4.10
Number of Profiles= 7
Profile Names=10-year,25-year,50-year,1pct_min,100-year,1pct_plu,500-year
River Rch & RM=LAKE CREEK TRIBU,Reach-1         ,11593
     619     837    1130     502    1517    4581    2824
Boundary for River Rch & Prof#=LAKE CREEK TRIBU,Reach-1         , 1
Up Type= 0
Dn Type= 3
Dn Slope=0.005
Boundary for River Rch & Prof#=LAKE CREEK TRIBU,Reach-1         , 2
Up Type= 0
Dn Type= 3
Dn Slope=0.005
Boundary for River Rch & Prof#=LAKE CREEK TRIBU,Reach-1         , 3
Up Type= 0
Dn Type= 3
Dn Slope=0.005
Boundary for River Rch & Prof#=LAKE CREEK TRIBU,Reach-1         , 4
Up Type= 0
Dn Type= 3
Dn Slope=0.005
Boundary for River Rch & Prof#=LAKE CREEK TRIBU,Reach-1         , 5
Up Type= 0
Dn Type= 3
Dn Slope=0.005
Boundary for River Rch & Prof#=LAKE CREEK TRIBU,Reach-1         , 6
Up Type= 0
Dn Type= 3
Dn Slope=0.005
Boundary for River Rch & Prof#=LAKE CREEK TRIBU,Reach-1         , 7
Up Type= 0
Dn Type= 3
Dn Slope=0.005
DSS Import GetInterval= 0
DSS Import GetPeak= 0
DSS Import FillOption= 0

--- LAKE CREEK TRIBUTARY NO 8 4.g01 (geometry) ---

Geom Title=Existing Conditions
Program Version=4.10

River Reach=LAKE CREEK TRIBU,Reach-1
Reach XY= 30
      3733573.23     10182661.84      3733213.74     10182331.36
       3733232.9     10182101.66      3733086.46     10182255.21
      3732717.47     10182254.37      3732614.48     10182043.21
      3732260.19     10181876.84      3732366.82     10181743.75
      3732304.14     10181533.91       3732089.5     10181484.32
      3732193.84     10180923.62      3731837.74     10180449.71
      3732105.33     10180353.95      3732347.94     10179950.43
      3732200.12     10179936.42      3732297.51     10179680.14
      3731978.08     10179134.54       3732090.6     10178636.83
      3732257.47     10178542.47       3732067.9     10178314.11
      3732242.85     10177962.17      3732121.39     10177888.13
      3732022.07     10177990.26       3731950.7     10177780.45
      3731664.95     10177752.89      3731666.81       10177615.
      3730995.12     10177164.26      3730699.68     10176785.14
       3730694.6     10176413.04      3730288.23     10176356.84

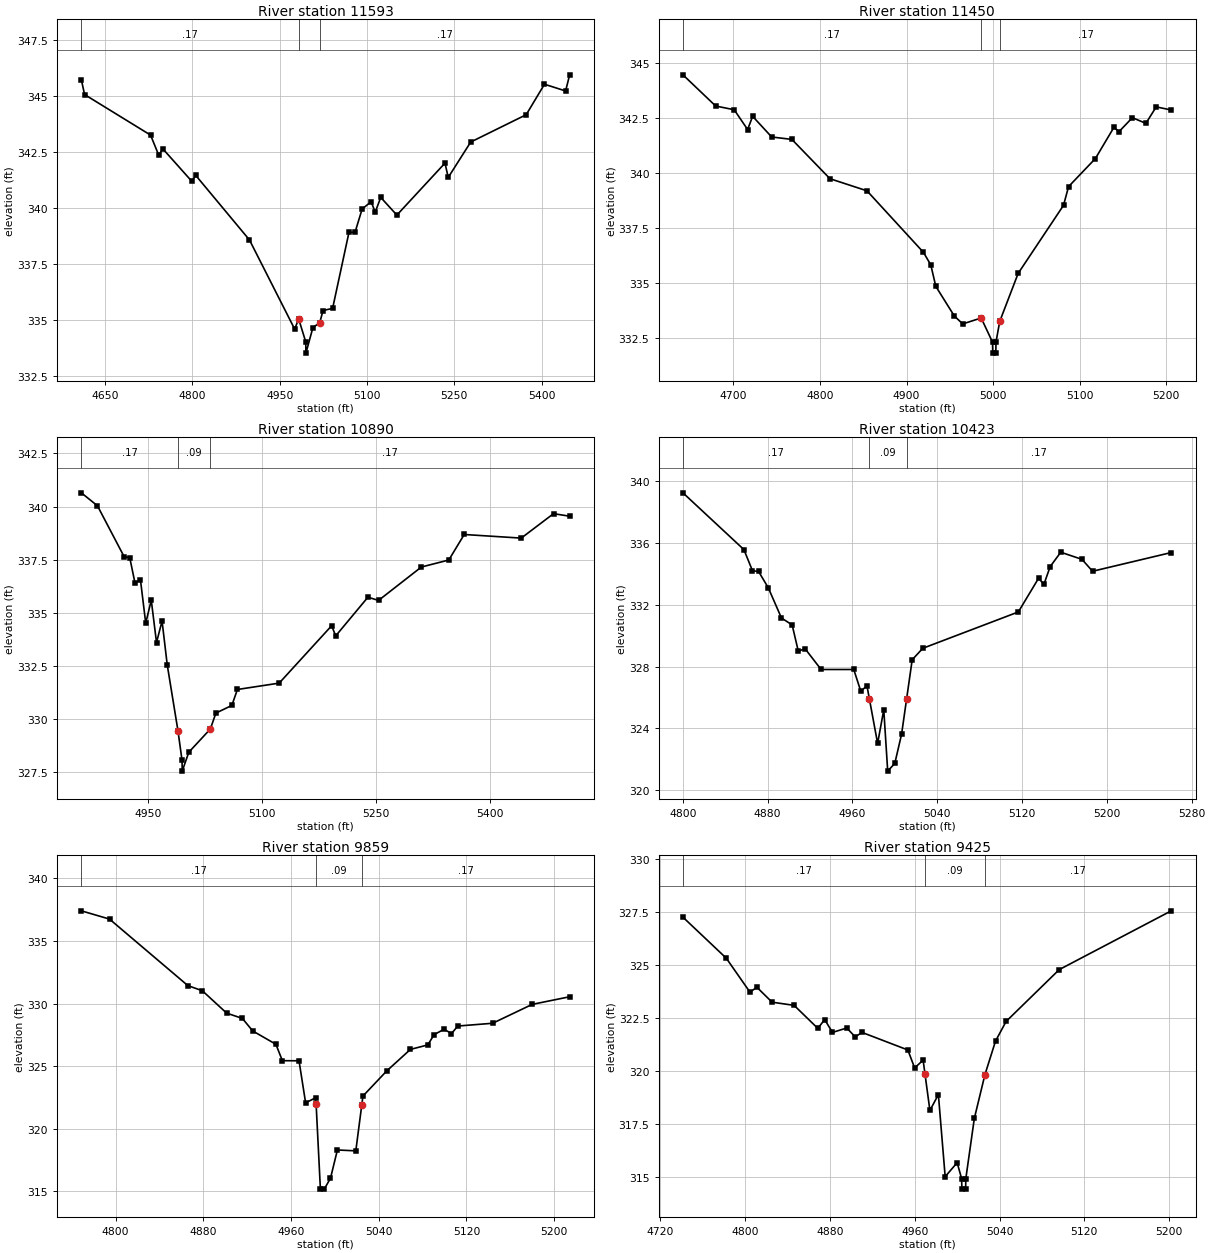
Type RM Length L Ch R = 1 ,11593   ,143,143,143
BEGIN DESCRIPTION:
LAKE CREEK TRIBUTARY NO. 8. 4 23.0
END DESCRIPTION:
XS GIS Cut Line= 3
      3733800.25     10182335.31      3733508.56     10182606.17
      3733304.34     10182997.31
#Sta/Elev= 30
    4609  345.72  4614.6  345.06    4728  343.25  4742.1  342.35    4749  342.64
  4798.8  341.19  4805.7  341.45    4898  338.57  4975.7  334.59  4982.5  335.05
  4994.7  334.02    4995  333.52    5007  334.66  5018.8  334.88  5024.4  335.42
  5040.9  335.52    5069  338.91  5079.4  338.91  5091.6  339.95  5107.1  340.28
  5114.1  339.81  5123.6  340.47  5151.3  339.68    5234     342  5239.6  341.36
  5278.2  342.94  5373.6  344.16    5405  345.52  5441.3  345.22  5448.3  345.94
#Mann= 3 , 0 , 0
    4609     .17       0  4982.5     .09       0  5018.8     .17       0
Bank Sta=4982.5,5018.8
XS Rating Curve= 0 ,0
Exp/Cntr=0.3,0.1

Type RM Length L Ch R = 1 ,11450   ,560,560,560
BEGIN DESCRIPTION:
Mapping XS c974f31a
END DESCRIPTION:
XS GIS Cut Line= 2
      3733725.54     10182326.68      3733242.92     10182618.33
#Sta/Elev= 30
  4641.8  344.46  4679.6  343.04    4701  342.87  4716.5  341.97  4722.3  342.57
  4744.3  341.63  4767.6  341.52  4811.6  339.73  4854.3  339.18  4919.5  336.38
    4928  335.81  4933.8  334.83  4955.2  333.48  4964.9  333.12  4986.2  333.39
  4999.3  332.29  4999.6  331.79  5003.1  331.79  5003.3  332.29  5007.6  333.23
  5028.9  335.42  5081.3  338.52  5087.1  339.37  5118.1  340.65  5139.5  342.07
  5145.3  341.87  5160.8  342.51  5176.4  342.25  5188.3     343  5205.7  342.86
#Mann= 3 , 0 , 0
  4641.8     .17       0  4986.2     .09       0  5007.6     .17       0
Bank Sta=4986.2,5007.6
XS Rating Curve= 0 ,0
Exp/Cntr=0.3,0.1

Type RM Length L Ch R = 1 ,10890   ,467,467,467
BEGIN DESCRIPTION:
LAKE CREEK TRIBUTARY NO. 8. 4 22.0
END DESCRIPTION:
XS GIS Cut Line= 3
      3733367.82      10182061.1      3733211.13     10182208.65
      3733067.85     10182611.08
#Sta/Elev= 30
  4862.1  340.65  4883.3  340.04  4918.5  337.64  4925.8   337.6  4932.6  336.42
  4939.9  336.55  4946.8  334.52  4954.1   335.6    4961  333.61  4968.3  334.62
  4975.1  332.56  4989.3  329.44  4994.6  328.06  4994.8  327.56  5003.5  328.45
  5031.8  329.54  5039.1  330.29  5060.1  330.65  5067.4   331.4  5122.4   331.7
  5191.4   334.4  5196.7  333.92  5239.1  335.74  5253.1  335.59  5309.4  337.16
  5345.5  337.49  5365.8  338.69  5440.8  338.52  5483.3  339.67  5504.5  339.55
#Mann= 3 , 0 , 0
  4862.1     .17       0  4989.3     .09       0  5031.8     .17       0
Bank Sta=4989.3,5031.8
XS Rating Curve= 0 ,0
Exp/Cntr=0.3,0.1

Type RM Length L Ch R = 1 ,10423   ,564,564,564
BEGIN DESCRIPTION:
LAKE CREEK TRIBUTARY NO. 8. 4 21.0
END DESCRIPTION:
XS GIS Cut Line= 3
      3733096.54     10182021.17       3732997.4     10182194.65
      3732988.91     10182455.21
#Sta/Elev= 30
  4800.2  339.23  4857.7  335.56  4865.8  334.19  4871.5  334.15  4880.7  333.09
  4893.1  331.14  4903.2  330.69    4909  328.99  4915.3  329.16  4930.5  327.81
  4961.3  327.81    4968  326.39  4973.7  326.77 4976.02325.9109  4983.8  323.03
  4989.6  325.21  4993.3  321.24    5000  321.74  5006.4  323.63 5011.11325.8955
  5016.4  328.44  5026.4  329.18  5116.5  331.53  5135.6  333.71  5140.6  333.31
  5146.5  334.46  5156.5  335.39  5176.5  334.93  5186.5  334.16  5260.7  335.37
#Mann= 3 , 0 , 0
  4800.2     .17       0 4976.02     .09       0 5011.11     .17       0
Bank Sta=4976.02,5011.11
XS Rating Curve= 0 ,0
Exp/Cntr=0.3,0.1

Type RM Length L Ch R = 1 ,9859    ,434,434,434
BEGIN DESCRIPTION:
LAKE CREEK TRIBUTARY NO. 8. 4 20.0
END DESCRIPTION:
XS GIS Cut Line= 3
        3732850.     10181979.49      3732652.11     10182104.48
       3732468.1     10182208.63
#Sta/Elev= 30
  4768.7  337.41  4794.4  336.75  4865.9  331.43  4879.1  331.02  4901.3  329.23
  4915.6  328.81    4925  327.81  4946.2  326.74  4952.1  325.43  4967.3  325.42
  4973.3  322.06  4982.6  322.47 4982.91321.9286  4986.8  315.16  4990.3  315.16
    4996  316.03  5002.3  318.29  5019.1  318.22 5024.52321.8722  5025.6   322.6
  5047.2   324.6  5068.9  326.33  5084.8  326.69  5090.5  327.51  5099.6  327.94
  5106.4   327.6  5112.2   328.2  5143.9  328.42    5180  329.93  5214.2  330.54
#Mann= 3 , 0 , 0
  4768.7     .17       0 4982.91     .09       0 5024.52     .17       0
Bank Sta=4982.91,5024.52
XS Rating Curve= 0 ,0
Exp/Cntr=0.3,0.1

Type RM Length L Ch R = 1 ,9425    ,497,497,497
BEGIN DESCRIPTION:
LAKE CREEK TRIBUTARY NO. 8. 4 19.0
END DESCRIPTION:
XS GIS Cut Line= 3
      3732547.91     10181732.98      3732346.09     10181894.83
      3732350.01      10182096.8
#Sta/Elev= 30
  4741.3  327.27  4782.2  325.33  4804.6  323.72    4811  323.96  4825.4  323.25
  4846.2   323.1  4868.6  322.01    4875  322.43  4882.4  321.82  4895.9  322.03
  4903.8  321.61  4910.3  321.82  4953.5  320.99  4959.9  320.14  4967.9  320.51
  4969.7319.8405  4974.3  318.13  4982.3  318.88  4988.7     315    5000  315.66
  5004.2  314.91  5004.5  314.41    5008  314.41  5008.2  314.91  5016.2  317.75
  5026.2  319.82  5036.2  321.41  5046.2  322.34  5096.3  324.79    5202  327.57
#Mann= 3 , 0 , 0
  4741.3     .17       0  4969.7     .09       0  5026.2     .17       0
Bank Sta=4969.7,5026.2
XS Rating Curve= 0 ,0
Exp/Cntr=0.3,0.1

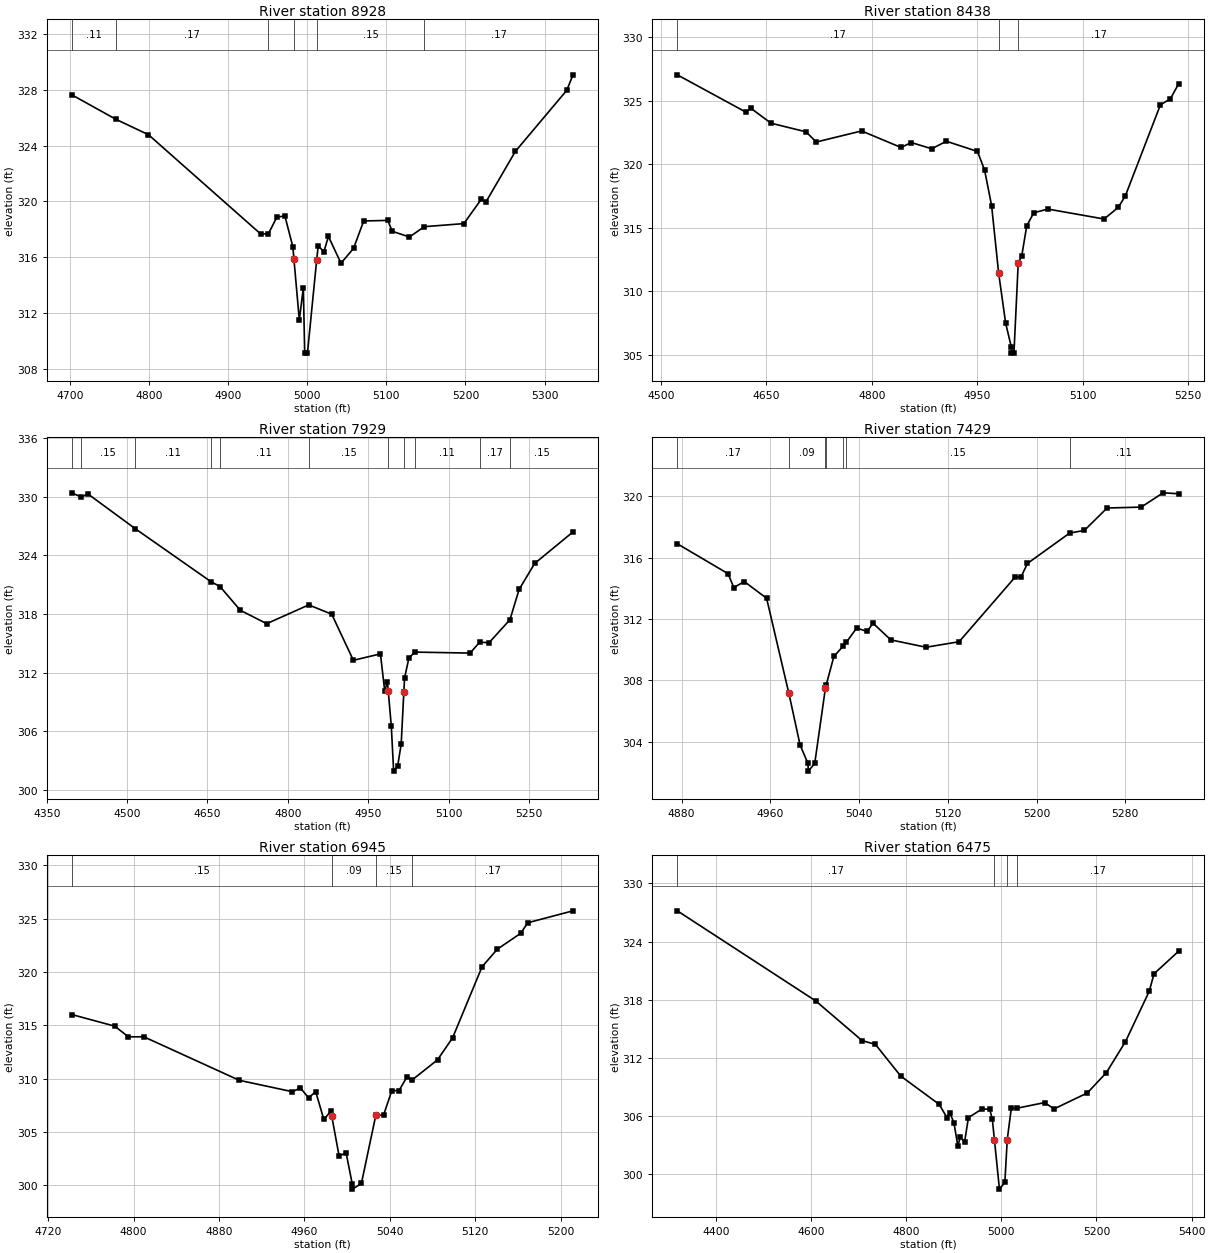
Type RM Length L Ch R = 1 ,8928    ,490,490,490
BEGIN DESCRIPTION:
LAKE CREEK TRIBUTARY NO. 8. 4 18.0
END DESCRIPTION:
XS GIS Cut Line= 3
      3732603.53     10181594.07      3732309.92     10181544.94
      3732017.86     10181711.07
#Sta/Elev= 30
  4702.3  327.64  4758.6  325.87  4799.3  324.78  4941.3  317.66    4951  317.69
  4961.5  318.86  4971.7  318.97  4981.8  316.76 4983.22315.8506    4990  311.51
  4995.1  313.81  4996.8  309.13  5000.3  309.13    5012315.8382  5013.9  316.81
  5021.1   316.4  5026.8  317.49  5042.7  315.57  5058.6  316.64  5071.4   318.6
  5101.8  318.64  5107.5  317.86  5129.2  317.45    5148  318.19    5198  318.41
    5220  320.15  5225.7  319.94  5263.2  323.59  5328.1  327.96    5336  329.07
#Mann= 6 ,-1 , 0
  4702.3     .11       0  4758.6     .17       0    4951     .15       0
 4983.22     .09       0    5012     .15       0    5148     .17       0
Bank Sta=4983.22,5012
XS Rating Curve= 0 ,0
Exp/Cntr=0.3,0.1

Type RM Length L Ch R = 1 ,8438    ,509,509,509
BEGIN DESCRIPTION:
LAKE CREEK TRIBUTARY NO. 8. 4 17.0
END DESCRIPTION:
XS GIS Cut Line= 3
      3732589.57     10181566.26      3732256.27     10181312.81
      3731962.02     10181326.66
#Sta/Elev= 30
  4523.3  327.02  4621.2  324.08  4627.5  324.41  4656.6  323.22  4706.5  322.54
    4721  321.74  4785.5  322.61  4841.7  321.31  4856.2   321.7  4885.3  321.21
  4906.1   321.8  4950.4     321  4960.5  319.54  4970.5  316.75  4980.5  311.45
  4990.5   307.5  4998.5  305.65  4998.8  305.15  5002.3  305.15  5008.4  312.24
  5013.4  312.79  5020.5  315.15  5030.5  316.18  5050.6  316.47  5130.6  315.69
  5150.7   316.6  5160.7  317.49  5210.7  324.66  5224.9  325.13  5236.6  326.31
#Mann= 3 , 0 , 0
  4523.3     .17       0  4980.5     .09       0  5008.4     .17       0
Bank Sta=4980.5,5008.4
XS Rating Curve= 0 ,0
Exp/Cntr=0.3,0.1

Type RM Length L Ch R = 1 ,7929    ,500,500,500
BEGIN DESCRIPTION:
LAKE CREEK TRIBUTARY NO. 8. 4 16.0
END DESCRIPTION:
XS GIS Cut Line= 3
      3732717.83     10180911.08      3732120.89     10180998.45
      3731917.82     10181261.11
#Sta/Elev= 30
  4396.7  330.41  4414.9  329.97  4426.6  330.31  4515.2  326.74  4656.7  321.31
  4673.4  320.82  4711.2  318.39  4760.5  317.02  4838.9  318.94  4881.8  317.99
  4922.2  313.27  4972.7  313.93  4980.7  310.12  4985.7   311.1  4987.3310.0942
    4993  306.51  4997.3  301.93  5004.8  302.43  5011.4   304.7  5016.4310.0569
  5017.7  311.45  5025.9  313.54  5037.3  314.11    5140  314.01  5157.9  315.13
  5175.3  315.07  5214.3  317.42  5231.4  320.52  5260.4  323.18    5332  326.41
#Mann= 11 ,-1 , 0
  4396.7     .17       0  4414.9     .15       0  4515.2     .11       0
  4656.7     .17       0  4673.4     .11       0  4838.9     .15       0
  4987.3     .09       0  5016.4     .15       0  5037.3     .11       0
  5157.9     .17       0  5214.3     .15       0
Bank Sta=4987.3,5016.4
XS Rating Curve= 0 ,0
Exp/Cntr=0.3,0.1

Type RM Length L Ch R = 1 ,7429    ,484,484,484
BEGIN DESCRIPTION:
LAKE CREEK TRIBUTARY NO. 8. 4 15.0
END DESCRIPTION:
XS GIS Cut Line= 3
      3732167.88     10180611.07       3732044.7     10180624.44
      3731725.01     10180698.23
#Sta/Elev= 30
  4876.1   316.9  4921.9  314.95    4927  314.05  4936.5  314.44  4956.6  313.35
  4976.7  307.15  4986.8  303.79  4993.9  302.59  4994.2  302.09    5000  302.59
  5009.7  307.53  5010.3  307.69  5017.3  309.57  5025.9  310.25  5028.5  310.48
  5037.8  311.41  5047.3  311.19  5052.5  311.73  5068.6  310.64  5100.4  310.16
  5130.2  310.52  5180.7  314.73  5185.9  314.72  5191.8  315.62  5229.9   317.6
  5243.1  317.77  5263.6  319.23  5294.4  319.29  5314.1  320.22  5328.1  320.16
#Mann= 7 ,-1 , 0
  4876.1     .17       0  4976.7     .09       0  5009.7     .17       0
  5010.3     .15       0  5025.9     .17       0  5028.5     .15       0
  5229.9     .11       0
Bank Sta=4976.7,5009.7
XS Rating Curve= 0 ,0
Exp/Cntr=0.3,0.1

Type RM Length L Ch R = 1 ,6945    ,470,470,470
BEGIN DESCRIPTION:
LAKE CREEK TRIBUTARY NO. 8. 4 14.0
END DESCRIPTION:
XS GIS Cut Line= 3
      3732193.79     10180538.52      3732013.22     10180434.34
      3731843.06      10180236.4
#Sta/Elev= 30
  4742.1  316.01  4782.4  314.92  4795.1  313.92  4809.7  313.92    4899  309.84
  4948.8  308.77  4956.3  309.12    4964  308.19  4970.6  308.78  4978.2  306.17
  4984.8  306.93 4985.53306.5337  4992.5  302.75  4999.1  303.02  5004.8  300.13
    5005  299.63  5013.4  300.16  5026.9306.5592  5034.2  306.58  5041.9  308.88
  5048.5  308.86  5056.1  310.16  5060.9  309.87  5084.7  311.76  5098.9  313.84
  5126.4  320.49  5140.7  322.14  5162.6  323.63  5169.2  324.62  5211.6  325.74
#Mann= 4 ,-1 , 0
  4742.1     .15       0 4985.53     .09       0  5026.9     .15       0
  5060.9     .17       0
Bank Sta=4985.53,5026.9
XS Rating Curve= 0 ,0
Exp/Cntr=0.3,0.1

Type RM Length L Ch R = 1 ,6475    ,498,498,498
BEGIN DESCRIPTION:
LAKE CREEK TRIBUTARY NO. 8. 4 13.0
END DESCRIPTION:
XS GIS Cut Line= 3
      3732817.81     10180411.05      3732208.74      10180106.2
      3731836.18     10180101.01
#Sta/Elev= 30
  4318.9  327.17  4609.6  317.88  4707.2  313.78  4735.2  313.39  4788.5  310.12
  4869.3   307.2  4886.1   305.8  4891.7  306.35  4900.4  305.28  4908.4  302.95
    4914  303.82  4922.7  303.31  4930.8  305.83  4958.7   306.7  4975.5  306.71
  4981.1  305.64 4985.44303.5449    4996  298.45  5007.4  299.15  5012.4  303.55
  5020.9   306.8  5031.9  306.79  5090.9  307.38  5110.9  306.73  5180.9  308.38
  5220.9  310.48  5260.9  313.67  5310.9  318.87  5320.9  320.67  5372.6     323
#Mann= 4 ,-1 , 0
  4318.9     .17       0 4985.44     .09       0  5012.4     .15       0
  5031.9     .17       0
Bank Sta=4985.44,5012.4
XS Rating Curve= 0 ,0
Exp/Cntr=0.3,0.1

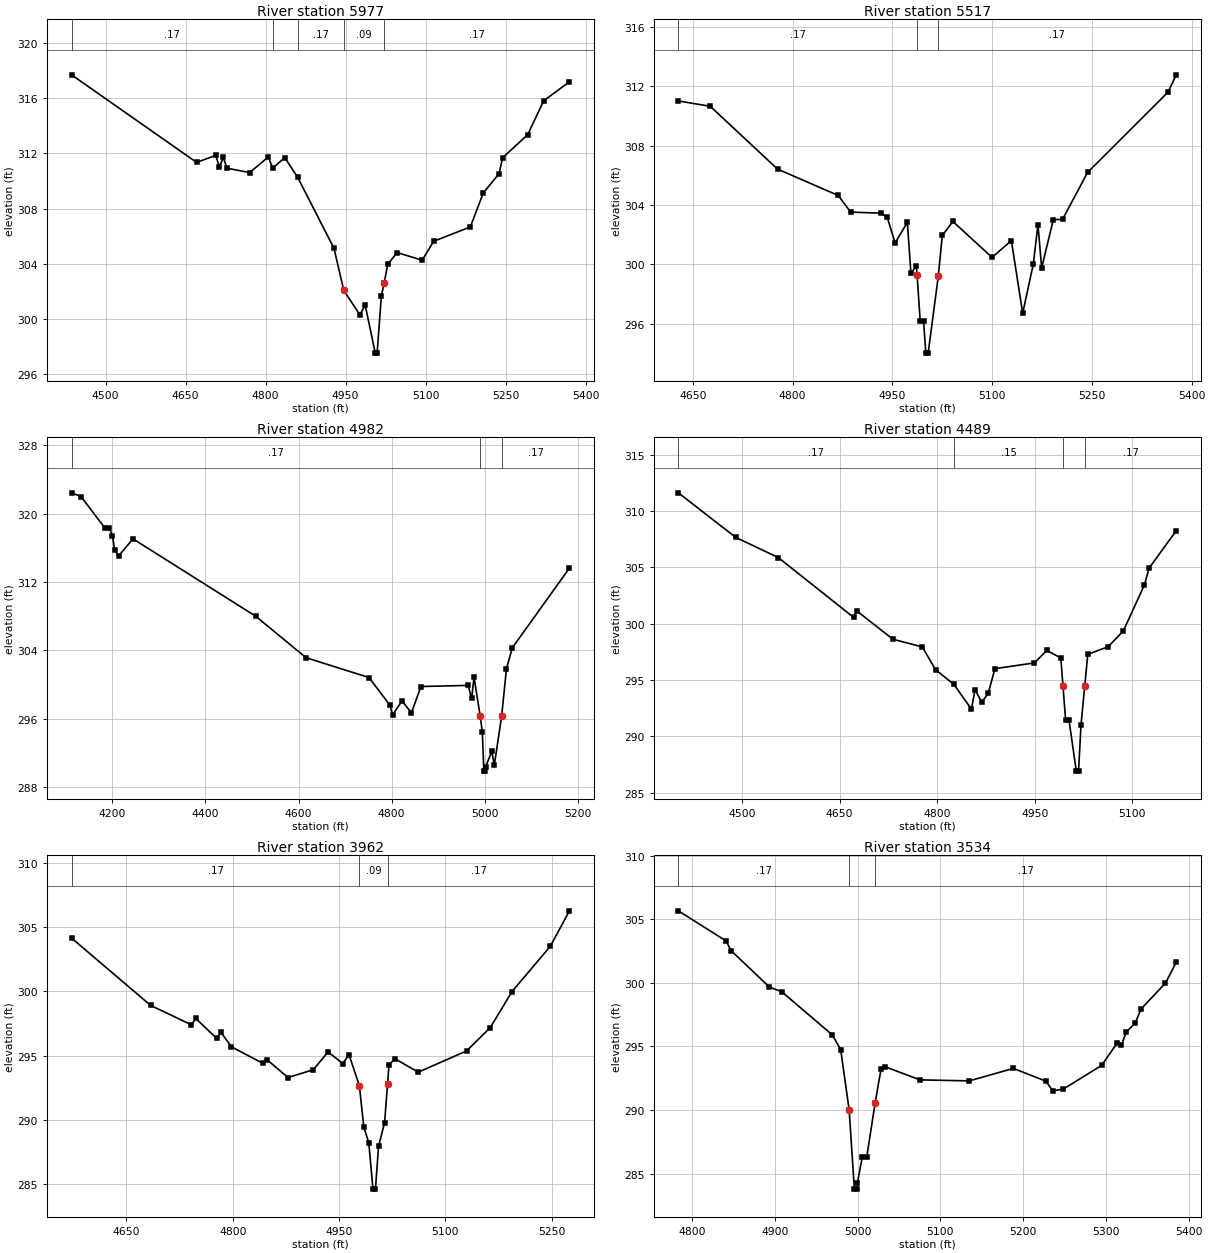
Type RM Length L Ch R = 1 ,5977    ,460,460,460
BEGIN DESCRIPTION:
LAKE CREEK TRIBUTARY NO. 8. 4 12.0
END DESCRIPTION:
XS GIS Cut Line= 4
      3732662.49     10180107.92      3732381.27     10179857.95
      3732194.77     10179838.18       3731851.4     10179975.46
#Sta/Elev= 30
  4436.2   317.7  4670.7  311.35  4706.6  311.86  4713.3  311.01  4720.8  311.71
  4727.5  310.93  4770.2  310.61  4805.3  311.75  4813.3  310.93    4836   311.7
  4860.1  310.27  4928.3  305.12  4946.6  302.08  4976.8   300.3  4986.8     301
  5005.7  297.52  5009.2  297.52  5017.1  301.67  5022.4  302.61    5029  303.95
  5046.7  304.81  5093.6  304.26  5115.2  305.63    5184  306.67  5208.3  309.14
  5237.9  310.53  5244.4  311.68  5291.7  313.37  5321.4  315.81  5369.8   317.2
#Mann= 5 ,-1 , 0
  4436.2     .17       0  4813.3     .15       0  4860.1     .17       0
  4946.6     .09       0  5022.4     .17       0
Bank Sta=4946.6,5022.4
XS Rating Curve= 0 ,0
Exp/Cntr=0.3,0.1

Type RM Length L Ch R = 1 ,5517    ,535,535,535
BEGIN DESCRIPTION:
LAKE CREEK TRIBUTARY NO. 8. 4 11.0
END DESCRIPTION:
XS GIS Cut Line= 3
      3732582.69     10179333.64      3732242.38     10179462.12
      3731892.24     10179621.59
#Sta/Elev= 30
  4628.4  311.01  4676.3  310.65  4777.4  306.42  4868.7  304.64  4887.4  303.52
  4932.9  303.45  4942.5  303.16  4954.2  301.44  4972.6  302.83    4978   299.4
  4986.3   299.9 4987.22299.2935  4991.9  296.21  4996.9  296.21  5000.4  294.02
  5003.9  294.02  5019.1   299.2  5025.2  301.95  5041.1  302.89  5099.9  300.47
    5129   301.6    5146  296.71    5162  300.03    5169  302.68  5174.5  299.76
  5192.1  303.02  5205.9  303.03  5243.7   306.2  5364.4   311.6  5376.9  312.77
#Mann= 3 , 0 , 0
  4628.4     .17       0 4987.22     .09       0  5019.1     .17       0
Bank Sta=4987.22,5019.1
XS Rating Curve= 0 ,0
Exp/Cntr=0.3,0.1

Type RM Length L Ch R = 1 ,4982    ,493,493,493
BEGIN DESCRIPTION:
LAKE CREEK TRIBUTARY NO. 8. 4 10.0
END DESCRIPTION:
XS GIS Cut Line= 3
      3732867.85     10179311.07       3731992.8     10179161.78
       3731817.9     10179111.08
#Sta/Elev= 30
  4112.3  322.43  4132.6     322  4183.3  318.36  4193.5  318.32    4200  317.43
  4205.1   315.7  4213.7  315.07  4244.2  317.05  4507.9  308.01  4616.1  303.16
  4751.4  300.84  4796.6  297.59  4802.1  296.48  4822.4   298.1  4842.7  296.72
    4863  299.79  4964.4  299.92    4972   298.4  4977.1  300.89  4990.4296.3133
  4994.9   294.5  4998.2   289.9  5001.7   289.9    5002   290.4  5015.4  292.23
  5020.6  290.58  5036.4   296.3  5046.8  301.89  5059.4  304.32  5182.1  313.63
#Mann= 3 , 0 , 0
  4112.3     .17       0  4990.4     .09       0  5036.4     .17       0
Bank Sta=4990.4,5036.4
XS Rating Curve= 0 ,0
Exp/Cntr=0.3,0.1

Type RM Length L Ch R = 1 ,4489    ,527,527,527
BEGIN DESCRIPTION:
LAKE CREEK TRIBUTARY NO. 8. 4 9.0
END DESCRIPTION:
XS GIS Cut Line= 3
      3732667.83     10178811.07      3732078.18     10178711.49
      3731917.87     10178761.07
#Sta/Elev= 30
    4402   311.6  4490.1  307.65  4555.6  305.86  4671.5  300.55  4676.5  301.12
  4731.9  298.61  4777.2  297.93  4797.5  295.91  4825.9   294.6  4852.8   292.4
  4858.3  294.15  4868.5  293.02  4878.6  293.81  4888.8     296  4949.6  296.51
  4968.6  297.62  4990.2  296.95  4993.6  294.42  4997.6  291.44  5002.8  291.44
    5014  286.91  5017.5  286.91  5021.3  291.02    5027294.4455  5031.7  297.27
  5063.1  297.95  5086.3  299.34  5118.9  303.44    5126  304.92  5167.8  308.24
#Mann= 4 ,-1 , 0
    4402     .17       0  4825.9     .15       0  4993.6     .09       0
    5027     .17       0
Bank Sta=4993.6,5027
XS Rating Curve= 0 ,0
Exp/Cntr=0.3,0.1

Type RM Length L Ch R = 1 ,3962    ,428,428,428
BEGIN DESCRIPTION:
LAKE CREEK TRIBUTARY NO. 8. 4 8.0
END DESCRIPTION:
XS GIS Cut Line= 3
       3732478.5     10178146.14      3732096.55     10178420.45
      3731867.88     10178461.07
#Sta/Elev= 30
  4572.5  304.15  4684.1  298.91  4741.7   297.4  4747.8   297.9  4777.3  296.34
  4783.4  296.81  4798.1  295.69  4842.3  294.41  4848.5  294.68  4877.9   293.3
  4913.6  293.91  4934.4  295.29  4955.3  294.39  4963.9  295.09  4978.6  292.67
  4984.8  289.47  4991.9  288.22  4997.8  284.62  5001.3  284.62  5005.7  287.96
  5014.2   289.8  5018.3 292.769  5020.4  294.29  5028.8  294.76  5061.7  293.72
  5129.9  295.37  5163.3  297.19    5194  299.99    5248  303.51    5275  306.27
#Mann= 3 ,-1 , 0
  4572.5     .17       0  4978.6     .09       0  5018.3     .17       0
Bank Sta=4978.6,5018.3
XS Rating Curve= 0 ,0
Exp/Cntr=0.3,0.1

Type RM Length L Ch R = 1 ,3534    ,541,541,541
BEGIN DESCRIPTION:
LAKE CREEK TRIBUTARY NO. 8. 4 7.0
END DESCRIPTION:
XS GIS Cut Line= 3
      3732440.31     10178045.45      3732221.55     10178087.12
        3731872.     10178231.53
#Sta/Elev= 30
  4783.8  305.66  4841.4  303.29  4847.4  302.53  4893.6  299.67  4908.5   299.3
  4969.5  295.91  4979.7  294.75  4989.9     290  4996.2  283.78  4999.7  283.78
  4999.9  284.28  5005.8  286.33  5011.2  286.33  5021.3  290.58  5028.3  293.19
  5033.7  293.39  5075.4  292.37  5134.8  292.29  5188.1  293.27  5226.9  292.28
  5235.9  291.51  5248.5  291.65  5294.5   293.5    5313  295.23  5318.4  295.08
  5324.3  296.13  5335.1  296.84  5342.4  297.96  5371.7  299.98  5384.7  301.63
#Mann= 3 , 0 , 0
  4783.8     .17       0  4989.9     .09       0  5021.3     .17       0
Bank Sta=4989.9,5021.3
XS Rating Curve= 0 ,0
Exp/Cntr=0.3,0.1

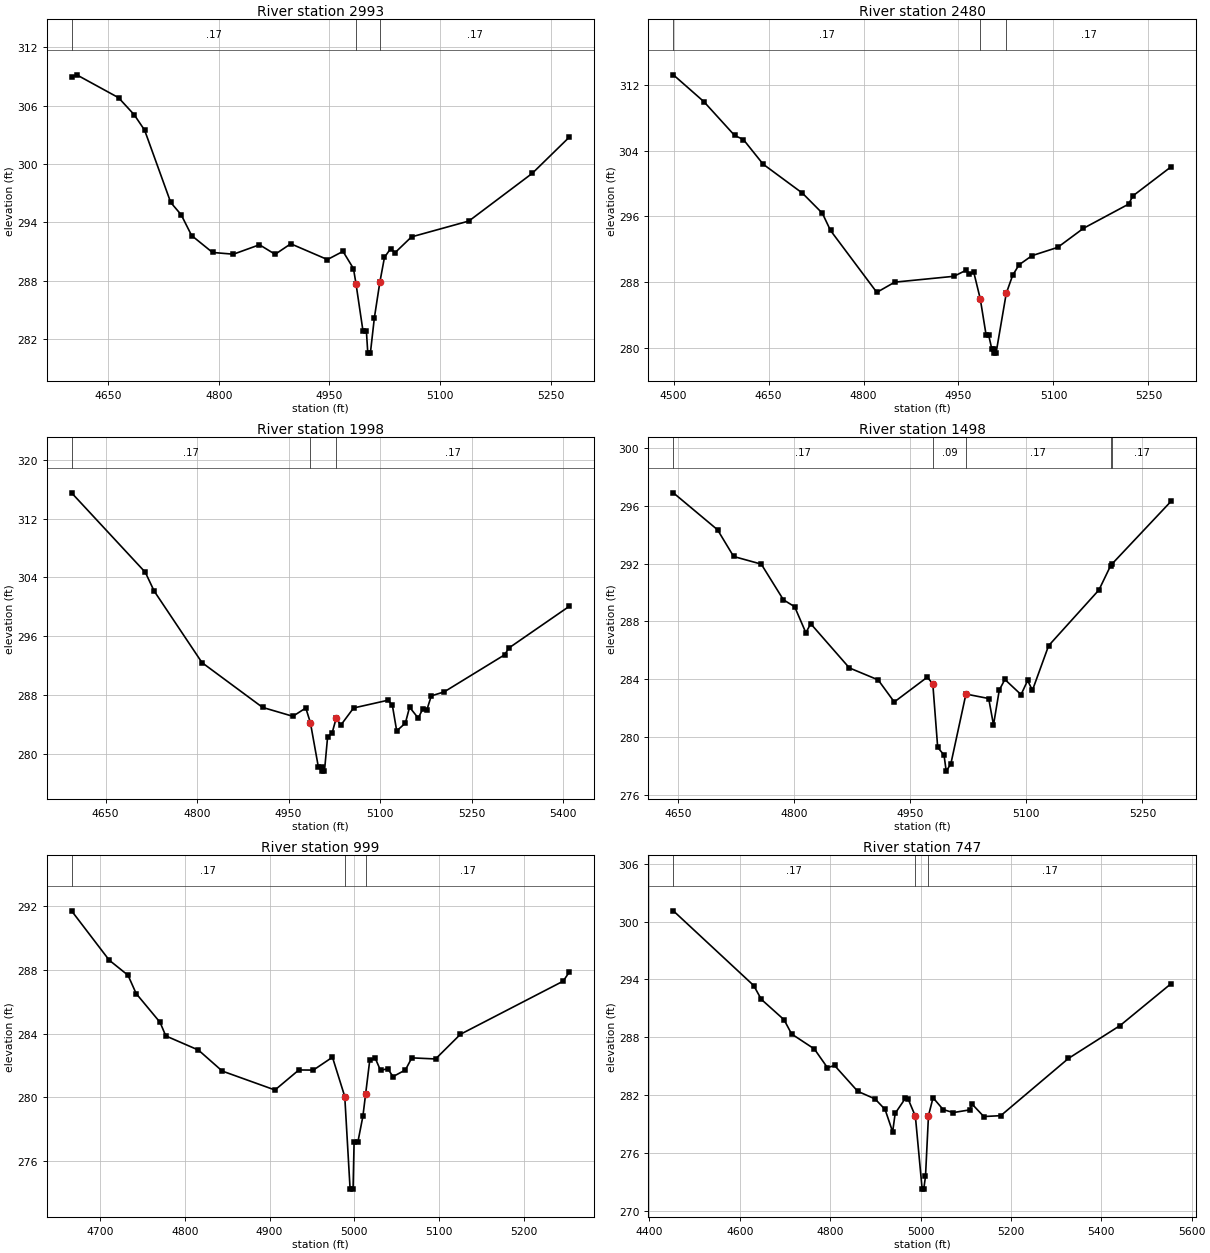
Type RM Length L Ch R = 1 ,2993    ,513,513,513
BEGIN DESCRIPTION:
LAKE CREEK TRIBUTARY NO. 8. 4 6.0
END DESCRIPTION:
XS GIS Cut Line= 3
      3732267.83      10177661.1      3731984.56     10177942.52
      3731817.84     10178161.09
#Sta/Elev= 30
  4600.7  308.94  4607.7  309.16  4664.3  306.81  4685.5  305.06  4699.6  303.48
    4735  296.04  4749.2  294.77  4763.3  292.64  4791.6   290.9  4819.9  290.72
  4855.2  291.69  4876.4  290.71  4897.6  291.79  4947.2  290.17  4968.3  291.01
  4982.5  289.24 4985.88287.7024  4995.4  282.82    5000  282.82  5001.9  280.55
  5005.4  280.55  5010.8  284.18  5018.2  287.83  5024.5   290.4  5032.7  291.28
    5039  290.89  5061.1   292.5  5138.8  294.13  5224.6  299.03  5274.9  302.76
#Mann= 3 , 0 , 0
  4600.7     .17       0 4985.88     .09       0  5018.2     .17       0
Bank Sta=4985.88,5018.2
XS Rating Curve= 0 ,0
Exp/Cntr=0.3,0.1

Type RM Length L Ch R = 1 ,2480    ,482,482,482
BEGIN DESCRIPTION:
LAKE CREEK TRIBUTARY NO. 8. 4 5.0
END DESCRIPTION:
XS GIS Cut Line= 3
       3731839.6     10177274.63      3731704.19     10177753.79
      3731652.33     10178037.26
#Sta/Elev= 30
  4499.7  313.18    4548  309.92  4596.4  305.83  4610.3  305.33  4641.5  302.34
  4703.5  298.83    4735  296.39  4747.9   294.3    4821  286.79  4849.3  288.03
  4942.8  288.74  4962.1  289.48  4967.3  288.99    4974  289.27  4984.4  285.99
  4993.6  281.62  4997.6  281.62  5002.5  279.95  5005.6  279.92  5005.8  279.42
  5009.3  279.42  5025.4  286.66  5035.5  288.86  5045.7  290.14    5066  291.24
  5106.7  292.25  5147.3  294.56  5218.5  297.49  5225.5   298.5  5285.8  302.03
#Mann= 3 , 0 , 0
  4499.7     .17       0  4984.4     .09       0  5025.4     .17       0
Bank Sta=4984.4,5025.4
XS Rating Curve= 0 ,0
Exp/Cntr=0.3,0.1

Type RM Length L Ch R = 1 ,1998    ,500,500,500
BEGIN DESCRIPTION:
LAKE CREEK TRIBUTARY NO. 8. 4 4.0
END DESCRIPTION:
XS GIS Cut Line= 3
      3731717.87     10177161.05       3731464.8     10177478.14
      3731167.82      10177761.1
#Sta/Elev= 30
  4594.3  315.53  4715.2   304.7  4729.6  302.16  4808.1   292.4  4907.4   286.3
    4957  285.09  4978.2  286.22  4985.8   284.2  4998.7  278.23  5005.1  278.12
  5005.3  277.62  5008.8  277.62    5014  282.32  5021.2  282.77  5028.2  284.88
  5035.4  283.86  5056.5  286.22  5113.1  287.28  5120.1  286.58  5127.2   283.1
  5141.4  284.16  5148.3  286.33  5162.5  284.84  5169.7  286.06  5176.6  285.96
  5183.9  287.87  5204.9  288.41    5304  293.46  5311.2   294.4  5410.2  300.08
#Mann= 3 , 0 , 0
  4594.3     .17       0  4985.8     .09       0  5028.2     .17       0
Bank Sta=4985.8,5028.2
XS Rating Curve= 0 ,0
Exp/Cntr=0.3,0.1

Type RM Length L Ch R = 1 ,1498    ,499,499,499
BEGIN DESCRIPTION:
LAKE CREEK TRIBUTARY NO. 8. 4 3.0
END DESCRIPTION:
XS GIS Cut Line= 3
      3731367.84     10176961.08      3731085.74     10177178.23
      3730917.82     10177411.11
#Sta/Elev= 30
    4644   296.9  4701.1  294.34  4721.9  292.49  4757.6  291.96  4786.2  289.49
  4800.7  289.01  4815.2  287.21  4821.5  287.83  4871.4  284.77  4908.6  283.94
  4929.4  282.41  4972.1  284.13  4979.2  283.66  4985.5  279.27  4993.7  278.73
  4996.5  277.62  5002.5  278.12    5022  282.96  5051.4  282.65  5057.6  280.82
  5065.1  283.24  5072.3  283.97  5093.2  282.92  5101.7   283.9  5107.9  283.22
  5128.8  286.31  5193.8  290.17  5208.8  291.84  5211.2     292  5287.1  296.32
#Mann= 5 ,-1 , 0
    4644     .17       0  4979.2     .09       0    5022     .17       0
  5208.8     .11       0  5211.2     .17       0
Bank Sta=4979.2,5022
XS Rating Curve= 0 ,0
Exp/Cntr=0.3,0.1

Type RM Length L Ch R = 1 ,999     ,252,252,252
BEGIN DESCRIPTION:
LAKE CREEK TRIBUTARY NO. 8. 4 2.0
END DESCRIPTION:
XS GIS Cut Line= 3
      3731067.83     10176711.08      3730767.64     10176856.38
      3730617.88     10177061.03
#Sta/Elev= 30
  4666.5  291.72  4710.9  288.62  4733.1  287.67  4742.7  286.52  4770.9  284.71
  4777.6  283.86  4816.1  282.97  4844.2  281.65  4906.4  280.46  4934.6  281.72
  4951.6  281.71  4974.2  282.52  4988.7  280.05    4995  274.23  4998.5  274.23
  4999.7  277.17  5004.1  277.17  5010.1  278.81 5013.36280.2306  5018.2  282.34
  5024.7  282.45  5030.9  281.69  5039.4   281.8  5045.6   281.3  5060.2  281.72
  5067.8  282.48  5095.8  282.41  5125.1  283.96  5246.3   287.3  5253.6  287.88
#Mann= 3 , 0 , 0
  4666.5     .17       0  4988.7     .09       0 5013.36     .17       0
Bank Sta=4988.7,5013.36
XS Rating Curve= 0 ,0
Exp/Cntr=0.3,0.1

Type RM Length L Ch R = 1 ,747     ,424,424,424
BEGIN DESCRIPTION:
Mapping XS 0460df10
END DESCRIPTION:
XS GIS Cut Line= 3
      3731172.95     10176416.98      3730596.55     10176705.18
      3730447.77     10177137.67
#Sta/Elev= 30
  4452.8  301.11  4630.7  293.37  4647.5  291.94  4697.8  289.83  4714.6  288.35
  4764.9   286.8  4793.9  284.86  4809.6  285.09    4861  282.41  4899.1  281.63
  4921.4  280.54  4938.2  278.21  4943.8  280.13  4966.1  281.67  4972.8  281.58
  4988.5  279.83  5003.5  272.28    5007  272.28  5010.9  273.59  5017.5  279.89
  5027.6  281.75    5050  280.52  5072.4  280.21  5108.7  280.49    5114  281.09
  5139.9   279.8  5177.5  279.89  5327.3  285.82  5441.7  289.23  5554.6  293.57
#Mann= 3 , 0 , 0
  4452.8     .17       0  4988.5     .09       0  5017.5     .17       0
Bank Sta=4988.5,5017.5
XS Rating Curve= 0 ,0
Exp/Cntr=0.3,0.1

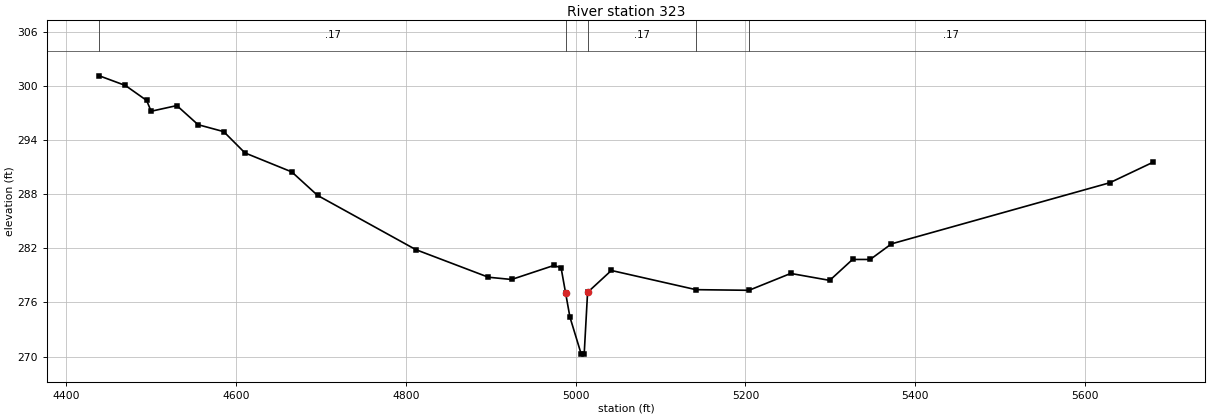
Type RM Length L Ch R = 1 ,323     ,0,0,0
BEGIN DESCRIPTION:
LAKE CREEK TRIBUTARY NO. 8. 4 1.0
END DESCRIPTION:
XS GIS Cut Line= 3
      3731030.56      10176114.9      3730575.72     10176285.04
      3730367.86     10177011.05
#Sta/Elev= 30
  4438.9  301.14  4469.6  300.07  4494.6  298.41  4499.9  297.21  4530.2  297.84
  4555.2  295.72  4585.4  294.95  4610.4  292.59  4665.6  290.48  4695.9  287.88
  4811.7  281.86  4897.2   278.8  4924.5  278.55  4974.4  280.11  4982.8  279.84
  4988.1277.0575  4993.2  274.38  5006.5  270.27    5010  270.27    5014  277.12
    5042  279.55  5141.7  277.42  5204.1  277.35  5253.3  279.22  5299.2  278.45
  5326.1  280.77  5346.9  280.77  5371.9   282.5  5629.1  289.28  5679.7  291.54
#Mann= 5 ,-1 , 0
  4438.9     .17       0  4988.1     .09       0    5014     .17       0
  5141.7     .15       0  5204.1     .17       0
Bank Sta=4988.1,5014
XS Rating Curve= 0 ,0
Exp/Cntr=0.3,0.1

Chan Stop Cuts=-1
Use User Specified Reach Order=0
Composite Channel Slope=5