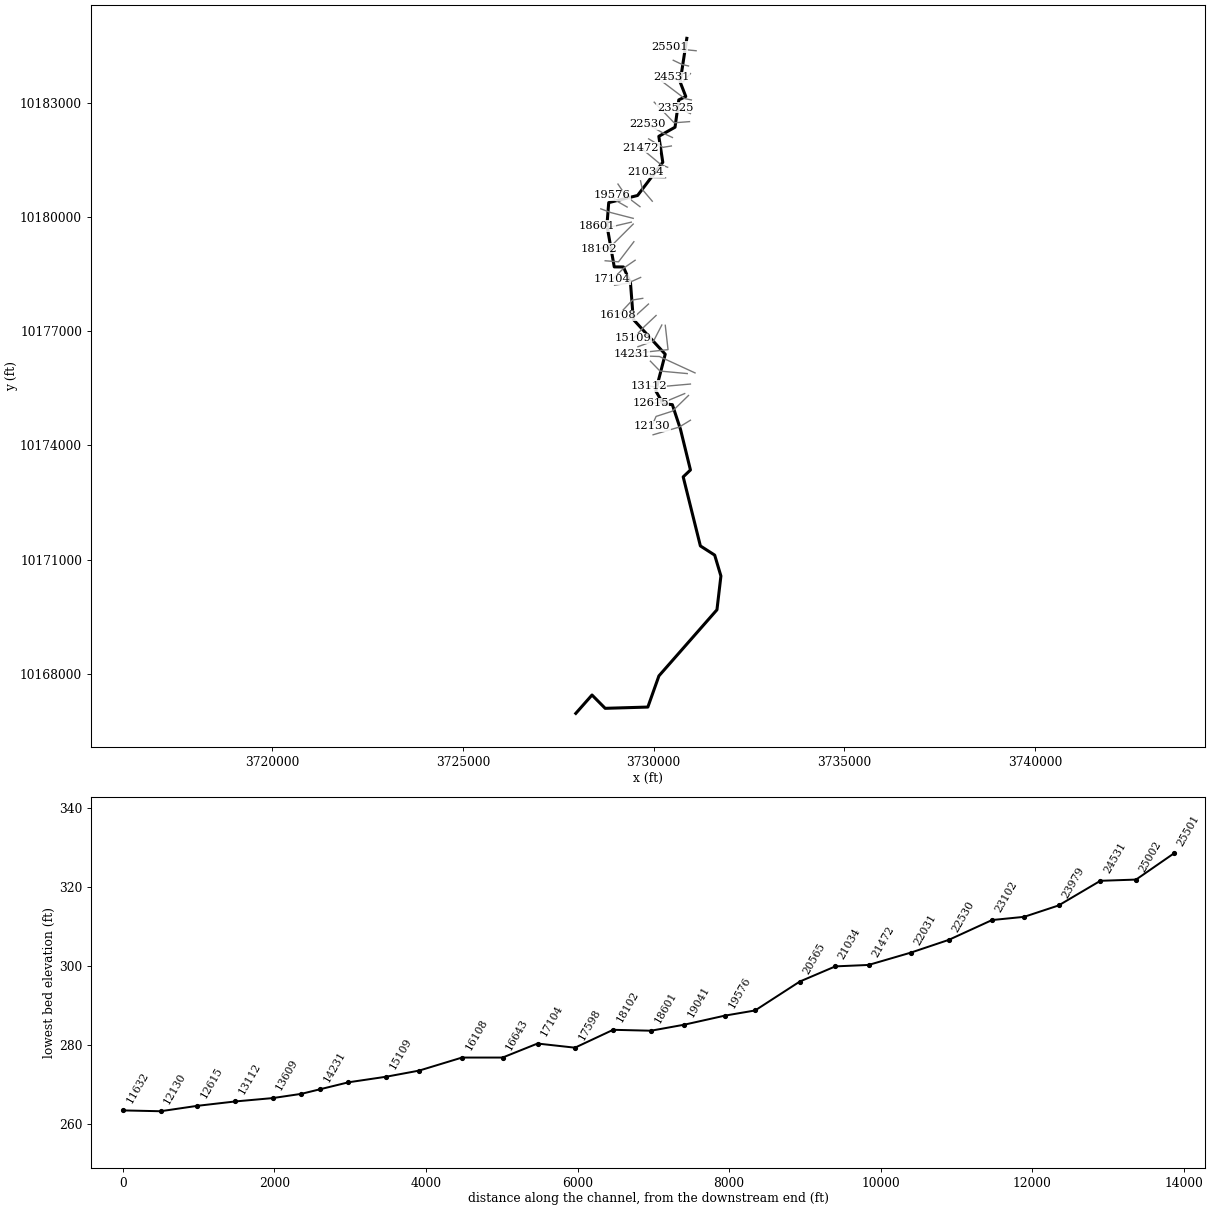
--- LAKE CREEK TRIBUTARY NO 8.prj (project) ---

Proj Title=LAKE CREEK TRIBUTARY NO 8 Base Level Engineering
Current Plan=p01
Default Exp/Contr=0.3,0.1
English Units
Geom File=g01
Flow File=f01
Plan File=p01
Y Axis Title=Elevation
X Axis Title(PF)=Main Channel Distance
X Axis Title(XS)=Station
BEGIN DESCRIPTION:
LAKE CREEK TRIBUTARY NO 8
END DESCRIPTION:
DSS Export Rating Curves= 0
DSS Export Rating Curve Sorted= 0
DSS Export Volume Flow Curves= 0
DXF OffsetX= 0
DXF OffsetY= 0
DXF ScaleX= 1
DXF ScaleY= 10

--- LAKE CREEK TRIBUTARY NO 8.p01 (plan) ---

Plan Title=Multiple Run
Short Identifier=Multiple
Geom File=g01
Flow File=f01
Subcritical Flow
K Sum by GR= 0
Std Step Tol= 0.01
Critical Tol= 0.01
Num of Std Step Trials= 20
Max Error Tol= 0.3
Flow Tol Ratio= 0.001
Split Flow NTrial= 30
Split Flow Tol= 0.02
Split Flow Ratio= 0.02
Log Output Level= 0
Friction Slope Method= 1
Unsteady Friction Slope Method= 2
Unsteady Bridges Friction Slope Method= 1
Parabolic Critical Depth
Global Vel Dist=  1 , 1 , 1
Global Log Level= 0
CheckData=True
Encroach Param= -1, 0, 0, 0
BEGIN DESCRIPTION:
Multiple Run
END DESCRIPTION:

--- LAKE CREEK TRIBUTARY NO 8.f01 (steady flow) ---

Flow Title=Multiple
Program Version=4.10
Number of Profiles= 7
Profile Names=10-year,25-year,50-year,1pct_min,100-year,1pct_plu,500-year
River Rch & RM=LAKE CREEK TRIBU,Reach-1         ,25501
     643     870    1176     523    1578    4765    2938
River Rch & RM=LAKE CREEK TRIBU,Reach-1         ,17598
     726     985    1332     592    1788    5400    3328
River Rch & RM=LAKE CREEK TRIBU,Reach-1         ,13989
    1288    1803    2492    1129    3409   10295    6607
River Rch & RM=LAKE CREEK TRIBU,Reach-1         ,7692
    1687    2388    3321    1514    4571   13804    8965
River Rch & RM=LAKE CREEK TRIBU,Reach-1         ,2549
    2158    3083    4316    1978    5972   18035   11842
Boundary for River Rch & Prof#=LAKE CREEK TRIBU,Reach-1         , 1
Up Type= 0
Dn Type= 3
Dn Slope=0.005
Boundary for River Rch & Prof#=LAKE CREEK TRIBU,Reach-1         , 2
Up Type= 0
Dn Type= 3
Dn Slope=0.005
Boundary for River Rch & Prof#=LAKE CREEK TRIBU,Reach-1         , 3
Up Type= 0
Dn Type= 3
Dn Slope=0.005
Boundary for River Rch & Prof#=LAKE CREEK TRIBU,Reach-1         , 4
Up Type= 0
Dn Type= 3
Dn Slope=0.005
Boundary for River Rch & Prof#=LAKE CREEK TRIBU,Reach-1         , 5
Up Type= 0
Dn Type= 3
Dn Slope=0.005
Boundary for River Rch & Prof#=LAKE CREEK TRIBU,Reach-1         , 6
Up Type= 0
Dn Type= 3
Dn Slope=0.005
Boundary for River Rch & Prof#=LAKE CREEK TRIBU,Reach-1         , 7
Up Type= 0
Dn Type= 3
Dn Slope=0.005
DSS Import GetInterval= 0
DSS Import GetPeak= 0
DSS Import FillOption= 0

--- LAKE CREEK TRIBUTARY NO 8.g01 (geometry) ---

Geom Title=Existing Conditions
Program Version=4.10

River Reach=LAKE CREEK TRIBU,Reach-1
Reach XY= 30
      3730873.23     10184686.84      3730697.97     10183541.15
      3730846.67     10183159.33        3730663.     10183070.81
      3730564.43     10182353.56      3730139.31     10182114.51
       3730243.3     10181433.42      3729582.12      10180561.4
      3728825.57     10180374.17      3728778.23     10179778.15
      3728970.45     10178686.73      3729210.99     10178684.63
      3729396.35     10178266.04      3729470.33     10177307.71
      3730307.05     10176394.28      3730058.61     10175431.95
      3730251.89     10175093.39      3730494.28     10175070.02
       3730706.9     10174424.34      3730968.51     10173355.17
      3730778.56     10173173.81      3731229.14     10171361.07
      3731604.24      10171120.1      3731767.59     10170571.74
      3731663.76     10169685.04      3730141.83     10167949.22
       3729851.4     10167130.94      3728732.45     10167097.67
      3728387.04     10167447.13      3727962.02     10166965.16

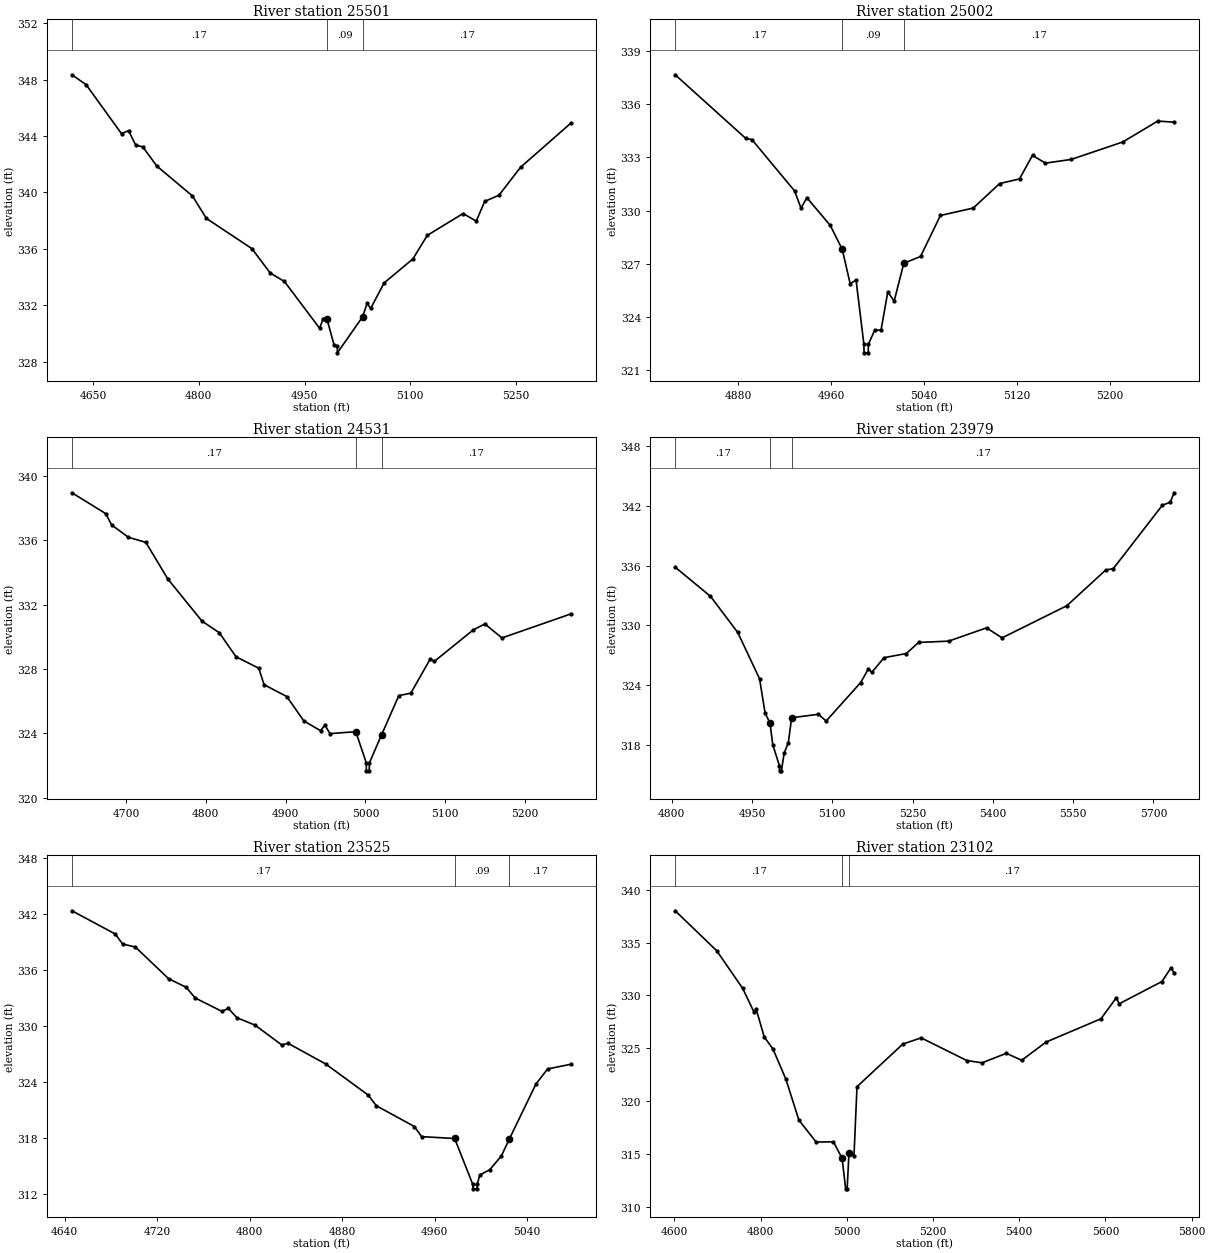
Type RM Length L Ch R = 1 ,25501   ,499,499,499
BEGIN DESCRIPTION:
LAKE CREEK TRIBUTARY NO. 8 48.0
END DESCRIPTION:
XS GIS Cut Line= 3
      3731117.88     10184361.07      3730739.62     10184398.42
      3730417.86     10184461.07
#Sta/Elev= 30
  4619.9  348.34    4640  347.64  4690.3  344.16  4700.3  344.38  4710.4  343.35
  4720.4  343.23  4740.5  341.86  4790.8  339.75  4810.8  338.15  4875.3  336.01
  4901.3  334.28  4921.4  333.68  4971.4  330.36  4976.4  331.05  4981.7  331.03
  4991.7  329.21  4996.4  329.12  4996.6  328.62  5032.4  331.18  5038.7  332.13
  5043.8  331.77  5062.9  333.58  5103.7  335.28  5124.1  336.95    5175   338.5
  5193.6  337.96  5205.6  339.36  5225.9   339.8  5256.5  341.78  5327.8  344.91
#Mann= 3 , 0 , 0
  4619.9     .17       0  4981.7     .09       0  5032.4     .17       0
Bank Sta=4981.7,5032.4
XS Rating Curve= 0 ,0
Exp/Cntr=0.3,0.1

Type RM Length L Ch R = 1 ,25002   ,471,471,471
BEGIN DESCRIPTION:
LAKE CREEK TRIBUTARY NO. 8 47.0
END DESCRIPTION:
XS GIS Cut Line= 3
      3730917.81     10183961.08      3730748.28     10184001.12
      3730517.86     10184111.07
#Sta/Elev= 30
  4825.8  337.66  4886.6  334.07  4891.8  334.01  4928.5  331.12  4934.1  330.15
  4939.2  330.73  4959.3  329.17  4969.6  327.82  4976.4  325.89  4981.5  326.09
  4988.2  322.49  4988.4  321.99  4991.9  321.99  4992.2  322.49  4997.6  323.27
    5003  323.27  5008.8  325.42  5014.3  324.91  5022.6  327.04    5037  327.42
  5054.1  329.73  5082.4  330.15  5105.1  331.53  5122.2  331.79  5133.4  333.12
  5144.5  332.68  5166.7  332.89    5211  333.87  5241.2  335.05  5255.3  334.99
#Mann= 3 , 0 , 0
  4825.8     .17       0  4969.6     .09       0  5022.6     .17       0
Bank Sta=4969.6,5022.6
XS Rating Curve= 0 ,0
Exp/Cntr=0.3,0.1

Type RM Length L Ch R = 1 ,24531   ,552,552,552
BEGIN DESCRIPTION:
LAKE CREEK TRIBUTARY NO. 8 46.0
END DESCRIPTION:
XS GIS Cut Line= 3
      3730967.85     10183761.07      3730773.63     10183538.51
      3730467.87     10183661.06
#Sta/Elev= 30
  4632.4  338.94  4674.6  337.65  4682.2  336.94  4703.1  336.18    4725  335.86
  4752.5  333.59  4795.2  330.98    4817  330.25  4837.9  328.76  4866.4  328.05
    4873  327.03  4901.5  326.29  4922.8  324.78  4943.8  324.17  4949.1  324.52
  4955.6  323.99  4987.9  324.11    5001  322.18  5001.2  321.68  5004.7  321.68
    5005  322.18  5020.2  323.92  5041.8  326.35  5056.8   326.5    5081  328.61
  5086.4  328.48  5134.8  330.42  5149.5   330.8    5171  329.93  5257.2  331.42
#Mann= 3 , 0 , 0
  4632.4     .17       0  4987.9     .09       0  5020.2     .17       0
Bank Sta=4987.9,5020.2
XS Rating Curve= 0 ,0
Exp/Cntr=0.3,0.1

Type RM Length L Ch R = 1 ,23979   ,454,454,454
BEGIN DESCRIPTION:
LAKE CREEK TRIBUTARY NO. 8 45.0
END DESCRIPTION:
XS GIS Cut Line= 3
      3730992.42     10183069.75      3730818.77     10183104.48
      3730217.85     10183561.07
#Sta/Elev= 30
  4806.7  335.84  4872.6  332.92  4923.5   329.3  4964.3  324.65  4974.5  321.23
  4983.8  320.22  4988.8  318.07  5001.4  315.93  5001.6  315.43  5005.1  315.43
  5010.1  317.18  5017.9  318.25  5024.2  320.75  5074.1   321.1  5088.6  320.42
  5153.1  324.28  5167.6  325.66  5173.9   325.3  5196.7  326.77  5238.4  327.19
  5261.2   328.3  5317.4  328.43  5388.1  329.76  5417.2  328.76  5537.9  331.97
  5610.6  335.55  5625.1  335.71  5716.7  342.06  5731.2  342.35  5738.5   343.3
#Mann= 3 , 0 , 0
  4806.7     .17       0  4983.8     .09       0  5024.2     .17       0
Bank Sta=4983.8,5024.2
XS Rating Curve= 0 ,0
Exp/Cntr=0.3,0.1

Type RM Length L Ch R = 1 ,23525   ,423,423,423
BEGIN DESCRIPTION:
LAKE CREEK TRIBUTARY NO. 8 44.0
END DESCRIPTION:
XS GIS Cut Line= 3
      3730967.84     10182711.08       3730645.5     10182856.92
      3730567.81     10182861.07
#Sta/Elev= 30
  4646.2  342.32  4683.6  339.84  4690.1  338.76  4701.1  338.44  4729.8  335.05
    4745  334.13  4752.9  332.98    4776  331.55  4781.5  331.88  4788.9  330.87
  4804.6  330.08  4827.7  327.96  4833.2  328.13  4865.7  325.92  4902.5  322.59
  4909.6  321.44  4942.5  319.22  4948.7  318.14  4977.3  317.94  4992.9  313.05
  4993.2  312.55  4996.7  312.55  4996.9  313.05    4999  314.03  5007.7   314.6
  5017.7  316.07 5024.63317.8856  5047.7  323.79  5057.7  325.38  5077.8  325.89
#Mann= 3 , 0 , 0
  4646.2     .17       0  4977.3     .09       0 5024.63     .17       0
Bank Sta=4977.3,5024.63
XS Rating Curve= 0 ,0
Exp/Cntr=0.3,0.1

Type RM Length L Ch R = 1 ,23102   ,572,572,572
BEGIN DESCRIPTION:
LAKE CREEK TRIBUTARY NO. 8 43.0
END DESCRIPTION:
XS GIS Cut Line= 3
      3730943.77     10182500.31        3730541.     10182469.06
      3730017.84     10183011.08
#Sta/Elev= 30
    4602     338  4698.2  334.23  4758.4  330.68  4784.8  328.43  4789.8  328.72
  4808.5  326.08  4828.6  324.96  4858.7   322.1  4888.8  318.24  4928.9  316.16
    4969  316.18  4989.1  314.63  4997.4  311.74  5000.9  311.74  5005.1  315.17
  5016.7  314.84  5023.7  321.39  5129.9  325.41  5172.4     326  5278.3  323.86
  5313.8  323.64  5370.2  324.54  5405.7  323.88  5462.3   325.6  5589.6   327.8
  5624.9  329.77  5632.1  329.22  5731.1  331.32  5752.2  332.62  5759.3  332.12
#Mann= 3 , 0 , 0
    4602     .17       0  4989.1     .09       0  5005.1     .17       0
Bank Sta=4989.1,5005.1
XS Rating Curve= 0 ,0
Exp/Cntr=0.3,0.1

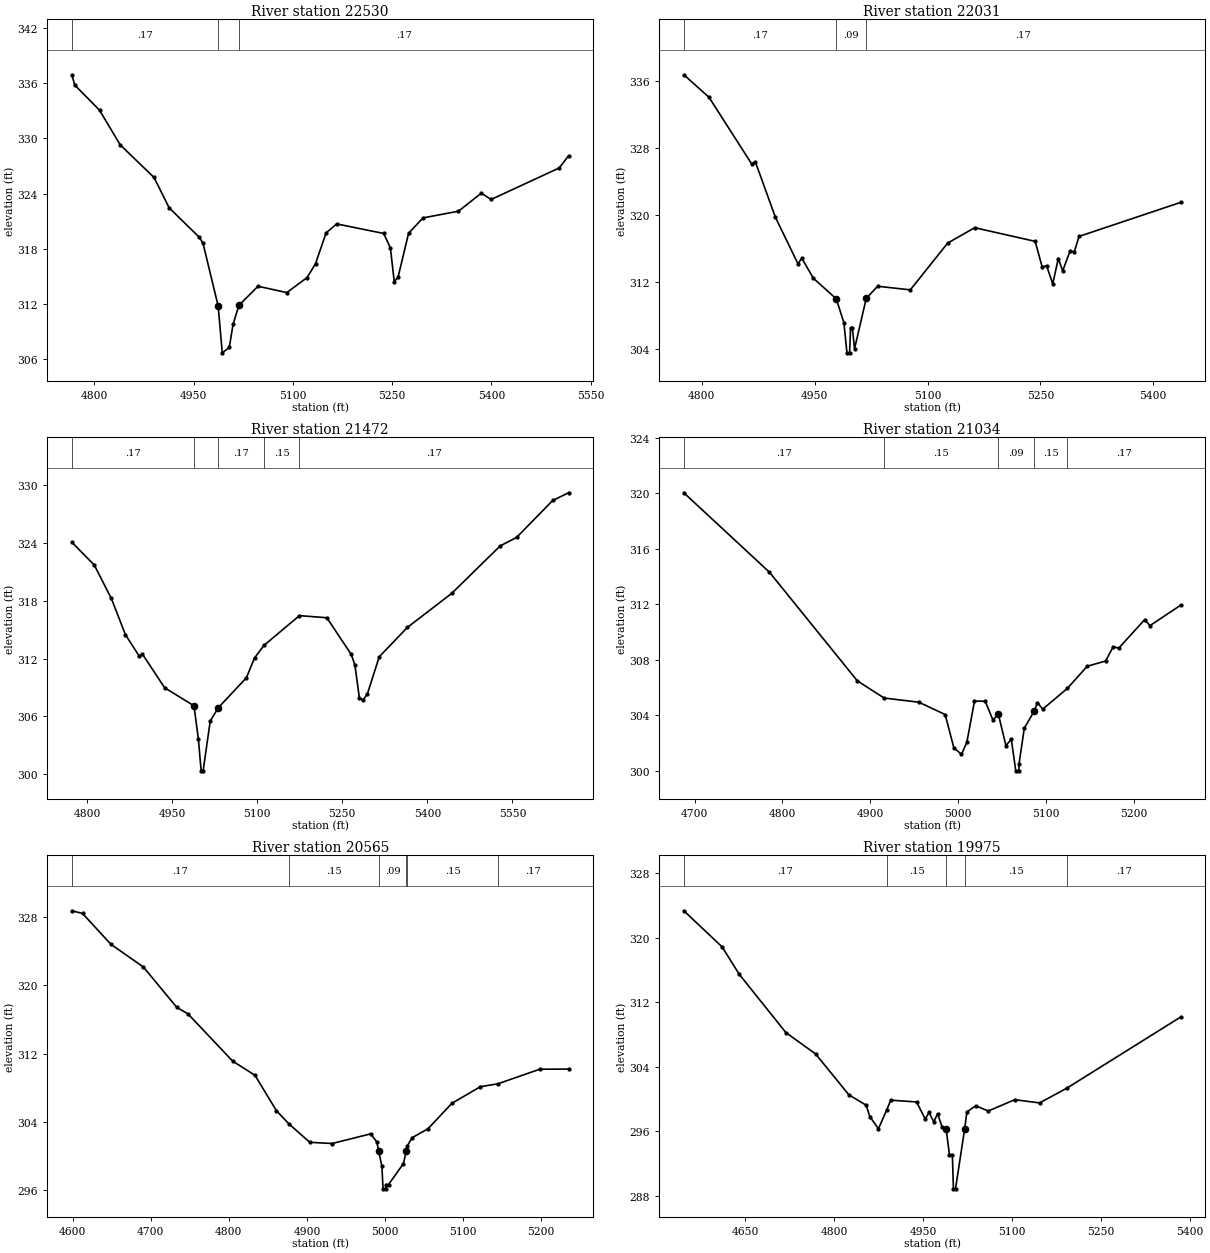
Type RM Length L Ch R = 1 ,22530   ,499,499,499
BEGIN DESCRIPTION:
LAKE CREEK TRIBUTARY NO. 8 42.0
END DESCRIPTION:
XS GIS Cut Line= 3
      3730495.84     10182083.66       3730283.9     10182182.85
      3729832.74      10182434.3
#Sta/Elev= 30
    4766   336.9  4770.5  335.78  4807.9  333.05    4839   329.3  4890.2  325.75
    4913  322.46  4958.7  319.25  4964.2  318.61  4987.1  311.79  4993.3  306.71
  5003.9  307.29  5009.6   309.8  5018.4  311.86  5047.3  313.94  5090.8  313.25
  5121.4  314.88  5134.2  316.39  5150.2  319.74  5166.2  320.71  5237.1  319.67
  5247.3  318.12  5253.1  314.45  5258.8   314.9  5274.8  319.69  5296.5  321.36
  5350.2  322.09  5384.7  324.05  5399.4  323.36  5502.3  326.78  5516.5   328.1
#Mann= 3 , 0 , 0
    4766     .17       0  4987.1     .09       0  5018.4     .17       0
Bank Sta=4987.1,5018.4
XS Rating Curve= 0 ,0
Exp/Cntr=0.3,0.1

Type RM Length L Ch R = 1 ,22031   ,559,559,559
BEGIN DESCRIPTION:
LAKE CREEK TRIBUTARY NO. 8 41.0
END DESCRIPTION:
XS GIS Cut Line= 3
      3730467.86     10181861.07      3730246.83     10181825.33
      3729871.84     10182048.34
#Sta/Elev= 30
  4776.1  336.69  4809.5  334.01  4866.1  326.07  4871.2  326.29  4897.7   319.7
  4927.8  314.12  4932.9  314.79  4948.3  312.39  4978.7  309.94  4988.8   307.1
  4992.9  303.49  4996.4  303.49  4997.7  306.47    5000  306.47    5003  303.99
  5018.6  310.01  5033.7  311.44  5077.1  311.01  5126.8   316.6  5162.7  318.43
  5243.1   316.8  5252.4  313.72  5258.2  313.91  5266.4  311.72  5273.8  314.75
  5279.6  313.28  5289.4  315.64  5295.2  315.56  5301.3  317.39  5436.3  321.45
#Mann= 3 , 0 , 0
  4776.1     .17       0  4978.7     .09       0  5018.6     .17       0
Bank Sta=4978.7,5018.6
XS Rating Curve= 0 ,0
Exp/Cntr=0.3,0.1

Type RM Length L Ch R = 1 ,21472   ,438,438,438
BEGIN DESCRIPTION:
LAKE CREEK TRIBUTARY NO. 8 40.0
END DESCRIPTION:
XS GIS Cut Line= 3
      3730370.85      10181302.4      3730197.25     10181368.37
      3729667.87     10181811.06
#Sta/Elev= 30
  4773.2  324.09  4812.8  321.72  4842.9  318.25  4867.7   314.5  4892.4  312.23
  4897.8  312.47  4936.9  308.98  4988.6  307.11  4996.4  303.63  5001.2  300.36
  5004.7  300.36  5017.2  305.52  5031.6  306.92    5081  310.02  5095.3  312.07
  5111.8  313.37  5174.5  316.47  5222.8  316.25  5265.8  312.45  5272.3  311.35
  5280.1  307.96  5286.6  307.69  5294.4  308.36  5315.2   312.2  5364.7  315.24
  5442.8  318.77  5528.6  323.71  5557.3  324.58    5621  328.42    5649  329.22
#Mann= 5 ,-1 , 0
  4773.2     .17       0  4988.6     .09       0  5031.6     .17       0
  5111.8     .15       0  5174.5     .17       0
Bank Sta=4988.6,5031.6
XS Rating Curve= 0 ,0
Exp/Cntr=0.3,0.1

Type RM Length L Ch R = 1 ,21034   ,469,469,469
BEGIN DESCRIPTION:
LAKE CREEK TRIBUTARY NO. 8 39.0
END DESCRIPTION:
XS GIS Cut Line= 3
       3730315.3     10181024.62      3730003.08     10181031.87
      3729795.42     10181176.73
#Sta/Elev= 30
  4687.7  320.05  4785.2  314.32  4885.2  306.49  4915.7  305.25  4955.2  304.95
  4985.2  304.06  4995.1  301.66  5003.8  301.19  5009.9  302.06  5018.6  305.03
  5030.8  305.02  5039.6  303.66  5045.7   304.1  5054.4  301.82  5060.5  302.28
  5065.6     300  5069.1     300  5069.3   300.5  5075.3  303.08  5086.7304.3235
  5090.2  304.92  5096.3  304.45  5124.4  305.95  5146.9  307.54  5167.8  307.92
  5176.6  308.96  5182.7  308.84  5212.3   310.9  5218.4  310.47  5253.2  311.94
#Mann= 5 ,-1 , 0
  4687.7     .17       0  4915.7     .15       0  5045.7     .09       0
  5086.7     .15       0  5124.4     .17       0
Bank Sta=5045.7,5086.7
XS Rating Curve= 0 ,0
Exp/Cntr=0.3,0.1

Type RM Length L Ch R = 1 ,20565   ,590,590,590
BEGIN DESCRIPTION:
LAKE CREEK TRIBUTARY NO. 8 38.0
END DESCRIPTION:
XS GIS Cut Line= 3
      3729967.84     10180411.09      3729708.76     10180717.29
      3729659.29     10180947.12
#Sta/Elev= 30
  4598.9  328.73  4612.6  328.42  4648.9  324.81  4690.6  322.14  4733.4  317.41
  4747.7  316.65  4804.9  311.12  4833.5  309.46  4860.9  305.32  4876.8  303.78
  4903.7  301.61  4932.3  301.47  4981.7   302.6  4989.5  301.65 4991.92300.5927
    4996  298.81  4997.5  296.16    5001  296.16  5001.2  296.66  5004.5  296.66
  5023.6  299.12  5027.3300.6142  5028.8  301.22  5034.6  302.14    5055  303.19
  5085.7  306.18  5122.3  308.13  5144.5  308.46  5198.2  310.17  5235.1  310.19
#Mann= 6 ,-1 , 0
  4598.9     .17       0  4876.8     .15       0 4991.92     .09       0
  5027.3     .12       0  5028.8     .15       0  5144.5     .17       0
Bank Sta=4991.92,5027.3
XS Rating Curve= 0 ,0
Exp/Cntr=0.3,0.1

Type RM Length L Ch R = 1 ,19975   ,399,399,399
BEGIN DESCRIPTION:
LAKE CREEK TRIBUTARY NO. 8 37.0
END DESCRIPTION:
XS GIS Cut Line= 3
      3729645.16     10180267.68      3729284.05     10180541.98
      3729067.86     10180861.06
#Sta/Elev= 30
    4546  323.36  4610.6  318.88  4639.7  315.46  4718.4  308.23  4768.6  305.58
  4824.8   300.5  4853.9  299.22  4860.1   297.8  4874.7  296.29  4888.8  298.66
  4895.5  299.84  4939.1  299.62  4953.7  297.49    4960  298.31  4968.2  297.16
  4974.5  298.16  4982.1  296.51  4989.1   296.2  4994.6  293.07  4999.5  293.07
  5001.3  288.83  5004.8  288.83 5020.33296.3026    5024  298.37    5039  299.15
    5060  298.49  5104.8   299.9  5146.8   299.5    5193  301.34  5384.9  310.16
#Mann= 5 ,-1 , 0
    4546     .17       0  4888.8     .15       0  4989.1     .09       0
 5020.33     .15       0    5193     .17       0
Bank Sta=4989.1,5020.33
XS Rating Curve= 0 ,0
Exp/Cntr=0.3,0.1

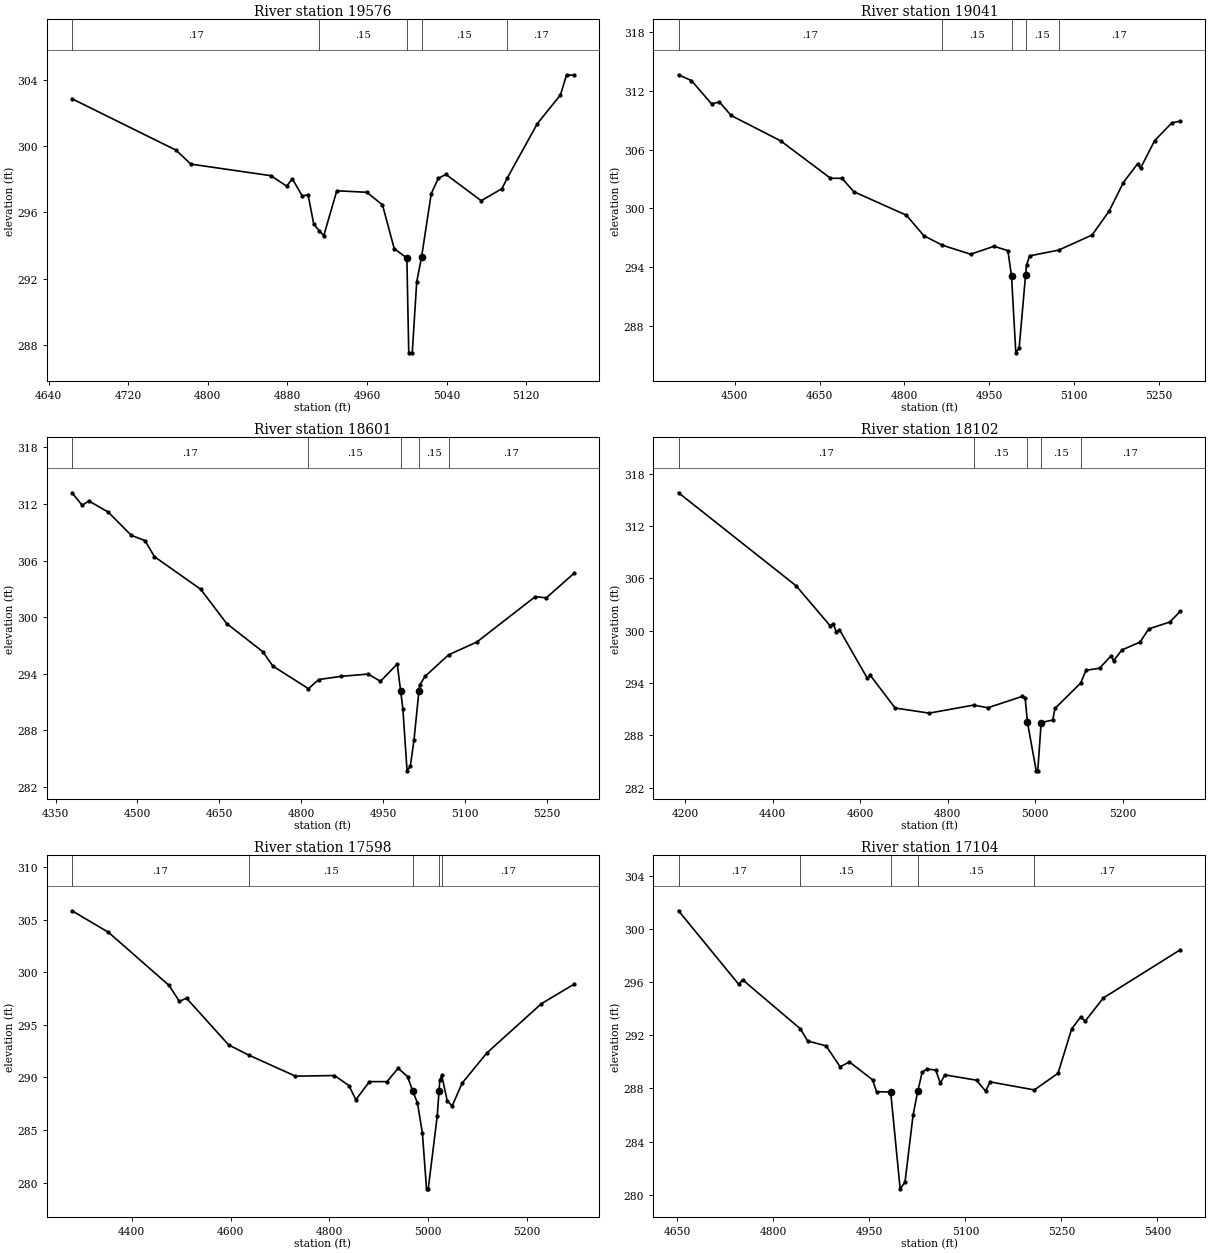
Type RM Length L Ch R = 1 ,19576   ,535,535,535
BEGIN DESCRIPTION:
LAKE CREEK TRIBUTARY NO. 8 36.0
END DESCRIPTION:
XS GIS Cut Line= 3
      3729308.47      10180257.9      3729016.83     10180425.57
      3728917.85     10180561.07
#Sta/Elev= 30
  4663.6  302.85  4768.1  299.75  4782.9  298.91  4863.4  298.21  4879.2  297.58
  4884.9  298.02    4895  296.98  4900.7  297.07  4906.5  295.27  4911.9   294.9
  4916.5  294.59  4929.6   297.3  4959.7  297.21  4975.5  296.45  4987.3  293.81
    5000  293.24  5001.9  287.52  5005.4  287.52  5009.9   291.8  5014.8293.3103
  5024.5  297.13  5031.6  298.05  5039.2  298.29  5074.7   296.7  5095.6  297.43
  5100.9  298.07  5131.1  301.35  5154.3  303.08  5160.5   304.3  5167.8  304.27
#Mann= 5 ,-1 , 0
  4663.6     .17       0  4911.9     .15       0    5000     .09       0
  5014.8     .15       0  5100.9     .17       0
Bank Sta=5000,5014.8
XS Rating Curve= 0 ,0
Exp/Cntr=0.3,0.1

Type RM Length L Ch R = 1 ,19041   ,440,440,440
BEGIN DESCRIPTION:
LAKE CREEK TRIBUTARY NO. 8 35.0
END DESCRIPTION:
XS GIS Cut Line= 3
      3729467.82     10179961.08      3728884.75     10180111.43
      3728617.89     10180211.06
#Sta/Elev= 30
  4400.7  313.65  4423.6  313.05  4459.1  310.68    4473  310.87  4493.6  309.49
  4581.1   306.9  4669.2  303.08  4689.8  303.06  4710.5   301.7  4803.4   299.3
  4834.4   297.2    4867  296.23    4917  295.31  4958.3  296.12  4982.8  295.68
  4989.3   293.1  4996.9  285.23  5002.8  285.73  5014.2293.2302  5015.8  294.17
  5021.2  295.14  5072.6  295.73  5131.7  297.27    5162  299.73    5187  302.64
    5212  304.54  5217.3  304.09  5242.3  306.92  5272.6  308.73  5287.7  308.92
#Mann= 5 ,-1 , 0
  4400.7     .17       0    4867     .15       0  4989.3     .09       0
  5014.2     .15       0  5072.6     .17       0
Bank Sta=4989.3,5014.2
XS Rating Curve= 0 ,0
Exp/Cntr=0.3,0.1

Type RM Length L Ch R = 1 ,18601   ,499,499,499
BEGIN DESCRIPTION:
LAKE CREEK TRIBUTARY NO. 8 34.0
END DESCRIPTION:
XS GIS Cut Line= 3
      3729417.85     10179861.07      3728814.52     10179719.14
      3728517.87     10179761.07
#Sta/Elev= 30
  4380.2  313.18  4398.8  311.85    4411  312.31  4446.3  311.14  4488.7  308.67
  4513.8  308.11  4531.1  306.41  4615.9  302.95  4663.4  299.32  4729.5  296.34
  4748.1  294.81  4813.3  292.41  4832.2  293.38  4873.3  293.72  4922.8  293.96
  4945.2  293.19    4976  295.03  4982.3292.1247  4986.3  290.28    4994   283.7
    5000   284.2  5006.7  286.98  5015.7292.1307  5016.8  292.76  5026.9  293.71
  5070.1     296  5121.9  297.36  5228.9  302.17  5249.1  302.04  5299.6  304.63
#Mann= 5 ,-1 , 0
  4380.2     .17       0  4813.3     .15       0  4982.3     .09       0
  5015.7     .15       0  5070.1     .17       0
Bank Sta=4982.3,5015.7
XS Rating Curve= 0 ,0
Exp/Cntr=0.3,0.1

Type RM Length L Ch R = 1 ,18102   ,504,504,504
BEGIN DESCRIPTION:
LAKE CREEK TRIBUTARY NO. 8 33.0
END DESCRIPTION:
XS GIS Cut Line= 3
      3729467.86     10179811.08      3728891.39     10179235.25
      3728567.88     10179161.08
#Sta/Elev= 30
  4185.2  315.83  4453.9  305.16  4531.7  300.57  4538.8  300.82  4545.8  299.85
  4552.9  300.13  4616.5  294.56  4623.6  294.87  4680.2  291.14    4758  290.55
  4859.3  291.47  4892.3  291.17  4970.1  292.46  4977.2  292.33  4982.5 289.506
  5002.6  283.93  5006.1  283.93  5013.9  289.47  5040.3  289.76  5045.4  291.09
  5103.9  293.98  5116.5  295.47  5147.3   295.7  5174.1  297.15  5179.2  296.55
  5198.6  297.81  5239.6  298.69  5259.9  300.22  5307.9     301  5331.9  302.24
#Mann= 5 ,-1 , 0
  4185.2     .17       0  4859.3     .15       0  4982.5     .09       0
  5013.9     .15       0  5103.9     .17       0
Bank Sta=4982.5,5013.9
XS Rating Curve= 0 ,0
Exp/Cntr=0.3,0.1

Type RM Length L Ch R = 1 ,17598   ,494,494,494
BEGIN DESCRIPTION:
LAKE CREEK TRIBUTARY NO. 8 32.0
END DESCRIPTION:
XS GIS Cut Line= 3
      3729485.41      10179347.5      3729082.66     10178819.76
      3728732.42      10178847.5
#Sta/Elev= 30
  4279.3  305.83    4353  303.78  4475.6  298.73  4496.4  297.22  4510.9  297.52
  4596.1  293.08  4636.4  292.12  4731.3  290.11  4810.2  290.17  4839.3  289.22
  4853.5  287.87  4880.9  289.59  4916.4  289.59    4939  290.86    4958  290.07
  4968.1  288.74  4978.1  287.56  4988.1  284.69  4996.4   279.4  4999.9   279.4
  5018.2  286.36  5021.7 288.705  5023.2  289.71  5027.2  290.18  5038.3  287.76
  5048.3  287.28  5068.4  289.44  5118.5  292.32  5228.9     297  5294.5  298.84
#Mann= 5 ,-1 , 0
  4279.3     .17       0  4636.4     .15       0  4968.1     .09       0
  5021.7     .15       0  5027.2     .17       0
Bank Sta=4968.1,5021.7
XS Rating Curve= 0 ,0
Exp/Cntr=0.3,0.1

Type RM Length L Ch R = 1 ,17104   ,461,461,461
BEGIN DESCRIPTION:
LAKE CREEK TRIBUTARY NO. 8 31.0
END DESCRIPTION:
XS GIS Cut Line= 3
      3729517.84     10178861.07      3729231.03     10178663.98
      3728917.85     10178361.07
#Sta/Elev= 30
    4652  301.36    4746  295.83  4752.1  296.17  4842.4  292.48  4853.6  291.57
  4882.5   291.2  4904.4  289.63  4918.9  289.99  4955.1  288.65  4961.2  287.75
  4983.3287.7364  4998.1  280.45  5005.7  280.95  5018.3  285.99  5025.5  287.77
  5032.5  289.21  5039.7  289.46  5053.8  289.38  5060.8  288.39    5068  289.02
  5117.4  288.62  5131.5   287.8  5138.7  288.49  5207.7  287.89  5244.7  289.14
    5266  292.48  5280.2  293.38  5287.1  293.06  5315.4   294.8  5435.7  298.43
#Mann= 5 ,-1 , 0
    4652     .17       0  4842.4     .15       0  4983.3     .09       0
  5025.5     .15       0  5207.7     .17       0
Bank Sta=4983.3,5025.5
XS Rating Curve= 0 ,0
Exp/Cntr=0.3,0.1

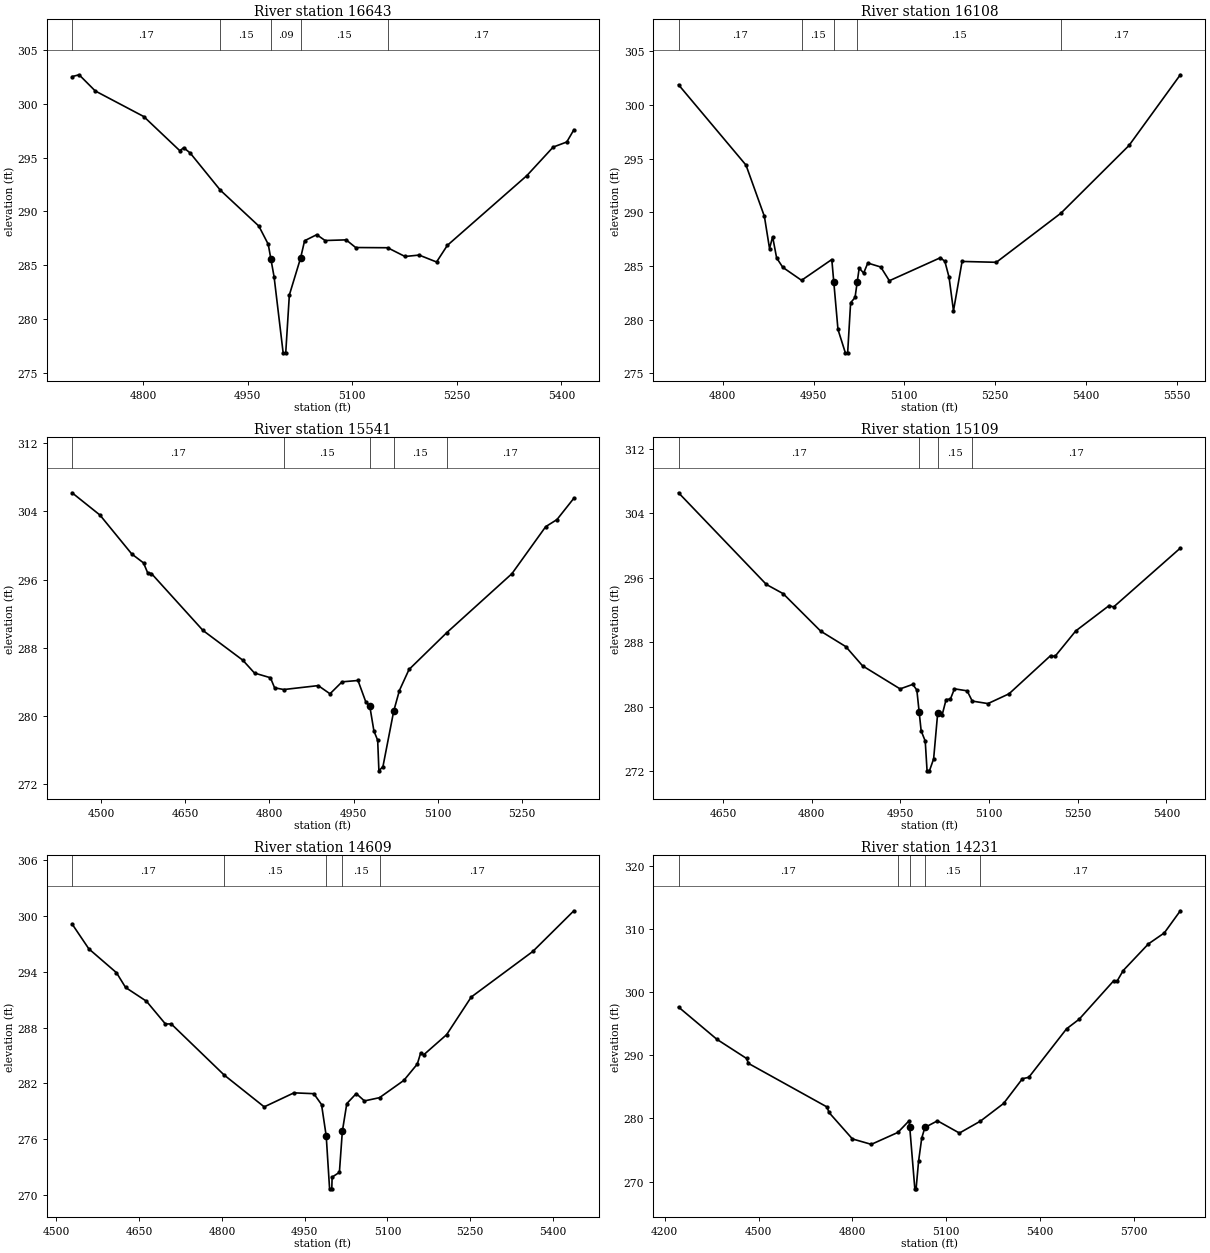
Type RM Length L Ch R = 1 ,16643   ,535,535,535
BEGIN DESCRIPTION:
LAKE CREEK TRIBUTARY NO. 8 30.0
END DESCRIPTION:
XS GIS Cut Line= 3
      3729662.49     10178410.02      3729329.19     10178260.73
      3728978.48     10178205.17
#Sta/Elev= 30
  4697.7   302.5  4707.8  302.67    4731  301.17  4800.6   298.8  4852.4  295.63
  4857.9  295.91  4867.1  295.43  4910.6  291.97  4965.8  288.65  4979.3  286.96
 4983.04285.6154  4987.7  283.94  5000.7   276.9  5004.4   276.9  5009.6  282.26
  5025.7  285.68  5031.5  287.29  5048.9  287.85  5060.9  287.31  5091.1  287.37
  5104.8  286.66  5150.7  286.64  5175.6  285.83  5195.9  285.96  5220.9  285.32
  5236.4  286.86  5350.6  293.33  5388.3  295.97  5407.8  296.44    5418  297.57
#Mann= 5 ,-1 , 0
  4697.7     .17       0  4910.6     .15       0 4983.04     .09       0
  5025.7     .15       0  5150.7     .17       0
Bank Sta=4983.04,5025.7
XS Rating Curve= 0 ,0
Exp/Cntr=0.3,0.1

Type RM Length L Ch R = 1 ,16108   ,567,567,567
BEGIN DESCRIPTION:
LAKE CREEK TRIBUTARY NO. 8 29.0
END DESCRIPTION:
XS GIS Cut Line= 3
      3729717.83     10177861.07      3729448.26     10177816.69
      3729067.85     10177411.07
#Sta/Elev= 30
  4726.8  301.89  4838.3   294.4  4868.7  289.62  4877.2  286.62  4882.3  287.72
  4888.9  285.75  4899.1  284.87  4930.1  283.66  4980.1   285.6  4983.4283.4906
  4990.3  279.08  5002.5   276.9  5006.3   276.9  5011.2  281.57  5018.5  282.06
  5022.1283.4948  5025.4  284.81  5032.7  284.33  5039.6  285.27    5061   284.9
  5075.2  283.62  5159.7  285.77    5167  285.42  5173.9  283.94  5181.2  280.82
  5195.4  285.42    5252  285.34  5358.8  289.92  5471.3  296.23  5556.1  302.82
#Mann= 5 ,-1 , 0
  4726.8     .17       0  4930.1     .15       0  4983.4     .09       0
  5022.1     .15       0  5358.8     .17       0
Bank Sta=4983.4,5022.1
XS Rating Curve= 0 ,0
Exp/Cntr=0.3,0.1

Type RM Length L Ch R = 1 ,15541   ,432,432,432
BEGIN DESCRIPTION:
LAKE CREEK TRIBUTARY NO. 8 28.0
END DESCRIPTION:
XS GIS Cut Line= 3
      3729867.86     10177711.08      3729461.13     10177340.59
      3729117.87     10177311.07
#Sta/Elev= 30
    4448  306.18  4497.7  303.57  4554.4  299.01  4575.4  297.96  4582.8   296.8
  4589.6  296.71  4681.5  290.04  4752.4  286.56  4773.3  285.05  4801.7   284.5
  4809.1  283.32  4825.6  283.12  4886.9  283.58  4907.9  282.62  4929.4  284.02
  4957.8  284.18    4972  281.62  4978.7  281.22  4986.2  278.26  4992.9  277.17
  4995.1  273.59  5002.3  274.09  5021.5  280.59  5031.6     283  5048.8  285.47
    5116  289.78  5232.3   296.7  5292.5  302.21  5312.6  303.04  5342.7  305.54
#Mann= 5 ,-1 , 0
    4448     .17       0  4825.6     .15       0  4978.7     .09       0
  5021.5     .15       0    5116     .17       0
Bank Sta=4978.7,5021.5
XS Rating Curve= 0 ,0
Exp/Cntr=0.3,0.1

Type RM Length L Ch R = 1 ,15109   ,500,500,500
BEGIN DESCRIPTION:
LAKE CREEK TRIBUTARY NO. 8 27.0
END DESCRIPTION:
XS GIS Cut Line= 3
      3730067.83     10177411.05      3729758.64     10177119.02
      3729467.88      10176811.1
#Sta/Elev= 30
  4574.7  306.53  4723.3  295.16  4751.7  294.02  4815.2  289.37  4857.7  287.45
    4886  285.07  4949.5  282.21  4970.9  282.77  4977.8  282.07 4981.72279.3527
  4985.1  277.01    4992  275.74  4995.1  272.05  4999.1  272.05  5006.2  273.53
  5013.1  279.24  5020.4  278.92  5027.3  280.89  5034.6  280.95  5041.4  282.22
  5062.9  281.97  5071.5   280.7  5098.1  280.39  5133.7   281.6  5204.1  286.34
  5211.4  286.23  5246.6   289.4  5303.2  292.55  5310.5  292.36  5423.5  299.67
#Mann= 4 ,-1 , 0
  4574.7     .17       0 4981.72     .09       0  5013.1     .15       0
  5071.5     .17       0
Bank Sta=4981.72,5013.1
XS Rating Curve= 0 ,0
Exp/Cntr=0.3,0.1

Type RM Length L Ch R = 1 ,14609   ,378,378,378
BEGIN DESCRIPTION:
LAKE CREEK TRIBUTARY NO. 8 26.0
END DESCRIPTION:
XS GIS Cut Line= 3
      3730217.83     10177161.03      3730002.68     10176741.37
      3729591.23     10176591.19
#Sta/Elev= 30
  4528.4  299.16  4558.8  296.48  4608.9  293.91  4625.4  292.32  4663.2  290.84
  4697.6  288.39  4708.2  288.39  4804.1  282.89  4876.7  279.46  4930.6  280.97
  4966.6  280.88  4980.6  279.71  4989.1  276.32  4995.2  270.63  4999.2  270.63
  4999.8  271.89    5013  272.41  5018.3  276.81  5026.4  279.81  5043.5  280.89
  5058.4   280.1  5085.7  280.45  5129.8  282.31  5154.2  284.07  5160.4  285.28
  5165.7  285.06  5207.4  287.24    5252  291.29  5363.6   296.2    5438  300.58
#Mann= 5 ,-1 , 0
  4528.4     .17       0  4804.1     .15       0  4989.1     .09       0
  5018.3     .15       0  5085.7     .17       0
Bank Sta=4989.1,5018.3
XS Rating Curve= 0 ,0
Exp/Cntr=0.3,0.1

Type RM Length L Ch R = 1 ,14231   ,242,242,242
BEGIN DESCRIPTION:
LAKE CREEK TRIBUTARY NO. 8 25.0
END DESCRIPTION:
XS GIS Cut Line= 3
      3730308.36     10177153.05      3730381.27      10176514.2
      3729426.43     10176410.04
#Sta/Elev= 30
  4244.4  297.66  4367.2  292.54  4461.6  289.52  4467.8  288.73  4719.4  281.81
  4724.7  280.98    4800  276.76  4860.4   275.9  4945.3  277.79  4981.4  279.65
 4983.26278.5992  4999.5  268.85  5003.5  268.85  5011.5  273.24  5021.6   276.9
  5031.7  278.58  5071.9  279.63    5142  277.69  5209.1  279.58  5283.1  282.38
  5343.5  286.31  5363.6  286.52  5484.3  294.21  5524.6  295.73  5635.2  301.84
  5645.3  301.73  5665.4  303.45  5745.9  307.67  5796.7  309.41  5847.9  312.92
#Mann= 5 ,-1 , 0
  4244.4     .17       0  4945.3     .15       0 4983.26     .09       0
  5031.7     .15       0  5209.1     .17       0
Bank Sta=4983.26,5031.7
XS Rating Curve= 0 ,0
Exp/Cntr=0.3,0.1

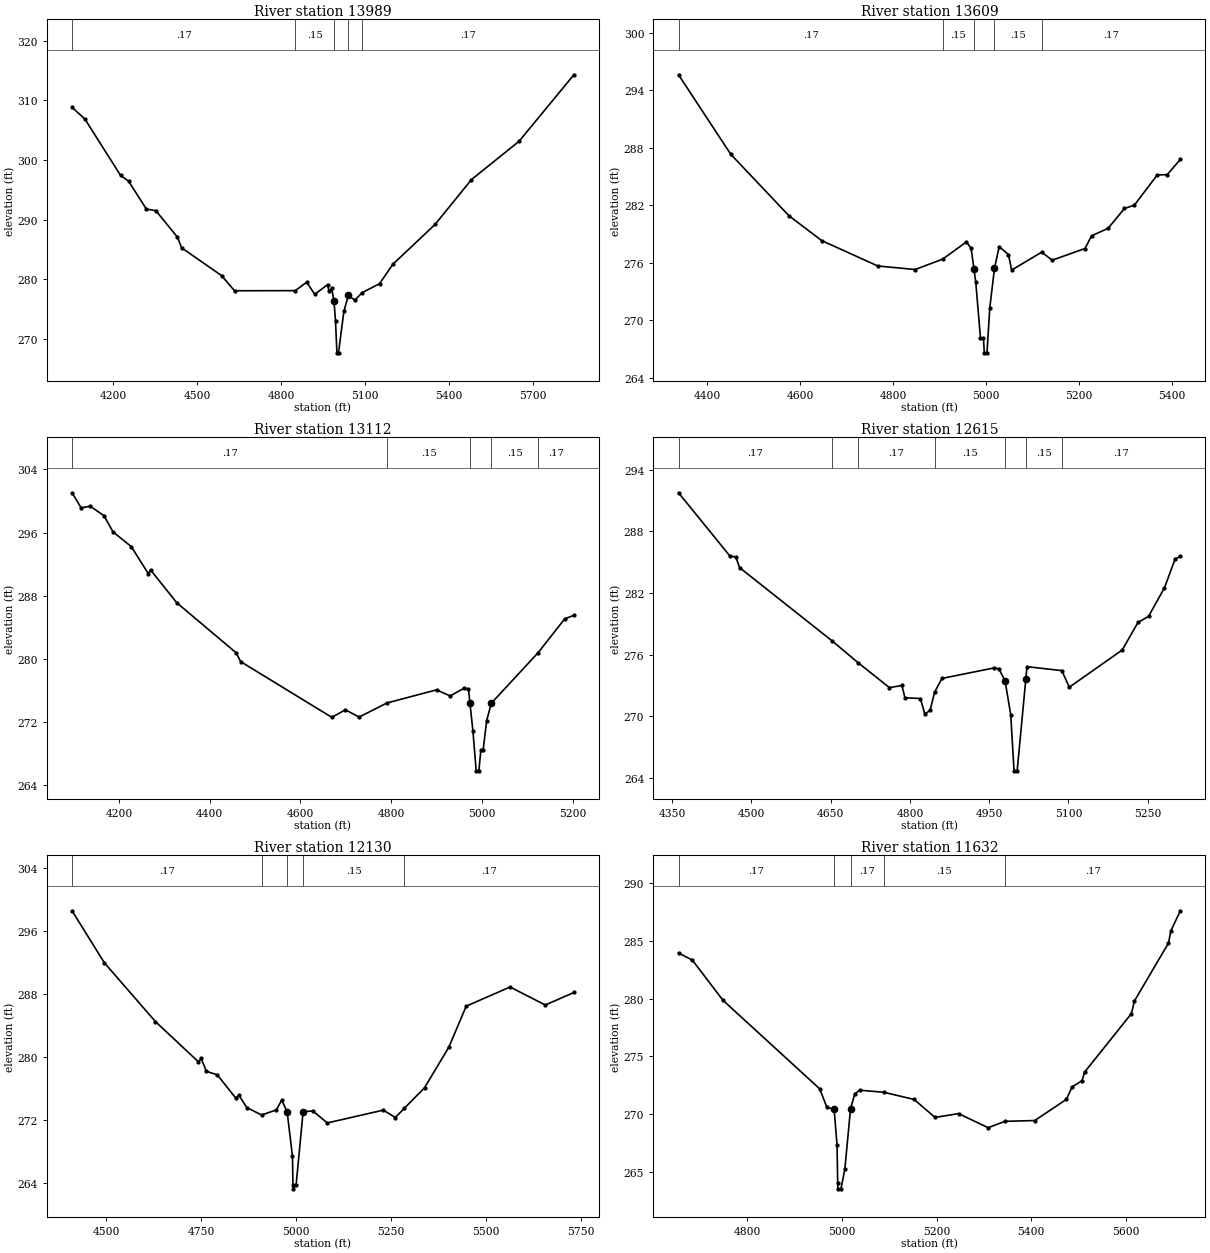
Type RM Length L Ch R = 1 ,13989   ,380,380,380
BEGIN DESCRIPTION:
Mapping XS d6ef5ba4
END DESCRIPTION:
XS GIS Cut Line= 3
      3731089.59      10175903.1      3730155.58     10176333.65
      3729392.25     10176361.41
#Sta/Elev= 30
  4053.9  308.83  4099.9  306.86  4227.3  297.42  4255.8  296.47  4319.2  291.79
  4353.1  291.53  4430.2  287.09    4445  285.31  4588.2  280.64  4634.1  278.11
    4851  278.13  4892.1  279.54  4920.6  277.52  4966.5  279.12    4972  277.99
  4980.8  278.49  4989.4  276.44  4994.9  272.98  4999.9  267.71  5005.6  267.71
  5024.8  274.68  5040.9  277.33  5063.8  276.53  5089.5  277.78  5152.1  279.29
  5200.2  282.57  5350.3  289.21  5480.4  296.73  5650.5  303.15  5846.2  314.29
#Mann= 5 ,-1 , 0
  4053.9     .17       0    4851     .15       0  4989.4     .09       0
  5040.9     .15       0  5089.5     .17       0
Bank Sta=4989.4,5040.9
XS Rating Curve= 0 ,0
Exp/Cntr=0.3,0.1

Type RM Length L Ch R = 1 ,13609   ,497,497,497
BEGIN DESCRIPTION:
LAKE CREEK TRIBUTARY NO. 8 24.0
END DESCRIPTION:
XS GIS Cut Line= 3
      3730884.79     10175885.73      3730169.47      10175951.7
      3729917.86     10176211.06
#Sta/Elev= 30
  4338.3   295.6  4450.8  287.31  4576.2   280.9  4646.5  278.32    4767  275.68
  4847.4  275.31  4906.5  276.39  4957.9  278.19  4967.9  277.51  4973.9 275.386
  4977.9  273.97    4988  268.15  4994.2  268.21  4996.3  266.63    5002  266.63
  5008.1  271.35  5018.1  275.42  5028.2  277.69  5048.2  276.87    5055  275.25
  5119.8  277.12  5142.2  276.28  5212.9   277.5    5227  278.82  5262.5   279.6
  5297.8  281.67  5319.1  282.02  5368.5  285.17  5389.8  285.19    5418  286.78
#Mann= 5 ,-1 , 0
  4338.3     .17       0  4906.5     .15       0  4973.9     .09       0
  5018.1     .15       0  5119.8     .17       0
Bank Sta=4973.9,5018.1
XS Rating Curve= 0 ,0
Exp/Cntr=0.3,0.1

Type RM Length L Ch R = 1 ,13112   ,497,497,497
BEGIN DESCRIPTION:
LAKE CREEK TRIBUTARY NO. 8 23.0
END DESCRIPTION:
XS GIS Cut Line= 3
      3730967.84     10175611.07      3730068.26     10175531.51
      3729867.82     10175561.08
#Sta/Elev= 30
  4096.9  301.04    4117  299.12    4137  299.34  4167.2  298.13  4187.2  296.08
  4227.4  294.21  4264.9  290.79  4269.9  291.25  4327.8  287.08  4458.3  280.75
  4468.3  279.63  4669.1  272.56  4699.2  273.51  4729.4  272.59  4790.8  274.38
    4900  276.04  4930.1  275.27  4960.2  276.24  4970.3  276.18  4973.6274.3912
  4980.3  270.76  4987.4  265.77  4993.3  265.77  4997.7  268.43  5002.7  268.43
  5010.5  272.14  5020.6  274.34  5123.6  280.74  5182.4  285.05  5202.6  285.49
#Mann= 5 ,-1 , 0
  4096.9     .17       0  4790.8     .15       0  4973.6     .09       0
  5020.6     .15       0  5123.6     .17       0
Bank Sta=4973.6,5020.6
XS Rating Curve= 0 ,0
Exp/Cntr=0.3,0.1

Type RM Length L Ch R = 1 ,12615   ,485,485,485
BEGIN DESCRIPTION:
LAKE CREEK TRIBUTARY NO. 8 22.0
END DESCRIPTION:
XS GIS Cut Line= 3
      3730817.89     10175361.09      3730229.37     10175115.51
      3729917.81     10175111.07
#Sta/Elev= 30
  4362.3  291.77  4459.9  285.58  4470.7  285.52  4477.7  284.48  4652.7  277.34
  4702.4  275.19  4761.3  272.78  4784.9  272.99  4790.6  271.79  4819.8  271.72
  4828.3  270.19  4838.2  270.58  4846.9  272.36  4860.8  273.68  4958.3  274.69
  4968.2  274.62    4980  273.46  4990.8  270.12    4997  264.67  5002.9  264.67
  5019.4273.6523  5021.5  274.82  5087.5  274.44  5101.5  272.82  5201.5  276.44
  5231.5  279.13  5251.5  279.73  5281.6  282.51  5301.6   285.3  5311.6  285.57
#Mann= 7 ,-1 , 0
  4362.3     .17       0  4652.7     .15       0  4702.4     .17       0
  4846.9     .15       0    4980     .09       0  5019.4     .15       0
  5087.5     .17       0
Bank Sta=4980,5019.4
XS Rating Curve= 0 ,0
Exp/Cntr=0.3,0.1

Type RM Length L Ch R = 1 ,12130   ,498,498,498
BEGIN DESCRIPTION:
LAKE CREEK TRIBUTARY NO. 8 21.0
END DESCRIPTION:
XS GIS Cut Line= 4
      3730917.83     10175311.05      3730496.11     10174899.43
      3730067.85     10174761.07      3729953.36     10174504.95
#Sta/Elev= 30
  4410.7  298.62  4495.5  292.02  4629.9  284.55  4743.1  279.43  4750.1  279.87
  4764.2  278.22  4792.5  277.79  4842.1  274.78  4849.1  275.22  4870.4  273.62
  4909.4  272.68  4948.1  273.33  4962.2  274.57  4976.4  273.08  4990.5  267.42
  4991.7   263.8  4992.2   263.3    5000   263.8  5018.5273.1217  5044.5  273.18
  5082.2  271.67  5229.4   273.3  5260.9  272.36  5284.9  273.54    5338  276.15
    5402  281.32  5447.4   286.5  5562.7  288.94  5655.5  286.65  5730.6  288.24
#Mann= 5 ,-1 , 0
  4410.7     .17       0  4909.4     .15       0  4976.4     .09       0
  5018.5     .15       0  5284.9     .17       0
Bank Sta=4976.4,5018.5
XS Rating Curve= 0 ,0
Exp/Cntr=0.3,0.1

Type RM Length L Ch R = 1 ,11632   ,478,478,478
BEGIN DESCRIPTION:
LAKE CREEK TRIBUTARY NO. 8 20.0
END DESCRIPTION:
XS GIS Cut Line= 3
      3730967.83     10174661.06      3730674.21     10174481.05
      3729988.89     10174278.95
#Sta/Elev= 30
  4655.6  283.95  4684.6  283.34  4749.4  279.85  4953.4  272.18  4968.8  270.57
    4984  270.41  4990.1  267.28  4991.5  264.01    4992  263.51  4998.3  263.51
  5006.6  265.23  5018.5270.4342  5027.5  271.74  5037.9  272.06  5088.6  271.88
  5152.6  271.26  5196.9   269.7  5246.4  270.03    5309  268.81  5344.3  269.36
  5407.3  269.43  5473.9  271.26  5486.2  272.35  5507.1  272.88  5512.4  273.62
  5611.3   278.7  5617.6  279.79  5689.4   284.8  5694.7  285.89  5714.5  287.61
#Mann= 5 ,-1 , 0
  4655.6     .17       0    4984     .09       0  5018.5     .17       0
  5088.6     .15       0  5344.3     .17       0
Bank Sta=4984,5018.5
XS Rating Curve= 0 ,0
Exp/Cntr=0.3,0.1