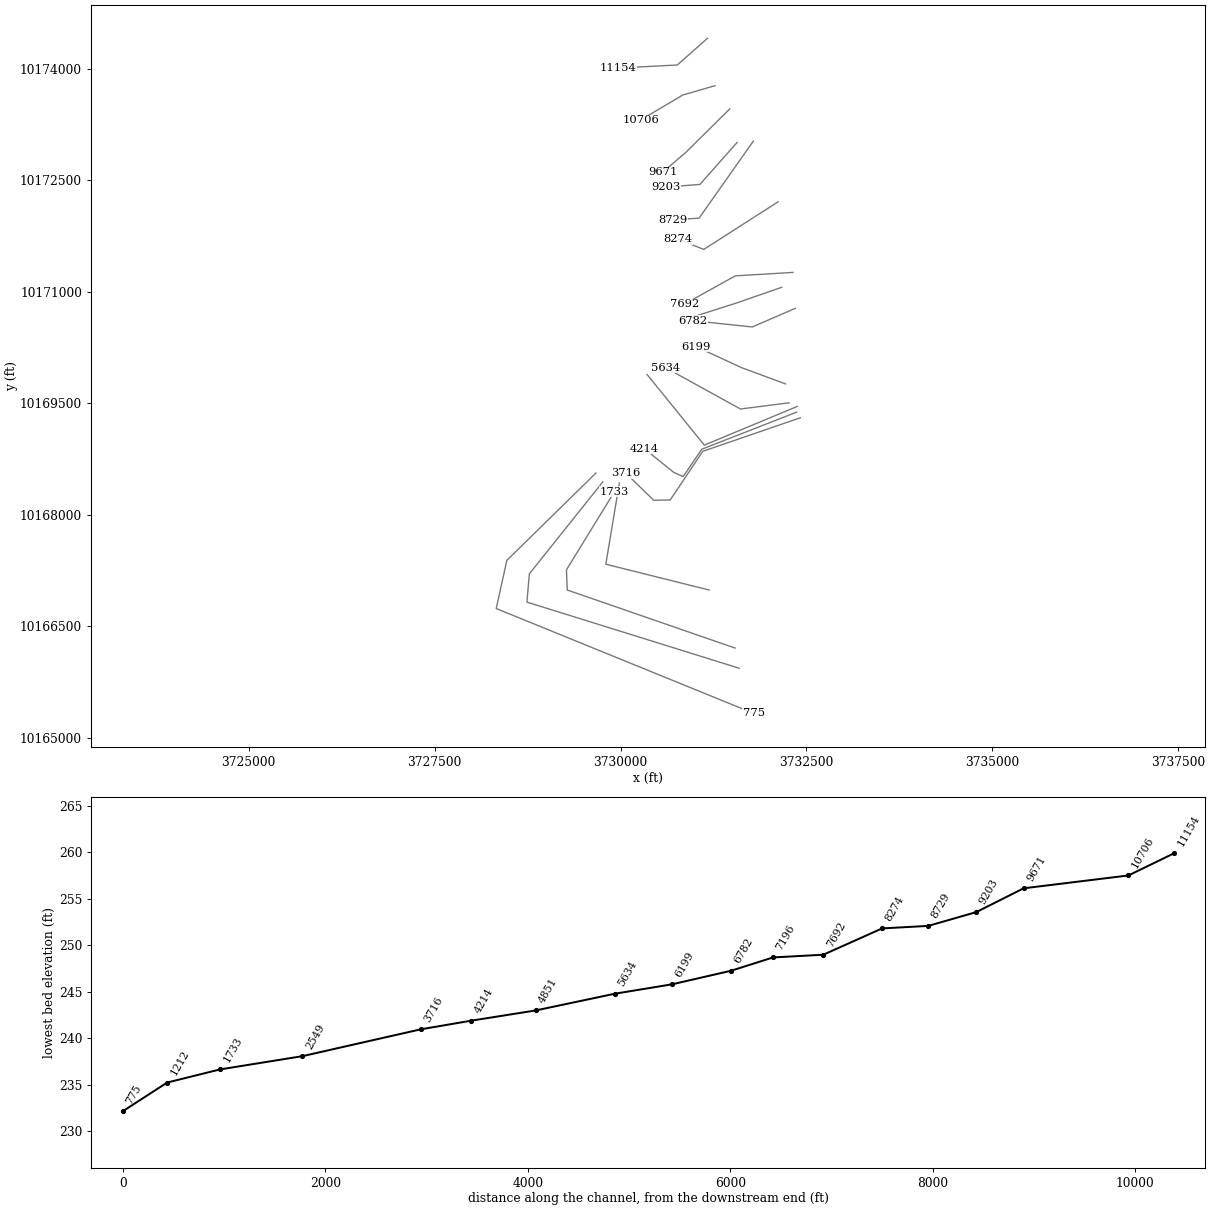
HEC-RAS study LAKE CREEK TRIBUTARY NO 8.prj: LAKE CREEK TRIBUTARY NO 8 Base Level Engineering

--- LAKE CREEK TRIBUTARY NO 8.g01 (geometry) --- (continued)

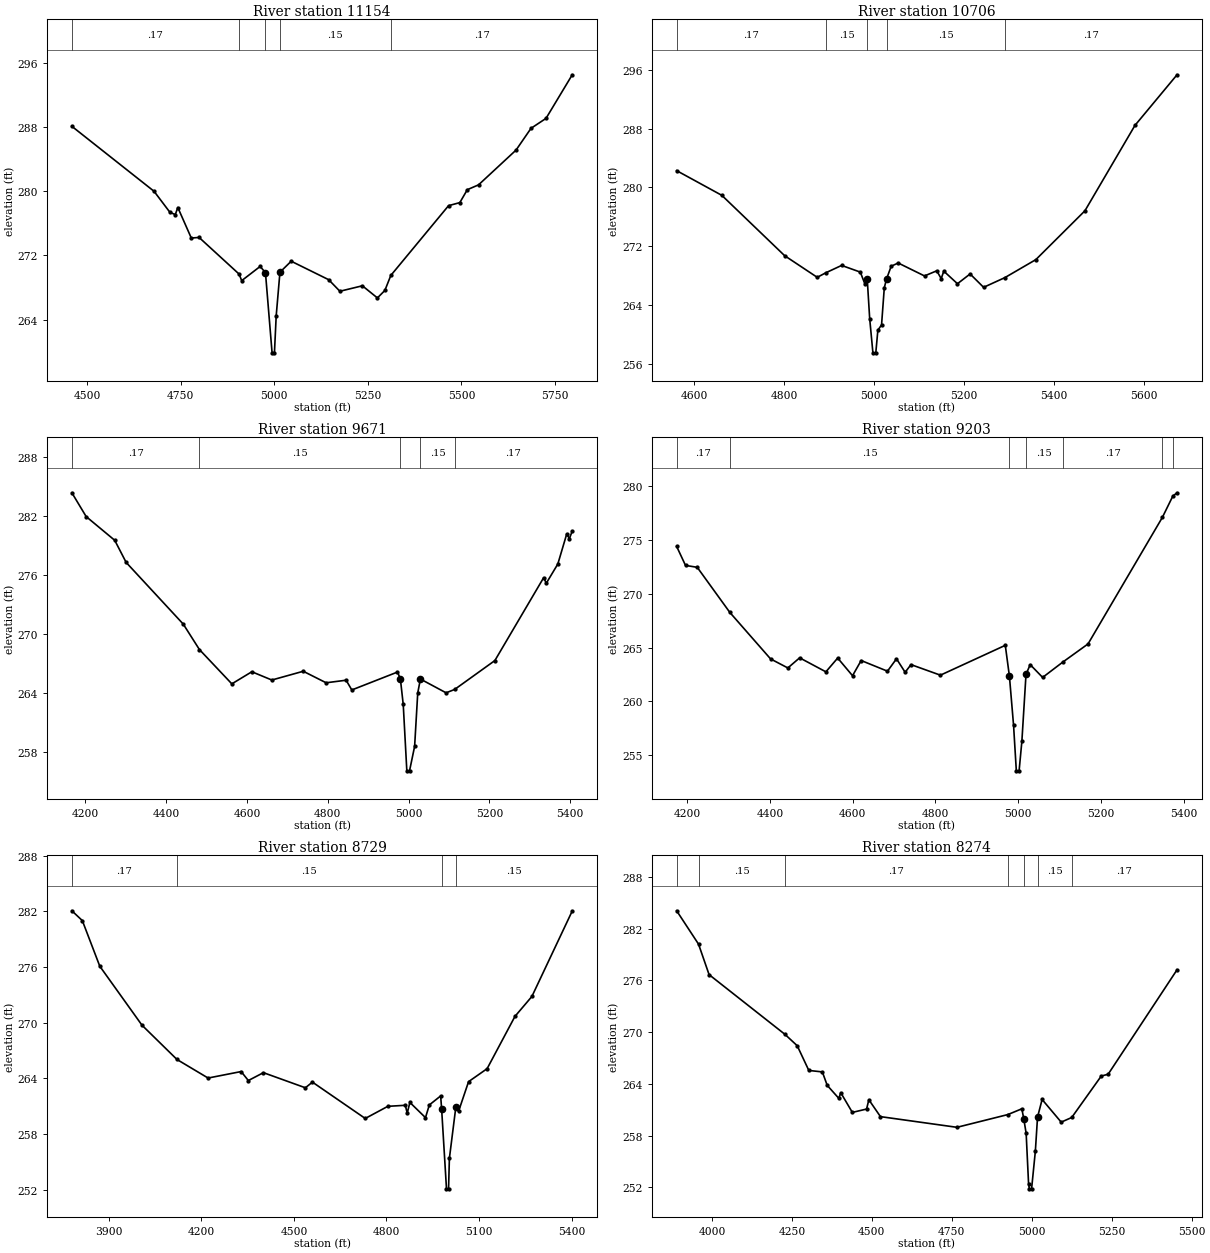
Type RM Length L Ch R = 1 ,11154   ,448,448,448
BEGIN DESCRIPTION:
LAKE CREEK TRIBUTARY NO. 8 19.0
END DESCRIPTION:
XS GIS Cut Line= 3
      3731167.85     10174411.07      3730762.95     10174052.43
      3729967.82     10174011.07
#Sta/Elev= 30
  4459.1  288.08  4678.7  279.99  4721.3  277.36  4735.5  277.09  4742.2  277.97
  4778.2  274.17  4799.1  274.24  4905.9  269.68  4912.9  268.86  4962.2  270.63
  4976.4  269.86  4994.1  259.87  5000.4  259.87  5005.1  264.48  5015.1  269.91
  5045.2  271.28  5145.3  268.98  5175.3  267.54  5235.4  268.22  5275.5  266.71
  5295.5  267.64  5311.4  269.51  5465.7   278.2  5495.8  278.58  5515.8  280.19
  5545.8  280.79    5646  285.12    5686  287.83  5726.1  289.07  5796.2   294.5
#Mann= 5 ,-1 , 0
  4459.1     .17       0  4905.9     .15       0  4976.4     .09       0
  5015.1     .15       0  5311.4     .17       0
Bank Sta=4976.4,5015.1
XS Rating Curve= 0 ,0
Exp/Cntr=0.3,0.1

Type RM Length L Ch R = 1 ,10706   ,1035,1035,1035
BEGIN DESCRIPTION:
LAKE CREEK TRIBUTARY NO. 8 18.0
END DESCRIPTION:
XS GIS Cut Line= 3
      3731270.18     10173773.76      3730837.87     10173648.75
      3730267.81     10173311.05
#Sta/Elev= 30
  4561.4  282.28  4661.9  278.92  4801.6  270.71    4874  267.77  4893.1  268.39
  4928.2  269.39  4969.8  268.48    4980  266.86  4985.2   267.5  4990.6  262.16
  4997.8   257.5  5004.2   257.5  5008.8  260.58    5017   261.3  5023.1  266.36
  5028.1267.5442  5038.4  269.28    5054  269.72  5112.5  267.96  5139.8  268.66
  5149.6  267.59  5155.4  268.61  5185.8   266.9  5213.9  268.23  5243.9  266.41
  5291.2  267.73  5360.1  270.18  5469.2  276.82  5580.4  288.43    5674  295.32
#Mann= 5 ,-1 , 0
  4561.4     .17       0  4893.1     .15       0  4985.2     .09       0
  5028.1     .15       0  5291.2     .17       0
Bank Sta=4985.2,5028.1
XS Rating Curve= 0 ,0
Exp/Cntr=0.3,0.1

Type RM Length L Ch R = 1 ,9671    ,468,468,468
BEGIN DESCRIPTION:
LAKE CREEK TRIBUTARY NO. 8 17.0
END DESCRIPTION:
XS GIS Cut Line= 3
      3731467.88      10173461.1      3730875.57     10172874.68
      3730567.84     10172611.06
#Sta/Elev= 30
  4166.5  284.38  4201.9  281.96  4272.6  279.55  4300.9   277.3  4442.3  271.03
  4482.2  268.45  4562.5  264.96    4612  266.19  4661.5  265.35  4739.3  266.24
  4795.9  265.07  4845.4  265.33  4859.5  264.34  4972.6  266.16  4979.7  265.47
  4986.8  262.87  4995.7  256.12  5002.4  256.12    5015  258.61  5022.7  264.03
  5029.3  265.45  5092.9  264.05    5114  264.39  5213.7  267.33  5334.4  275.75
    5341  275.19  5369.5  277.14  5391.5  280.19  5398.1  279.72  5405.2  280.49
#Mann= 5 ,-1 , 0
  4166.5     .17       0  4482.2     .15       0  4979.7     .09       0
  5029.3     .15       0    5114     .17       0
Bank Sta=4979.7,5029.3
XS Rating Curve= 0 ,0
Exp/Cntr=0.3,0.1

Type RM Length L Ch R = 1 ,9203    ,474,474,474
BEGIN DESCRIPTION:
LAKE CREEK TRIBUTARY NO. 8 16.0
END DESCRIPTION:
XS GIS Cut Line= 3
      3731567.87     10173011.09      3731067.04     10172445.63
      3730613.87     10172409.17
#Sta/Elev= 30
  4174.2  274.39  4195.6  272.63    4224  272.45  4302.9  268.26  4401.3  263.95
  4443.1  263.11  4471.6  264.05  4535.1  262.75  4563.6  264.03  4599.5  262.39
  4620.4   263.8    4684  262.81  4705.8  263.96  4726.7  262.71  4740.9  263.42
    4812  262.44  4968.9  265.21  4978.9  262.34  4988.9  257.79  4995.6  253.56
  5002.3  253.56    5009   256.3    5019  262.51  5029.1  263.42  5059.2  262.23
  5107.8  263.65    5169  265.34  5348.8  277.09    5374  279.06  5384.2  279.37
#Mann= 7 ,-1 , 0
  4174.2     .17       0  4302.9     .15       0  4978.9     .09       0
    5019     .15       0  5107.8     .17       0  5348.8     .15       0
    5374     .17       0
Bank Sta=4978.9,5019
XS Rating Curve= 0 ,0
Exp/Cntr=0.3,0.1

Type RM Length L Ch R = 1 ,8729    ,455,455,455
BEGIN DESCRIPTION:
LAKE CREEK TRIBUTARY NO. 8 15.0
END DESCRIPTION:
XS GIS Cut Line= 3
      3731785.78     10173028.94      3731056.62      10171992.5
      3730702.61     10171966.47
#Sta/Elev= 30
  3780.1  282.07    3814  281.01  3870.6  276.09  4007.4  269.73  4120.9  266.03
  4221.7  264.03  4328.9  264.73  4352.2  263.76  4401.1  264.61  4537.1  262.98
    4560  263.59  4731.2  259.67  4804.5  260.98  4861.1  261.09  4867.3  260.24
  4875.9   261.4  4926.5  259.76    4939  261.13  4975.7   262.1 4978.84260.6914
  4994.6  252.08  5001.3  252.08    5004  255.37  5024.9   260.9  5033.6  260.43
  5066.2  263.64  5126.3  265.04  5216.6  270.68  5271.5  272.83  5402.3  282.05
#Mann= 4 ,-1 , 0
  3780.1     .17       0  4120.9     .15       0 4978.84     .09       0
  5024.9     .15       0
Bank Sta=4978.84,5024.9
XS Rating Curve= 0 ,0
Exp/Cntr=0.3,0.1

Type RM Length L Ch R = 1 ,8274    ,582,582,582
BEGIN DESCRIPTION:
LAKE CREEK TRIBUTARY NO. 8 14.0
END DESCRIPTION:
XS GIS Cut Line= 3
      3732117.83     10172211.06      3731119.12     10171570.63
      3730767.86     10171711.07
#Sta/Elev= 30
  3889.6  284.08    3958  280.21    3991  276.67  4228.2  269.74  4266.6  268.42
  4302.9  265.55  4345.2  265.38  4360.4  263.82  4396.7  262.31  4402.7  262.97
    4439  260.68  4483.5  261.07  4490.6  262.15  4526.9  260.19  4766.1  258.95
  4925.4  260.43    4969   261.1  4974.9  259.97  4982.5  258.25  4990.1  252.37
  4992.6  251.81  4999.5  251.81  5011.3  256.19  5018.1  260.13  5032.4  262.18
  5092.1  259.55    5125  260.09  5217.4   264.9  5238.9  265.11  5454.3  277.23
#Mann= 7 ,-1 , 0
  3889.6     .17       0    3958     .15       0  4228.2     .17       0
  4925.4     .15       0  4974.9     .09       0  5018.1     .15       0
    5125     .17       0
Bank Sta=4974.9,5018.1
XS Rating Curve= 0 ,0
Exp/Cntr=0.3,0.1

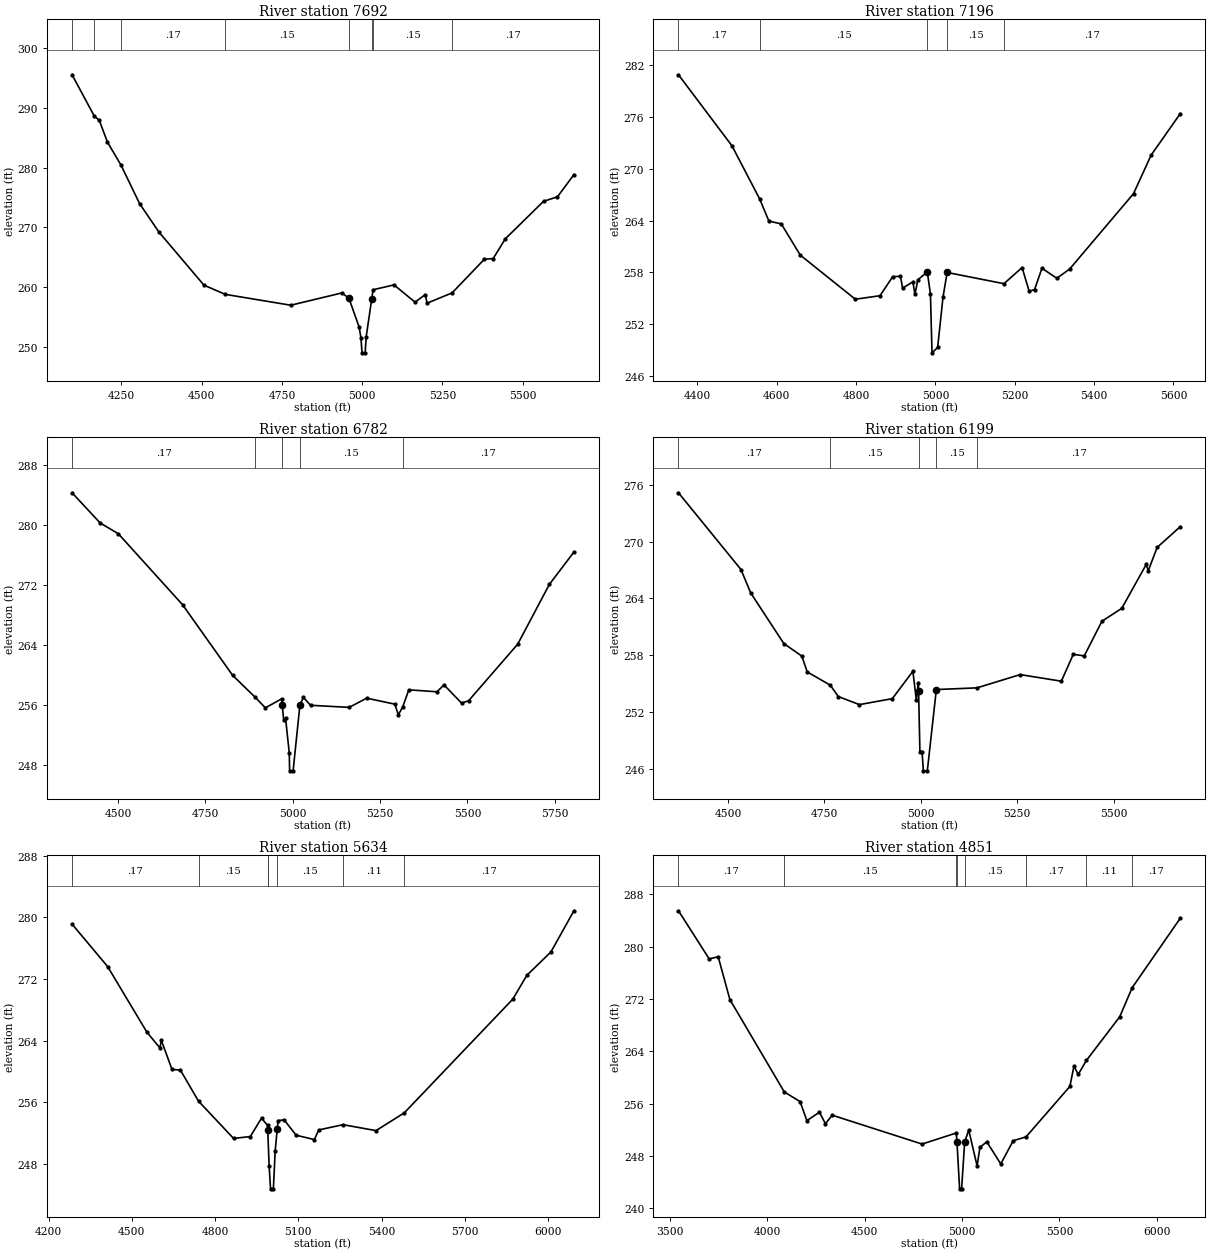
Type RM Length L Ch R = 1 ,7692    ,496,496,496
BEGIN DESCRIPTION:
LAKE CREEK TRIBUTARY NO. 8 13.0
END DESCRIPTION:
XS GIS Cut Line= 3
      3732317.89     10171261.07      3731542.73     10171214.72
      3730855.24     10170832.78
#Sta/Elev= 30
  4096.4  295.58  4166.2   288.6  4180.9  287.98  4206.6  284.29  4248.5  280.47
  4306.8  273.98  4366.9  269.22  4507.2  260.32  4573.4  258.78  4777.6  256.96
  4936.7  259.02  4958.6  258.14  4990.5  253.29  4996.2  251.45  4999.4  248.98
  5009.3  248.98  5012.2  251.58  5029.7 258.033  5033.9  259.55  5099.1  260.37
  5164.5  257.47  5196.4  258.73  5202.1   257.3  5280.1  259.03  5380.5  264.67
    5408  264.78  5445.7  268.09  5564.7  274.37  5608.2  275.13  5659.4  278.85
#Mann= 8 ,-1 , 0
  4096.4     .17       0  4166.2     .15       0  4248.5     .17       0
  4573.4     .15       0  4958.6     .09       0  5029.7     .12       0
  5033.9     .15       0  5280.1     .17       0
Bank Sta=4958.6,5029.7
XS Rating Curve= 0 ,0
Exp/Cntr=0.3,0.1

Type RM Length L Ch R = 1 ,7196    ,414,414,414
BEGIN DESCRIPTION:
LAKE CREEK TRIBUTARY NO. 8 12.0
END DESCRIPTION:
XS GIS Cut Line= 3
       3732167.8     10171061.06      3731556.09     10170848.48
      3730967.82     10170661.06
#Sta/Elev= 30
  4352.4   280.9  4487.1  272.68  4556.9  266.53  4580.4  263.95  4611.5  263.63
  4659.4  260.01  4798.2   254.9  4860.5  255.31  4892.3  257.51    4912  257.56
  4917.3  256.18  4943.2  256.91  4948.5  255.47  4955.8  257.15  4979.6  258.07
  4987.5  255.51  4991.5  248.69  5005.7  249.31  5019.1  255.11  5029.6     258
  5172.8   256.7  5218.5  258.57  5236.4  255.82    5250  256.02  5268.6  258.49
  5306.1  257.33  5338.3  258.39  5499.4  267.13  5543.9   271.6  5617.4  276.41
#Mann= 5 ,-1 , 0
  4352.4     .17       0  4556.9     .15       0  4979.6     .09       0
  5029.6     .15       0  5172.8     .17       0
Bank Sta=4979.6,5029.6
XS Rating Curve= 0 ,0
Exp/Cntr=0.3,0.1

Type RM Length L Ch R = 1 ,6782    ,583,583,583
BEGIN DESCRIPTION:
LAKE CREEK TRIBUTARY NO. 8 11.0
END DESCRIPTION:
XS GIS Cut Line= 3
      3732348.29     10170777.22       3731771.9     10170527.22
      3730967.83     10170611.07
#Sta/Elev= 30
  4368.1  284.33  4448.4  280.31  4500.7  278.86  4684.7  269.39  4827.6     260
  4892.8  257.05  4921.5  255.66  4968.1  256.86  4969.9255.9853  4973.8  254.09
  4979.3  254.28  4989.9  249.63  4990.9  247.26  5000.9  247.26  5020.5   256.1
  5030.6  257.05  5050.7     256  5161.3  255.72  5211.6  256.95    5292  256.15
  5302.1  254.74  5314.2  255.73  5332.2  258.06  5412.7   257.8  5432.8  258.72
    5483   256.3  5503.2   256.6  5643.9  264.15  5734.4  272.11  5804.8  276.43
#Mann= 5 ,-1 , 0
  4368.1     .17       0  4892.8     .15       0  4969.9     .09       0
  5020.5     .15       0  5314.2     .17       0
Bank Sta=4969.9,5020.5
XS Rating Curve= 0 ,0
Exp/Cntr=0.3,0.1

Type RM Length L Ch R = 1 ,6199    ,565,565,565
BEGIN DESCRIPTION:
LAKE CREEK TRIBUTARY NO. 8 10.0
END DESCRIPTION:
XS GIS Cut Line= 3
      3732217.86     10169761.07      3731628.61     10169978.82
      3731017.87     10170261.06
#Sta/Elev= 30
  4371.8  275.15  4533.8  267.05  4558.9  264.59  4644.8  259.24  4691.6  257.91
  4705.6  256.24  4765.4  254.84  4786.2  253.64  4840.9  252.79  4926.2  253.42
  4979.5  256.31  4988.4  253.29  4993.8  255.12  4994.3254.1868  4997.7  247.84
  5003.2  247.84  5006.7   245.8  5016.9   245.8  5040.3  254.38  5145.7  254.56
  5257.7  255.96  5364.4  255.26  5395.3   258.1  5423.7  257.93  5469.6  261.59
    5521  262.95  5584.3  267.58  5589.8  266.93  5612.7  269.38  5672.8  271.58
#Mann= 5 ,-1 , 0
  4371.8     .17       0  4765.4     .15       0  4994.3     .09       0
  5040.3     .15       0  5145.7     .17       0
Bank Sta=4994.3,5040.3
XS Rating Curve= 0 ,0
Exp/Cntr=0.3,0.1

Type RM Length L Ch R = 1 ,5634    ,783,783,783
BEGIN DESCRIPTION:
LAKE CREEK TRIBUTARY NO. 8 9.0
END DESCRIPTION:
XS GIS Cut Line= 3
      3732264.99      10169506.4      3731612.18     10169423.06
      3730605.19     10169978.64
#Sta/Elev= 30
  4284.7  279.12  4412.9  273.61    4554  265.12  4601.3  263.06  4606.3  264.05
  4644.7  260.28    4675  260.19  4740.3  256.16  4866.5  251.33    4927  251.57
  4967.3  253.96  4989.1  253.01  4989.7 252.452  4994.8  247.71  4999.8  244.79
    5010  244.79  5016.6  249.74  5024.2252.6104  5026.9  253.63  5048.7  253.74
  5092.2  251.74  5157.6  251.18  5173.6  252.43    5261  253.11  5379.9  252.34
  5481.9  254.65  5872.9   269.4  5923.1  272.47  6010.2  275.52  6092.9  280.85
#Mann= 7 ,-1 , 0
  4284.7     .17       0  4740.3     .15       0  4989.1     .12       0
  4989.7     .09       0  5024.2     .15       0    5261     .11       0
  5481.9     .17       0
Bank Sta=4989.7,5024.2
XS Rating Curve= 0 ,0
Exp/Cntr=0.3,0.1

Type RM Length L Ch R = 1 ,4851    ,637,637,637
BEGIN DESCRIPTION:
LAKE CREEK TRIBUTARY NO. 8 8.0
END DESCRIPTION:
XS GIS Cut Line= 3
      3732376.08     10169457.79      3731126.06     10168936.95
      3730356.15     10169887.21
#Sta/Elev= 30
  3543.9  285.46  3701.7  278.11  3747.8  278.44  3807.9   271.9  4087.3  257.79
  4168.6  256.31  4203.3   253.4  4267.8   254.7  4298.6  252.93  4333.3  254.24
  4794.8  249.83  4970.5  251.52  4974.1250.1301  4987.6  242.99  4997.9  242.99
  5013.6  250.11  5034.4  251.97  5077.5  246.49  5091.9  249.32  5127.1  250.18
    5199   246.8  5262.9  250.34  5328.8  250.93  5553.9  258.63  5574.7  261.72
    5597  260.47  5638.7   262.6  5809.7  269.26    5874  273.72  6121.1  284.33
#Mann= 8 ,-1 , 0
  3543.9     .17       0  4087.3     .15       0  4970.5     .12       0
  4974.1     .09       0  5013.6     .15       0  5328.8     .17       0
  5638.7     .11       0    5874     .17       0
Bank Sta=4974.1,5013.6
XS Rating Curve= 0 ,0
Exp/Cntr=0.3,0.1

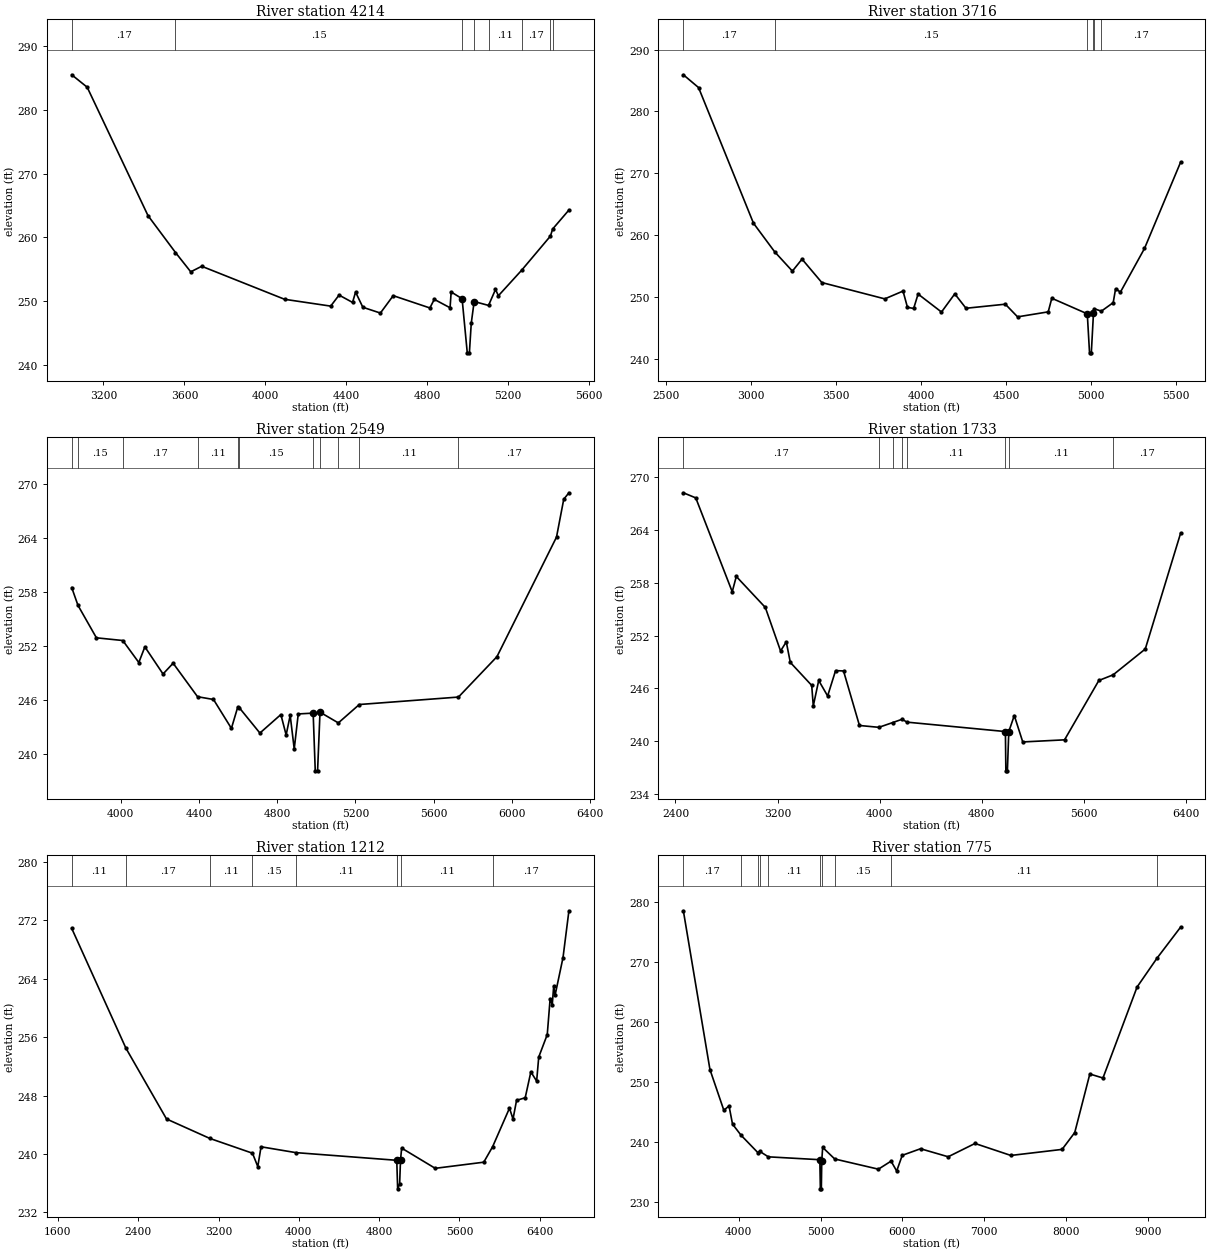
Type RM Length L Ch R = 1 ,4214    ,498,498,498
BEGIN DESCRIPTION:
LAKE CREEK TRIBUTARY NO. 8 6.0
END DESCRIPTION:
XS GIS Cut Line= 5
       3732369.1     10169381.38      3731091.34     10168881.39
      3730841.34     10168513.34      3730713.72     10168571.29
      3730323.08     10168886.26
#Sta/Elev= 30
  3042.8  285.51  3119.3  283.56    3420  263.42    3556  257.63  3631.5   254.6
  3685.8  255.47  4095.7  250.29  4323.6  249.22    4365  250.95  4431.7   249.8
  4446.7  251.42  4482.6  249.04  4569.4  248.13  4632.9  250.86  4814.2  248.93
  4835.9  250.28    4914  248.96  4919.4  251.44  4973.5  250.38  4999.1  241.89
  5009.6  241.89  5018.8  246.52  5033.1  249.94  5104.3  249.33  5138.7  251.83
  5153.1  250.85  5267.8  254.84  5410.5  260.21  5421.2  261.31  5501.8  264.29
#Mann= 8 ,-1 , 0
  3042.8     .17       0    3556     .15       0  4973.5     .09       0
  5033.1     .15       0  5104.3     .11       0  5267.8     .17       0
  5410.5     .15       0  5421.2     .17       0
Bank Sta=4973.5,5033.1
XS Rating Curve= 0 ,0
Exp/Cntr=0.3,0.1

Type RM Length L Ch R = 1 ,3716    ,1167,1167,1167
BEGIN DESCRIPTION:
LAKE CREEK TRIBUTARY NO. 8 5.0
END DESCRIPTION:
XS GIS Cut Line= 5
      3732417.76     10169305.01      3731105.23     10168853.61
      3730667.76     10168199.16      3730445.99     10168194.75
      3730067.84     10168561.09
#Sta/Elev= 30
    2603  285.94  2692.4  283.87  3015.3  261.93  3139.2  257.33  3244.1  254.18
  3300.8  256.12  3417.2  252.33  3787.3  249.69  3894.7  250.95  3920.7  248.32
  3957.2  248.14  3983.2  250.47  4120.8  247.56  4198.9   250.5  4264.9  248.17
  4496.2  248.83  4568.2  246.78  4748.4  247.59  4769.4  249.79  4978.1  247.27
  4991.3  240.96  5001.8  240.96 5014.44247.3624  5017.3  248.11  5060.8   247.7
  5130.5  249.08  5144.6  251.34  5172.9  250.78  5314.4  257.84  5526.5  271.78
#Mann= 6 ,-1 , 0
    2603     .17       0  3139.2     .15       0  4978.1     .09       0
 5014.44     .12       0  5017.3     .15       0  5060.8     .17       0
Bank Sta=4978.1,5014.44
XS Rating Curve= 0 ,0
Exp/Cntr=0.3,0.1

Type RM Length L Ch R = 1 ,2549    ,816,816,816
BEGIN DESCRIPTION:
Mapping XS 1c1450c8
END DESCRIPTION:
XS GIS Cut Line= 3
      3731190.29      10166987.3      3729801.41     10167334.52
      3729983.51     10168427.12
#Sta/Elev= 30
  3750.8   258.5  3782.9  256.51    3877   252.9  4011.6   252.6  4093.5  250.15
  4124.4  251.89  4217.2  248.87  4268.7  250.07  4393.4  246.34  4474.9  246.03
  4566.4  242.81  4598.8  245.19  4607.5  245.09  4711.9  242.29    4819  244.35
  4845.9  242.08  4866.6  244.26  4887.2  240.52  4907.8  244.42  4983.9  244.51
  4994.6  238.08  5006.5  238.08 5018.87244.6155  5112.5  243.42  5219.5  245.47
    5726   246.3  5922.6   250.8  6226.7  264.12  6263.7  268.34  6290.1  269.06
#Mann= 11 ,-1 , 0
  3750.8     .17       0  3782.9     .15       0  4011.6     .17       0
  4393.4     .11       0  4598.8     .17       0  4607.5     .15       0
  4983.9     .09       0 5018.87     .15       0  5112.5     .17       0
  5219.5     .11       0    5726     .17       0
Bank Sta=4983.9,5018.87
XS Rating Curve= 0 ,0
Exp/Cntr=0.3,0.1

Type RM Length L Ch R = 1 ,1733    ,521,521,521
BEGIN DESCRIPTION:
LAKE CREEK TRIBUTARY NO. 8 3.0
END DESCRIPTION:
XS GIS Cut Line= 4
       3731539.7     10166206.04      3729282.75     10166987.29
       3729271.9     10167258.56      3729917.83     10168311.03
#Sta/Elev= 30
    2462  268.22  2559.2  267.64  2844.9  256.98  2876.7  258.72  3104.1   255.2
  3223.5  250.26  3268.2  251.29  3299.9  248.96  3467.4  246.35  3479.8  244.02
  3522.2  246.91  3592.1  245.15  3654.4  248.03  3716.7  247.99  3841.4   241.8
  3993.6  241.59  4101.7  242.13  4176.2  242.51  4212.7  242.18 4984.66241.1099
  4988.3  236.65  5000.2  236.65  5011.2241.1079  5054.3  242.93  5120.6  239.93
    5448  240.17  5716.8  246.91  5828.7  247.55  6080.3  250.48  6356.7  263.61
#Mann= 8 ,-1 , 0
    2462     .17       0  3993.6     .15       0  4101.7     .11       0
  4176.2     .15       0  4212.7     .11       0 4984.66     .06       0
  5011.2     .11       0  5828.7     .17       0
Bank Sta=4984.66,5011.2
XS Rating Curve= 0 ,0
Exp/Cntr=0.3,0.1

Type RM Length L Ch R = 1 ,1212    ,437,437,437
BEGIN DESCRIPTION:
LAKE CREEK TRIBUTARY NO. 8 2.0
END DESCRIPTION:
XS GIS Cut Line= 4
      3731593.96     10165934.77      3728740.21     10166824.53
      3728772.77     10167204.31      3729760.21     10168441.32
#Sta/Elev= 30
  1737.6  270.92  2277.5  254.51  2682.1  244.81  3112.7  242.15  3538.4  240.12
  3591.3  238.29  3623.8     241    3971   240.2 4975.74239.1495  4984.7  235.24
  5004.4  235.91 5013.12239.1801  5024.5  240.82    5359  238.05  5842.5  238.89
  5930.7  241.01  6098.7  246.29  6133.9   244.8  6169.2  247.36  6255.4  247.72
  6311.7  251.26  6369.3     250  6390.1  253.29    6475  256.37  6503.8   261.3
  6524.6  260.43    6539  262.97  6553.5   261.8  6631.9  266.91  6690.8  273.33
#Mann= 8 ,-1 , 0
  1737.6     .11       0  2277.5     .17       0  3112.7     .11       0
  3538.4     .15       0    3971     .11       0 4975.74     .06       0
 5013.12     .11       0  5930.7     .17       0
Bank Sta=4975.74,5013.12
XS Rating Curve= 0 ,0
Exp/Cntr=0.3,0.1

Type RM Length L Ch R = 1 ,775     ,0,0,0
BEGIN DESCRIPTION:
LAKE CREEK TRIBUTARY NO. 8 1.0
END DESCRIPTION:
XS GIS Cut Line= 4
      3729667.83     10168561.05      3728469.82      10167385.4
      3728327.89     10166737.73      3731789.26     10165327.14
#Sta/Elev= 30
  3321.5  278.55  3646.7  252.06  3816.4  245.27  3880.2  245.99  3922.6  242.96
  4027.1   241.1  4232.7   238.2  4253.3  238.43  4360.4   237.5  4990.3  237.02
  4996.7  232.16  5008.6  232.16  5013.8236.8477  5024.9  239.07  5172.6  237.14
  5706.2  235.44  5861.1  236.78    5930  235.13  5997.8  237.75  6221.5  238.85
  6559.3  237.51  6887.5  239.73    7326  237.73  7952.3  238.74    8107  241.55
  8291.6  251.32  8452.1  250.65  8869.2  265.83  9111.2  270.61  9400.8  275.81
#Mann= 10 ,-1 , 0
  3321.5     .17       0  4027.1     .15       0  4232.7     .17       0
  4253.3     .15       0  4360.4     .11       0  4990.3     .06       0
  5013.8     .11       0  5172.6     .15       0  5861.1     .11       0
  9111.2     .17       0
Bank Sta=4990.3,5013.8
XS Rating Curve= 0 ,0
Exp/Cntr=0.3,0.1

Chan Stop Cuts=-1
Use User Specified Reach Order=0
Composite Channel Slope=5