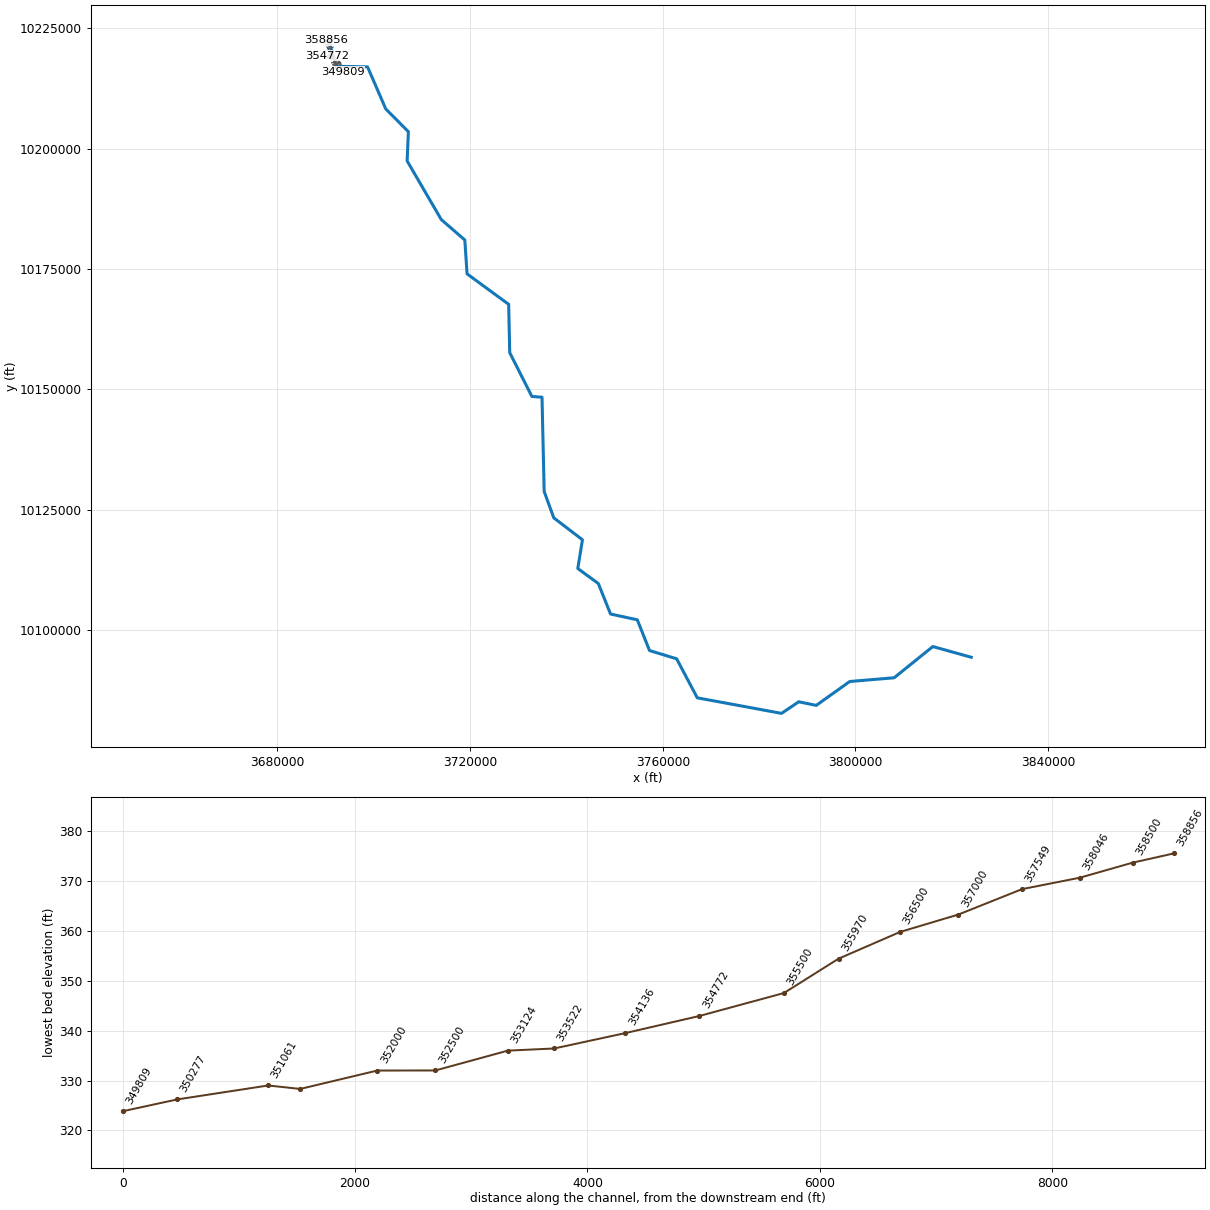
--- LAKE CREEK.prj (project) ---

Proj Title=LAKE CREEK Base Level Engineering
Current Plan=p01
Default Exp/Contr=0.3,0.1
English Units
Geom File=g01
Flow File=f01
Flow File=f02
Plan File=p01
Y Axis Title=Elevation
X Axis Title(PF)=Main Channel Distance
X Axis Title(XS)=Station
BEGIN DESCRIPTION:
LAKE CREEK
END DESCRIPTION:
DSS Export Rating Curves= 0
DSS Export Rating Curve Sorted= 0
DSS Export Volume Flow Curves= 0
DXF OffsetX= 0
DXF OffsetY= 0
DXF ScaleX= 1
DXF ScaleY= 10

--- LAKE CREEK.p01 (plan) ---

Plan Title=Multiple Run
Short Identifier=Multiple
Geom File=g01
Flow File=f01
Subcritical Flow
K Sum by GR= 0
Std Step Tol= 0.01
Critical Tol= 0.01
Num of Std Step Trials= 20
Max Error Tol= 0.3
Flow Tol Ratio= 0.001
Split Flow NTrial= 30
Split Flow Tol= 0.02
Split Flow Ratio= 0.02
Log Output Level= 0
Friction Slope Method= 1
Unsteady Friction Slope Method= 2
Unsteady Bridges Friction Slope Method= 1
Parabolic Critical Depth
Global Vel Dist=  1 , 1 , 1
Global Log Level= 0
CheckData=True
Encroach Param= -1, 0, 0, 0
BEGIN DESCRIPTION:
Multiple Run
END DESCRIPTION:

--- LAKE CREEK.f01 (steady flow) ---

Flow Title=Multiple
Program Version=4.10
Number of Profiles= 7
Profile Names=10-year,25-year,50-year,1pct_min,100-year,1pct_plu,500-year
River Rch & RM=LAKE CREEK,Reach-1         ,358856
     639     869    1176     524    1583    4781    2964
River Rch & RM=LAKE CREEK,Reach-1         ,349809
    1404    1985    2759    1257    3797   11467    7449
River Rch & RM=LAKE CREEK,Reach-1         ,342475
    3190    4649    6596    3061    9244   27916   18808
River Rch & RM=LAKE CREEK,Reach-1         ,336405
    3322    4843    6872    3188    9629   29079   19582
River Rch & RM=LAKE CREEK,Reach-1         ,334000
    3321    4837    6861    3181    9607   29013   19517
River Rch & RM=LAKE CREEK,Reach-1         ,333000
    3542    5166    7332    3402   10275   31030   20896
River Rch & RM=LAKE CREEK,Reach-1         ,331000
    3703    5402    7667    3557   10741   32437   21835
River Rch & RM=LAKE CREEK,Reach-1         ,328500
    3785    5499    7784    3600   10871   32830   21959
River Rch & RM=LAKE CREEK,Reach-1         ,322500
    3915    5695    8067    3734   11275   34050   22811
River Rch & RM=LAKE CREEK,Reach-1         ,322000
    4517    6589    9354    4336   13094   39543   26574
River Rch & RM=LAKE CREEK,Reach-1         ,314500
    4827    7040    9991    4629   13979   42216   28339
River Rch & RM=LAKE CREEK,Reach-1         ,308375
    6424    9448   13490    6283   18975   57304   38872
River Rch & RM=LAKE CREEK,Reach-1         ,307830
    6750    9927   14170    6599   19928   60182   40800
River Rch & RM=LAKE CREEK,Reach-1         ,306500
    6750    9927   14170    6599   19928   60182   40800
River Rch & RM=LAKE CREEK,Reach-1         ,300318
    6798    9993   14260    6638   20046   60538   41010
River Rch & RM=LAKE CREEK,Reach-1         ,298000
    6737    9889   14098    6556   19798   59789   40417
River Rch & RM=LAKE CREEK,Reach-1         ,295338
    7105   10443   14902    6935   20944   63250   42828
River Rch & RM=LAKE CREEK,Reach-1         ,292500
    7193   10572   15087    7021   21203   64032   43356
River Rch & RM=LAKE CREEK,Reach-1         ,290894
    7170   10525   15005    6977   21069   63627   42998
River Rch & RM=LAKE CREEK,Reach-1         ,287118
    7119   10409   14799    6861   20721   62576   42039
River Rch & RM=LAKE CREEK,Reach-1         ,286460
    7119   10409   14799    6861   20721   62576   42039
River Rch & RM=LAKE CREEK,Reach-1         ,276500
    7056   10307   14644    6784   20488   61873   41507
River Rch & RM=LAKE CREEK,Reach-1         ,274498
    7412   10833   15400    7137   21554   65092   43698
River Rch & RM=LAKE CREEK,Reach-1         ,272139
    7605   11128   15832    7343   22175   66967   45024
River Rch & RM=LAKE CREEK,Reach-1         ,270440
    7700   11272   16041    7442   22474   67870   45661
River Rch & RM=LAKE CREEK,Reach-1         ,267720
   10561   15566   22263   10375   31333   94624   64208
River Rch & RM=LAKE CREEK,Reach-1         ,260966
   10655   15668   22371   10408   31431   94920   64180
River Rch & RM=LAKE CREEK,Reach-1         ,252000
   10655   15668   22371   10408   31431   94920   64180
River Rch & RM=LAKE CREEK,Reach-1         ,248000
   10746   15798   22554   10492   31684   95684   64674
River Rch & RM=LAKE CREEK,Reach-1         ,246759
   11166   16407   23414   10887   32877   99287   67046
River Rch & RM=LAKE CREEK,Reach-1         ,240000
   10992   16117   22969   10664   32204   97255   65475
River Rch & RM=LAKE CREEK,Reach-1         ,227021
   11486   16812   23933   11099   33519  101226   67976
River Rch & RM=LAKE CREEK,Reach-1         ,219793
   11415   16731   23840   11064   33414  100909   67894
River Rch & RM=LAKE CREEK,Reach-1         ,219000
   11620   16992   24175   11204   33836  102183   68528
River Rch & RM=LAKE CREEK,Reach-1         ,213829
   11619   16947   24071   11135   33628  101555   67857
River Rch & RM=LAKE CREEK,Reach-1         ,201940
   11769   17153   24351   11258   34000  102678   68525
River Rch & RM=LAKE CREEK,Reach-1         ,191914
   11843   17262   24507   11331   34220  103343   68977
River Rch & RM=LAKE CREEK,Reach-1         ,189735
   14194   20732   29480   13651   41224  124494   83306
River Rch & RM=LAKE CREEK,Reach-1         ,182928
   14196   20735   29484   13652   41228  124507   83313
River Rch & RM=LAKE CREEK,Reach-1         ,181530
   14328   20926   29759   13779   41613  125669   84091
River Rch & RM=LAKE CREEK,Reach-1         ,176927
   14288   20861   29657   13729   41462  125213   83740
River Rch & RM=LAKE CREEK,Reach-1         ,175805
   14287   20857   29648   13723   41444  125159   83688
River Rch & RM=LAKE CREEK,Reach-1         ,174899
   14194   20703   29412   13606   41088  124084   82866
River Rch & RM=LAKE CREEK,Reach-1         ,168971
   14126   20587   29232   13514   40812  123250   82216
River Rch & RM=LAKE CREEK,Reach-1         ,165824
   17558   25681   36567   16951   51190  154591  103630
River Rch & RM=LAKE CREEK,Reach-1         ,163000
   17776   26005   37032   17169   51849  156581  104989
River Rch & RM=LAKE CREEK,Reach-1         ,156351
   17825   26073   37127   17211   51977  156968  105231
River Rch & RM=LAKE CREEK,Reach-1         ,152177
   17724   25905   36868   17082   51587  155790  104327
River Rch & RM=LAKE CREEK,Reach-1         ,147837
   18405   26858   38190   17679   53391  161238  107748
River Rch & RM=LAKE CREEK,Reach-1         ,144904
   18922   27607   39252   18168   54865  165690  110685
River Rch & RM=LAKE CREEK,Reach-1         ,139839
   19128   27902   39667   18358   55440  167426  111817
River Rch & RM=LAKE CREEK,Reach-1         ,134000
   19125   27873   39599   18315   55310  167034  111404
River Rch & RM=LAKE CREEK,Reach-1         ,126188
   19125   27873   39599   18315   55310  167034  111404
River Rch & RM=LAKE CREEK,Reach-1         ,125000
   19146   27886   39603   18309   55292  166979  111272
River Rch & RM=LAKE CREEK,Reach-1         ,123847
   19193   27948   39685   18344   55397  167296  111446
River Rch & RM=LAKE CREEK,Reach-1         ,119032
   19193   27948   39685   18344   55397  167296  111446
River Rch & RM=LAKE CREEK,Reach-1         ,117000
   19257   28009   39743   18355   55432  167402  111336
River Rch & RM=LAKE CREEK,Reach-1         ,109357
   19257   28009   39743   18355   55432  167402  111336
River Rch & RM=LAKE CREEK,Reach-1         ,103711
   19101   27742   39323   18143   54790  165463  109813
River Rch & RM=LAKE CREEK,Reach-1         ,90132
   19248   27950   39613   18274   55188  166665  110581
River Rch & RM=LAKE CREEK,Reach-1         ,87000
   19549   28385   40228   18557   56042  169244  112278
River Rch & RM=LAKE CREEK,Reach-1         ,82773
   19480   28271   40056   18472   55784  168465  111692
River Rch & RM=LAKE CREEK,Reach-1         ,81000
   19585   28395   40203   18526   55948  168960  111853
River Rch & RM=LAKE CREEK,Reach-1         ,66728
   19585   28395   40203   18526   55948  168960  111853
River Rch & RM=LAKE CREEK,Reach-1         ,64363
   20343   29454   41671   19188   57948  175000  115639
River Rch & RM=LAKE CREEK,Reach-1         ,53000
   20343   29454   41671   19188   57948  175000  115639
River Rch & RM=LAKE CREEK,Reach-1         ,50000
   20416   29556   41812   19252   58140  175580  116004
River Rch & RM=LAKE CREEK,Reach-1         ,45042
   20415   29551   41803   19246   58123  175529  115957
River Rch & RM=LAKE CREEK,Reach-1         ,44395
   20460   29613   41888   19284   58236  175870  116160
River Rch & RM=LAKE CREEK,Reach-1         ,40899
   20460   29613   41888   19284   58236  175870  116160
River Rch & RM=LAKE CREEK,Reach-1         ,40632
   21439   31038   43914   20222   61068  184422  121855
River Rch & RM=LAKE CREEK,Reach-1         ,39384
   21439   31038   43914   20222   61068  184422  121855
River Rch & RM=LAKE CREEK,Reach-1         ,31779
   21462   31068   43955   20239   61121  184582  121946
River Rch & RM=LAKE CREEK,Reach-1         ,29940
   21741   31463   44504   20488   61872  186850  123391
River Rch & RM=LAKE CREEK,Reach-1         ,25000
   21741   31463   44504   20488   61872  186850  123391
River Rch & RM=LAKE CREEK,Reach-1         ,22191
   21750   31465   44497   20480   61848  186778  123279
River Rch & RM=LAKE CREEK,Reach-1         ,17000
   21670   31333   44296   20379   61545  185863  122588
River Rch & RM=LAKE CREEK,Reach-1         ,11221
   21550   31132   43984   20224   61074  184441  121494
River Rch & RM=LAKE CREEK,Reach-1         ,3866
   21529   31088   43907   20182   60948  184060  121165
Boundary for River Rch & Prof#=LAKE CREEK,Reach-1         , 1
Up Type= 0
Dn Type= 3
Dn Slope=0.0005
Boundary for River Rch & Prof#=LAKE CREEK,Reach-1         , 2
Up Type= 0
Dn Type= 3
Dn Slope=0.0005
Boundary for River Rch & Prof#=LAKE CREEK,Reach-1         , 3
Up Type= 0
Dn Type= 3
Dn Slope=0.0005
Boundary for River Rch & Prof#=LAKE CREEK,Reach-1         , 4
Up Type= 0
Dn Type= 3
Dn Slope=0.0005
Boundary for River Rch & Prof#=LAKE CREEK,Reach-1         , 5
Up Type= 0
Dn Type= 3
Dn Slope=0.0005
Boundary for River Rch & Prof#=LAKE CREEK,Reach-1         , 6
Up Type= 0
Dn Type= 3
Dn Slope=0.0005
Boundary for River Rch & Prof#=LAKE CREEK,Reach-1         , 7
Up Type= 0
Dn Type= 3
Dn Slope=0.0005
DSS Import GetInterval= 0
DSS Import GetPeak= 0
DSS Import FillOption= 0

--- LAKE CREEK.f02 (steady flow) ---

Flow Title=Orig_BLE_Flows
Program Version=4.10
Number of Profiles= 7
Profile Names=10-year,25-year,50-year,1pct_min,100-year,1pct_plu,500-year
River Rch & RM=LAKE CREEK,Reach-1         ,358856
     639     852    1023     403    1218    3678    1723
River Rch & RM=LAKE CREEK,Reach-1         ,349809
    1404    1946    2399     967    2921    8820    4331
River Rch & RM=LAKE CREEK,Reach-1         ,342475
    3190    4558    5736    2355    7111   21476   10935
River Rch & RM=LAKE CREEK,Reach-1         ,336405
    3322    4748    5976    2453    7407   22368   11385
River Rch & RM=LAKE CREEK,Reach-1         ,334000
    3321    4742    5966    2447    7390   22318   11347
River Rch & RM=LAKE CREEK,Reach-1         ,333000
    3542    5065    6376    2617    7904   23868   12149
River Rch & RM=LAKE CREEK,Reach-1         ,331000
    3703    5296    6667    2736    8262   24952   12695
River Rch & RM=LAKE CREEK,Reach-1         ,328500
    3785    5391    6769    2769    8362   25253   12767
River Rch & RM=LAKE CREEK,Reach-1         ,322500
    3915    5583    7015    2872    8673   26191   13262
River Rch & RM=LAKE CREEK,Reach-1         ,322000
    4517    6460    8134    3335   10072   30418   15450
River Rch & RM=LAKE CREEK,Reach-1         ,314500
    4827    6902    8688    3561   10753   32474   16476
River Rch & RM=LAKE CREEK,Reach-1         ,308375
    6424    9263   11730    4833   14596   44079   22600
River Rch & RM=LAKE CREEK,Reach-1         ,307830
    6750    9732   12322    5076   15329   46293   23721
River Rch & RM=LAKE CREEK,Reach-1         ,306500
    6750    9732   12322    5076   15329   46293   23721
River Rch & RM=LAKE CREEK,Reach-1         ,300318
    6798    9797   12400    5106   15420   46568   23843
River Rch & RM=LAKE CREEK,Reach-1         ,298000
    6737    9695   12259    5043   15229   45990   23498
River Rch & RM=LAKE CREEK,Reach-1         ,295338
    7105   10238   12958    5335   16111   48655   24900
River Rch & RM=LAKE CREEK,Reach-1         ,292500
    7193   10365   13119    5401   16310   49257   25207
River Rch & RM=LAKE CREEK,Reach-1         ,290894
    7170   10319   13048    5367   16207   48945   24999
River Rch & RM=LAKE CREEK,Reach-1         ,287115
    7119   10205   12869    5278   15939   48134   24441
River Rch & RM=LAKE CREEK,Reach-1         ,286460
    7119   10205   12869    5278   15939   48134   24441
River Rch & RM=LAKE CREEK,Reach-1         ,276500
    7056   10105   12734    5219   15760   47595   24132
River Rch & RM=LAKE CREEK,Reach-1         ,274498
    7412   10621   13391    5490   16580   50070   25406
River Rch & RM=LAKE CREEK,Reach-1         ,272139
    7605   10910   13767    5648   17058   51513   26177
River Rch & RM=LAKE CREEK,Reach-1         ,270440
    7700   11051   13949    5725   17288   52210   26547
River Rch & RM=LAKE CREEK,Reach-1         ,267720
   10561   15261   19359    7981   24102   72788   37330
River Rch & RM=LAKE CREEK,Reach-1         ,260966
   10655   15361   19453    8006   24178   73016   37314
River Rch & RM=LAKE CREEK,Reach-1         ,252000
   10655   15361   19453    8006   24178   73016   37314
River Rch & RM=LAKE CREEK,Reach-1         ,248000
   10746   15488   19612    8070   24372   73601   37601
River Rch & RM=LAKE CREEK,Reach-1         ,246759
   11166   16085   20360    8374   25290   76375   38980
River Rch & RM=LAKE CREEK,Reach-1         ,240000
   10992   15801   19973    8203   24772   74810   38067
River Rch & RM=LAKE CREEK,Reach-1         ,227021
   11486   16482   20811    8538   25784   77866   39521
River Rch & RM=LAKE CREEK,Reach-1         ,219793
   11415   16403   20730    8511   25703   77623   39473
River Rch & RM=LAKE CREEK,Reach-1         ,219000
   11620   16659   21022    8619   26028   78604   39842
River Rch & RM=LAKE CREEK,Reach-1         ,213829
   11619   16615   20931    8566   25868   78121   39452
River Rch & RM=LAKE CREEK,Reach-1         ,201940
   11769   16817   21175    8660   26154   78984   39840
River Rch & RM=LAKE CREEK,Reach-1         ,191914
   11843   16924   21310    8717   26323   79496   40103
River Rch & RM=LAKE CREEK,Reach-1         ,189735
   14194   20325   25635   10500   31711   95766   48434
River Rch & RM=LAKE CREEK,Reach-1         ,182928
   14196   20328   25638   10502   31714   95776   48438
River Rch & RM=LAKE CREEK,Reach-1         ,181530
   14328   20516   25877   10599   32010   96668   48890
River Rch & RM=LAKE CREEK,Reach-1         ,176927
   14288   20452   25789   10561   31894   96317   48686
River Rch & RM=LAKE CREEK,Reach-1         ,175805
   14287   20448   25781   10557   31880   96277   48656
River Rch & RM=LAKE CREEK,Reach-1         ,174899
   14194   20297   25576   10466   31606   95450   48178
River Rch & RM=LAKE CREEK,Reach-1         ,168971
   14126   20183   25419   10396   31394   94809   47800
River Rch & RM=LAKE CREEK,Reach-1         ,165824
   17558   25177   31797   13039   39377  118916   60250
River Rch & RM=LAKE CREEK,Reach-1         ,163000
   17776   25495   32202   13207   39884  120446   61040
River Rch & RM=LAKE CREEK,Reach-1         ,156351
   17825   25562   32284   13239   39982  120745   61181
River Rch & RM=LAKE CREEK,Reach-1         ,152177
   17724   25397   32059   13140   39682  119838   60655
River Rch & RM=LAKE CREEK,Reach-1         ,147837
   18405   26331   33209   13599   41070  124028   62644
River Rch & RM=LAKE CREEK,Reach-1         ,144904
   18922   27066   34132   13975   42204  127455   64352
River Rch & RM=LAKE CREEK,Reach-1         ,139839
   19128   27355   34493   14122   42646  128790   65010
River Rch & RM=LAKE CREEK,Reach-1         ,134000
   19125   27326   34434   14088   42546  128486   64770
River Rch & RM=LAKE CREEK,Reach-1         ,126188
   19125   27326   34434   14088   42546  128486   64770
River Rch & RM=LAKE CREEK,Reach-1         ,125000
   19146   27339   34437   14084   42532  128444   64693
River Rch & RM=LAKE CREEK,Reach-1         ,123847
   19193   27400   34509   14110   42613  128689   64794
River Rch & RM=LAKE CREEK,Reach-1         ,119032
   19193   27400   34509   14110   42613  128689   64794
River Rch & RM=LAKE CREEK,Reach-1         ,117000
   19257   27460   34559   14120   42640  128771   64730
River Rch & RM=LAKE CREEK,Reach-1         ,109357
   19257   27460   34559   14120   42640  128771   64730
River Rch & RM=LAKE CREEK,Reach-1         ,103711
   19101   27198   34194   13956   42146  127279   63845
River Rch & RM=LAKE CREEK,Reach-1         ,90132
   19248   27402   34446   14057   42452  128202   64291
River Rch & RM=LAKE CREEK,Reach-1         ,87000
   19549   27828   34981   14275   43109  130186   65278
River Rch & RM=LAKE CREEK,Reach-1         ,82773
   19480   27717   34831   14209   42911  129589   64937
River Rch & RM=LAKE CREEK,Reach-1         ,81000
   19585   27838   34959   14251   43037  129969   65031
River Rch & RM=LAKE CREEK,Reach-1         ,66728
   19585   27838   34959   14251   43037  129969   65031
River Rch & RM=LAKE CREEK,Reach-1         ,64363
   20343   28876   36236   14760   44575  134615   67232
River Rch & RM=LAKE CREEK,Reach-1         ,53000
   20343   28876   36236   14760   44575  134615   67232
River Rch & RM=LAKE CREEK,Reach-1         ,50000
   20416   28976   36358   14809   44723  135060   67444
River Rch & RM=LAKE CREEK,Reach-1         ,45042
   20415   28972   36350   14805   44710  135023   67417
River Rch & RM=LAKE CREEK,Reach-1         ,44395
   20460   29032   36424   14834   44797  135283   67535
River Rch & RM=LAKE CREEK,Reach-1         ,40899
   20460   29032   36424   14834   44797  135283   67535
River Rch & RM=LAKE CREEK,Reach-1         ,40632
   21439   30429   38186   15555   46975  141863   70846
River Rch & RM=LAKE CREEK,Reach-1         ,39384
   21439   30429   38186   15555   46975  141863   70846
River Rch & RM=LAKE CREEK,Reach-1         ,31779
   21462   30459   38222   15569   47016  141987   70899
River Rch & RM=LAKE CREEK,Reach-1         ,29940
   21741   30846   38699   15760   47594  143732   71739
River Rch & RM=LAKE CREEK,Reach-1         ,25000
   21741   30846   38699   15760   47594  143732   71739
River Rch & RM=LAKE CREEK,Reach-1         ,22191
   21750   30848   38693   15753   47575  143674   71674
River Rch & RM=LAKE CREEK,Reach-1         ,17000
   21670   30719   38518   15676   47342  142971   71272
River Rch & RM=LAKE CREEK,Reach-1         ,11221
   21550   30522   38247   15557   46980  141877   70636
River Rch & RM=LAKE CREEK,Reach-1         ,3866
   21529   30478   38180   15524   46883  141583   70445
Boundary for River Rch & Prof#=LAKE CREEK,Reach-1         , 1
Up Type= 0
Dn Type= 3
Dn Slope=0.0005
Boundary for River Rch & Prof#=LAKE CREEK,Reach-1         , 2
Up Type= 0
Dn Type= 3
Dn Slope=0.0005
Boundary for River Rch & Prof#=LAKE CREEK,Reach-1         , 3
Up Type= 0
Dn Type= 3
Dn Slope=0.0005
Boundary for River Rch & Prof#=LAKE CREEK,Reach-1         , 4
Up Type= 0
Dn Type= 3
Dn Slope=0.0005
Boundary for River Rch & Prof#=LAKE CREEK,Reach-1         , 5
Up Type= 0
Dn Type= 3
Dn Slope=0.0005
Boundary for River Rch & Prof#=LAKE CREEK,Reach-1         , 6
Up Type= 0
Dn Type= 3
Dn Slope=0.0005
Boundary for River Rch & Prof#=LAKE CREEK,Reach-1         , 7
Up Type= 0
Dn Type= 3
Dn Slope=0.0005
DSS Import GetInterval= 0
DSS Import GetPeak= 0
DSS Import FillOption= 0

--- LAKE CREEK.g01 (geometry) ---

Geom Title=Existing Conditions
Program Version=4.10

River Reach=LAKE CREEK      ,Reach-1
Reach XY= 30
      3690584.38     10222801.59      3692215.46      10217129.7
      3698706.25     10217008.99       3702500.8     10208246.17
      3707184.65     10203539.24      3706930.37     10197445.15
      3714021.03     10185262.72      3718902.56     10181030.29
      3719371.12     10173985.28       3728011.5       10167657.
      3728229.74     10157608.32      3732831.05     10148505.59
      3734930.01     10148349.99      3735379.17     10128771.13
       3737374.7     10123280.59      3743325.91      10118726.8
      3742361.33     10112755.24      3746623.82     10109630.83
      3749161.15     10103294.08      3754711.27     10102094.21
      3757258.71     10095706.23      3762888.15     10093987.06
      3767166.59     10085878.11      3784671.28     10082647.16
      3788231.57      10085055.7      3791868.32     10084308.87
        3798817.     10089266.23      3808043.71     10090049.96
      3816081.63     10096535.64      3824049.75     10094306.84

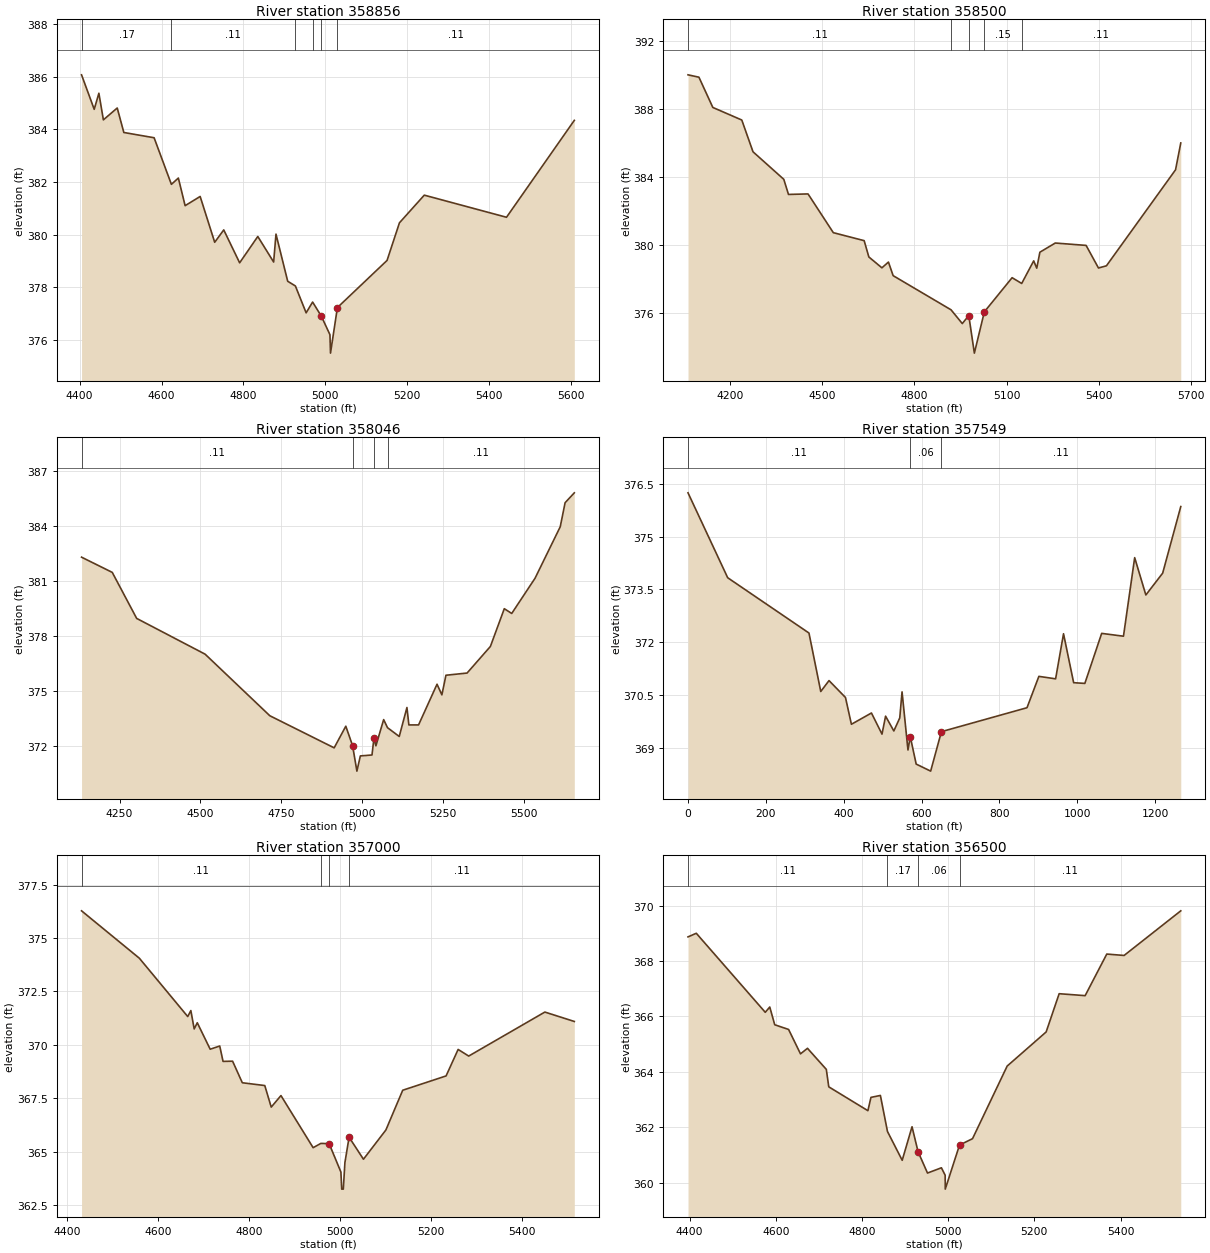
Type RM Length L Ch R = 1 ,358856  ,356,356,356
BEGIN DESCRIPTION:
LAKE CREEK 696.0
END DESCRIPTION:
XS GIS Cut Line= 3
      3691165.31     10222932.96      3690628.89     10222656.94
      3690035.18     10222573.61
#Sta/Elev= 30
  4404.7  386.07  4435.6  384.76    4447  385.37    4458  384.36  4491.8  384.81
  4507.9  383.88  4581.8  383.68    4624  381.91    4641  382.15  4657.5   381.1
  4694.2  381.45  4729.7  379.71  4751.8  380.18  4790.6  378.93  4834.9  379.93
  4873.6  378.96  4879.3  380.02  4907.9  378.23  4926.7  378.05  4952.9  377.03
  4968.7  377.44  4990.1   376.9    5011   376.2  5012.4   375.5  5029.2  377.23
  5150.4  379.02  5180.7  380.45  5241.3   381.5    5442  380.66  5607.5  384.34
#Mann= 6 ,-1 , 0
  4404.7     .17       0    4624     .11       0  4926.7     .15       0
  4968.7     .11       0  4990.1     .06       0  5029.2     .11       0
Bank Sta=4990.1,5029.2
XS Rating Curve= 0 ,0
Exp/Cntr=0.3,0.1

Type RM Length L Ch R = 1 ,358500  ,454,454,454
BEGIN DESCRIPTION:
LAKE CREEK 695.0
END DESCRIPTION:
XS GIS Cut Line= 3
      3691467.88     10222811.09      3690675.06     10222312.43
      3690010.95     10222365.12
#Sta/Elev= 30
  4063.4  390.02  4098.9  389.88  4144.1   388.1  4238.3  387.36  4274.8  385.49
  4374.9  383.87  4390.2  382.98  4453.8  383.01    4536  380.73  4636.3  380.26
  4651.6   379.3  4694.1  378.66  4715.3     379  4730.6   378.2  4918.9  376.19
  4955.5  375.38  4976.7  375.85  4994.8  373.64  5027.3  376.07  5117.6  378.08
  5148.8  377.74  5187.8  379.07  5197.8  378.64  5207.9  379.58    5258  380.12
  5358.3  379.98  5398.5  378.65  5424.4  378.78  5649.2  384.43  5666.2  386.01
#Mann= 5 ,-1 , 0
  4063.4     .11       0  4918.9     .15       0  4976.7     .06       0
  5027.3     .15       0  5148.8     .11       0
Bank Sta=4976.7,5027.3
XS Rating Curve= 0 ,0
Exp/Cntr=0.3,0.1

Type RM Length L Ch R = 1 ,358046  ,497,497,497
BEGIN DESCRIPTION:
LAKE CREEK 694.0
END DESCRIPTION:
XS GIS Cut Line= 3
      3691267.84     10222211.06      3690597.64     10221839.23
      3689967.89     10222261.04
#Sta/Elev= 30
  4132.3   382.3  4227.3  381.47  4302.8  378.96  4514.5  377.01  4714.8  373.65
  4913.8   371.9  4949.8  373.08  4970.8  372.02  4984.1  370.63  4994.8  371.46
  5030.8  371.51  5036.9  372.44  5042.9  372.01  5066.9  373.44  5078.8     373
  5115.1  372.52  5138.9   374.1  5144.9  373.15  5174.9  373.15    5232  375.37
    5247  374.79  5259.6  375.86    5325  375.98  5397.1  377.43  5440.1  379.49
  5463.1  379.23  5535.2  381.15  5613.2  383.96  5628.2  385.27  5656.7  385.81
#Mann= 4 ,-1 , 0
  4132.3     .11       0  4970.8     .06       0  5036.9     .15       0
  5078.8     .11       0
Bank Sta=4970.8,5036.9
XS Rating Curve= 0 ,0
Exp/Cntr=0.3,0.1

Type RM Length L Ch R = 1 ,357549  ,549,549,549
BEGIN DESCRIPTION:
LAKE CREEK 693.0
END DESCRIPTION:
XS GIS Cut Line= 4
      3690957.01     10221912.15      3690462.22     10221594.44
      3690134.84     10221403.87      3689946.66     10221637.17
#Sta/Elev= 30
       0  376.24   101.9  373.83   310.7  372.26     341   370.6   362.2  370.91
   404.5  370.43   419.7  369.67   471.2  369.99   498.3  369.39   507.5   369.9
   528.7  369.48   543.9  369.85   549.8  370.59     565  368.94   570.9  369.32
   586.1  368.54   623.3  368.34   650.9  369.46   870.8  370.14   901.3  371.03
   944.3  370.96   964.6  372.24   990.6  370.85  1019.4  370.83  1062.6  372.25
  1118.6  372.17  1147.4   374.4  1176.1  373.34  1219.3  373.96  1265.8  375.85
#Mann= 3 , 0 , 0
       0     .11       0   570.9     .06       0   650.9     .11       0
Bank Sta=570.9,650.9
XS Rating Curve= 0 ,0
Exp/Cntr=0.3,0.1

Type RM Length L Ch R = 1 ,357000  ,500,500,500
BEGIN DESCRIPTION:
LAKE CREEK 692.0
END DESCRIPTION:
XS GIS Cut Line= 3
      3691217.85     10221611.07      3690827.08     10221198.29
      3690337.21     10221037.14
#Sta/Elev= 30
  4431.6  376.27  4558.8  374.05  4665.2  371.32  4672.1   371.6  4679.4  370.74
  4686.2  371.03  4714.6  369.79  4735.6  369.94  4742.9  369.22  4763.9  369.23
  4785.3  368.22  4834.7  368.09  4848.9  367.08  4870.3  367.62  4941.1  365.18
    4958  365.38  4976.3  365.37  5002.2  364.04    5004  363.24  5007.5  363.24
    5011  364.48  5020.2  365.67  5051.8  364.64  5101.2  366.01  5138.2  367.87
  5233.6  368.54  5260.1  369.78  5283.4  369.47  5450.9  371.53  5515.7  371.09
#Mann= 4 ,-1 , 0
  4431.6     .11       0    4958     .17       0  4976.3     .06       0
  5020.2     .11       0
Bank Sta=4976.3,5020.2
XS Rating Curve= 0 ,0
Exp/Cntr=0.3,0.1

Type RM Length L Ch R = 1 ,356500  ,530,530,530
BEGIN DESCRIPTION:
LAKE CREEK 691.0
END DESCRIPTION:
XS GIS Cut Line= 3
      3691524.69     10221089.21      3690994.16     10220801.34
      3690457.02     10220854.85
#Sta/Elev= 30
  4396.4  368.87  4415.6     369  4575.6  366.15  4586.1  366.34  4597.6   365.7
  4629.8  365.53  4657.4  364.65  4673.6  364.85  4717.3  364.09    4723  363.46
  4813.8   362.6  4820.9  363.08  4842.8  363.15  4859.2  361.85  4893.4  360.81
  4916.2  362.02  4930.2  361.12  4952.1  360.35  4984.4  360.54  4993.1  360.27
  4993.3  359.77  5026.4  361.36  5056.6  361.59    5137  364.21  5227.4  365.44
  5257.6  366.82  5317.9  366.75  5368.1  368.25  5408.3   368.2  5539.8  369.81
#Mann= 4 ,-1 , 0
  4396.4     .11       0  4859.2     .17       0  4930.2     .06       0
  5026.4     .11       0
Bank Sta=4930.2,5026.4
XS Rating Curve= 0 ,0
Exp/Cntr=0.3,0.1

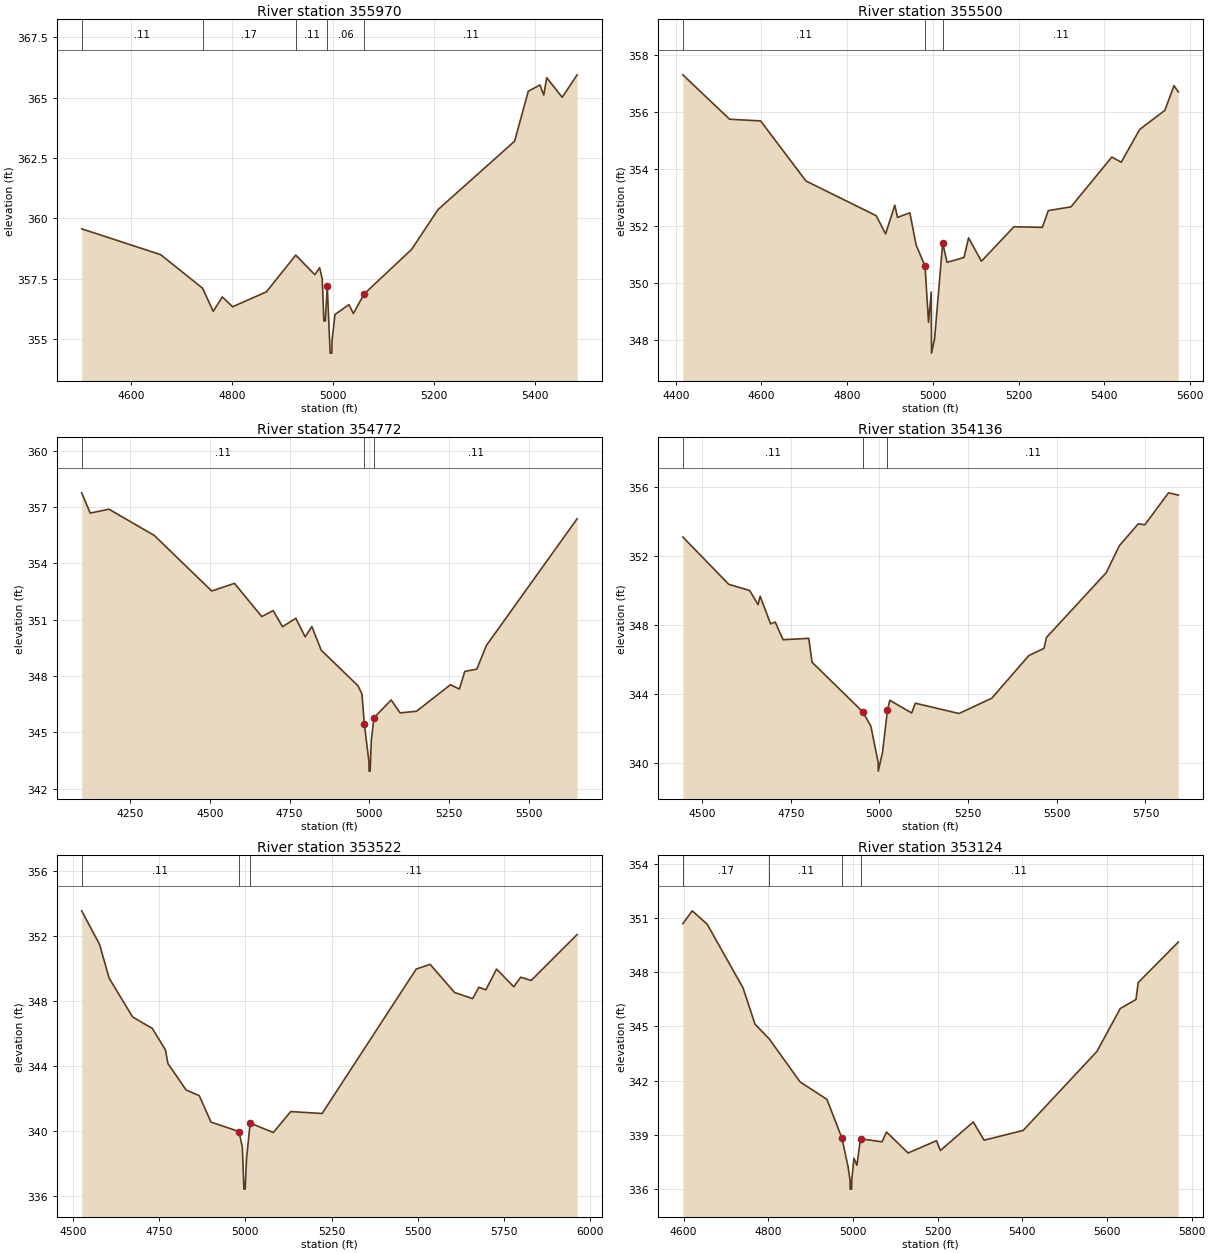
Type RM Length L Ch R = 1 ,355970  ,470,470,470
BEGIN DESCRIPTION:
LAKE CREEK 690.0
END DESCRIPTION:
XS GIS Cut Line= 3
      3691441.44      10220443.4      3690967.43     10220354.85
      3690545.59     10220620.46
#Sta/Elev= 30
  4502.7  359.56  4658.9  358.49    4742   357.1  4763.1  356.14    4781  356.74
  4801.4  356.33  4868.4  356.95  4926.4  358.47  4964.1  357.66  4973.7  357.95
  4978.8  357.49  4982.1  355.74  4984.9  355.74  4988.8  357.19  4994.5  354.41
    4998  354.41  4998.2  354.91    5004  356.01  5031.7  356.42  5040.5  356.05
  5061.7  356.86  5155.9  358.71  5207.7  360.35  5359.6  363.19  5386.7  365.26
  5409.8  365.52  5417.3   365.1  5423.2  365.82  5453.8  365.01  5483.4  365.94
#Mann= 5 ,-1 , 0
  4502.7     .11       0    4742     .17       0  4926.4     .11       0
  4988.8     .06       0  5061.7     .11       0
Bank Sta=4988.8,5061.7
XS Rating Curve= 0 ,0
Exp/Cntr=0.3,0.1

Type RM Length L Ch R = 1 ,355500  ,728,728,728
BEGIN DESCRIPTION:
LAKE CREEK 689.0
END DESCRIPTION:
XS GIS Cut Line= 4
      3691441.38     10220261.09      3690980.76     10219903.06
      3690811.04     10219887.65      3690608.05     10220235.07
#Sta/Elev= 30
  4416.6  357.31  4525.6  355.75    4598  355.69  4703.9  353.58  4867.7  352.36
  4889.7  351.72  4911.2  352.73  4917.5   352.3  4946.4  352.46  4960.9  351.33
  4981.7  350.59  4989.9  348.61  4996.2  349.68  4996.9  347.53    5004  348.03
    5023  351.41    5033  350.72  5072.7  350.89  5083.3  351.58  5113.4  350.76
  5189.2  351.97  5255.5  351.95  5269.4  352.54  5322.3  352.67  5417.6  354.42
  5439.7  354.24  5482.6  355.39  5541.3  356.06  5562.8  356.93  5572.8  356.71
#Mann= 3 , 0 , 0
  4416.6     .11       0  4981.7     .06       0    5023     .11       0
Bank Sta=4981.7,5023
XS Rating Curve= 0 ,0
Exp/Cntr=0.3,0.1

Type RM Length L Ch R = 1 ,354772  ,636,636,636
BEGIN DESCRIPTION:
LAKE CREEK 688.0
END DESCRIPTION:
XS GIS Cut Line= 3
      3691524.74      10220302.8      3691003.89     10219584.02
      3690404.98     10219292.38
#Sta/Elev= 30
  4098.1  357.75  4124.9  356.67  4183.5  356.88  4325.8  355.48    4506  352.52
  4577.1  352.93  4662.9  351.16  4698.5  351.48  4727.9  350.62  4769.6  351.07
    4799  350.08  4819.9  350.63  4849.3  349.37  4964.5  347.48    4977  347.04
  4984.5  345.45    4999  343.43  4999.2  342.93  5002.7  342.93  5006.5  344.58
  5014.7  345.77  5068.6  346.72  5096.7  346.03  5148.2  346.12  5254.5  347.53
  5282.6   347.3  5299.6  348.24  5337.3  348.36  5367.2  349.62  5651.9  356.37
#Mann= 3 , 0 , 0
  4098.1     .11       0  4984.5     .06       0  5014.7     .11       0
Bank Sta=4984.5,5014.7
XS Rating Curve= 0 ,0
Exp/Cntr=0.3,0.1

Type RM Length L Ch R = 1 ,354136  ,614,614,614
BEGIN DESCRIPTION:
LAKE CREEK 686.0
END DESCRIPTION:
XS GIS Cut Line= 3
      3691717.86     10219461.08      3691253.89     10219172.56
      3690425.78     10218979.86
#Sta/Elev= 30
    4446  353.12  4575.5  350.37  4634.4  350.01  4657.9  349.19  4663.8  349.68
  4693.3  348.07  4706.3  348.18  4728.6  347.15  4800.8  347.23  4810.2  345.84
  4953.1  342.96  4975.9  342.13  4996.6  340.01  4996.8  339.51  5008.8   340.6
  5022.6  343.04  5029.4  343.63    5091  342.89  5101.2  343.46  5224.4  342.86
  5316.8  343.75  5421.4  346.23    5464  346.65  5470.9  347.28  5639.5  351.05
  5676.2  352.61  5729.8  353.89  5748.1  353.83    5815  355.69  5842.6  355.56
#Mann= 3 ,-1 , 0
    4446     .11       0  4953.1     .06       0  5022.6     .11       0
Bank Sta=4953.1,5022.6
XS Rating Curve= 0 ,0
Exp/Cntr=0.3,0.1

Type RM Length L Ch R = 1 ,353522  ,398,398,398
BEGIN DESCRIPTION:
LAKE CREEK 685.0
END DESCRIPTION:
XS GIS Cut Line= 3
      3691917.88     10219011.09      3691436.18     10218750.69
      3690555.94      10218880.9
#Sta/Elev= 30
    4525  353.57  4576.9   351.5  4604.6  349.42  4672.8  347.03  4730.1  346.32
  4768.2  344.99  4775.1  344.16  4828.1  342.53  4866.1  342.18  4900.2  340.55
  4981.3  339.97  4991.1  339.02  4995.7  336.42  4999.2  336.42  5003.2  338.28
  5013.7  340.49    5081  339.91  5131.5   341.2  5222.5  341.08  5495.5  349.98
  5535.9  350.27  5606.7  348.54  5659.2  348.16  5677.4  348.86  5697.6   348.7
  5728.7  349.98  5778.5  348.89  5798.7  349.48  5829.1  349.28  5962.4  352.11
#Mann= 3 , 0 , 0
    4525     .11       0  4981.3     .06       0  5013.7     .11       0
Bank Sta=4981.3,5013.7
XS Rating Curve= 0 ,0
Exp/Cntr=0.3,0.1

Type RM Length L Ch R = 1 ,353124  ,624,624,624
BEGIN DESCRIPTION:
LAKE CREEK 684.0
END DESCRIPTION:
XS GIS Cut Line= 3
      3692009.09      10218761.1      3691712.22     10218474.65
      3690998.72     10218729.84
#Sta/Elev= 30
  4598.3  350.69  4620.4   351.4  4655.7  350.66  4740.5  347.13  4768.8  345.12
  4802.7   344.3  4875.1  341.93  4938.6  340.96  4974.1  338.81  4988.3  337.26
  4993.2  336.49  4993.5  335.99    4997  335.99  4997.2  336.49  5002.4   337.7
  5009.4  337.31  5017.9  338.78  5068.6  338.61  5079.5  339.15  5130.4  337.99
  5197.3  338.67  5206.6  338.13  5284.3  339.71  5309.8   338.7  5402.1  339.24
  5576.2  343.61  5631.5  345.99  5668.5  346.49  5673.9  347.43  5768.6  349.67
#Mann= 4 ,-1 , 0
  4598.3     .17       0  4802.7     .11       0  4974.1     .06       0
  5017.9     .11       0
Bank Sta=4974.1,5017.9
XS Rating Curve= 0 ,0
Exp/Cntr=0.3,0.1

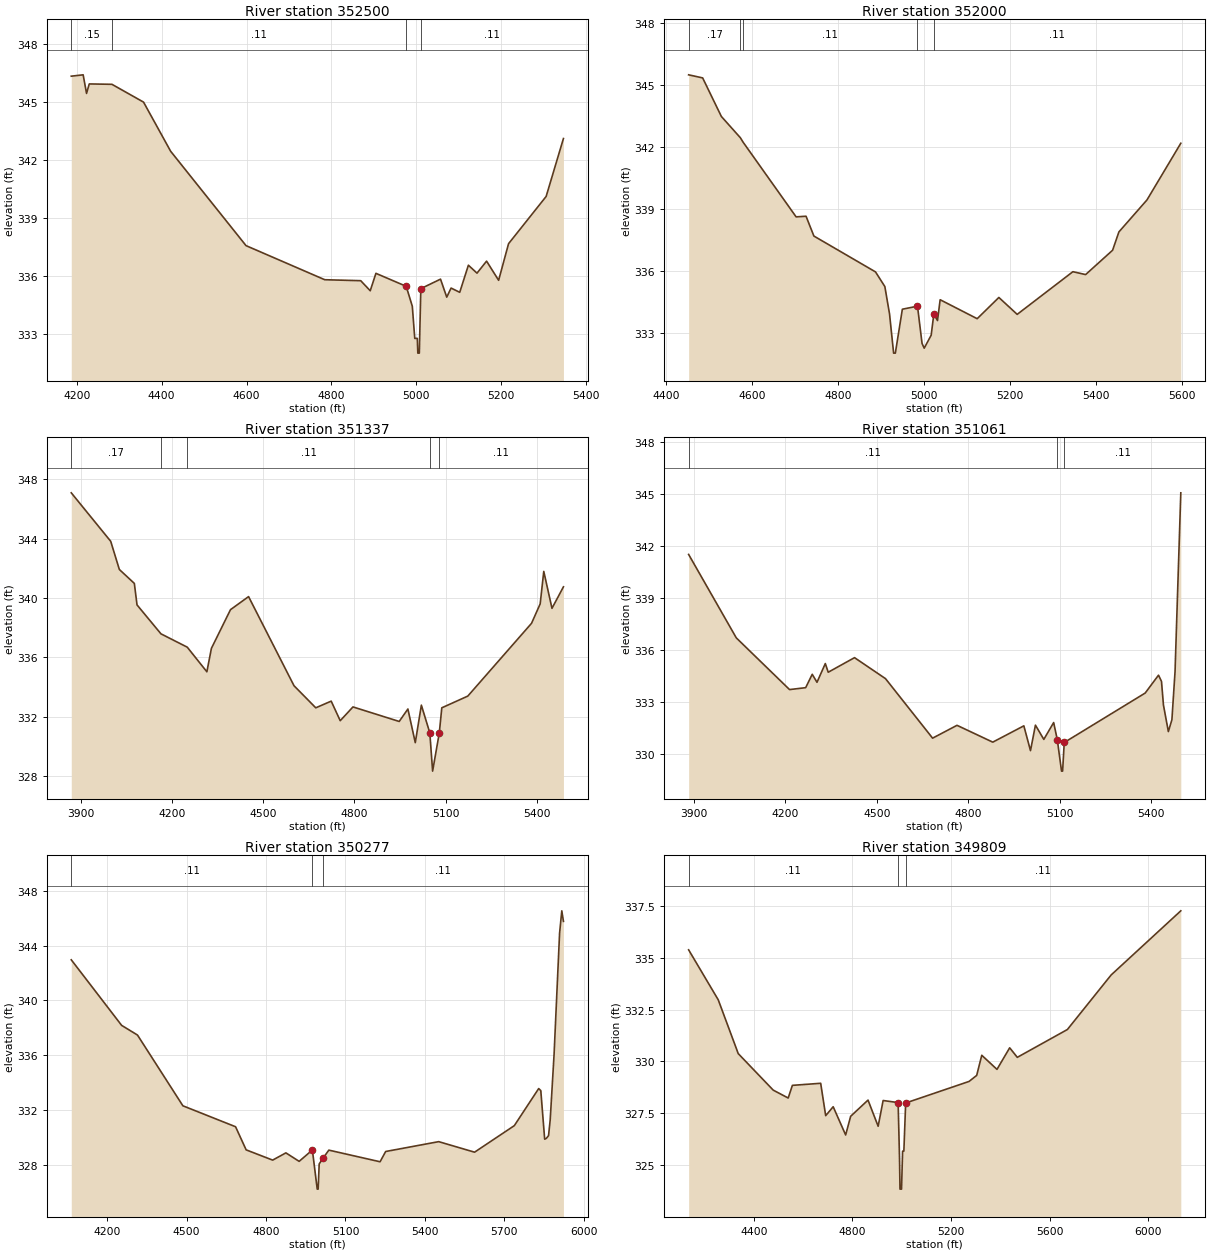
Type RM Length L Ch R = 1 ,352500  ,500,500,500
BEGIN DESCRIPTION:
LAKE CREEK 683.0
END DESCRIPTION:
XS GIS Cut Line= 3
      3692117.83     10218561.05      3691608.67      10217927.1
      3691267.81     10217861.06
#Sta/Elev= 30
  4186.9  346.32  4214.9  346.39  4222.9  345.43  4229.3  345.92  4282.8   345.9
  4357.3  344.98  4421.3  342.44  4598.9  337.57  4784.5  335.81  4869.3  335.76
  4891.7  335.24  4905.1  336.14  4976.5  335.47  4990.9  334.44  4996.7  332.78
  5002.7  332.78  5003.9  332.02  5007.4  332.02    5011  335.35  5057.4  335.84
  5072.1  334.91  5082.3  335.38  5102.7  335.16  5123.1  336.56  5143.4  336.15
    5166  336.77  5194.4  335.78  5217.8  337.67  5306.4  340.11  5347.2   343.1
#Mann= 4 ,-1 , 0
  4186.9     .15       0  4282.8     .11       0  4976.5     .06       0
    5011     .11       0
Bank Sta=4976.5,5011
XS Rating Curve= 0 ,0
Exp/Cntr=0.3,0.1

Type RM Length L Ch R = 1 ,352000  ,663,663,663
BEGIN DESCRIPTION:
LAKE CREEK 682.0
END DESCRIPTION:
XS GIS Cut Line= 3
      3692217.86      10218311.1      3692004.04     10217806.86
      3691517.86     10217461.08
#Sta/Elev= 30
  4452.3   345.5  4484.9  345.35  4528.4  343.48  4572.5  342.45  4578.7  342.24
  4702.2  338.61  4725.3  338.64  4743.5  337.68  4886.8  335.94  4908.5  335.23
  4919.4   333.9  4928.9     332  4932.9     332  4949.2  334.13  4984.4334.2771
    4995  332.47    5000  332.24  5016.2  332.87 5022.35333.8882  5030.9  333.58
  5037.1  334.59  5123.2  333.67  5173.6   334.7  5216.2  333.88  5345.7  335.95
  5375.3  335.81    5438  336.99  5452.7  337.88  5517.9  339.43  5596.6  342.18
#Mann= 5 ,-1 , 0
  4452.3     .17       0  4572.5     .15       0  4578.7     .11       0
  4984.4     .06       0 5022.35     .11       0
Bank Sta=4984.4,5022.35
XS Rating Curve= 0 ,0
Exp/Cntr=0.3,0.1

Type RM Length L Ch R = 1 ,351337  ,276,276,276
BEGIN DESCRIPTION:
LAKE CREEK 681.0
END DESCRIPTION:
XS GIS Cut Line= 3
      3692717.83     10218261.04       3692073.8     10217331.13
      3691605.69      10217195.9
#Sta/Elev= 30
    3869  347.09  3998.7  343.82  4027.1  341.92  4076.4  340.98  4085.2  339.53
  4163.9  337.58  4250.4  336.68  4314.9  335.02  4329.8   336.6  4392.6  339.21
    4452  340.09  4601.4  334.08    4673  332.59  4723.7  333.04  4753.4  331.72
  4795.3  332.65  4947.3  331.67  4975.9  332.51  5000.2  330.24  5020.2  332.77
    5048   330.9  5057.2  328.32  5079.2   330.9  5087.4  332.59  5172.9  333.38
  5382.5  338.29  5410.9   339.6  5422.7  341.79  5449.7   339.3  5487.4  340.75
#Mann= 5 ,-1 , 0
    3869     .17       0  4163.9     .15       0  4250.4     .11       0
    5048     .06       0  5079.2     .11       0
Bank Sta=5048,5079.2
XS Rating Curve= 0 ,0
Exp/Cntr=0.3,0.1

Type RM Length L Ch R = 1 ,351061  ,784,784,784
BEGIN DESCRIPTION:
LAKE CREEK 680.0
END DESCRIPTION:
XS GIS Cut Line= 3
      3692797.74     10218075.89      3692250.88     10217143.63
      3691995.98     10216675.44
#Sta/Elev= 30
  3882.9   341.5  4039.2  336.69  4213.8  333.71  4266.7  333.82  4288.2  334.59
  4303.8  334.13  4331.1  335.21  4340.6  334.71  4426.9  335.55  4528.5  334.34
  4682.9  330.91    4763  331.65  4880.2  330.68  4982.1  331.62  5003.9  330.19
  5020.1  331.66  5047.6  330.84  5079.9  331.81  5091.9  330.81  5105.7  329.01
  5109.2  329.01  5114.6  330.66    5380  333.51  5423.7  334.54  5433.5  334.18
  5439.9  332.82    5456  331.29  5467.6  331.97  5477.9  334.74  5496.8  345.05
#Mann= 3 , 0 , 0
  3882.9     .11       0  5091.9     .06       0  5114.6     .11       0
Bank Sta=5091.9,5114.6
XS Rating Curve= 0 ,0
Exp/Cntr=0.3,0.1

Type RM Length L Ch R = 1 ,350277  ,468,468,468
BEGIN DESCRIPTION:
LAKE CREEK 679.0
END DESCRIPTION:
XS GIS Cut Line= 3
      3692867.85     10218111.03      3692834.21     10217174.88
      3692282.78     10216436.16
#Sta/Elev= 30
  4064.5  342.97  4254.6  338.18  4314.6  337.47    4486   332.3  4684.9  330.77
  4724.9  329.08    4825  328.33    4875  328.86    4925  328.24    4975  329.07
  4993.3  326.21  4996.8  326.21  5000.7  328.05  5016.3   328.5  5037.1  329.06
  5230.6  328.21  5251.8  328.96    5452  329.68  5587.5  328.91  5737.6  330.85
  5829.6  333.56  5837.6  333.41  5852.2  329.86  5858.5  329.92  5866.8  330.12
  5873.1  331.27  5887.7  336.05  5908.5  344.91  5916.9  346.55  5923.1  345.78
#Mann= 3 , 0 , 0
  4064.5     .11       0    4975     .06       0  5016.3     .11       0
Bank Sta=4975,5016.3
XS Rating Curve= 0 ,0
Exp/Cntr=0.3,0.1

Type RM Length L Ch R = 1 ,349809  ,309,309,309
BEGIN DESCRIPTION:
LAKE CREEK 678.0
END DESCRIPTION:
XS GIS Cut Line= 3
      3693094.63     10217919.66      3693235.26     10217060.29
      3693500.87     10215966.58
#Sta/Elev= 30
  4135.8  335.38    4256  332.97    4337  330.38  4478.9  328.62  4539.7  328.24
  4556.6  328.85  4671.4  328.95  4691.7  327.39  4722.1  327.82  4772.7  326.46
    4793  327.36  4863.4  328.14  4904.5  326.88  4924.7  328.12  4985.5  328.02
  4991.2  325.34  4993.1  323.85  4999.3  323.85  5003.7  325.68  5008.8  325.68
  5016.1     328  5273.4  329.04  5304.2  329.33  5324.8   330.3  5386.5  329.62
    5438  330.66  5468.9   330.2    5672  331.54  5849.6  334.17  6132.1  337.26
#Mann= 3 , 0 , 0
  4135.8     .11       0  4985.5     .06       0  5016.1     .11       0
Bank Sta=4985.5,5016.1
XS Rating Curve= 0 ,0
Exp/Cntr=0.3,0.1