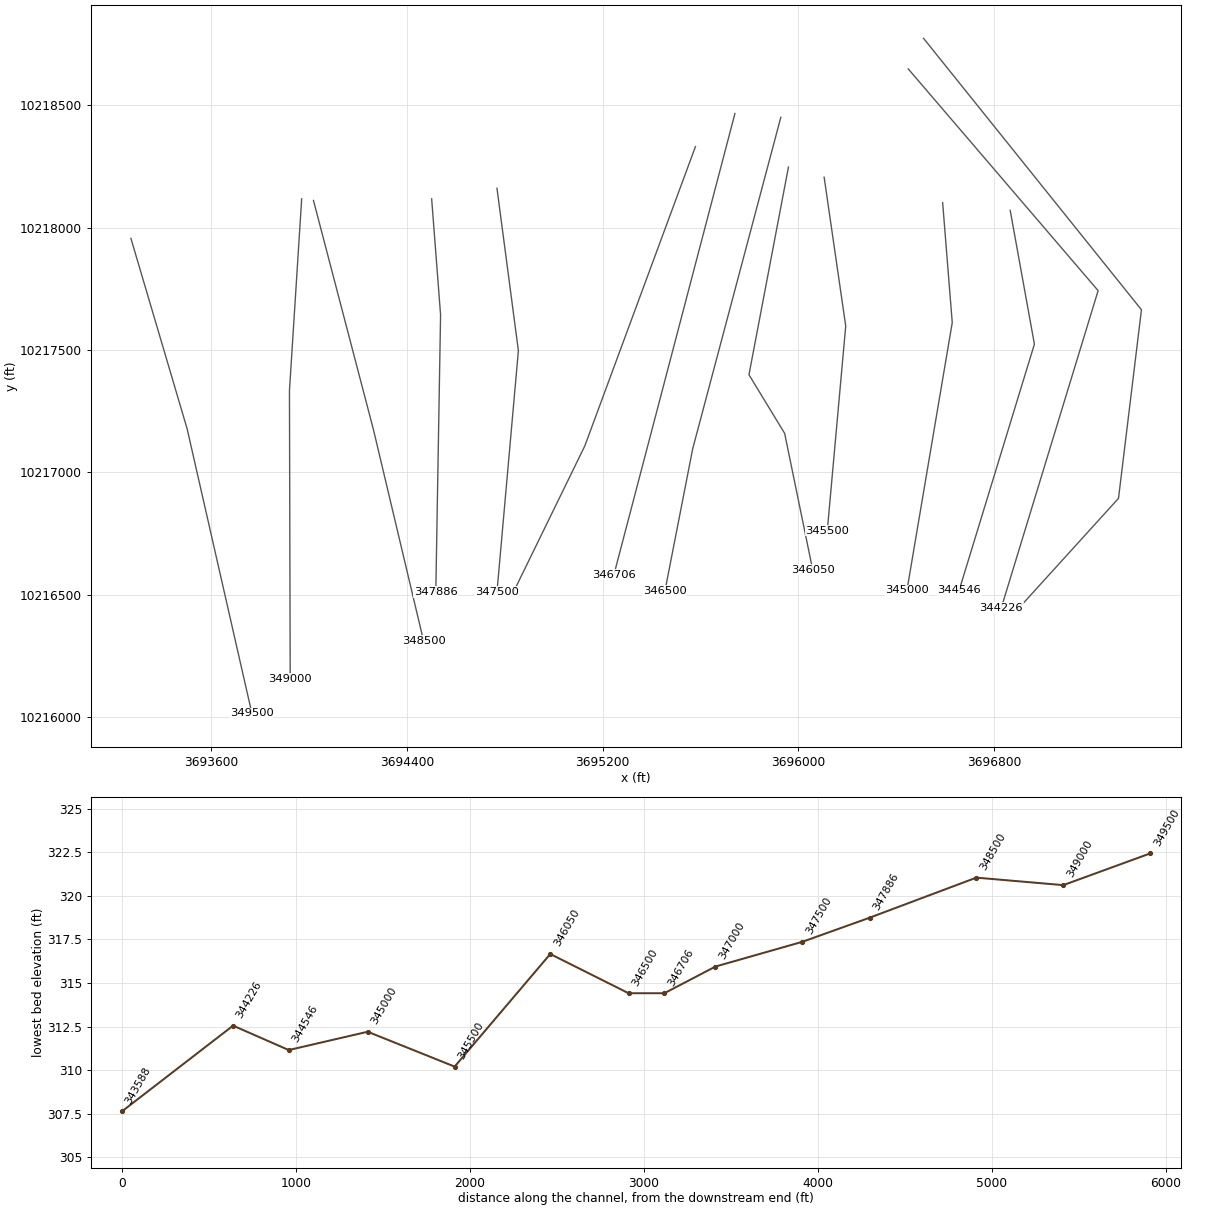
HEC-RAS study LAKE CREEK.prj: LAKE CREEK Base Level Engineering

--- LAKE CREEK.g01 (geometry) --- (continued)

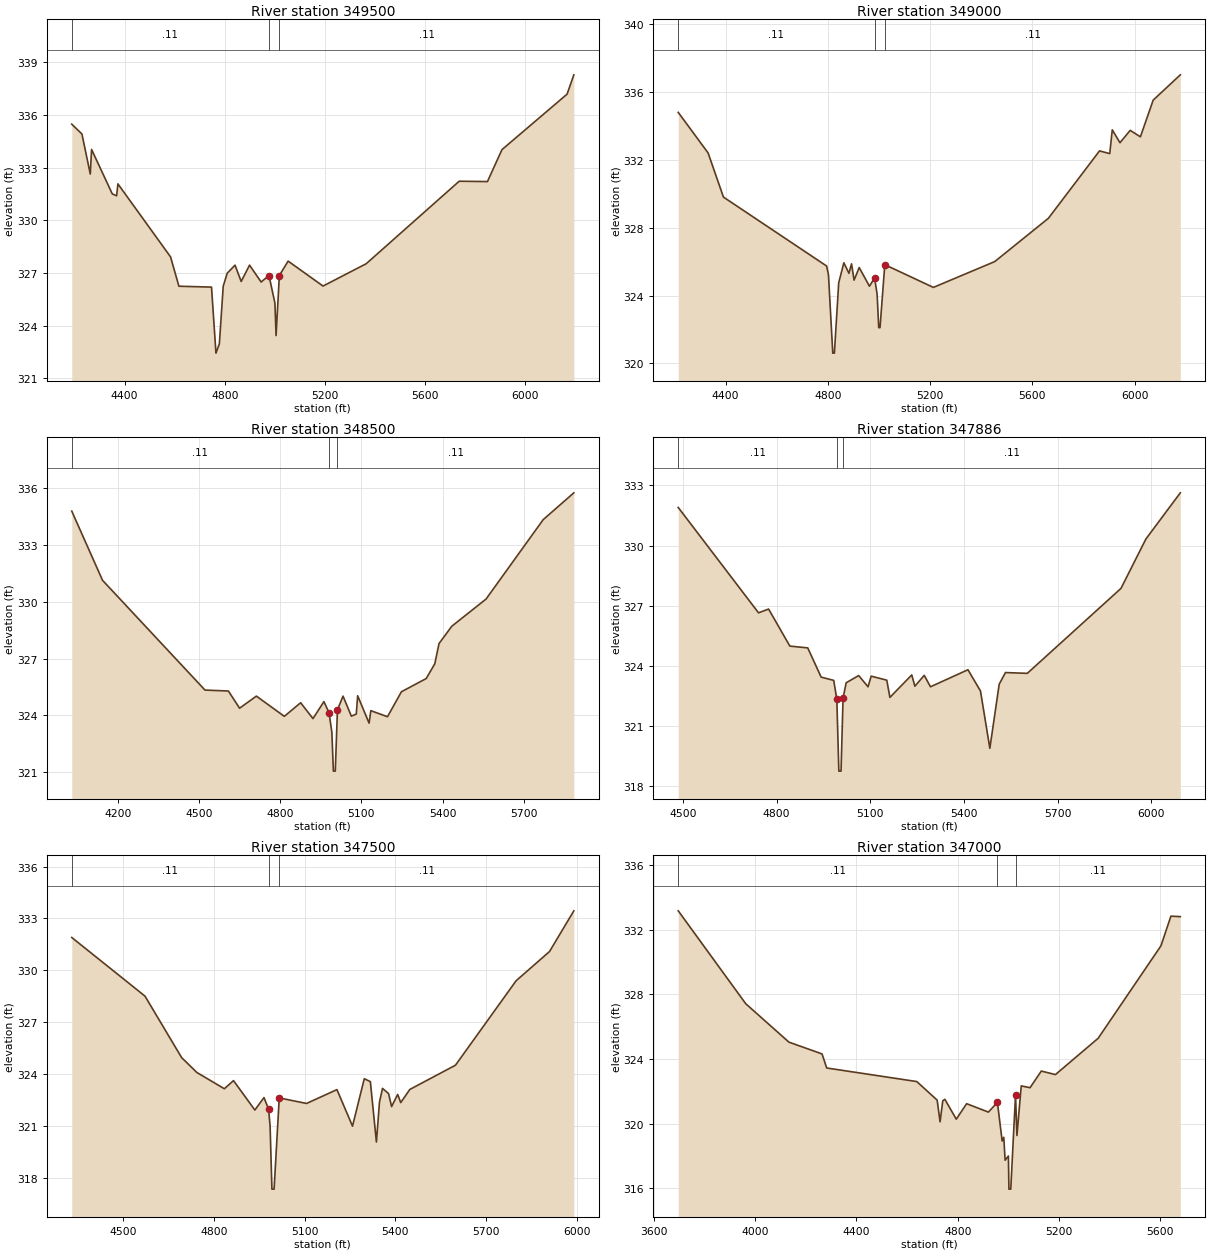
Type RM Length L Ch R = 1 ,349500  ,500,500,500
BEGIN DESCRIPTION:
LAKE CREEK 677.0
END DESCRIPTION:
XS GIS Cut Line= 3
      3693271.71     10217956.13      3693501.34     10217178.32
      3693766.19     10216014.79
#Sta/Elev= 30
    4189  335.47  4229.6  334.91  4262.9  332.63  4268.1  334.03  4350.7   331.5
    4368  331.39  4373.2  332.07  4583.4  327.91  4616.7  326.24  4746.9  326.19
  4764.6  322.43  4778.2  322.96  4793.6  326.24  4809.5  326.98  4840.7  327.44
  4865.4  326.51  4898.7  327.44    4945  326.48  4976.3  326.85    5000  325.28
  5004.6  323.43  5017.7  326.85  5052.7  327.67  5192.1  326.25  5364.3  327.52
  5735.6  332.22  5848.4   332.2  5906.4  334.02  6166.3  337.18  6193.3  338.28
#Mann= 3 , 0 , 0
    4189     .11       0  4976.3     .06       0  5017.7     .11       0
Bank Sta=4976.3,5017.7
XS Rating Curve= 0 ,0
Exp/Cntr=0.3,0.1

Type RM Length L Ch R = 1 ,349000  ,500,500,500
BEGIN DESCRIPTION:
LAKE CREEK 676.0
END DESCRIPTION:
XS GIS Cut Line= 3
      3693969.63     10218117.62      3693919.67     10217333.61
      3693922.75     10216155.01
#Sta/Elev= 30
  4214.4  334.79  4331.2   332.4  4391.3   329.8  4794.9  325.74  4802.1  325.23
    4819  320.61  4825.3  320.61  4842.2  324.75  4862.3  325.93  4882.3  325.31
  4892.3  325.87  4902.3  324.91  4922.4  325.65  4962.5  324.55  4982.5  325.04
  4992.5  324.08  4998.8  322.11  5003.8  322.11  5022.5  325.82  5212.5  324.48
  5452.5     326  5662.5  328.55  5862.5  332.52  5902.5  332.36  5912.5  333.76
  5942.5     333  5982.5  333.73  6022.5  333.35  6072.5  335.51  6178.6     337
#Mann= 3 , 0 , 0
  4214.4     .11       0  4982.5     .06       0  5022.5     .11       0
Bank Sta=4982.5,5022.5
XS Rating Curve= 0 ,0
Exp/Cntr=0.3,0.1

Type RM Length L Ch R = 1 ,348500  ,614,614,614
BEGIN DESCRIPTION:
LAKE CREEK 675.0
END DESCRIPTION:
XS GIS Cut Line= 3
      3694017.84      10218111.1      3694263.49     10217172.31
      3694467.86     10216311.02
#Sta/Elev= 30
  4029.6   334.8  4143.3  331.14    4522  325.33  4608.5  325.28  4649.8  324.37
  4711.9  325.01  4815.2  323.94  4875.5  324.66  4921.1  323.82  4961.5  324.72
  4980.6  324.12  4990.9  323.09  4996.5  321.04  5003.5  321.04  5011.5  324.28
  5032.1  325.01  5062.9  323.95  5081.1  324.06  5086.2  325.03  5128.5  323.58
  5134.9  324.24  5196.5  323.92  5247.9  325.24  5339.5  325.94  5371.3  326.72
  5386.9  327.79  5434.2  328.71  5560.9  330.15  5771.9  334.35  5885.2  335.77
#Mann= 3 , 0 , 0
  4029.6     .11       0  4980.6     .06       0  5011.5     .11       0
Bank Sta=4980.6,5011.5
XS Rating Curve= 0 ,0
Exp/Cntr=0.3,0.1

Type RM Length L Ch R = 1 ,347886  ,386,386,386
BEGIN DESCRIPTION:
LAKE CREEK 674.0
END DESCRIPTION:
XS GIS Cut Line= 3
      3694500.88     10218117.55      3694537.34     10217643.63
      3694517.85     10216511.12
#Sta/Elev= 30
  4484.8   331.9    4742  326.64  4774.2  326.83  4842.3  324.98  4899.6  324.89
  4942.6  323.43  4982.7  323.27  4992.7  322.33  4999.2  318.74  5006.2  318.74
  5012.7  322.39  5022.7  323.15  5062.7  323.51  5092.7  322.95  5102.7  323.48
  5152.7  323.28  5162.7  322.42  5232.7  323.54  5242.7  322.98  5272.7  323.52
  5292.7  322.95  5412.7   323.8  5452.8  322.74  5482.8  319.88  5512.8  323.08
  5532.8  323.66  5602.8  323.62  5902.8  327.86  5982.8  330.33  6092.8  332.63
#Mann= 3 , 0 , 0
  4484.8     .11       0  4992.7     .06       0  5012.7     .11       0
Bank Sta=4992.7,5012.7
XS Rating Curve= 0 ,0
Exp/Cntr=0.3,0.1

Type RM Length L Ch R = 1 ,347500  ,500,500,500
BEGIN DESCRIPTION:
LAKE CREEK 673.0
END DESCRIPTION:
XS GIS Cut Line= 3
      3694767.85     10218161.05      3694855.35     10217497.09
      3694767.85     10216511.06
#Sta/Elev= 30
  4330.3   331.9  4572.4  328.51  4693.4  324.96  4743.8   324.1  4834.6  323.16
  4864.9  323.63  4935.5  321.93  4965.7  322.65  4980.9  321.98  4985.9  320.99
  4991.9  317.36  4999.1  317.36  5016.1  322.63  5106.4  322.31  5206.8  323.11
  5258.3     321  5297.2  323.74  5317.3  323.57  5337.3  320.08  5347.4  322.38
  5357.4  323.18  5377.5  322.88  5387.5  322.13  5407.6  322.83  5417.7  322.36
  5447.8  323.12  5598.6  324.52  5799.1   329.4  5909.6  331.09  5989.9  333.44
#Mann= 3 , 0 , 0
  4330.3     .11       0  4980.9     .06       0  5016.1     .11       0
Bank Sta=4980.9,5016.1
XS Rating Curve= 0 ,0
Exp/Cntr=0.3,0.1

Type RM Length L Ch R = 1 ,347000  ,294,294,294
BEGIN DESCRIPTION:
LAKE CREEK 672.0
END DESCRIPTION:
XS GIS Cut Line= 3
      3695579.01     10218331.14      3695126.87     10217107.93
      3694828.99     10216497.76
#Sta/Elev= 30
  3695.9  333.17  3962.5  327.42  4133.1  325.04    4264  324.31  4282.3  323.44
  4638.1   322.6  4718.6  321.45  4730.1  320.11  4740.8  321.41  4749.1   321.5
  4794.1  320.27    4835  321.23  4920.9  320.71  4956.6  321.31  4975.3  318.92
  4981.7  319.15    4987  317.73    5000  317.99    5002  315.94  5009.3  315.94
  5028.1  321.75  5033.7  319.26  5050.7  322.33  5085.5  322.22    5130  323.25
  5185.7  323.03  5354.6  325.28  5602.4     331  5641.9  332.84    5679  332.81
#Mann= 3 , 0 , 0
  3695.9     .11       0  4956.6     .06       0  5028.1     .11       0
Bank Sta=4956.6,5028.1
XS Rating Curve= 0 ,0
Exp/Cntr=0.3,0.1

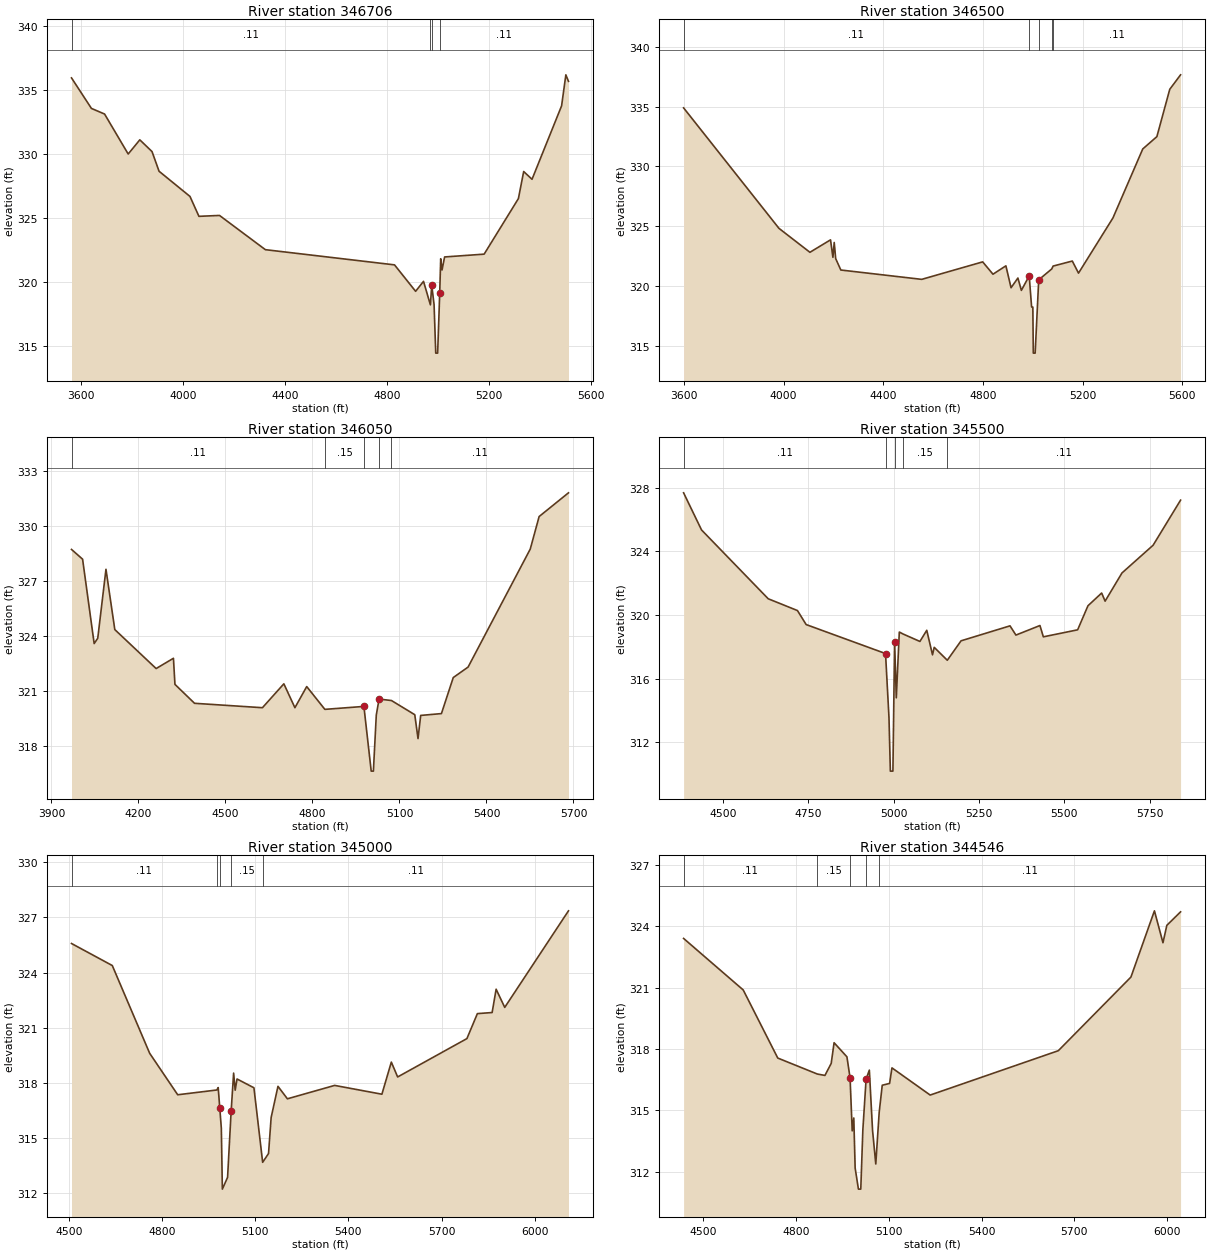
Type RM Length L Ch R = 1 ,346706  ,206,206,206
BEGIN DESCRIPTION:
Mapping XS 2f667da0
END DESCRIPTION:
XS GIS Cut Line= 2
      3695740.47     10218466.57      3695245.67     10216581.12
#Sta/Elev= 30
  3563.1  335.96  3641.2  333.57  3692.8  333.13  3785.4     330    3831  331.11
  3878.9  330.19  3906.5  328.65  4027.7  326.68  4062.9  325.12  4143.6  325.19
  4323.5  322.51  4830.1  321.32  4912.8  319.25  4943.8  320.03  4970.8  318.19
    4976  319.72  4985.2  318.21  4991.8  314.41  4999.2  314.41 5007.38319.1331
  5011.2   321.8  5016.4  320.92  5026.5  321.94  5181.6  322.16    5316  326.51
  5336.7  328.63  5369.4  328.02  5485.4  333.77  5502.1   336.2  5512.4  335.69
#Mann= 4 ,-1 , 0
  3563.1     .11       0  4970.8     .08       0    4976     .06       0
 5007.38     .11       0
Bank Sta=4976,5007.38
XS Rating Curve= 0 ,0
Exp/Cntr=0.3,0.1

Type RM Length L Ch R = 1 ,346500  ,450,450,450
BEGIN DESCRIPTION:
LAKE CREEK 671.0
END DESCRIPTION:
XS GIS Cut Line= 3
      3695927.96     10218450.92      3695567.88     10217096.57
      3695454.27     10216514.76
#Sta/Elev= 30
  3598.6  334.89  3981.3  324.83  4105.5  322.83  4188.2  323.87  4197.8  322.41
    4203  323.65  4208.9   322.3  4229.6  321.35  4554.1  320.57  4798.7  322.03
  4840.1     321  4891.9   321.7  4912.6  319.87  4940.1  320.68    4954  319.65
  4985.4  320.86  4995.1  318.26    5000  318.26  5001.9  314.41  5009.3  314.41
  5023.6  320.53  5075.9  321.44  5081.4  321.68  5158.4   322.1  5183.3  321.09
  5321.5   325.7  5441.1  331.46  5497.8  332.49  5549.4  336.44  5592.8  337.65
#Mann= 5 ,-1 , 0
  3598.6     .11       0  4985.4     .06       0  5023.6     .11       0
  5075.9     .15       0  5081.4     .11       0
Bank Sta=4985.4,5023.6
XS Rating Curve= 0 ,0
Exp/Cntr=0.3,0.1

Type RM Length L Ch R = 1 ,346050  ,550,550,550
BEGIN DESCRIPTION:
LAKE CREEK 670.0
END DESCRIPTION:
XS GIS Cut Line= 4
      3695959.21     10218247.78      3695797.76     10217398.84
      3695943.59     10217159.25      3696058.17     10216601.95
#Sta/Elev= 30
  3969.2  328.72  4007.4  328.19  4047.3   323.6  4059.7  323.89    4088  327.64
  4118.5  324.36    4261  322.24  4320.7   322.8  4325.8  321.38  4393.4  320.35
  4627.5  320.11  4701.4  321.41  4739.5  320.11  4780.2  321.26  4842.8  320.02
  4977.4  320.18  5002.6  316.66  5010.1  316.66  5020.1  319.71  5029.7  320.58
  5072.5   320.5  5152.8  319.73    5164  318.43  5173.2  319.69  5244.7  319.79
  5285.5  321.75  5336.6  322.32    5551  328.74  5581.6  330.51  5682.8   331.8
#Mann= 5 ,-1 , 0
  3969.2     .11       0  4842.8     .15       0  4977.4     .09       0
  5029.7     .15       0  5072.5     .11       0
Bank Sta=4977.4,5029.7
XS Rating Curve= 0 ,0
Exp/Cntr=0.3,0.1

Type RM Length L Ch R = 1 ,345500  ,500,500,500
BEGIN DESCRIPTION:
LAKE CREEK 669.0
END DESCRIPTION:
XS GIS Cut Line= 3
      3696105.04     10218206.17      3696193.25     10217598.03
      3696117.85     10216761.02
#Sta/Elev= 30
  4385.5  327.67    4438  325.34  4633.2  321.02  4718.8  320.28  4744.3   319.4
  4976.7  317.58  4986.8  313.55  4990.8   310.2  4998.3   310.2  5003.2  318.33
  5008.2   314.8    5017  318.93  5027.8  318.81  5077.3  318.34  5097.4  319.04
  5114.2   317.5  5119.2  317.97  5157.5  317.16  5197.8  318.38  5341.1  319.32
  5358.4  318.74  5428.7  319.34  5438.7  318.63  5539.1  319.07  5569.3  320.58
  5609.4  321.38  5619.5  320.87  5668.9  322.64    5760  324.38  5840.4  327.21
#Mann= 5 ,-1 , 0
  4385.5     .11       0  4976.7     .07       0  5003.2     .11       0
  5027.8     .15       0  5157.5     .11       0
Bank Sta=4976.7,5003.2
XS Rating Curve= 0 ,0
Exp/Cntr=0.3,0.1

Type RM Length L Ch R = 1 ,345000  ,454,454,454
BEGIN DESCRIPTION:
LAKE CREEK 668.0
END DESCRIPTION:
XS GIS Cut Line= 3
      3696589.42     10218101.99      3696628.63     10217611.86
      3696443.59     10216518.61
#Sta/Elev= 30
  4508.3  325.58  4639.6  324.38    4760   319.6  4850.3  317.34  4976.2   317.6
  4980.7  317.73 4985.66316.6447  4990.8  315.52  4994.1   312.2  5010.9  312.84
 5022.35316.4339  5030.4  318.52  5035.4  317.59  5041.4   318.2  5095.8  317.72
  5123.9  313.66  5142.8  314.14  5151.2   316.1  5173.2   317.8  5203.6  317.12
  5355.8  317.85  5507.9  317.37  5538.3  319.12  5558.6  318.31  5781.7   320.4
  5815.4  321.76  5862.9  321.82  5875.8  323.09  5903.5   322.1  6108.8  327.36
#Mann= 5 ,-1 , 0
  4508.3     .11       0  4976.2     .15       0 4985.66     .09       0
 5022.35     .15       0  5123.9     .11       0
Bank Sta=4985.66,5022.35
XS Rating Curve= 0 ,0
Exp/Cntr=0.3,0.1

Type RM Length L Ch R = 1 ,344546  ,320,320,320
BEGIN DESCRIPTION:
LAKE CREEK 667.0
END DESCRIPTION:
XS GIS Cut Line= 3
      3696865.46     10218070.75      3696964.42     10217523.84
      3696657.14     10216518.65
#Sta/Elev= 30
  4436.5  323.41  4629.3  320.89    4741  317.56  4868.7  316.78  4893.5  316.71
  4913.8   317.3  4923.1  318.31  4964.6  317.62  4974.8  316.59  4981.7     314
  4986.8  314.63  4991.2  312.18  5001.8  311.15  5009.4  311.15  5016.1  314.05
  5026.6  316.53  5037.1  316.97  5047.5  314.02  5057.9  312.38  5068.9   314.9
  5078.8  316.23  5102.6  316.32  5110.2  317.08  5233.8  315.75  5648.2  317.92
  5882.9  321.52  5958.9  324.76  5986.5   323.2    5999  324.05  6043.4  324.71
#Mann= 5 ,-1 , 0
  4436.5     .11       0  4868.7     .15       0  4974.8     .09       0
  5026.6     .15       0  5068.9     .11       0
Bank Sta=4974.8,5026.6
XS Rating Curve= 0 ,0
Exp/Cntr=0.3,0.1

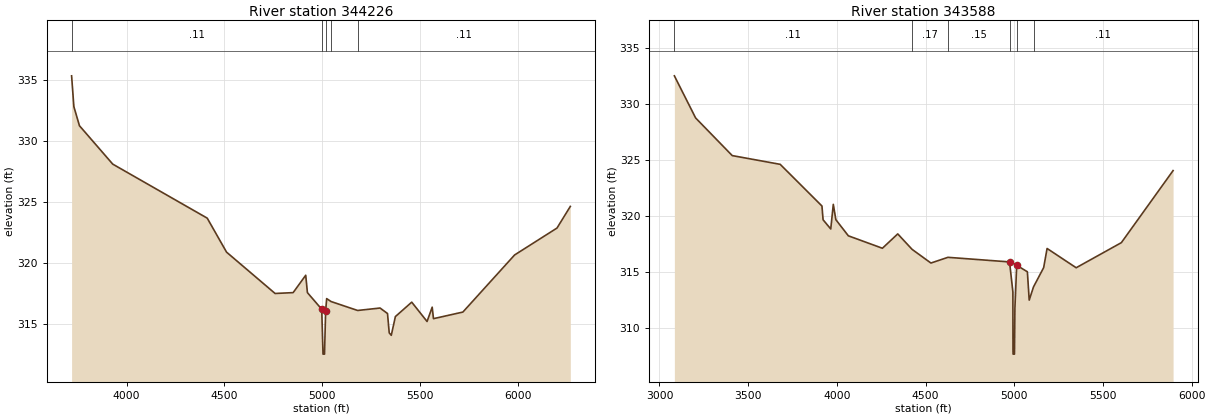
Type RM Length L Ch R = 1 ,344226  ,638,638,638
BEGIN DESCRIPTION:
Mapping XS 234237df
END DESCRIPTION:
XS GIS Cut Line= 3
      3696448.77     10218648.87      3697224.84     10217742.59
      3696829.06      10216445.9
#Sta/Elev= 30
  3718.9  335.31  3730.5  332.79    3759  331.23  3929.1  328.09  4412.1  323.67
  4510.9  320.89    4759  317.51  4851.2  317.58  4915.5     319  4924.1  317.58
  4997.3  316.22  5003.9  312.55  5011.5  312.55  5017.3  316.08  5022.5  317.09
  5045.1  316.85    5181  316.12  5295.5  316.32  5333.5  315.87  5342.3  314.29
  5352.8  314.09  5373.7  315.62  5457.3   316.8  5535.6  315.22  5561.9  316.39
  5568.4  315.45  5718.7  315.99  5983.1  320.66  6199.7  322.86  6267.8  324.63
#Mann= 5 ,-1 , 0
  3718.9     .11       0  4997.3     .06       0  5017.3     .11       0
  5045.1     .15       0    5181     .11       0
Bank Sta=4997.3,5017.3
XS Rating Curve= 0 ,0
Exp/Cntr=0.3,0.1

Type RM Length L Ch R = 1 ,343588  ,636,636,636
BEGIN DESCRIPTION:
Mapping XS 59c53da6
END DESCRIPTION:
XS GIS Cut Line= 4
      3696511.32      10218773.8      3697401.92     10217664.46
      3697308.17     10216893.63       3696896.7     10216440.49
#Sta/Elev= 30
  3084.1  332.48  3203.9  328.72  3410.3  325.36  3680.7  324.58    3916  320.86
  3922.4  319.63  3965.6  318.81    3980  321.01  3994.4  319.64  4064.8   318.2
  4256.8  317.09  4343.2  318.37  4424.2  316.99  4530.3  315.77  4626.2  316.28
  4973.5  315.87  4992.3  313.19  4992.9  308.14  4993.4  307.64  5001.2  307.64
  5003.7  311.75  5013.8  315.57    5074  314.99  5084.3  312.46  5108.5  313.64
  5165.8  315.36  5185.1  317.07    5349  315.35  5603.8  317.59  5895.3  324.02
#Mann= 6 ,-1 , 0
  3084.1     .11       0  4424.2     .17       0  4626.2     .15       0
  4973.5     .09       0  5013.8     .15       0  5108.5     .11       0
Bank Sta=4973.5,5013.8
XS Rating Curve= 0 ,0
Exp/Cntr=0.3,0.1