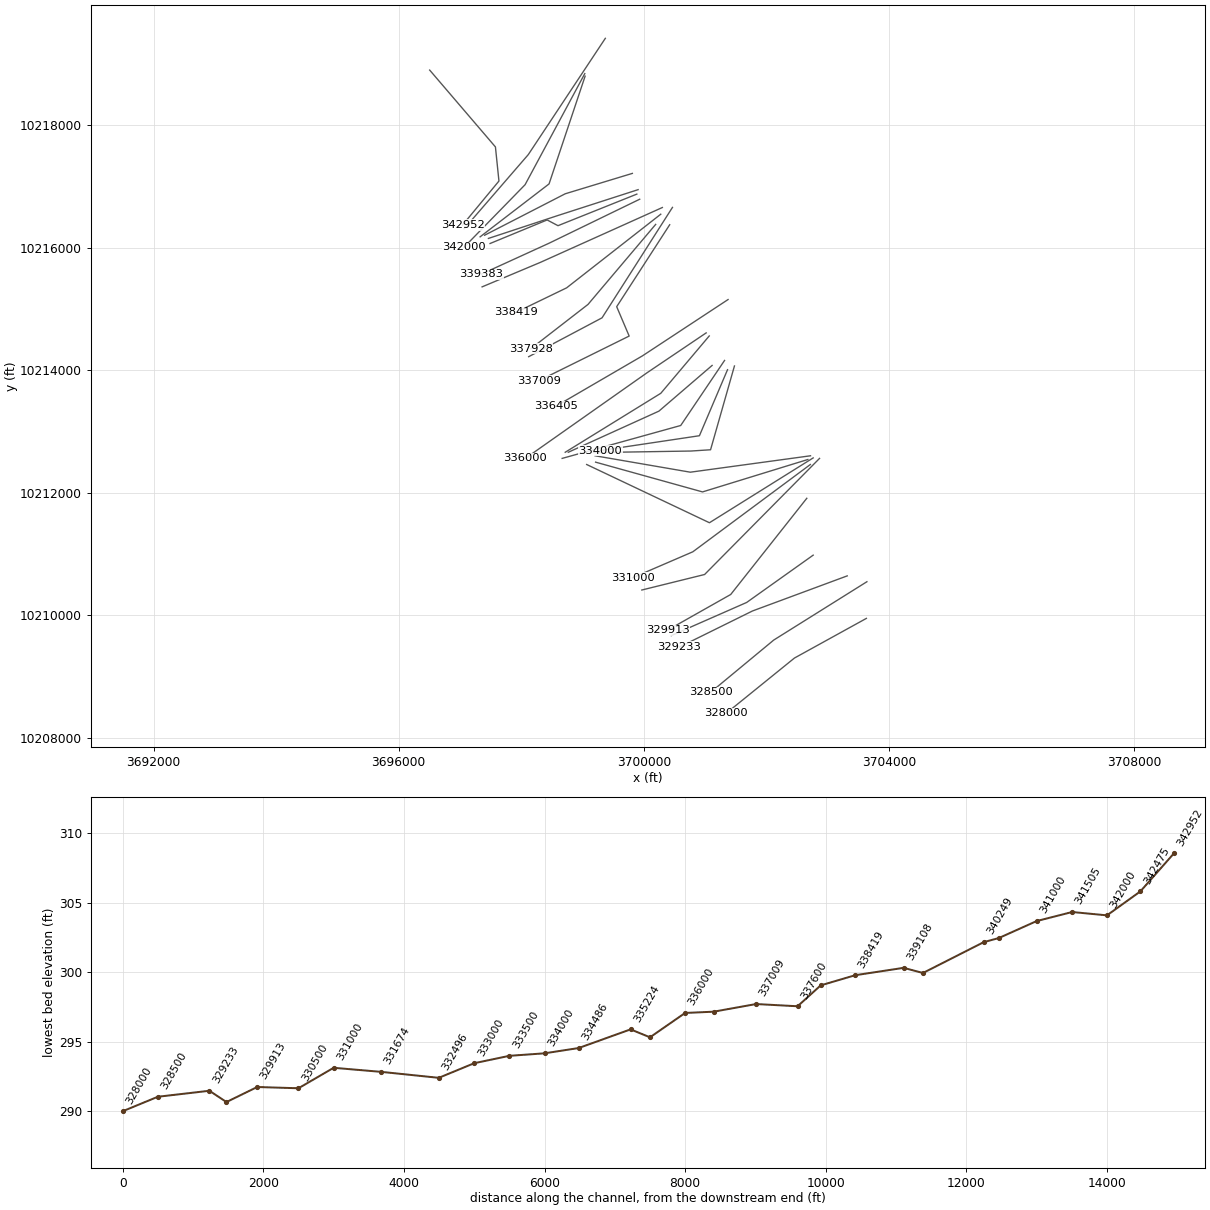
HEC-RAS study LAKE CREEK.prj: LAKE CREEK Base Level Engineering

--- LAKE CREEK.g01 (geometry) --- (continued)

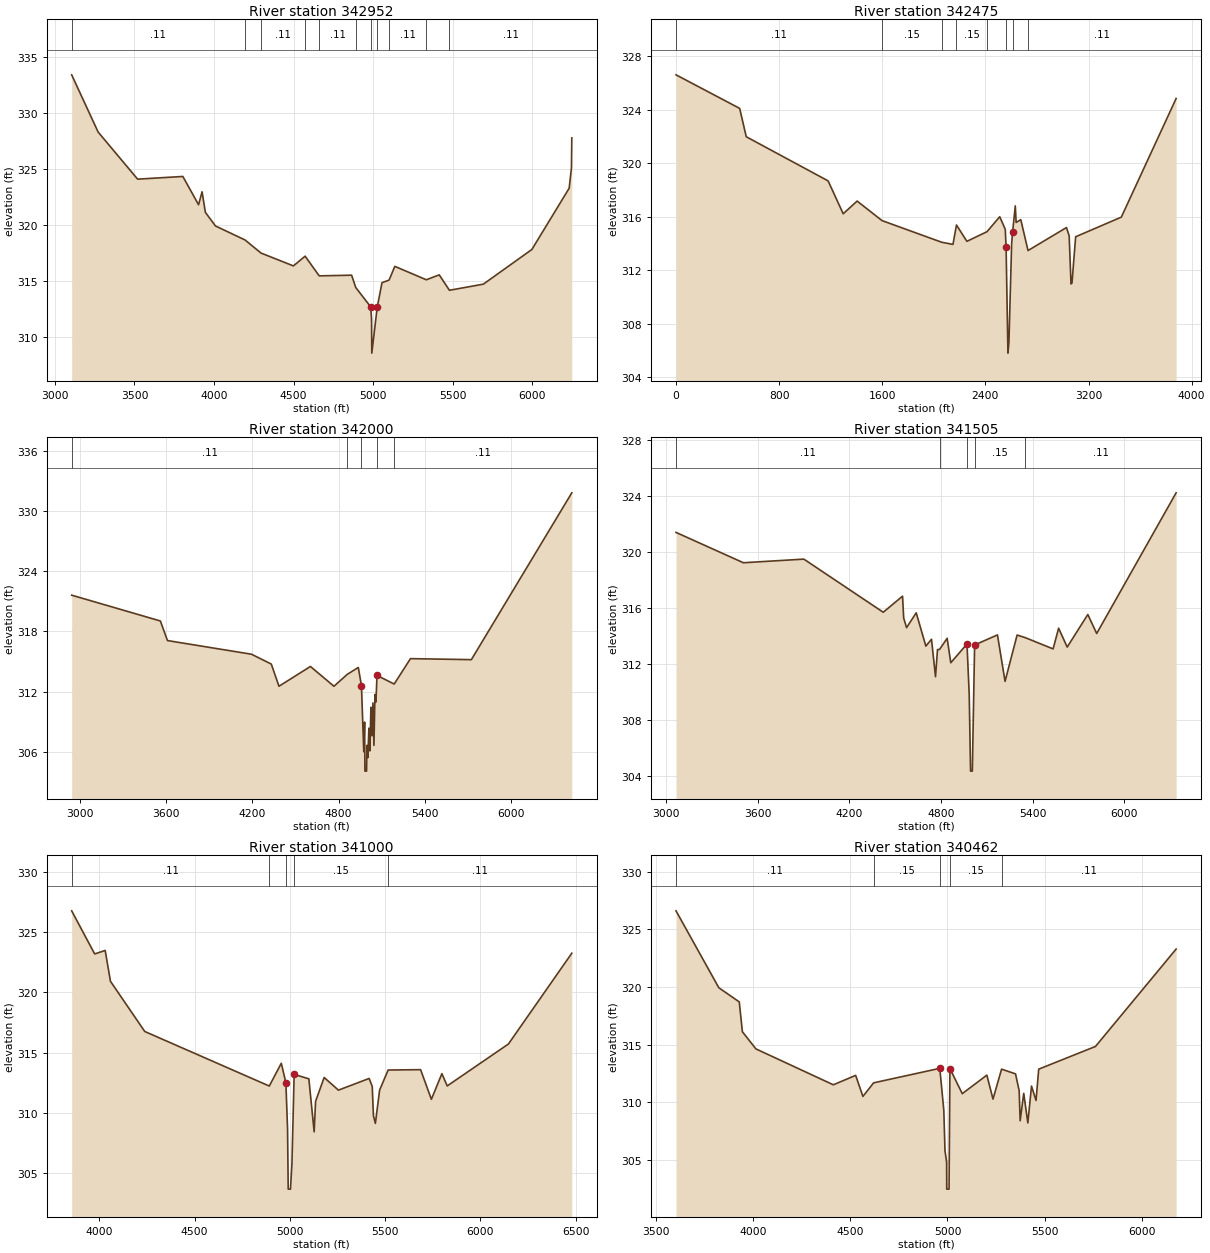
Type RM Length L Ch R = 1 ,342952  ,477,477,477
BEGIN DESCRIPTION:
Mapping XS 6c86430d
END DESCRIPTION:
XS GIS Cut Line= 4
      3696506.07     10218904.06      3697579.01     10217648.84
       3697636.3     10217091.54      3697042.68     10216372.95
#Sta/Elev= 30
  3105.2  333.42  3271.6   328.3  3519.7  324.09    3804  324.33  3902.8   321.8
  3924.8  322.96  3945.6  321.12  4009.3   319.9  4194.9  318.65  4295.3  317.48
  4498.9  316.33  4572.6   317.2  4661.1  315.44  4864.8   315.5  4890.7   314.4
  4985.1  312.66  4990.1  311.56  4991.6  308.53  5025.7  312.63  5055.8  314.83
  5100.2  315.06  5136.3  316.29  5334.5  315.09  5415.5  315.53  5479.6  314.15
    5693   314.7  5997.8   317.8  6232.3  323.28  6246.6   325.1  6248.8  327.78
#Mann= 11 ,-1 , 0
  3105.2     .11       0  4194.9     .17       0  4295.3     .11       0
  4572.6     .17       0  4661.1     .11       0  4890.7     .15       0
  4985.1     .09       0  5025.7     .15       0  5100.2     .11       0
  5334.5     .15       0  5479.6     .11       0
Bank Sta=4985.1,5025.7
XS Rating Curve= 0 ,0
Exp/Cntr=0.3,0.1

Type RM Length L Ch R = 1 ,342475  ,475,475,475
BEGIN DESCRIPTION:
LAKE CREEK 663.0
END DESCRIPTION:
XS GIS Cut Line= 3
      3699372.25     10219422.73      3698115.46     10217523.84
      3697067.85     10216311.07
#Sta/Elev= 30
       0  326.61   493.9   324.1     545  321.98  1179.9  318.68  1297.1  316.22
    1405  317.17  1598.1  315.71  2061.5  314.09  2148.5  313.93  2175.8  315.38
  2256.5  314.16  2412.6  314.88  2511.3     316  2554.1  315.06  2560.7   313.7
  2574.9   305.8  2582.6  306.61  2603.5  313.95  2611.1  314.85    2632  316.81
  2638.6  315.57  2674.7  315.78  2730.7  313.47    3029  315.19  3049.9  314.57
  3064.2  310.98  3071.8  311.04  3100.1   314.5  3454.6  315.97  3879.7  324.84
#Mann= 8 ,-1 , 0
       0     .11       0  1598.1     .15       0  2061.5     .11       0
  2175.8     .15       0  2412.6     .11       0  2560.7     .09       0
  2611.1     .15       0  2730.7     .11       0
Bank Sta=2560.7,2611.1
XS Rating Curve= 0 ,0
Exp/Cntr=0.3,0.1

Type RM Length L Ch R = 1 ,342000  ,495,495,495
BEGIN DESCRIPTION:
LAKE CREEK 662.0
END DESCRIPTION:
XS GIS Cut Line= 3
      3699037.36     10218846.78      3698062.84     10217031.75
      3697067.86     10216011.08
#Sta/Elev= 30
  2939.9   321.6    3558  319.03  3607.6  317.08    4193  315.72  4331.1  314.74
  4384.6  312.53  4603.8   314.5  4767.8  312.53    4861  313.72  4937.5   314.4
  4959.4   312.6  4975.6  306.01  4981.3  308.96  4983.6  304.08  4995.2  304.08
  4997.5  306.65    5004  305.42  5011.1  308.36  5018.1  306.09  5025.3  310.44
  5032.3   307.6  5039.4  310.87  5046.4  306.65  5053.6  311.71  5060.5  310.96
  5067.7  313.61  5187.6  312.75    5301  315.28  5725.4  315.18  6425.4  331.79
#Mann= 5 ,-1 , 0
  2939.9     .11       0    4861     .15       0  4959.4     .09       0
  5067.7     .15       0  5187.6     .11       0
Bank Sta=4959.4,5067.7
XS Rating Curve= 0 ,0
Exp/Cntr=0.3,0.1

Type RM Length L Ch R = 1 ,341505  ,505,505,505
BEGIN DESCRIPTION:
LAKE CREEK 661.0
END DESCRIPTION:
XS GIS Cut Line= 3
      3699042.56     10218805.11      3698454.01     10217044.67
      3697328.98     10216180.07
#Sta/Elev= 30
  3064.1  321.39  3505.3  319.22  3901.3  319.48  4421.3  315.68  4547.6  316.83
  4555.1  315.26    4574  314.58  4637.1  315.64  4700.3  313.26  4737.2  313.75
  4763.5  311.07  4776.5  313.01  4789.8  313.02  4839.8  313.82  4863.5  312.07
  4969.7  313.41  4984.2   309.8    4993  304.32  5004.6  304.32  5019.6  313.34
  5169.1  314.06  5218.9  310.74  5297.8  314.05    5350  313.87  5533.5  313.06
  5569.7  314.54  5625.9  313.19  5760.9  315.52  5818.9  314.16  6339.2  324.22
#Mann= 5 ,-1 , 0
  3064.1     .11       0  4789.8     .15       0  4969.7     .09       0
  5019.6     .15       0    5350     .11       0
Bank Sta=4969.7,5019.6
XS Rating Curve= 0 ,0
Exp/Cntr=0.3,0.1

Type RM Length L Ch R = 1 ,341000  ,538,538,538
BEGIN DESCRIPTION:
LAKE CREEK 660.0
END DESCRIPTION:
XS GIS Cut Line= 3
      3699813.38     10217216.54      3698717.95     10216883.63
      3697402.35     10216206.35
#Sta/Elev= 30
  3855.1  326.78  3975.8   323.2    4031  323.49  4058.6  320.93  4238.7  316.76
  4892.2  312.23  4955.1  314.12  4979.2  312.51    4988  308.68  4991.5  303.67
  5003.3  303.67  5011.1  305.82  5022.6   313.2  5099.8  312.83  5127.6  308.43
  5135.1  310.96  5180.1  312.94    5255  311.89  5416.3  312.86  5432.4  312.19
  5438.8  309.75  5448.9  309.13  5471.1  311.89  5515.8  313.56  5686.2  313.59
  5742.8  311.13    5798  313.26  5825.8  312.24  6147.1  315.72  6479.7  323.26
#Mann= 5 ,-1 , 0
  3855.1     .11       0  4892.2     .15       0  4979.2     .09       0
  5022.6     .15       0  5515.8     .11       0
Bank Sta=4979.2,5022.6
XS Rating Curve= 0 ,0
Exp/Cntr=0.3,0.1

Type RM Length L Ch R = 1 ,340462  ,213,213,213
BEGIN DESCRIPTION:
LAKE CREEK 659.0
END DESCRIPTION:
XS GIS Cut Line= 3
      3699907.17     10216950.93      3698584.21     10216523.84
      3697464.39     10216154.03
#Sta/Elev= 30
  3605.3  326.62  3825.3  319.94  3930.3  318.71  3946.4  316.12  4015.7  314.63
  4413.7  311.51  4528.3  312.33  4565.6   310.5  4620.5  311.68  4960.5  312.94
  4981.2  309.31  4987.3  305.76  4995.5  304.82  4996.3  302.45  5008.1  302.45
  5012.7  312.92  5075.9  310.74  5202.3  312.35  5233.9  310.27    5278  312.87
  5349.7  312.46  5368.3     311  5373.5  308.39  5391.8  310.77  5412.9   308.2
  5431.8   311.4    5455  310.15  5468.8  312.87  5760.4  314.84  6174.8   323.3
#Mann= 5 ,-1 , 0
  3605.3     .11       0  4620.5     .15       0  4960.5     .09       0
  5012.7     .15       0    5278     .11       0
Bank Sta=4960.5,5012.7
XS Rating Curve= 0 ,0
Exp/Cntr=0.3,0.1

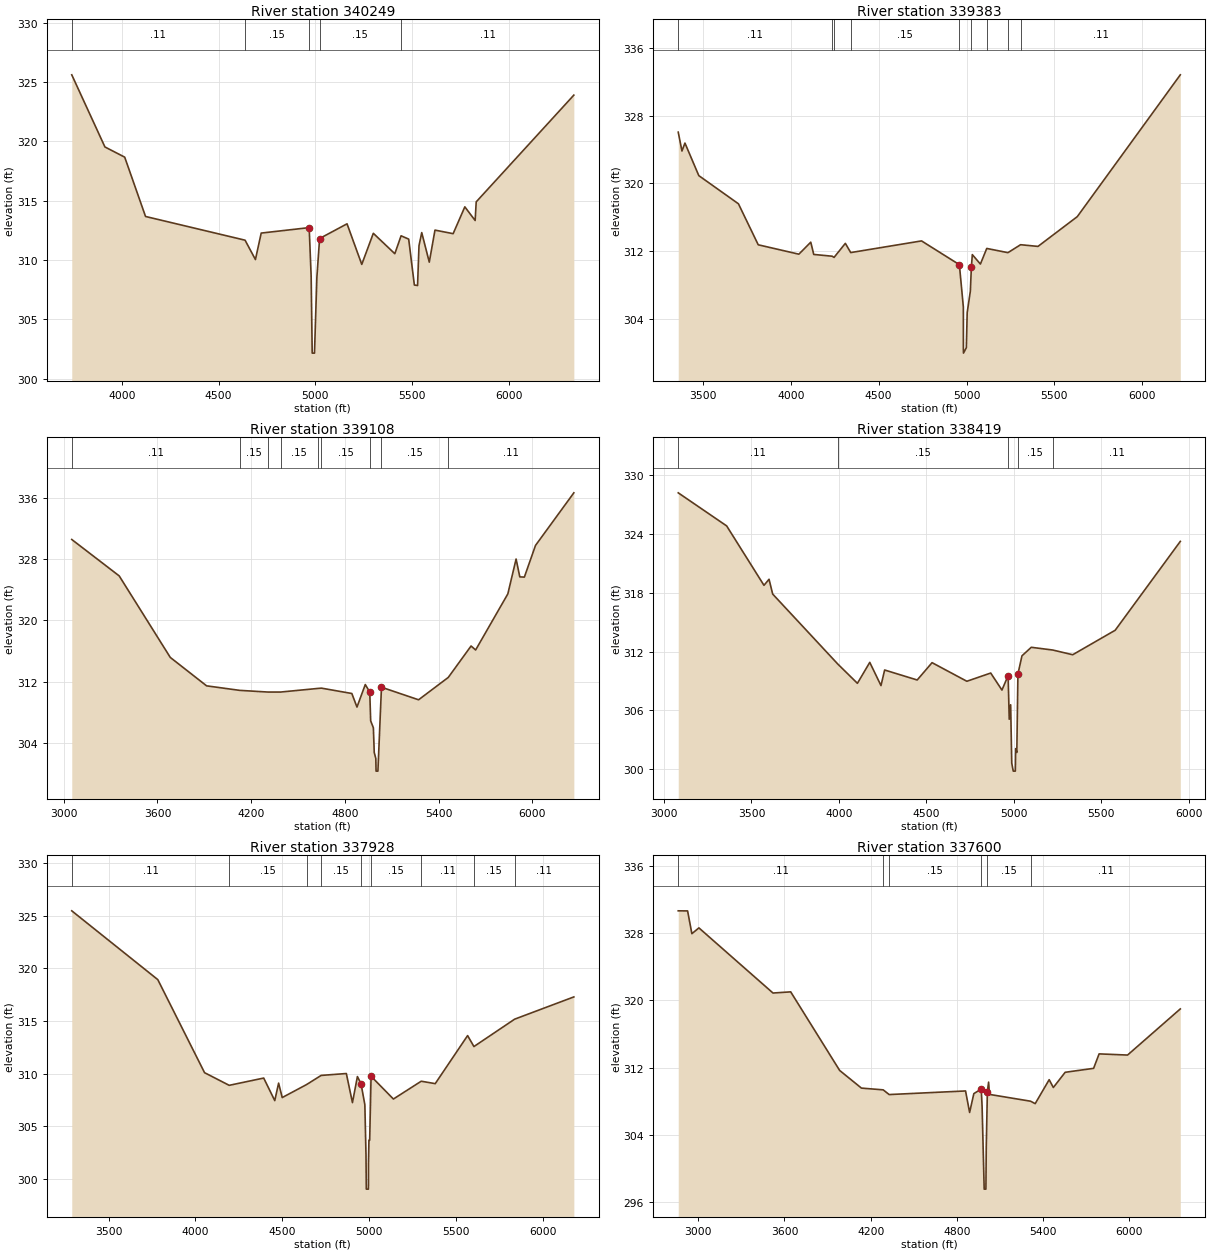
Type RM Length L Ch R = 1 ,340249  ,866,866,866
BEGIN DESCRIPTION:
Mapping XS c6464f07
END DESCRIPTION:
XS GIS Cut Line= 4
      3699886.28     10216877.99      3698599.84     10216362.38
      3698422.76     10216456.13      3697491.67     10216071.21
#Sta/Elev= 30
  3741.4  325.62  3912.7  319.54  4014.9  318.68  4122.5  313.68  4636.7  311.68
  4690.2  310.05  4720.1  312.28  4967.9  312.74  4978.1  308.64  4983.5  302.16
  4995.3  302.16  5007.7  308.56  5021.7  311.82  5163.5  313.06  5239.6  309.64
  5299.3  312.26  5410.3  310.54  5442.7  312.05    5482  311.77  5511.3   307.9
  5527.8  307.86  5535.2  311.21  5549.4  312.32  5588.4  309.83  5617.8  312.53
  5711.7  312.23    5772  314.49  5825.3  313.34  5830.8  314.91  6335.2  323.91
#Mann= 5 ,-1 , 0
  3741.4     .11       0  4636.7     .15       0  4967.9     .09       0
  5021.7     .15       0  5442.7     .11       0
Bank Sta=4967.9,5021.7
XS Rating Curve= 0 ,0
Exp/Cntr=0.3,0.1

Type RM Length L Ch R = 1 ,339383  ,275,275,275
BEGIN DESCRIPTION:
LAKE CREEK 657.0
END DESCRIPTION:
XS GIS Cut Line= 3
      3699933.21     10216794.69      3698454.01     10216075.92
      3697351.34      10215571.4
#Sta/Elev= 30
  3359.4  326.07  3380.6  323.84  3397.6  324.78  3476.5  320.93    3702   317.6
  3814.7  312.75  4045.9  311.64  4113.6  313.06  4130.6  311.61  4235.6   311.4
  4246.1  311.26  4310.4  312.92    4341  311.83    4744  313.21  4959.3   310.4
  4981.9   305.4  4982.2  300.44  4982.7  299.94  4998.9  300.58  5003.8  304.73
  5021.8  307.28  5027.5  310.07    5033  311.59    5079  310.47  5115.1  312.32
  5235.7  311.82  5307.5  312.76  5406.7  312.56  5630.3  316.08  6216.6  332.85
#Mann= 9 ,-1 , 0
  3359.4     .11       0  4235.6     .15       0  4246.1     .11       0
    4341     .15       0  4959.3     .09       0  5027.5     .15       0
  5115.1     .11       0  5235.7     .15       0  5307.5     .11       0
Bank Sta=4959.3,5027.5
XS Rating Curve= 0 ,0
Exp/Cntr=0.3,0.1

Type RM Length L Ch R = 1 ,339108  ,689,689,689
BEGIN DESCRIPTION:
LAKE CREEK 656.0
END DESCRIPTION:
XS GIS Cut Line= 3
      3700302.94     10216659.24      3698313.38     10215763.42
      3697361.54     10215362.92
#Sta/Elev= 30
  3051.4  330.54    3355  325.79  3682.1  315.15  3914.7  311.44  4126.4  310.85
  4307.4  310.63  4388.3  310.63  4626.6   311.1  4650.1  311.14  4844.6  310.44
  4877.5  308.67  4930.7  311.61  4959.3  310.63  4965.2  306.87  4982.5  305.96
    4988  302.74  4998.1  301.96  4999.7  300.31  5011.5  300.31  5034.3  311.26
  5271.9  309.62  5462.1  312.54    5608  316.64  5637.2  316.12  5843.4  323.44
  5896.3  327.99    5920  325.66  5949.2  325.63  6020.4  329.76    6266  336.63
#Mann= 9 ,-1 , 0
  3051.4     .11       0  4126.4     .15       0  4307.4     .11       0
  4388.3     .15       0  4626.6     .11       0  4650.1     .15       0
  4959.3     .09       0  5034.3     .15       0  5462.1     .11       0
Bank Sta=4959.3,5034.3
XS Rating Curve= 0 ,0
Exp/Cntr=0.3,0.1

Type RM Length L Ch R = 1 ,338419  ,491,491,491
BEGIN DESCRIPTION:
LAKE CREEK 655.0
END DESCRIPTION:
XS GIS Cut Line= 3
      3700276.92     10216549.88      3698740.46     10215346.75
      3697912.96     10214946.01
#Sta/Elev= 30
  3081.1  328.21    3358  324.83  3571.4  318.76  3600.3  319.38  3621.1  317.87
  3993.4  310.72  4105.7  308.75  4176.3  310.89  4240.5  308.52  4261.3  310.11
  4447.5  309.09  4532.5  310.86  4731.4  308.96  4867.9   309.8  4932.1  308.06
  4967.4  309.54  4973.8  305.08  4981.9  306.56  4988.2  300.59  4996.8  299.78
  5008.6  299.78  5010.5  302.08  5017.1  301.69  5023.5   309.7  5046.6  311.56
  5099.8  312.43  5222.8  312.15  5336.7  311.67  5579.6  314.17    5952  323.25
#Mann= 5 ,-1 , 0
  3081.1     .11       0  3993.4     .15       0  4967.4     .09       0
  5023.5     .15       0  5222.8     .11       0
Bank Sta=4967.4,5023.5
XS Rating Curve= 0 ,0
Exp/Cntr=0.3,0.1

Type RM Length L Ch R = 1 ,337928  ,328,328,328
BEGIN DESCRIPTION:
LAKE CREEK 654.0
END DESCRIPTION:
XS GIS Cut Line= 3
      3700193.62     10216383.24      3699089.42     10215075.92
      3698157.09     10214353.02
#Sta/Elev= 30
  3288.5  325.46  3783.9  318.93  4053.1   310.1    4195   308.9  4393.7  309.59
  4457.4  307.45  4479.5  309.11  4500.3  307.74  4640.3  308.97  4724.3  309.84
  4869.5  310.02  4904.7  307.26  4933.3  309.73  4954.1  309.05  4976.1  307.06
  4982.7  302.29  4984.5  299.05  4996.4  299.05  4996.9  299.55    4997  301.57
  4999.6  303.69  5003.9  303.69  5011.9  309.76  5140.5   307.6  5300.7  309.29
  5381.3  309.06  5567.8  313.62  5604.2  312.58  5838.8  315.18  6179.5  317.29
#Mann= 9 ,-1 , 0
  3288.5     .11       0    4195     .15       0  4640.3     .11       0
  4724.3     .15       0  4954.1     .09       0  5011.9     .15       0
  5300.7     .11       0  5604.2     .15       0  5838.8     .11       0
Bank Sta=4954.1,5011.9
XS Rating Curve= 0 ,0
Exp/Cntr=0.3,0.1

Type RM Length L Ch R = 1 ,337600  ,591,591,591
BEGIN DESCRIPTION:
LAKE CREEK 653.0
END DESCRIPTION:
XS GIS Cut Line= 3
      3700467.88     10216661.11      3699318.59     10214857.17
      3698121.78     10214222.34
#Sta/Elev= 30
  2860.7  330.66  2925.9  330.65  2955.6  327.94  3004.6  328.63  3520.1  320.88
  3643.3  321.02    3984  311.67  4135.5  309.57    4287  309.36  4328.5   308.8
    4860  309.23  4888.3  306.67  4917.6  308.91  4969.2  309.46  4975.2  307.35
  4989.7  297.55  5001.6  297.55  5004.1  302.51  5011.8  309.14  5020.4  310.28
  5026.1  308.82  5312.6  308.01  5344.6  307.72  5441.9  310.57  5470.9  309.64
  5553.2  311.45  5751.1  311.92  5789.4  313.64  5987.3   313.5  6354.4  318.99
#Mann= 6 ,-1 , 0
  2860.7     .11       0    4287     .17       0  4328.5     .15       0
  4969.2     .09       0  5011.8     .15       0  5312.6     .11       0
Bank Sta=4969.2,5011.8
XS Rating Curve= 0 ,0
Exp/Cntr=0.3,0.1

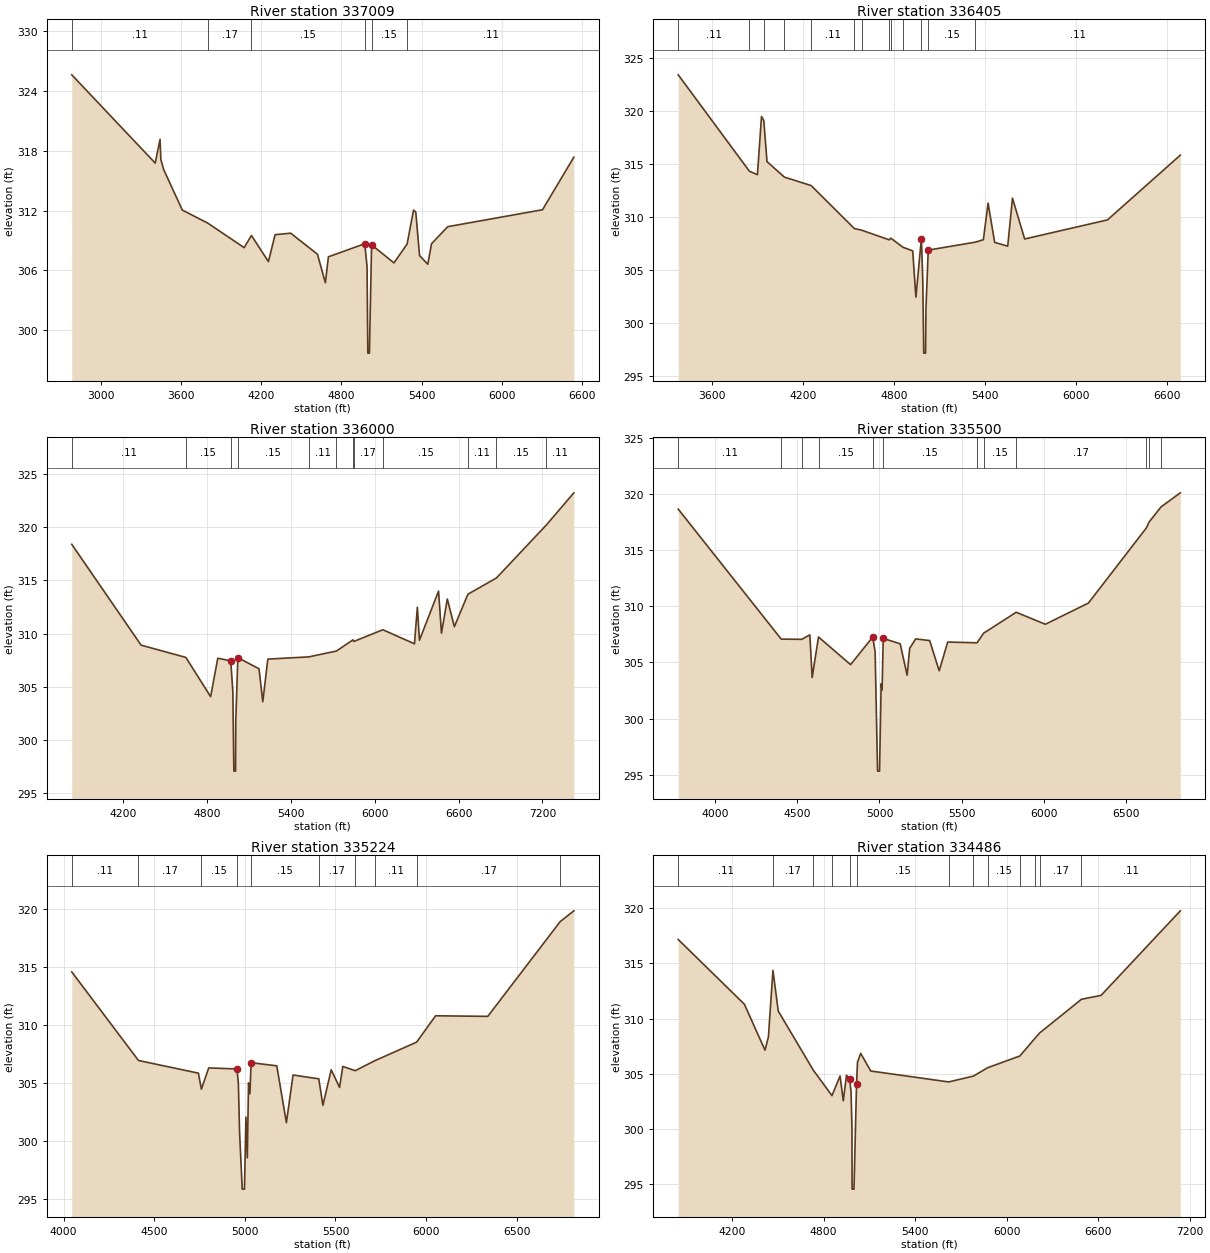
Type RM Length L Ch R = 1 ,337009  ,604,604,604
BEGIN DESCRIPTION:
LAKE CREEK 652.0
END DESCRIPTION:
XS GIS Cut Line= 4
      3700422.73     10216377.97      3699557.67     10215039.25
       3699761.3     10214559.43      3698292.69     10213832.27
#Sta/Elev= 30
  2783.8  325.62  3407.6  316.77  3443.9  319.15  3449.8  317.13    3471  316.12
  3610.1  312.06  3800.4  310.75  4072.6  308.29  4127.2  309.51  4254.1  306.89
  4304.1  309.59  4420.6  309.74  4620.7  307.63  4679.9  304.77  4702.6  307.37
  4974.7  308.68  4991.6  306.38  4997.3  297.71  5009.2  297.71  5025.5  308.57
  5192.9  306.76    5291  308.65  5339.1  312.05    5356  311.86    5384   307.5
  5445.7  306.62  5473.7  308.68  5594.6  310.39  6303.5  312.09  6537.7  317.36
#Mann= 6 ,-1 , 0
  2783.8     .11       0  3800.4     .17       0  4127.2     .15       0
  4974.7     .09       0  5025.5     .15       0    5291     .11       0
Bank Sta=4974.7,5025.5
XS Rating Curve= 0 ,0
Exp/Cntr=0.3,0.1

Type RM Length L Ch R = 1 ,336405  ,405,405,405
BEGIN DESCRIPTION:
LAKE CREEK 651.0
END DESCRIPTION:
XS GIS Cut Line= 3
      3701375.05      10215155.8      3699977.44     10214235.64
      3698562.71      10213411.1
#Sta/Elev= 30
  3374.7  323.42  3844.2  314.32  3896.9     314  3923.9  319.49  3938.8  319.12
  3960.1  315.23  4074.7  313.77  4251.4  312.97  4535.7  308.92  4586.3  308.75
  4766.2  307.85  4776.2  308.01  4856.7  307.15  4920.9  306.81  4941.9  302.44
  4978.1  307.96  4987.2   304.1  4993.6  297.16  5005.7  297.16  5008.2  301.35
  5023.3  306.88  5333.5  307.63  5386.9  307.86  5417.9  311.31  5461.3  307.61
  5547.3  307.25  5578.8  311.78    5659  307.93    6205  309.73  6685.5  315.84
#Mann= 13 ,-1 , 0
  3374.7     .11       0  3844.2     .15       0  3938.8     .11       0
  4074.7     .17       0  4251.4     .11       0  4535.7     .15       0
  4586.3     .11       0  4766.2     .17       0  4776.2     .11       0
  4856.7     .15       0  4978.1     .09       0  5023.3     .15       0
  5333.5     .11       0
Bank Sta=4978.1,5023.3
XS Rating Curve= 0 ,0
Exp/Cntr=0.3,0.1

Type RM Length L Ch R = 1 ,336000  ,500,500,500
BEGIN DESCRIPTION:
LAKE CREEK 650.0
END DESCRIPTION:
XS GIS Cut Line= 3
      3701017.82     10214611.05      3700050.16     10213957.84
      3698067.83     10212561.06
#Sta/Elev= 30
  3832.5  318.39  4328.6  308.91  4648.8  307.76  4826.1  304.07  4877.1  307.68
    4970  307.44    4985  304.58  4992.3  297.07  5004.4  297.07    5006  301.82
  5020.8  307.74  5172.3  306.69  5199.4  303.59  5235.3   307.6  5528.8  307.81
  5726.7  308.36  5844.3  309.41  5850.8  309.26  6058.2  310.36  6284.5  309.04
  6305.4  312.48  6320.2  309.37  6456.9  313.99  6477.8  310.03  6519.7  313.25
  6570.2  310.65  6667.1   313.7  6871.5  315.23  7226.3  320.18    7425  323.23
#Mann= 12 ,-1 , 0
  3832.5     .11       0  4648.8     .15       0    4970     .09       0
  5020.8     .15       0  5528.8     .11       0  5726.7     .17       0
  5844.3     .11       0  5850.8     .17       0  6058.2     .15       0
  6667.1     .11       0  6871.5     .15       0  7226.3     .11       0
Bank Sta=4970,5020.8
XS Rating Curve= 0 ,0
Exp/Cntr=0.3,0.1

Type RM Length L Ch R = 1 ,335500  ,276,276,276
BEGIN DESCRIPTION:
LAKE CREEK 649.0
END DESCRIPTION:
XS GIS Cut Line= 3
      3701067.88      10214561.1      3700277.02     10213624.16
      3698717.88     10212661.09
#Sta/Elev= 30
  3773.9  318.64  4401.3  307.07  4526.3  307.05  4575.6  307.45  4589.8  303.65
  4628.4  307.26  4823.9   304.8  4959.1  307.26  4973.4  305.92  4988.2  295.32
  5000.3  295.32  5010.1   303.1    5016  302.53  5022.5  307.14    5126  306.65
  5168.5  303.86  5183.9  306.25  5220.6  307.09  5305.7  306.94  5363.6  304.25
  5415.6  306.81  5594.3  306.74  5634.4   307.6  5832.8  309.46  6010.3  308.39
  6272.8  310.28    6626  316.97  6641.4  317.47  6715.4  318.84  6832.6  320.09
#Mann= 12 ,-1 , 0
  3773.9     .11       0  4401.3     .17       0  4526.3     .11       0
  4628.4     .15       0  4959.1     .09       0  5022.5     .15       0
  5594.3     .17       0  5634.4     .15       0  5832.8     .17       0
    6626     .15       0  6641.4     .17       0  6715.4     .11       0
Bank Sta=4959.1,5022.5
XS Rating Curve= 0 ,0
Exp/Cntr=0.3,0.1

Type RM Length L Ch R = 1 ,335224  ,738,738,738
BEGIN DESCRIPTION:
LAKE CREEK 648.0
END DESCRIPTION:
XS GIS Cut Line= 3
      3701114.62     10214079.41      3700246.54     10213332.86
      3698767.84     10212661.07
#Sta/Elev= 30
  4045.6   314.6  4413.5  306.97  4743.9  305.88  4760.5   304.5    4801  306.33
  4956.8  306.24  4964.5  305.01  4971.1  300.77  4985.8  295.89    4998  295.89
  5006.2  302.09  5013.8  298.59  5020.4  305.04  5028.1   304.1  5034.7  306.78
  5176.3  306.51  5229.3  301.62    5266  305.72  5407.9  305.39  5430.7  303.11
  5476.5  306.17  5522.7  304.65  5540.3  306.46  5608.9  306.09  5715.4  306.94
  5947.6  308.55  6052.2  310.82  6340.1  310.77  6739.2  318.93  6814.7  319.86
#Mann= 10 ,-1 , 0
  4045.6     .11       0  4413.5     .17       0  4760.5     .15       0
  4956.8     .09       0  5034.7     .15       0  5407.9     .17       0
  5608.9     .15       0  5715.4     .11       0  5947.6     .17       0
  6739.2     .11       0
Bank Sta=4956.8,5034.7
XS Rating Curve= 0 ,0
Exp/Cntr=0.3,0.1

Type RM Length L Ch R = 1 ,334486  ,486,486,486
BEGIN DESCRIPTION:
LAKE CREEK 647.0
END DESCRIPTION:
XS GIS Cut Line= 3
      3701317.82     10214161.03      3700602.44     10213098.49
      3698667.83     10212561.06
#Sta/Elev= 30
  3848.4  317.16  4281.7   311.3  4416.7  307.14  4439.1  308.34  4468.8  314.36
  4503.6  310.68  4733.9  305.31  4855.5  303.02  4908.5   304.8  4929.5  302.55
  4950.5  304.86  4971.5  304.54  4980.4  303.33  4986.5  300.03    4987  295.05
  4987.5  294.55  4999.7  294.55  5016.4   304.1  5022.5  306.04  5043.5  306.85
  5109.4  305.25  5619.8  304.26    5782  304.79  5875.7  305.55  6086.1  306.61
  6187.5  308.25  6216.1   308.7  6489.9  311.75  6618.2   312.1  7137.2  319.76
#Mann= 13 ,-1 , 0
  3848.4     .11       0  4468.8     .17       0  4733.9     .11       0
  4855.5     .15       0  4971.5     .09       0  5016.4     .15       0
  5619.8     .17       0    5782     .11       0  5875.7     .15       0
  6086.1     .17       0  6187.5     .11       0  6216.1     .17       0
  6489.9     .11       0
Bank Sta=4971.5,5016.4
XS Rating Curve= 0 ,0
Exp/Cntr=0.3,0.1

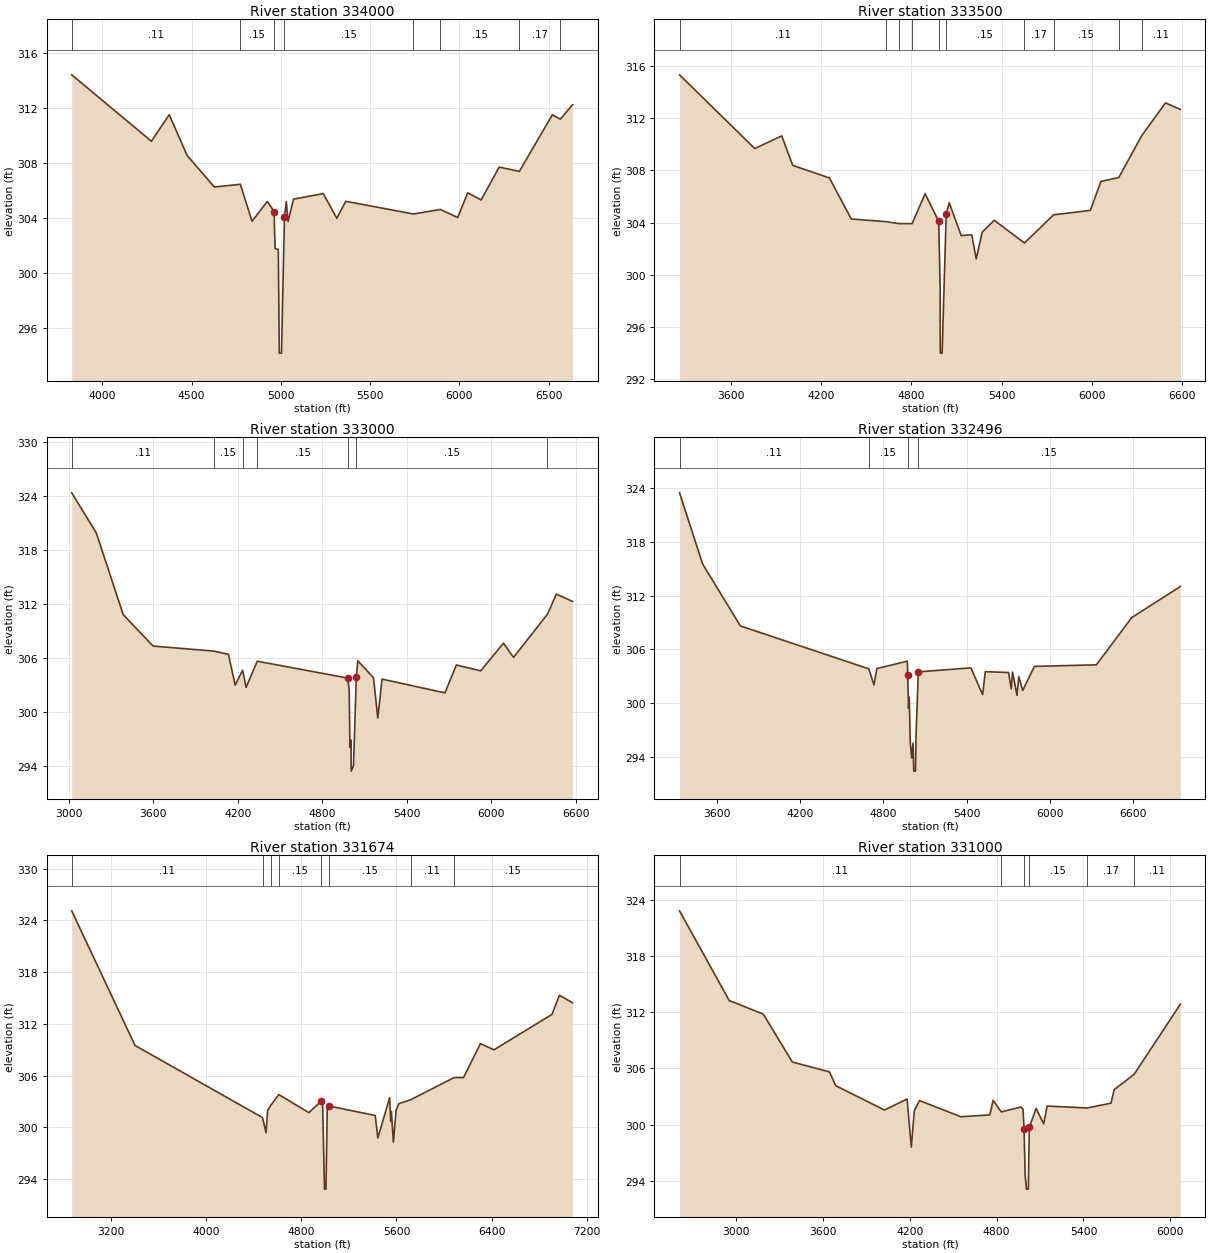
Type RM Length L Ch R = 1 ,334000  ,500,500,500
BEGIN DESCRIPTION:
LAKE CREEK 646.0
END DESCRIPTION:
XS GIS Cut Line= 3
      3701366.34     10214009.98      3700907.77     10212931.31
       3699291.4     10212689.18
#Sta/Elev= 30
  3827.9  314.41  4274.5  309.58  4374.5  311.51  4474.5  308.55  4627.3  306.25
  4772.9  306.45  4838.2  303.76  4924.2   305.2  4961.8  304.47  4967.7  301.78
  4985.5  301.71  4991.3  294.17  5003.5  294.17  5020.1  304.07  5030.3  305.19
  5040.4  303.74  5070.7  305.37  5237.7  305.77  5313.4  303.98  5363.9  305.21
    5743  304.29  5893.8  304.62  5990.9  304.03  6047.2  305.83  6122.3  305.31
  6223.4   307.7  6336.5  307.39    6521   311.5  6565.9  311.19  6634.4  312.23
#Mann= 8 ,-1 , 0
  3827.9     .11       0  4772.9     .15       0  4961.8     .09       0
  5020.1     .15       0    5743     .17       0  5893.8     .15       0
  6336.5     .17       0  6565.9     .11       0
Bank Sta=4961.8,5020.1
XS Rating Curve= 0 ,0
Exp/Cntr=0.3,0.1

Type RM Length L Ch R = 1 ,333500  ,500,500,500
BEGIN DESCRIPTION:
LAKE CREEK 645.0
END DESCRIPTION:
XS GIS Cut Line= 4
      3701479.19     10214070.74      3701089.49     10212701.98
      3700769.11      10212681.3      3699178.81     10212655.78
#Sta/Elev= 30
  3255.8  315.32  3756.7  309.67  3936.4  310.64  4009.3  308.38  4253.6  307.42
  4399.2  304.27  4629.6  304.07  4713.9  303.92  4804.1  303.91    4891  306.21
  4981.2  304.09  4991.2  298.93  4991.5  294.49    4992  293.99  5004.2  293.99
  5031.3  304.63  5051.3  305.52  5131.3     303  5201.3  303.06  5231.3  301.22
  5271.3  303.27  5351.3  304.17  5552.4  302.43  5746.1  304.59  5991.4  304.93
  6061.4  307.15  6180.4  307.45  6333.9  310.67  6491.4  313.17  6590.5  312.67
#Mann= 10 ,-1 , 0
  3255.8     .11       0  4629.6     .15       0  4713.9     .11       0
  4804.1     .15       0  4981.2     .09       0  5031.3     .15       0
  5552.4     .17       0  5746.1     .15       0  6180.4     .17       0
  6333.9     .11       0
Bank Sta=4981.2,5031.3
XS Rating Curve= 0 ,0
Exp/Cntr=0.3,0.1

Type RM Length L Ch R = 1 ,333000  ,504,504,504
BEGIN DESCRIPTION:
LAKE CREEK 644.0
END DESCRIPTION:
XS GIS Cut Line= 3
      3702720.54      10212603.7      3700759.28      10212335.6
      3699204.83      10212603.7
#Sta/Elev= 30
  3020.5  324.37  3194.8  319.93  3386.6  310.83  3598.6  307.35  4029.5  306.79
  4133.4  306.44  4181.6  303.01  4234.1  304.67  4258.9  302.76  4338.2  305.67
  4981.3  303.79  4991.3  302.37  4996.5   296.1  5004.6   296.9  5004.9  293.96
  5005.4  293.46  5021.7  294.06    5042  303.97  5052.2  305.72  5163.8  303.83
  5194.3  299.36  5224.7  303.68  5671.2  302.15  5752.4  305.25  5924.9   304.6
  6087.2  307.67  6158.3  306.09  6399.3  310.89  6462.7  313.12  6577.4  312.31
#Mann= 7 ,-1 , 0
  3020.5     .11       0  4029.5     .15       0  4234.1     .11       0
  4338.2     .15       0  4981.3     .09       0    5042     .15       0
  6399.3     .11       0
Bank Sta=4981.3,5042
XS Rating Curve= 0 ,0
Exp/Cntr=0.3,0.1

Type RM Length L Ch R = 1 ,332496  ,822,822,822
BEGIN DESCRIPTION:
LAKE CREEK 643.0
END DESCRIPTION:
XS GIS Cut Line= 3
      3702677.08     10212542.93      3700958.35     10212013.42
      3699213.55     10212499.53
#Sta/Elev= 30
  3331.7  323.48  3498.3  315.53  3770.4  308.62  4695.9  303.83    4733  302.04
    4754  303.86  4973.7  304.69 4976.11303.1839  4982.1  299.44  4987.3  300.68
  4994.6  295.64  5005.1  293.87  5014.8  295.53  5019.8  292.41  5032.2  292.41
  5036.5   296.5  5052.7  303.49  5431.7  303.94  5516.3  300.95  5535.5  303.51
  5702.9  303.42  5722.4  301.59  5731.9  303.47  5763.9  300.87  5776.5  302.95
  5805.4  301.42  5889.4   304.1  6336.2  304.28  6591.2  309.56  6941.4  313.02
#Mann= 4 ,-1 , 0
  3331.7     .11       0  4695.9     .15       0 4976.11     .09       0
  5052.7     .15       0
Bank Sta=4976.11,5052.7
XS Rating Curve= 0 ,0
Exp/Cntr=0.3,0.1

Type RM Length L Ch R = 1 ,331674  ,674,674,674
BEGIN DESCRIPTION:
LAKE CREEK 642.0
END DESCRIPTION:
XS GIS Cut Line= 3
      3702763.92     10212568.99      3701071.19     10211509.95
      3699067.84     10212461.08
#Sta/Elev= 30
  2867.3  325.11    3400   309.5  4473.4  301.13  4502.3  299.39  4516.5  301.98
  4547.6  302.65  4610.1   303.8    4863  301.71  4966.7  303.04  4978.4  302.85
  4994.4  292.84  5006.8  292.84  5017.7  302.38  5033.8  302.47  5421.2  301.38
  5443.4  298.77    5543  303.45  5551.5  300.72    5557  301.86  5574.2  298.29
    5597  301.98  5619.7  302.75  5720.2  303.21  6084.4  305.77  6164.6  305.78
  6306.8  309.72  6420.1  308.99  6908.5   313.1    6971  315.32  7081.7  314.45
#Mann= 8 ,-1 , 0
  2867.3     .11       0  4473.4     .15       0  4547.6     .11       0
  4610.1     .15       0  4966.7     .09       0  5033.8     .15       0
  5720.2     .11       0  6084.4     .15       0
Bank Sta=4966.7,5033.8
XS Rating Curve= 0 ,0
Exp/Cntr=0.3,0.1

Type RM Length L Ch R = 1 ,331000  ,500,500,500
BEGIN DESCRIPTION:
LAKE CREEK 640.0
END DESCRIPTION:
XS GIS Cut Line= 3
      3702717.88     10212461.09      3700799.76     10211035.12
      3699817.82     10210611.06
#Sta/Elev= 30
  2609.9  322.82  2953.1  313.25  3188.8   311.8    3389  306.69  3645.6  305.64
  3689.4  304.16  4025.2  301.57  4181.7  302.74  4210.9  297.61  4231.7  301.48
  4267.2  302.58  4553.8  300.85  4753.2  301.05  4776.2   302.6  4832.1  301.37
  4968.1  301.89  4982.7  301.66  4989.9  299.53  4997.3  294.61  5006.6  293.13
  5019.3  293.13  5026.1  299.72  5073.1  301.74  5125.5   300.1    5149  301.99
  5426.5  301.79  5590.3   302.3  5612.1  303.74  5749.7  305.37  6069.6  312.86
#Mann= 6 ,-1 , 0
  2609.9     .11       0  4832.1     .15       0  4989.9     .09       0
  5026.1     .15       0  5426.5     .17       0  5749.7     .11       0
Bank Sta=4989.9,5026.1
XS Rating Curve= 0 ,0
Exp/Cntr=0.3,0.1

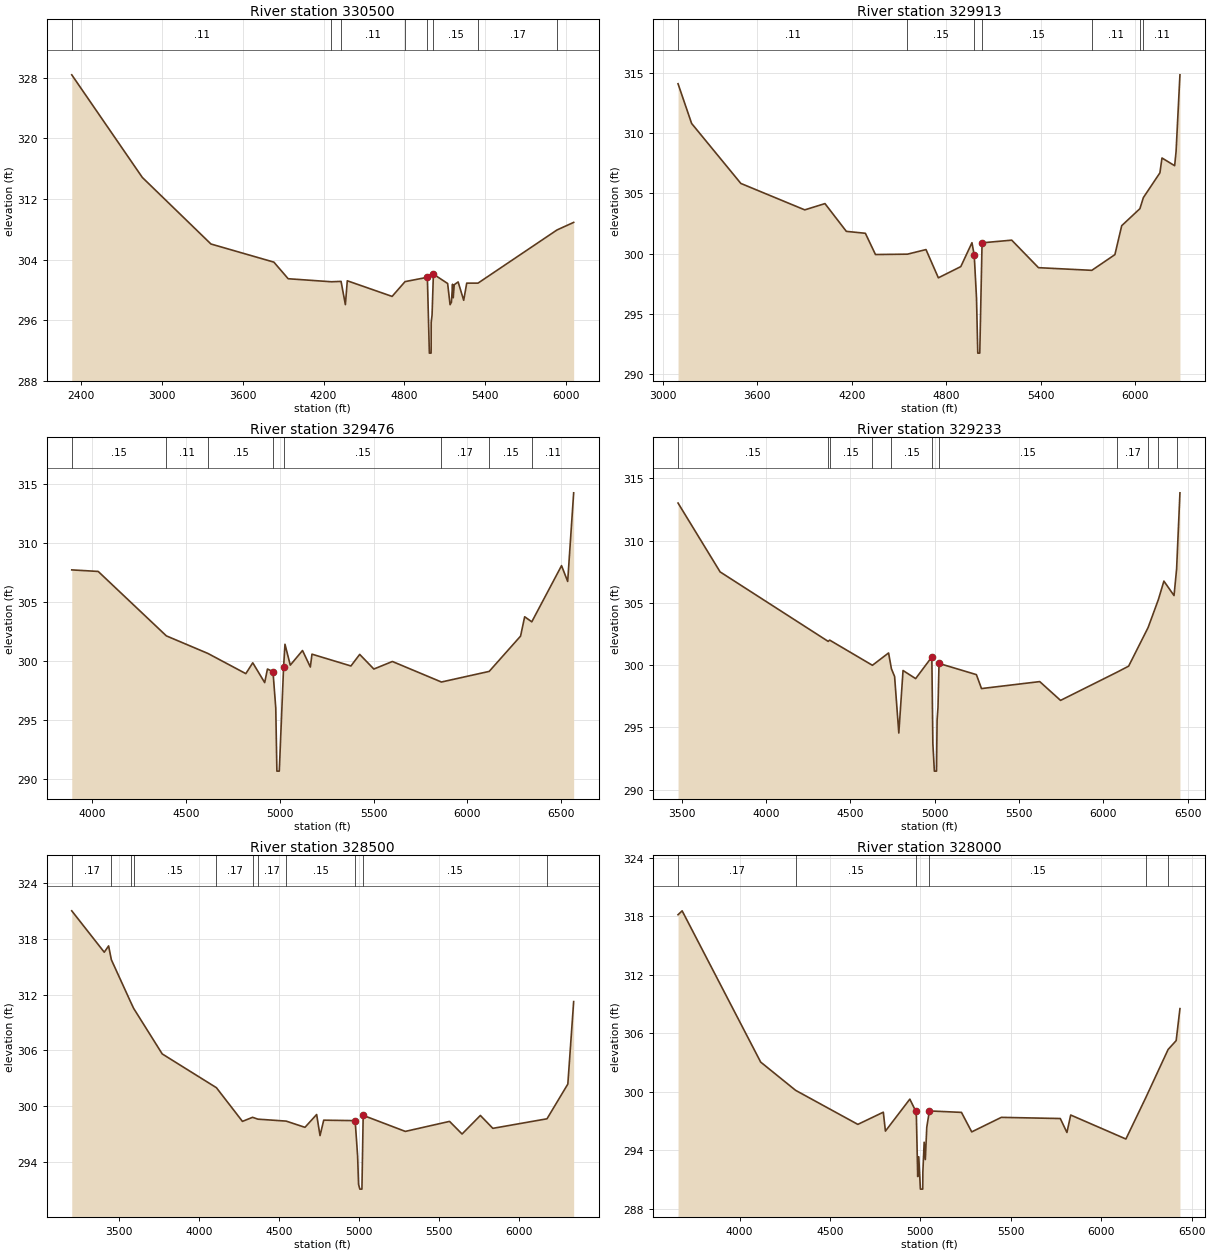
Type RM Length L Ch R = 1 ,330500  ,587,587,587
BEGIN DESCRIPTION:
LAKE CREEK 639.0
END DESCRIPTION:
XS GIS Cut Line= 3
      3702867.88      10212561.1       3700992.1     10210664.39
      3699967.86     10210411.07
#Sta/Elev= 30
  2332.4  328.36  2855.7  314.83  3364.8  306.05  3831.5  303.66  3937.6  301.47
  4258.7  301.07  4329.9  301.12  4361.9  298.05    4376   301.2  4708.4  299.14
  4804.5  301.09    4970  301.66  4984.8  291.66  4997.5  291.66    4998  292.16
  4998.3   295.7  5004.8  296.68  5014.7  302.08  5120.4  300.84  5138.3  298.05
  5148.6  298.38  5156.7  300.75  5161.8  298.96  5169.2  300.68  5198.1  301.05
  5239.5  298.63  5261.9  300.89  5345.6  300.89  5931.2   307.9  6055.1   308.9
#Mann= 8 ,-1 , 0
  2332.4     .11       0  4258.7     .15       0  4329.9     .11       0
  4804.5     .15       0    4970     .09       0  5014.7     .15       0
  5345.6     .17       0  5931.2     .11       0
Bank Sta=4970,5014.7
XS Rating Curve= 0 ,0
Exp/Cntr=0.3,0.1

Type RM Length L Ch R = 1 ,329913  ,437,437,437
BEGIN DESCRIPTION:
LAKE CREEK 638.0
END DESCRIPTION:
XS GIS Cut Line= 3
      3702659.76     10211909.28      3701418.42     10210338.07
      3700388.54     10209755.57
#Sta/Elev= 30
  3097.6  314.07  3183.8  310.78  3496.3  305.81  3901.9  303.62  4030.1  304.14
  4165.8  301.84  4286.6  301.68  4350.7  299.92  4553.7  299.95  4671.3  300.33
  4749.9  297.99  4892.3  298.92  4963.1   300.9  4977.5  299.87    4992  296.31
    5000  291.75  5012.7  291.75  5027.2  300.89  5215.5  301.11  5385.3  298.83
  5723.8  298.61  5870.3  299.91  5913.6  302.31    6029  303.72  6051.1  304.64
  6156.1  306.69  6169.1  307.92  6249.5  307.28  6258.6  308.45  6283.2  314.81
#Mann= 7 ,-1 , 0
  3097.6     .11       0  4553.7     .15       0  4977.5     .09       0
  5027.2     .15       0  5723.8     .11       0    6029     .15       0
  6051.1     .11       0
Bank Sta=4977.5,5027.2
XS Rating Curve= 0 ,0
Exp/Cntr=0.3,0.1

Type RM Length L Ch R = 1 ,329476  ,243,243,243
BEGIN DESCRIPTION:
LAKE CREEK 637.0
END DESCRIPTION:
XS GIS Cut Line= 3
      3702763.93     10210980.46      3701678.83     10210207.86
      3700448.68     10209666.62
#Sta/Elev= 30
  3890.8  307.72  4031.7  307.59  4395.1  302.13  4616.8  300.64  4818.9  298.93
  4855.8  299.85  4919.4  298.17  4934.2  299.32  4963.7   299.1  4978.5  296.02
  4984.5  290.67  4997.2  290.67  5020.3  299.51  5027.6  301.42  5055.9  299.65
  5121.1  300.89  5162.9  299.49  5171.5  300.58  5379.3  299.58    5426  300.56
  5501.5  299.32  5600.3  299.96  5861.7  298.22  6116.4  299.12  6283.7  302.11
  6305.5  303.75  6343.5  303.32  6502.2  308.08  6534.9  306.74  6566.8  314.25
#Mann= 8 ,-1 , 0
  3890.8     .15       0  4395.1     .11       0  4616.8     .15       0
  4963.7     .09       0  5020.3     .15       0  5861.7     .17       0
  6116.4     .15       0  6343.5     .11       0
Bank Sta=4963.7,5020.3
XS Rating Curve= 0 ,0
Exp/Cntr=0.3,0.1

Type RM Length L Ch R = 1 ,329233  ,733,733,733
BEGIN DESCRIPTION:
LAKE CREEK 636.0
END DESCRIPTION:
XS GIS Cut Line= 3
      3703319.41     10210641.88      3701774.32     10210068.97
      3700582.53     10209479.93
#Sta/Elev= 30
  3477.7  313.01  3727.3  307.48  4368.3   301.9  4377.4     302  4630.7  299.98
  4726.6  300.97  4743.5   299.7  4762.3  299.08  4787.3  294.54  4812.4  299.56
  4887.2  298.91  4983.2  300.65  4989.3   293.7  4998.2  291.48  5010.9  291.48
  5014.4  295.58  5019.7  296.59  5025.8  300.13  5247.5  299.23  5277.8  298.11
  5623.3  298.67  5746.7  297.16  6082.4  299.43  6150.6  299.91  6266.1  303.01
  6327.1  305.26  6359.8  306.74  6419.9  305.58  6435.2  307.71    6455  313.83
#Mann= 11 ,-1 , 0
  3477.7     .15       0  4368.3     .11       0  4377.4     .15       0
  4630.7     .17       0  4743.5     .15       0  4983.2     .09       0
  5025.8     .15       0  6082.4     .17       0  6266.1     .11       0
  6327.1     .17       0  6435.2     .11       0
Bank Sta=4983.2,5025.8
XS Rating Curve= 0 ,0
Exp/Cntr=0.3,0.1

Type RM Length L Ch R = 1 ,328500  ,500,500,500
BEGIN DESCRIPTION:
LAKE CREEK 635.0
END DESCRIPTION:
XS GIS Cut Line= 3
      3703640.64     10210546.41      3702121.14     10209594.02
      3701089.43     10208739.09
#Sta/Elev= 30
  3206.7  321.04  3409.6  316.58  3436.7  317.26  3453.9  315.77  3574.5  311.21
    3593  310.53  3771.4  305.62  4109.7  301.98  4272.2  298.35  4335.5  298.79
  4368.5  298.59  4545.2  298.38  4662.4  297.71  4735.4  299.09  4756.6  296.82
  4779.6  298.48  4975.8  298.43  4991.2  294.61  4997.1  291.56  5005.2  291.05
  5018.1  291.05  5025.9     299    5289  297.27  5565.1  298.35  5643.2  296.99
  5757.5  298.99  5835.4   297.6  6173.5  298.63  6303.5  302.37  6339.9  311.26
#Mann= 11 ,-1 , 0
  3206.7     .17       0  3453.9     .15       0  3574.5     .17       0
    3593     .15       0  4109.7     .17       0  4335.5     .15       0
  4368.5     .17       0  4545.2     .15       0  4975.8     .09       0
  5025.9     .15       0  6173.5     .11       0
Bank Sta=4975.8,5025.9
XS Rating Curve= 0 ,0
Exp/Cntr=0.3,0.1

Type RM Length L Ch R = 1 ,328000  ,406,406,406
BEGIN DESCRIPTION:
LAKE CREEK 634.0
END DESCRIPTION:
XS GIS Cut Line= 3
        3703632.     10209947.47      3702458.23     10209299.61
      3701343.05     10208395.86
#Sta/Elev= 30
  3659.3  318.15    3682  318.55  4116.3  303.04  4309.7  300.14  4653.8  296.65
  4794.7   297.9  4806.3  295.96  4941.4  299.24  4973.1298.0438  4977.6  297.48
    4985   291.3  4990.7  293.33  4999.8  290.01  5012.7  290.01  5013.4  291.75
  5020.6  294.82  5027.1  293.04    5035  296.34  5049.4  298.03  5226.9  297.88
  5283.7  295.88  5447.4  297.37  5773.6  297.25  5810.3  295.82  5831.1  297.61
  6136.5  295.15  6246.9  299.41  6369.9  304.33  6414.5  305.24  6435.4  308.52
#Mann= 6 ,-1 , 0
  3659.3     .17       0  4309.7     .15       0  4973.1     .09       0
  5049.4     .15       0  6246.9     .11       0  6369.9     .17       0
Bank Sta=4973.1,5049.4
XS Rating Curve= 0 ,0
Exp/Cntr=0.3,0.1