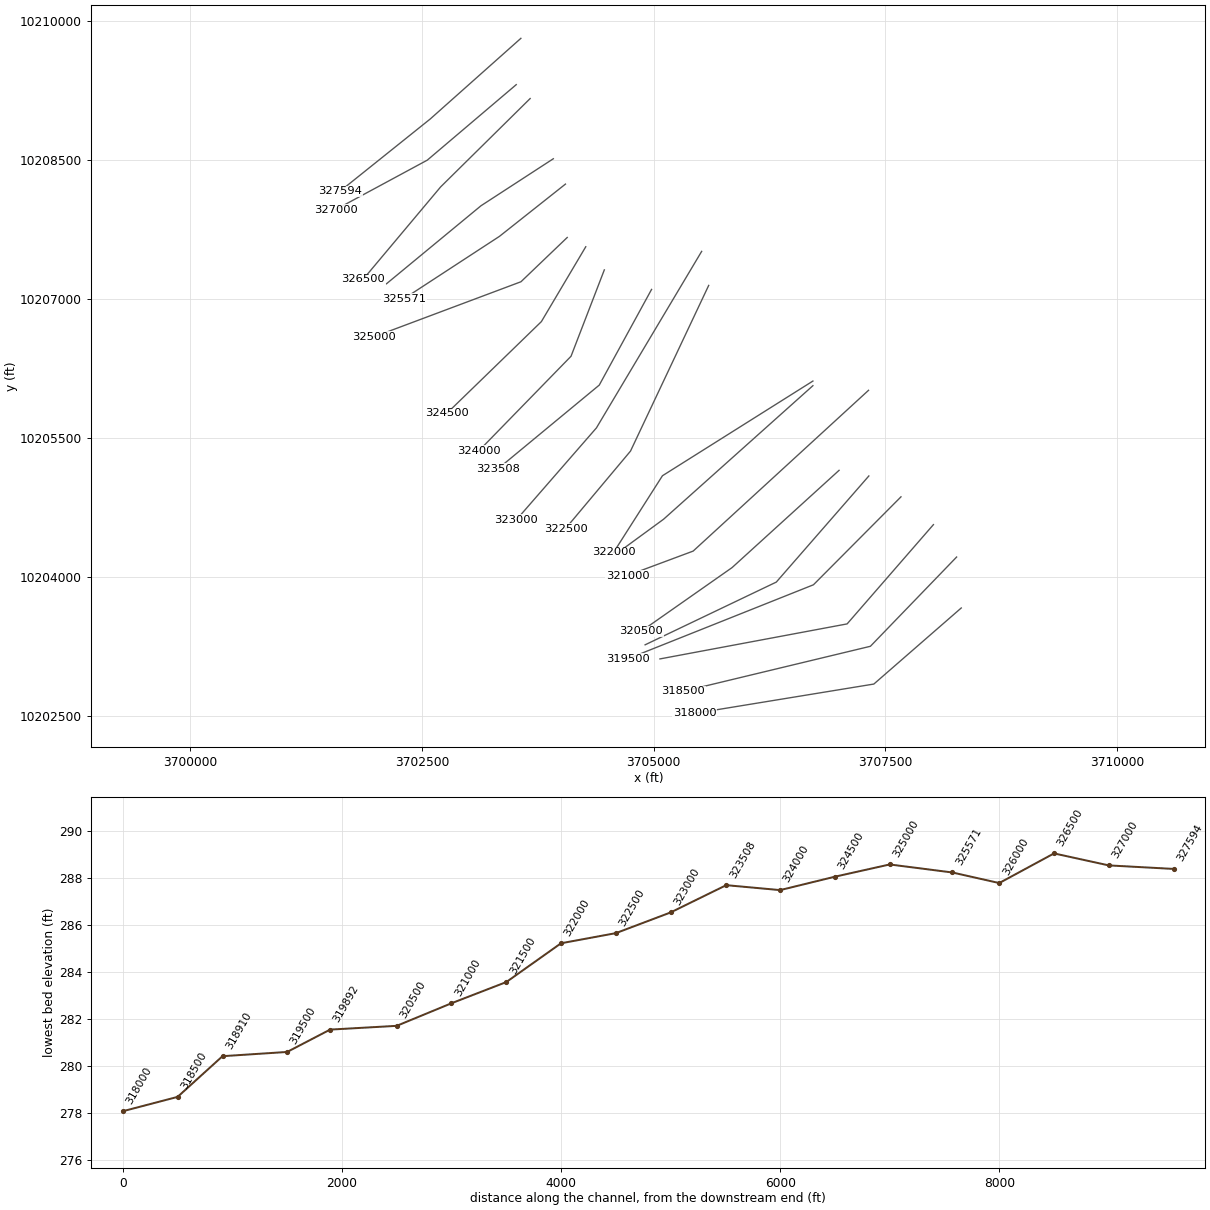
HEC-RAS study LAKE CREEK.prj: LAKE CREEK Base Level Engineering

--- LAKE CREEK.g01 (geometry) --- (continued)

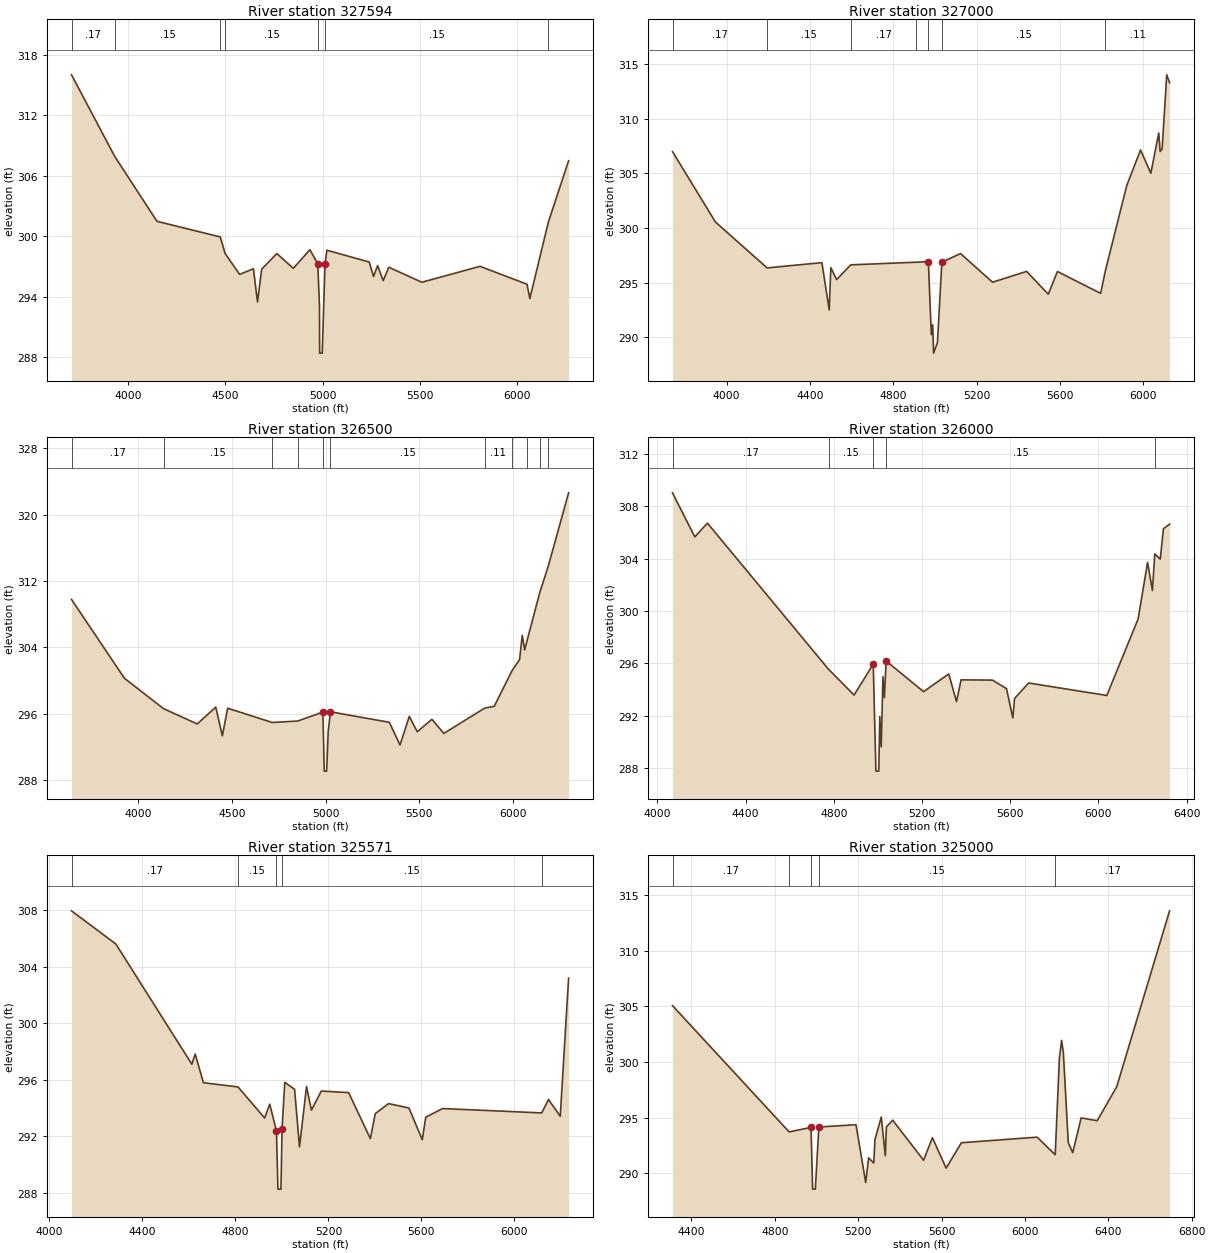
Type RM Length L Ch R = 1 ,327594  ,594,594,594
BEGIN DESCRIPTION:
LAKE CREEK 633.0
END DESCRIPTION:
XS GIS Cut Line= 3
      3703567.88     10209811.09      3702590.29      10208940.5
      3701617.85     10208161.07
#Sta/Elev= 30
  3708.6  316.03  3930.6  307.93    4148  301.48  4473.3  299.93  4498.2  298.28
  4572.8  296.21  4643.8  296.77  4664.7  293.47  4686.1  296.73  4764.2  298.28
  4848.7  296.81    4934  298.66 4974.35 297.273  4983.3   293.1  4983.9  288.89
  4984.4  288.39  4997.3  288.39  5011.7  297.21  5021.2  298.61  5238.8  297.44
  5261.2     296    5282  297.08  5310.8  295.59  5339.6  296.92  5509.3  295.43
  5808.6  297.01  6050.2  295.23  6064.6  293.81  6159.9  301.41  6263.9   307.5
#Mann= 7 ,-1 , 0
  3708.6     .17       0  3930.6     .15       0  4473.3     .17       0
  4498.2     .15       0 4974.35     .09       0  5011.7     .15       0
  6159.9     .11       0
Bank Sta=4974.35,5011.7
XS Rating Curve= 0 ,0
Exp/Cntr=0.3,0.1

Type RM Length L Ch R = 1 ,327000  ,500,500,500
BEGIN DESCRIPTION:
LAKE CREEK 632.0
END DESCRIPTION:
XS GIS Cut Line= 3
      3703517.88     10209311.09       3702558.2     10208495.86
      3701567.87     10207961.08
#Sta/Elev= 30
  3740.8  306.98  3946.8  300.54  4194.7  296.34  4457.5  296.82  4492.6   292.5
  4500.4  296.36  4528.1  295.27    4596  296.62  4909.2  296.86  4968.2  296.92
  4982.5  290.23  4989.1  291.13  4993.4  288.54  5011.8  289.51 5032.98296.8673
  5122.8  297.65    5276  295.03  5439.7  296.02  5543.5  293.93  5587.3  296.01
  5794.8  294.01    5818  296.13  5920.4   303.9  5986.1  307.13  6035.5     305
  6073.6  308.69  6080.1     307  6089.8  307.24  6111.7  314.01  6125.5  313.29
#Mann= 7 ,-1 , 0
  3740.8     .17       0  4194.7     .15       0    4596     .17       0
  4909.2     .15       0  4968.2     .09       0 5032.98     .15       0
    5818     .11       0
Bank Sta=4968.2,5032.98
XS Rating Curve= 0 ,0
Exp/Cntr=0.3,0.1

Type RM Length L Ch R = 1 ,326500  ,500,500,500
BEGIN DESCRIPTION:
LAKE CREEK 631.0
END DESCRIPTION:
XS GIS Cut Line= 3
      3703667.88      10209161.1      3702702.34     10208207.03
      3701867.88     10207211.11
#Sta/Elev= 30
  3642.6  309.76  3925.5  300.25  4134.8  296.58  4314.4  294.74  4413.4  296.77
  4448.7  293.31    4477  296.64  4715.2  294.92  4850.8  295.09  4986.2  296.17
  4993.2  289.05  5006.1  289.05  5014.5  293.84 5026.46 296.207  5341.1  294.94
  5398.3  292.21  5447.8  295.65  5490.5   293.8  5568.8   295.3  5632.5   293.6
  5850.7  296.65  5901.9  296.87  5997.6  301.19  6037.2   302.5  6051.5  305.43
  6064.5  303.67  6078.9  304.93  6144.5  310.53  6190.7  313.78  6299.3  322.62
#Mann= 11 ,-1 , 0
  3642.6     .17       0  4134.8     .15       0  4715.2     .17       0
  4850.8     .15       0  4986.2     .09       0 5026.46     .15       0
  5850.7     .11       0  5997.6     .17       0  6078.9     .11       0
  6144.5     .17       0  6190.7     .11       0
Bank Sta=4986.2,5026.46
XS Rating Curve= 0 ,0
Exp/Cntr=0.3,0.1

Type RM Length L Ch R = 1 ,326000  ,429,429,429
BEGIN DESCRIPTION:
LAKE CREEK 630.0
END DESCRIPTION:
XS GIS Cut Line= 3
      3703917.81     10208511.05      3703137.25     10208003.25
      3702117.84     10207161.06
#Sta/Elev= 30
  4068.8  309.01  4169.9  305.65  4227.2   306.7    4776  295.56  4891.9  293.59
  4978.9  295.95  4990.9  287.79  5003.9  287.79  5008.5  291.95    5015  289.65
  5022.8  294.99  5029.3  293.39  5037.2  296.19  5206.8  293.85  5321.2   295.2
  5356.3  293.09  5377.1  294.75  5519.1  294.73    5583  294.08  5611.6  291.85
  5619.5  293.33  5683.3  294.51  6037.6  293.56  6179.6  299.39  6222.6  303.71
  6244.5  301.56  6255.2  304.35    6280  303.95  6294.3  306.27  6322.3  306.62
#Mann= 5 ,-1 , 0
  4068.8     .17       0    4776     .15       0  4978.9     .09       0
  5037.2     .15       0  6255.2     .11       0
Bank Sta=4978.9,5037.2
XS Rating Curve= 0 ,0
Exp/Cntr=0.3,0.1

Type RM Length L Ch R = 1 ,325571  ,571,571,571
BEGIN DESCRIPTION:
LAKE CREEK 629.0
END DESCRIPTION:
XS GIS Cut Line= 3
      3704048.62     10208237.38      3703336.82     10207673.14
       3702307.7     10207000.78
#Sta/Elev= 30
  4095.3  307.96  4285.9  305.61  4612.8  297.09  4627.2  297.81  4662.5  295.78
  4811.4  295.48  4925.7  293.28  4947.7  294.26  4976.6  292.36    4983  288.24
    4996  288.24 5000.57292.4992  5012.4  295.81  5054.6  295.31  5075.7  291.24
  5105.9  295.51    5127  293.84  5169.6  295.19  5286.9  295.08  5380.4  291.82
  5401.5  293.59  5458.8   294.3  5546.3  293.99  5603.6  291.74  5618.7  293.34
  5691.1  293.95  6117.2  293.64  6146.6  294.59  6196.9   293.4  6232.9  303.19
#Mann= 5 ,-1 , 0
  4095.3     .17       0  4811.4     .15       0  4976.6     .09       0
 5000.57     .15       0  6117.2     .11       0
Bank Sta=4976.6,5000.57
XS Rating Curve= 0 ,0
Exp/Cntr=0.3,0.1

Type RM Length L Ch R = 1 ,325000  ,500,500,500
BEGIN DESCRIPTION:
LAKE CREEK 628.0
END DESCRIPTION:
XS GIS Cut Line= 3
      3704067.82     10207661.04      3703568.88     10207183.13
      3701982.72      10206588.1
#Sta/Elev= 30
  4309.1  305.07  4868.7  293.72  4973.7  294.13  4981.4  288.58  4994.4  288.58
 5011.25294.1615  5189.5  294.37  5236.1  289.17    5250  291.39  5274.9  290.92
  5280.2  293.01  5310.8  295.06  5330.1  291.59  5335.4  294.18  5365.7  294.77
  5513.8  291.18  5556.1   293.2  5621.9  290.47  5695.3  292.75  6058.5  293.25
  6145.3  291.67  6165.3  300.34    6176  301.95  6184.3  300.89    6208  292.76
  6229.4  291.86  6269.8  294.98  6346.8  294.73  6440.6  297.79  6694.1  313.59
#Mann= 5 ,-1 , 0
  4309.1     .17       0  4868.7     .15       0  4973.7     .09       0
 5011.25     .15       0  6145.3     .17       0
Bank Sta=4973.7,5011.25
XS Rating Curve= 0 ,0
Exp/Cntr=0.3,0.1

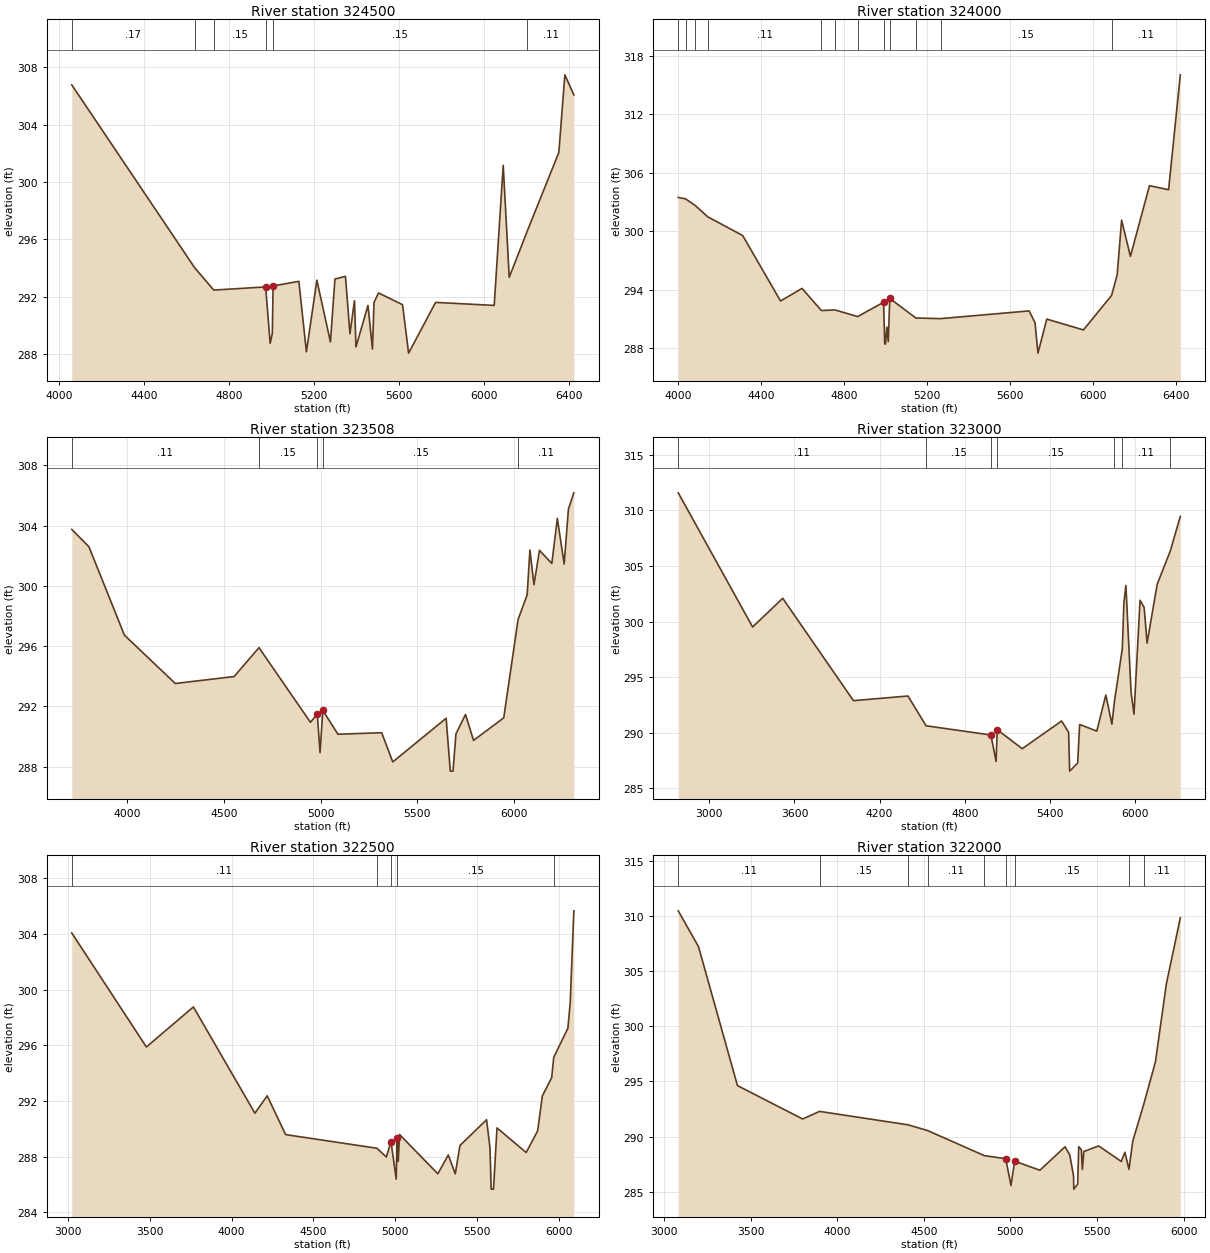
Type RM Length L Ch R = 1 ,324500  ,500,500,500
BEGIN DESCRIPTION:
LAKE CREEK 627.0
END DESCRIPTION:
XS GIS Cut Line= 3
      3704267.85     10207561.07      3703788.96     10206752.66
      3702767.89      10205761.1
#Sta/Elev= 30
  4060.4  306.78  4639.2  294.01  4728.7  292.46  4972.8  292.68  4994.2  288.74
  5004.3  289.44 5007.84  292.75  5129.1  293.07  5164.6  288.15    5214  293.15
  5277.8  288.84  5298.9  293.23  5348.5  293.42  5369.6  289.41  5390.9  291.72
  5397.9  288.49  5454.5  291.39  5475.6  288.34  5482.8  291.59  5503.9  292.26
  5617.1  291.44  5645.6  288.06  5772.7   291.6  6048.5  291.39  6090.9  301.16
  6119.2  293.35  6204.7   296.6  6352.7  302.06    6381  307.48  6423.3  306.08
#Mann= 6 ,-1 , 0
  4060.4     .17       0  4639.2     .11       0  4728.7     .15       0
  4972.8     .09       0 5007.84     .15       0  6204.7     .11       0
Bank Sta=4972.8,5007.84
XS Rating Curve= 0 ,0
Exp/Cntr=0.3,0.1

Type RM Length L Ch R = 1 ,324000  ,492,492,492
BEGIN DESCRIPTION:
LAKE CREEK 626.0
END DESCRIPTION:
XS GIS Cut Line= 3
      3704467.86      10207311.1      3704108.89     10206378.83
      3703117.82     10205361.04
#Sta/Elev= 30
    4001  303.46  4036.1  303.32    4082  302.65    4143  301.48  4311.8  299.55
    4494  292.84  4597.6  294.13  4690.8  291.86  4756.3  291.92  4865.7  291.24
  4990.6  292.71  4996.1  288.43    5000  288.43  5006.3  290.17  5013.2  288.68
  5020.4   293.1  5146.5  291.09  5265.1  291.03  5692.2  291.82  5720.5   290.6
  5734.6  287.49  5777.1  290.98  5953.8  289.87  6089.4  293.41  6116.4  295.51
  6137.7  301.13  6180.2  297.42    6272  304.67  6364.1  304.25  6420.6  316.04
#Mann= 12 ,-1 , 0
    4001     .17       0  4036.1     .11       0    4082     .17       0
    4143     .11       0  4690.8     .15       0  4756.3     .11       0
  4865.7     .15       0  4990.6     .09       0  5020.4     .15       0
  5146.5     .17       0  5265.1     .15       0  6089.4     .11       0
Bank Sta=4990.6,5020.4
XS Rating Curve= 0 ,0
Exp/Cntr=0.3,0.1

Type RM Length L Ch R = 1 ,323508  ,508,508,508
BEGIN DESCRIPTION:
LAKE CREEK 625.0
END DESCRIPTION:
XS GIS Cut Line= 3
      3704977.44     10207100.22      3704413.21     10206067.24
      3703317.88     10205161.09
#Sta/Elev= 30
  3712.6  303.75  3801.4   302.6  3985.1  296.73  4248.3  293.52  4552.9  293.98
  4681.5   295.9  4948.1  290.94  4983.3   291.5  4997.6  288.93  5011.9  291.74
  5090.1  290.15  5316.7  290.25    5374  288.31  5650.2  291.21  5671.8   287.7
  5685.8   287.7    5701  290.17  5750.5  291.46  5792.1  289.74  5948.4  291.24
  6022.5  297.76  6069.6  299.41  6083.9  302.38  6104.8  300.08  6133.4  302.36
  6197.2  301.49  6225.9  304.48  6261.1  301.45  6283.2   305.1  6311.2  306.18
#Mann= 5 ,-1 , 0
  3712.6     .11       0  4681.5     .15       0  4983.3     .09       0
  5011.9     .15       0  6022.5     .11       0
Bank Sta=4983.3,5011.9
XS Rating Curve= 0 ,0
Exp/Cntr=0.3,0.1

Type RM Length L Ch R = 1 ,323000  ,500,500,500
BEGIN DESCRIPTION:
LAKE CREEK 624.0
END DESCRIPTION:
XS GIS Cut Line= 3
      3705517.88     10207511.11      3704382.79     10205605.22
      3703517.88      10204611.1
#Sta/Elev= 30
  2781.7  311.58  3305.5  299.51  3517.7  302.09  4015.5  292.88  4399.7   293.3
  4527.2  290.62  4983.9  289.79  5020.3  287.41  5027.9  290.27  5204.5  288.56
  5481.7  291.05  5531.1  290.03  5538.3  286.54  5594.7  287.26    5609  290.74
  5729.5  290.14  5793.2  293.39  5835.9  290.76  5853.5  292.78    5909  297.53
  5920.4  301.68  5934.6  303.25  5970.7  293.66  5991.6  291.67  6034.3  301.91
  6062.8  301.27  6083.7  298.06  6154.9  303.35  6247.5  306.36  6317.7  309.46
#Mann= 7 ,-1 , 0
  2781.7     .11       0  4527.2     .15       0  4983.9     .09       0
  5027.9     .15       0  5853.5     .17       0    5909     .11       0
  6247.5     .15       0
Bank Sta=4983.9,5027.9
XS Rating Curve= 0 ,0
Exp/Cntr=0.3,0.1

Type RM Length L Ch R = 1 ,322500  ,500,500,500
BEGIN DESCRIPTION:
LAKE CREEK 623.0
END DESCRIPTION:
XS GIS Cut Line= 3
      3705593.76     10207143.63      3704750.44     10205354.96
      3704049.46     10204518.18
#Sta/Elev= 30
  3022.5  304.08  3478.6  295.88  3766.1  298.76    4142  291.12  4217.2  292.37
  4329.9  289.58  4887.9   288.6  4945.5  287.97  4973.8  289.08  5005.8  286.38
  5011.7  289.36  5018.2  287.65    5026  289.59  5260.2  286.76    5324  288.12
  5366.9  286.76  5395.5   288.8  5558.2  290.65  5579.1  288.61  5586.2  285.66
  5600.4  285.66  5621.9  290.06  5800.2  288.29  5870.4  289.85  5899.1  292.36
  5956.3  293.68  5968.6  295.13  6055.2  297.23  6069.5  299.07  6091.6  305.67
#Mann= 5 ,-1 , 0
  3022.5     .11       0  4887.9     .15       0  4973.8     .09       0
  5011.7     .15       0  5968.6     .11       0
Bank Sta=4973.8,5011.7
XS Rating Curve= 0 ,0
Exp/Cntr=0.3,0.1

Type RM Length L Ch R = 1 ,322000  ,500,500,500
BEGIN DESCRIPTION:
LAKE CREEK 622.0
END DESCRIPTION:
XS GIS Cut Line= 3
      3706717.84     10206111.06      3705094.92      10205088.7
      3704567.85     10204261.07
#Sta/Elev= 30
  3081.9  310.47    3199  307.22  3423.8  294.62  3800.6  291.59  3897.9  292.28
  4409.9  291.06  4522.2  290.54    4849  288.27  4973.1  287.99  5003.5  285.56
  5024.6  287.77  5170.2  286.94  5315.8  289.07  5342.9  288.33  5364.7  286.43
    5366  285.23  5388.4  285.68  5394.6  289.08  5409.8   288.8  5415.7  287.02
    5424  288.64  5509.7  289.15  5640.1  287.74  5661.2  288.57  5684.7  287.03
  5706.9   289.6  5772.3  293.05  5837.3  296.76  5900.8  303.85  5981.2  309.83
#Mann= 9 ,-1 , 0
  3081.9     .11       0  3897.9     .15       0  4409.9     .17       0
  4522.2     .11       0    4849     .15       0  4973.1     .09       0
  5024.6     .15       0  5684.7     .17       0  5772.3     .11       0
Bank Sta=4973.1,5024.6
XS Rating Curve= 0 ,0
Exp/Cntr=0.3,0.1

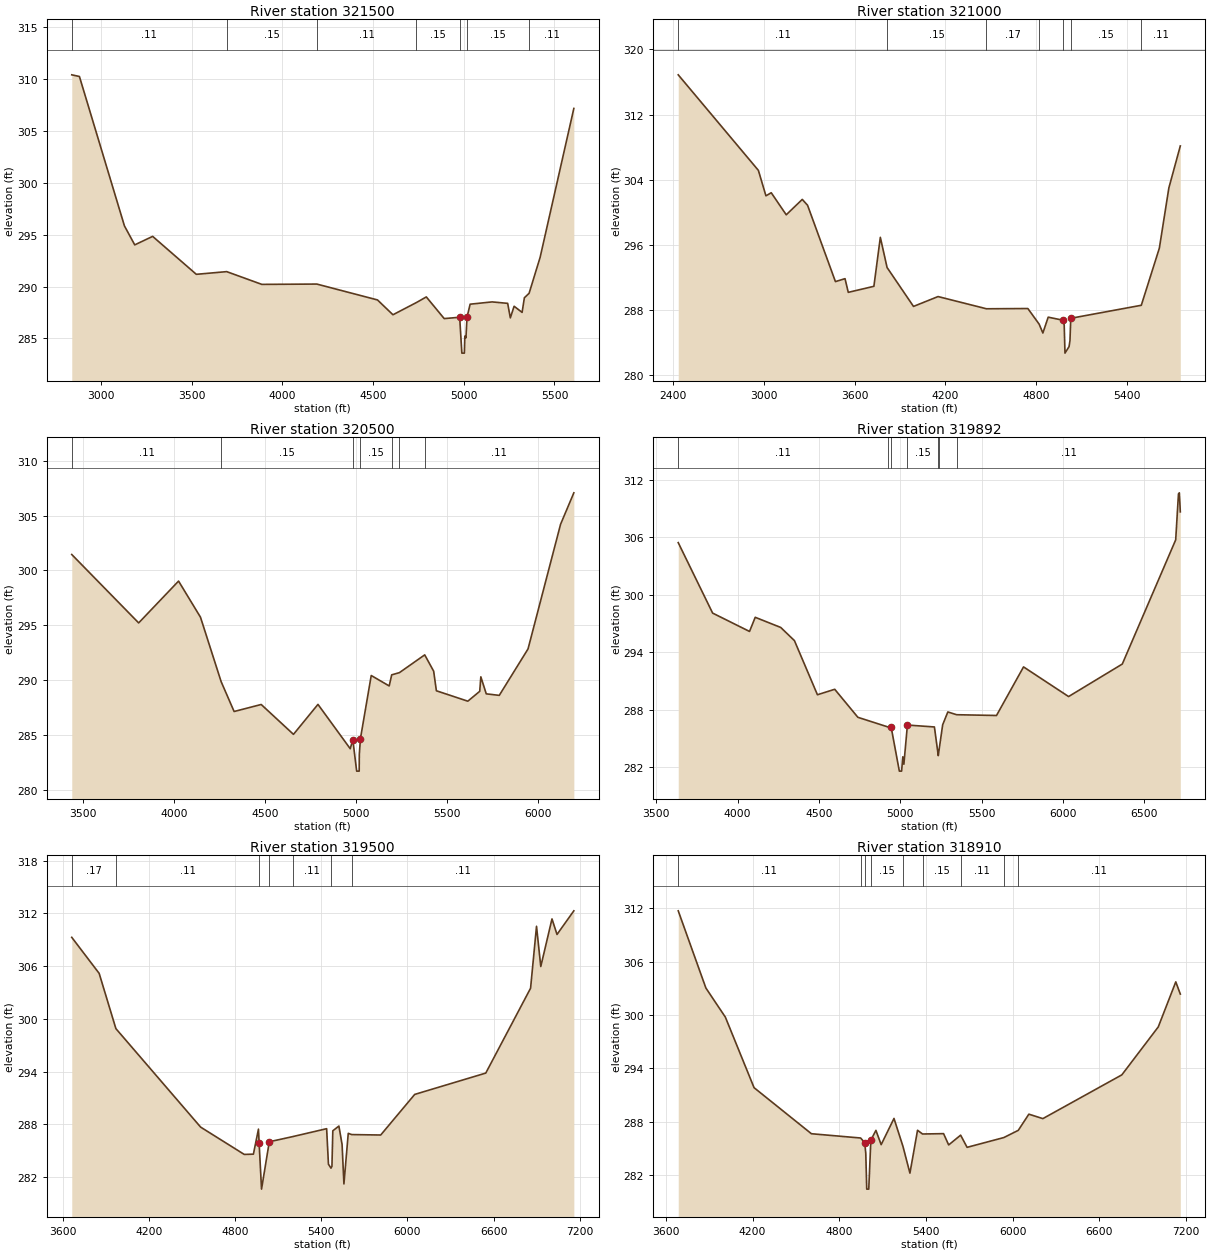
Type RM Length L Ch R = 1 ,321500  ,500,500,500
BEGIN DESCRIPTION:
LAKE CREEK 621.0
END DESCRIPTION:
XS GIS Cut Line= 3
      3706717.82     10206061.04      3705107.51     10204619.62
      3704617.85     10204261.07
#Sta/Elev= 30
  2838.8  310.42    2881  310.26  3129.2  295.85    3186  294.02  3284.7  294.84
  3525.5  291.18  3692.9  291.44  3886.6  290.21  4189.9  290.24  4524.3  288.71
  4609.6  287.28  4739.2  288.46  4793.5     289  4892.2  286.91  4977.4  287.04
  4989.5  283.58  5003.3  283.58  5005.9  285.22  5012.1  285.06 5018.01287.0554
  5035.2   288.3  5156.4  288.52  5242.1  288.38  5256.8  286.98  5277.6   288.1
  5321.6  287.51  5334.2  288.92  5360.2  289.35    5421  292.82  5606.9  307.18
#Mann= 7 ,-1 , 0
  2838.8     .11       0  3692.9     .15       0  4189.9     .11       0
  4739.2     .15       0  4977.4     .09       0 5018.01     .15       0
  5360.2     .11       0
Bank Sta=4977.4,5018.01
XS Rating Curve= 0 ,0
Exp/Cntr=0.3,0.1

Type RM Length L Ch R = 1 ,321000  ,500,500,500
BEGIN DESCRIPTION:
LAKE CREEK 620.0
END DESCRIPTION:
XS GIS Cut Line= 3
      3707317.82     10206011.04      3705426.05     10204275.16
      3704717.89     10204011.09
#Sta/Elev= 30
  2432.5  316.88    2963  305.14    3013  302.01  3048.1  302.39  3147.4  299.68
  3253.5  301.57  3288.6  300.85    3473  291.47  3536.5  291.83    3558  290.15
  3727.6  290.89  3770.2  296.91  3814.9   293.2  3989.7  288.42  4152.4  289.63
  4472.8  288.13  4746.8  288.16  4821.5  286.24  4846.1  285.15  4881.3   287.1
  4980.5  286.72  4987.3  286.12  4992.4  282.68  5019.4  283.48  5025.4  284.21
  5030.7  286.96  5497.6  288.56  5617.1  295.58    5680  302.98  5755.8  308.14
#Mann= 7 ,-1 , 0
  2432.5     .11       0  3814.9     .15       0  4472.8     .17       0
  4821.5     .15       0  4980.5     .09       0  5030.7     .15       0
  5497.6     .11       0
Bank Sta=4980.5,5030.7
XS Rating Curve= 0 ,0
Exp/Cntr=0.3,0.1

Type RM Length L Ch R = 1 ,320500  ,608,608,608
BEGIN DESCRIPTION:
LAKE CREEK 619.0
END DESCRIPTION:
XS GIS Cut Line= 3
      3707000.01      10205147.1      3705846.14     10204097.25
      3704867.88     10203411.09
#Sta/Elev= 30
    3440  301.45  3807.1  295.22    4026  299.03  4146.3  295.74  4259.4  289.88
  4330.8  287.15  4479.4  287.79  4656.5  285.07  4790.9   287.8    4968  283.76
  4982.1  284.59  5003.2  281.72  5017.1  281.72  5017.8  283.25    5024  284.69
  5083.2  290.43  5181.7  289.48  5195.5  290.49  5237.8  290.69  5376.7  292.31
  5425.8  290.82  5440.6  289.04  5613.1  288.09  5678.5  288.99  5684.6  290.31
  5714.3  288.76  5785.7  288.62  5943.5  292.85  6122.2  304.21  6194.9  307.07
#Mann= 7 ,-1 , 0
    3440     .11       0  4259.4     .15       0  4982.1     .09       0
    5024     .15       0  5195.5     .11       0  5237.8     .15       0
  5376.7     .11       0
Bank Sta=4982.1,5024
XS Rating Curve= 0 ,0
Exp/Cntr=0.3,0.1

Type RM Length L Ch R = 1 ,319892  ,392,392,392
BEGIN DESCRIPTION:
LAKE CREEK 618.0
END DESCRIPTION:
XS GIS Cut Line= 3
       3707321.2     10205086.35      3706322.93      10203940.5
        3704908.     10203263.42
#Sta/Elev= 30
  3634.6  305.46  3846.2  298.09  4073.1  296.17  4108.2  297.65  4264.9  296.59
  4349.4  295.21  4490.8  289.55  4597.2  290.12  4739.6  287.19  4924.5  286.18
  4944.6  286.13  4994.7  281.56  5008.6  281.56  5015.9  283.06  5022.5  282.28
  5044.3  286.38  5210.4  286.18  5234.1  283.18  5238.7  283.74  5261.2  286.41
    5293  287.75  5347.1  287.46  5592.3  287.38  5758.6  292.46  6035.7  289.36
    6366  292.76  6694.5  305.75  6711.6  310.56  6717.1  310.67  6722.9  308.68
#Mann= 7 ,-1 , 0
  3634.6     .11       0  4924.5     .15       0  4944.6     .09       0
  5044.3     .15       0  5234.1     .11       0  5238.7     .15       0
  5347.1     .11       0
Bank Sta=4944.6,5044.3
XS Rating Curve= 0 ,0
Exp/Cntr=0.3,0.1

Type RM Length L Ch R = 1 ,319500  ,590,590,590
BEGIN DESCRIPTION:
LAKE CREEK 617.0
END DESCRIPTION:
XS GIS Cut Line= 3
      3707667.82     10204861.04      3706723.44     10203911.37
      3704717.82     10203111.06
#Sta/Elev= 30
  3660.7  309.27  3851.6  305.17  3968.2  298.88  4558.7  287.67  4862.7  284.56
  4926.4  284.59  4961.7  287.44 4966.24285.8477  4983.1  280.61  5037.1     286
  5200.9  286.59  5436.7  287.49  5449.4  283.45    5467     283  5473.7   283.2
  5479.8  287.25  5522.2  287.79  5544.4  285.69  5557.2   281.2  5587.4  286.96
  5611.2  286.82  5813.5  286.77  6050.4  291.39  6545.7  293.82  6857.9  303.48
  6899.3  310.53    6929  305.95  7007.1  311.37  7042.1   309.6  7159.4  312.29
#Mann= 7 ,-1 , 0
  3660.7     .17       0  3968.2     .11       0 4966.24     .06       0
  5037.1     .15       0  5200.9     .11       0    5467     .15       0
  5611.2     .11       0
Bank Sta=4966.24,5037.1
XS Rating Curve= 0 ,0
Exp/Cntr=0.3,0.1

Type RM Length L Ch R = 1 ,318910  ,410,410,410
BEGIN DESCRIPTION:
LAKE CREEK 616.0
END DESCRIPTION:
XS GIS Cut Line= 3
      3708017.83     10204561.04      3707086.82     10203489.11
       3705067.9     10203111.08
#Sta/Elev= 30
  3686.1  311.73  3877.4  303.05  4012.3  299.77  4210.7  291.84  4607.6  286.66
  4948.1  286.18  4976.1  285.66  4983.7  284.46  4990.4  280.43  5004.3  280.43
  5018.8  285.94  5053.9  287.04  5090.1  285.43  5178.9  288.38  5241.1  285.23
  5289.2  282.23  5341.8  287.05  5376.4  286.63    5522  286.67  5557.3   285.4
  5639.9   286.5  5684.7  285.13    5939  286.23  6038.7  287.04    6112  288.86
  6208.9  288.36  6755.3  293.28  7007.3  298.67  7128.6  303.74  7159.9  302.37
#Mann= 9 ,-1 , 0
  3686.1     .11       0  4948.1     .15       0  4976.1     .09       0
  5018.8     .15       0  5241.1     .17       0  5376.4     .15       0
  5639.9     .11       0    5939     .17       0  6038.7     .11       0
Bank Sta=4976.1,5018.8
XS Rating Curve= 0 ,0
Exp/Cntr=0.3,0.1

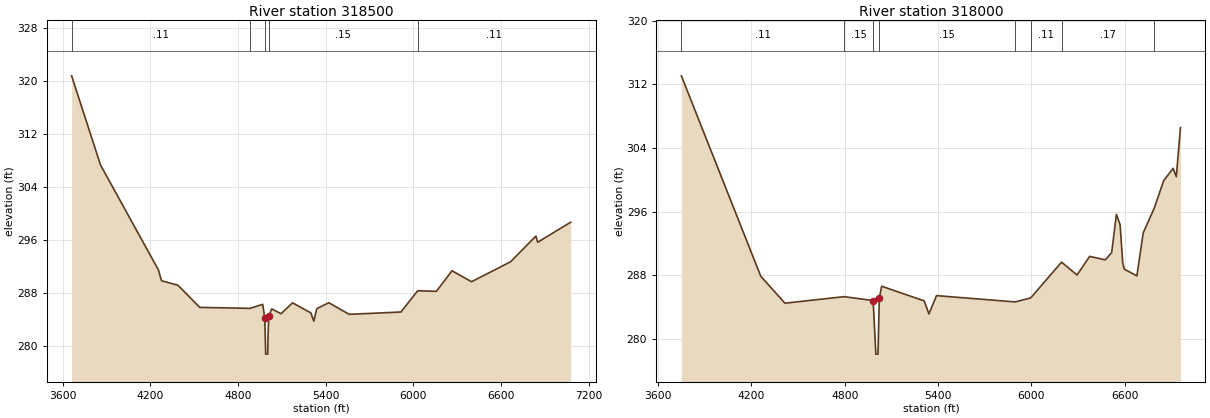
Type RM Length L Ch R = 1 ,318500  ,500,500,500
BEGIN DESCRIPTION:
LAKE CREEK 615.0
END DESCRIPTION:
XS GIS Cut Line= 3
      3708267.85     10204211.07      3707338.11     10203247.49
      3705317.84     10202761.07
#Sta/Elev= 30
    3661  320.72    3859  307.25  4255.1  291.42  4276.2  289.79  4389.4   289.1
  4537.9  285.76  4882.6  285.61  4969.3  286.22  4983.4  284.18  4989.6   278.7
  5003.5   278.7  5005.7   281.5  5010.9  284.45  5031.1  285.53  5094.7   284.8
  5173.5  286.45  5298.6  284.93  5319.1  283.68  5339.7  285.57    5422  286.46
  5561.1  284.71  5915.7  285.06  6030.6  288.27  6158.5  288.18  6265.4  291.29
  6399.1  289.63  6666.6  292.65  6839.7  296.52  6851.7  295.59    7078  298.62
#Mann= 5 ,-1 , 0
    3661     .11       0  4882.6     .15       0  4983.4     .09       0
  5010.9     .15       0  6030.6     .11       0
Bank Sta=4983.4,5010.9
XS Rating Curve= 0 ,0
Exp/Cntr=0.3,0.1

Type RM Length L Ch R = 1 ,318000  ,472,472,472
BEGIN DESCRIPTION:
LAKE CREEK 614.0
END DESCRIPTION:
XS GIS Cut Line= 3
      3708317.86     10203661.08      3707375.06     10202839.73
      3705441.41     10202523.12
#Sta/Elev= 30
  3749.6  313.06  4259.9  287.89  4415.6  284.49    4796  285.31    4983  284.82
  5000.4  278.09  5014.3  278.09  5022.6  285.11  5037.7  286.62  5311.3  284.78
  5341.7  283.14  5390.6  285.44  5896.6  284.65    5996  285.15  6194.8  289.65
  6294.2  288.03  6375.3  290.37  6476.6  289.94  6517.1  290.86  6547.5  295.65
  6571.3  294.35  6588.1  289.59  6598.2  288.77  6679.3  287.92  6719.8  293.32
  6791.2  296.46  6851.5  299.89  6912.3  301.43  6932.6  300.38  6959.4  306.55
#Mann= 8 ,-1 , 0
  3749.6     .11       0    4796     .15       0    4983     .09       0
  5022.6     .15       0  5896.6     .17       0    5996     .11       0
  6194.8     .17       0  6791.2     .11       0
Bank Sta=4983,5022.6
XS Rating Curve= 0 ,0
Exp/Cntr=0.3,0.1