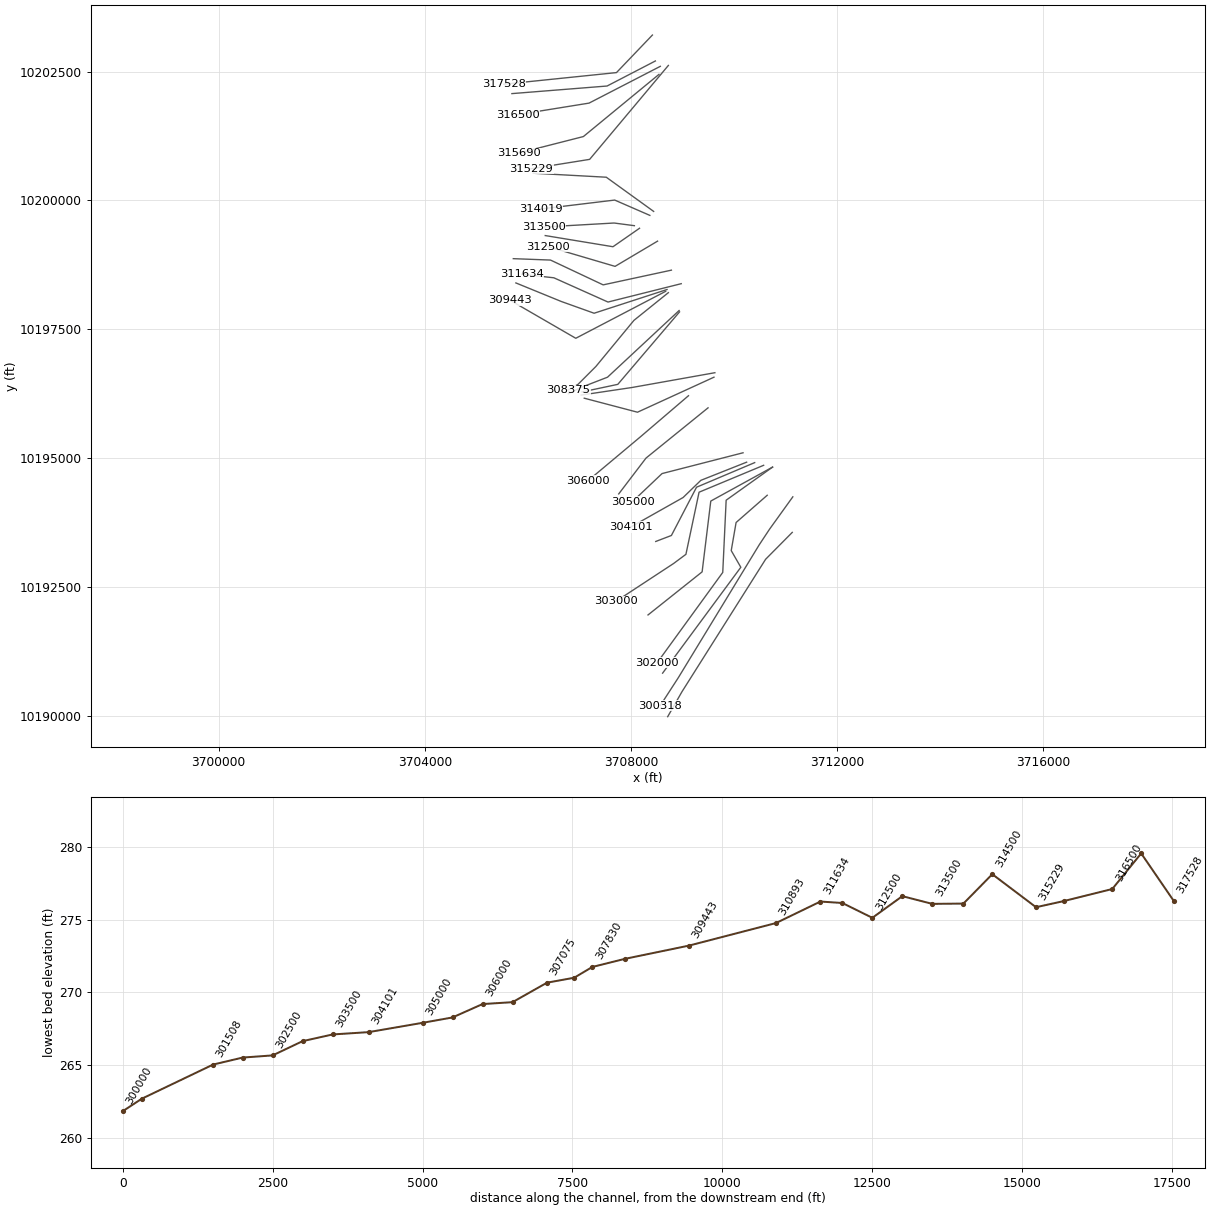
HEC-RAS study LAKE CREEK.prj: LAKE CREEK Base Level Engineering

--- LAKE CREEK.g01 (geometry) --- (continued)

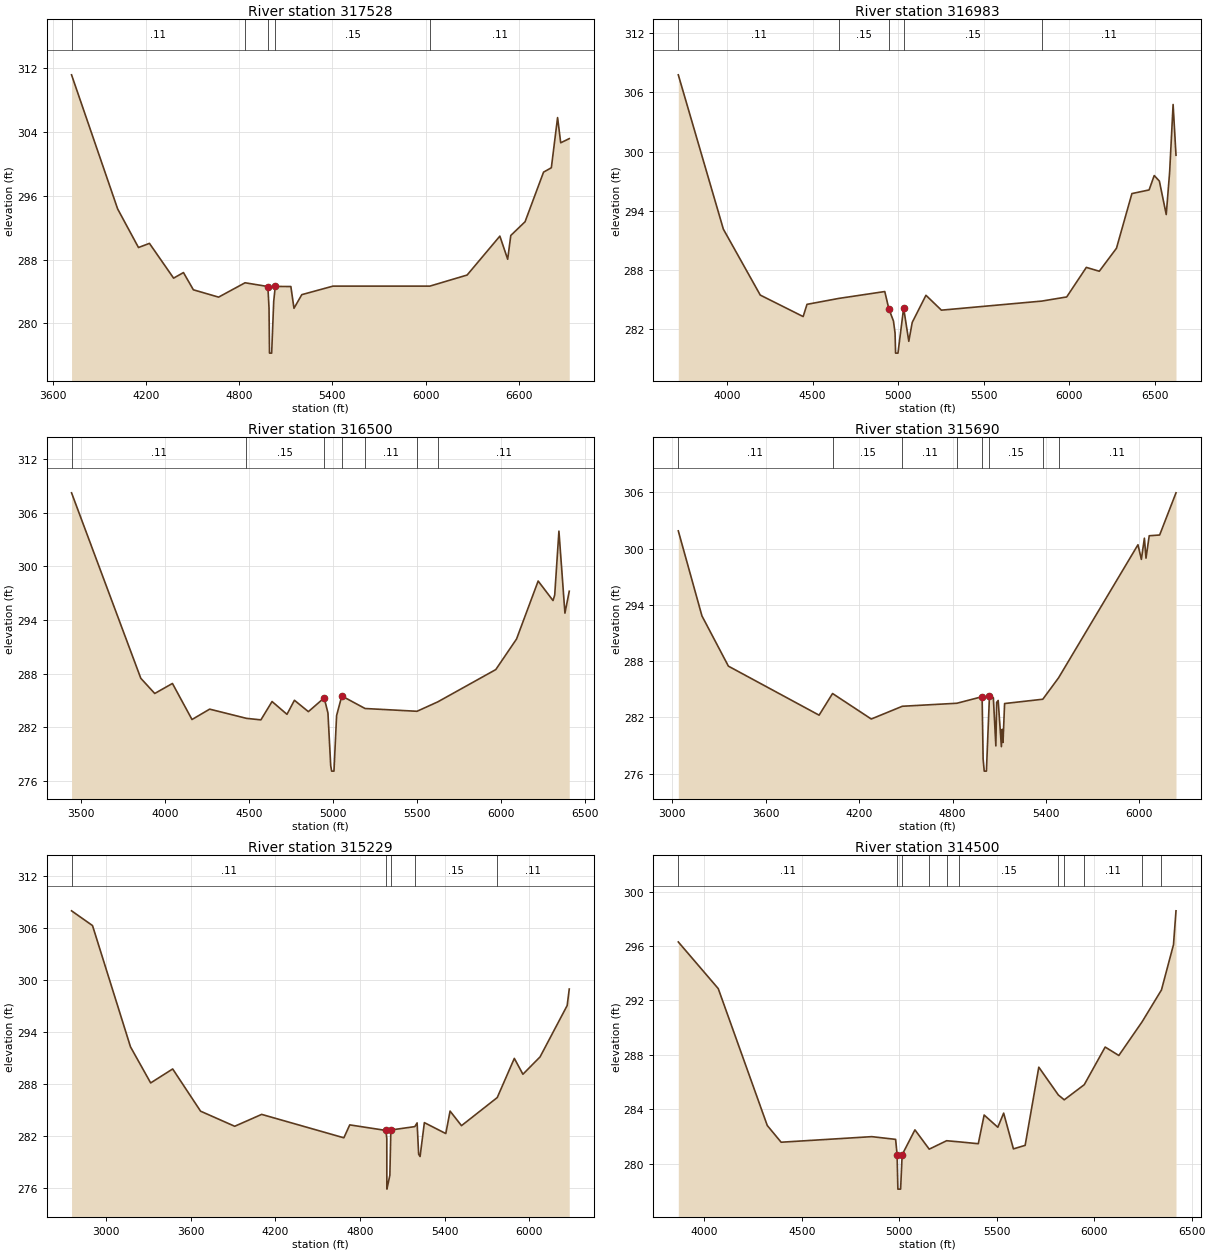
Type RM Length L Ch R = 1 ,317528  ,545,545,545
BEGIN DESCRIPTION:
LAKE CREEK 613.0
END DESCRIPTION:
XS GIS Cut Line= 3
      3708417.88      10203211.1       3707720.5     10202482.17
      3705533.01     10202256.48
#Sta/Elev= 30
  3718.5  311.16  4015.6  294.35  4149.9  289.51  4220.6  290.03  4376.3  285.67
  4439.8  286.37  4503.7  284.21  4666.3  283.29  4836.8  285.09  4983.9  284.62
  4991.3  281.92  4994.4  276.27  5008.3  276.27  5021.5  282.75  5031.6  284.63
  5132.1  284.62  5152.2  281.89  5202.5   283.6  5403.5  284.67  6027.9  284.67
  6268.1  286.06  6479.2  290.94  6529.5  288.04  6549.6  291.02  6641.6  292.74
  6760.7  298.96  6810.9  299.51  6851.2   305.8  6871.3  302.64  6926.4  303.16
#Mann= 5 ,-1 , 0
  3718.5     .11       0  4836.8     .15       0  4983.9     .09       0
  5031.6     .15       0  6027.9     .11       0
Bank Sta=4983.9,5031.6
XS Rating Curve= 0 ,0
Exp/Cntr=0.3,0.1

Type RM Length L Ch R = 1 ,316983  ,483,483,483
BEGIN DESCRIPTION:
LAKE CREEK 612.0
END DESCRIPTION:
XS GIS Cut Line= 3
      3708475.69     10202707.86      3707538.21     10202221.75
        3705691.     10202074.32
#Sta/Elev= 30
  3715.1  307.79  3978.5  292.13  4194.2  285.44  4444.9  283.26  4467.4   284.5
  4652.5   285.1    4922   285.8 4945.79284.0446  4972.7  282.81  4982.1  281.59
  4985.2  279.55  4999.1  279.55  5032.3  284.13  5062.4  280.75  5082.5  282.67
  5162.7  285.42    5253  283.91  5839.4  284.83  5985.3  285.25  6100.1  288.25
  6175.9  287.86  6276.2  290.19  6366.5  295.74  6466.9  296.11  6496.9  297.57
    6527  297.01  6567.2  293.61  6587.2  297.97  6607.3  304.78  6624.2  299.63
#Mann= 5 ,-1 , 0
  3715.1     .11       0  4652.5     .15       0 4945.79     .09       0
  5032.3     .15       0  5839.4     .11       0
Bank Sta=4945.79,5032.3
XS Rating Curve= 0 ,0
Exp/Cntr=0.3,0.1

Type RM Length L Ch R = 1 ,316500  ,810,810,810
BEGIN DESCRIPTION:
LAKE CREEK 611.0
END DESCRIPTION:
XS GIS Cut Line= 3
      3708571.22     10202603.71      3707188.24     10201889.95
      3705802.48     10201666.26
#Sta/Elev= 30
  3443.7  308.21  3855.5  287.48  3938.5  285.78  4043.7   286.9  4160.1  282.87
  4265.2  284.03  4483.9     283  4569.8  282.83  4636.2  284.88  4724.9  283.45
  4769.2  285.02  4852.2  283.75  4946.4  285.29  4968.6  283.59  4985.1   277.7
  4990.5   277.1  5004.4   277.1    5020  283.31    5051   285.5  5189.3   284.1
  5498.4  283.79  5621.5  284.84  5966.7  288.45  6090.2  291.87  6218.8  298.35
  6307.1  296.17  6317.2  296.78  6342.3  303.93    6378  294.76  6403.7  297.21
#Mann= 7 ,-1 , 0
  3443.7     .11       0  4483.9     .15       0  4946.4     .09       0
    5051     .15       0  5189.3     .11       0  5498.4     .15       0
  5621.5     .11       0
Bank Sta=4946.4,5051
XS Rating Curve= 0 ,0
Exp/Cntr=0.3,0.1

Type RM Length L Ch R = 1 ,315690  ,461,461,461
BEGIN DESCRIPTION:
LAKE CREEK 610.0
END DESCRIPTION:
XS GIS Cut Line= 3
      3708545.14     10202447.43      3707078.14     10201240.85
      3705821.17     10200920.11
#Sta/Elev= 30
  3038.7   301.9  3190.6  292.83  3360.5  287.47  3943.1  282.24  4029.5  284.55
  4278.1  281.83  4477.7  283.19  4827.7  283.51  4990.1  284.21  4996.6  277.56
  5003.7  276.27  5017.7  276.27  5037.4  284.33  5062.3   284.1  5078.3  278.96
  5083.5  283.61  5093.3  283.81  5113.9  278.88  5119.2  280.73  5124.3  279.33
  5134.5  283.48  5379.9  283.94  5481.4  286.23  5991.1  300.42    6013  298.86
  6032.4  301.12  6042.7  298.99  6063.4  301.38  6130.4  301.46  6235.4  305.96
#Mann= 8 ,-1 , 0
  3038.7     .11       0  4029.5     .15       0  4477.7     .11       0
  4827.7     .15       0  4990.1     .09       0  5037.4     .15       0
  5379.9     .17       0  5481.4     .11       0
Bank Sta=4990.1,5037.4
XS Rating Curve= 0 ,0
Exp/Cntr=0.3,0.1

Type RM Length L Ch R = 1 ,315229  ,729,729,729
BEGIN DESCRIPTION:
LAKE CREEK 609.0
END DESCRIPTION:
XS GIS Cut Line= 3
      3708727.45     10202621.07      3707199.67     10200798.14
      3706063.36     10200615.99
#Sta/Elev= 30
  2755.2  307.95  2903.9  306.25  3173.2  292.26  3316.2   288.1  3472.4  289.71
  3670.2  284.84  3912.2   283.1  4103.4  284.47  4686.2  281.77  4727.9  283.26
  4984.2  282.62  4990.7  281.69    4991  276.35  4991.5  275.85  5012.4  277.45
  5019.4  282.67  5189.3  283.06  5205.6  283.49  5216.5  279.88  5226.7  279.61
  5257.1  283.52    5409  282.26  5439.4  284.85  5520.4  283.17  5773.8  286.41
  5895.1  290.93  5955.9   289.1  6077.4   291.1  6269.8  297.03  6284.5  298.93
#Mann= 5 ,-1 , 0
  2755.2     .11       0  4984.2     .06       0  5019.4     .11       0
  5189.3     .15       0  5773.8     .11       0
Bank Sta=4984.2,5019.4
XS Rating Curve= 0 ,0
Exp/Cntr=0.3,0.1

Type RM Length L Ch R = 1 ,314500  ,481,481,481
BEGIN DESCRIPTION:
LAKE CREEK 607.0
END DESCRIPTION:
XS GIS Cut Line= 3
      3708441.89     10199788.12      3707522.66     10200451.66
      3706104.97     10200529.03
#Sta/Elev= 30
  3866.3   296.3  4071.3  292.87  4322.8   282.8  4393.9  281.57  4858.9  281.98
  4981.3  281.78  4988.9  280.66  4992.9  278.12  5006.9  278.12  5014.8  280.65
  5080.4  282.48  5153.7  281.06    5243  281.68  5305.5   281.6  5405.4  281.46
  5435.5  283.57  5505.6  282.67  5535.6  283.71  5585.7  281.08  5645.8  281.34
  5715.9  287.09  5816.5  285.04  5846.5  284.69    5949   285.8  6056.4  288.57
  6126.5  287.95    6246  290.43  6345.2  292.77  6406.9   296.1  6419.8  298.59
#Mann= 11 ,-1 , 0
  3866.3     .11       0  4988.9     .06       0  5014.8     .11       0
  5153.7     .15       0    5243     .11       0  5305.5     .15       0
  5816.5     .11       0  5846.5     .15       0    5949     .11       0
    6246     .17       0  6345.2     .11       0
Bank Sta=4988.9,5014.8
XS Rating Curve= 0 ,0
Exp/Cntr=0.3,0.1

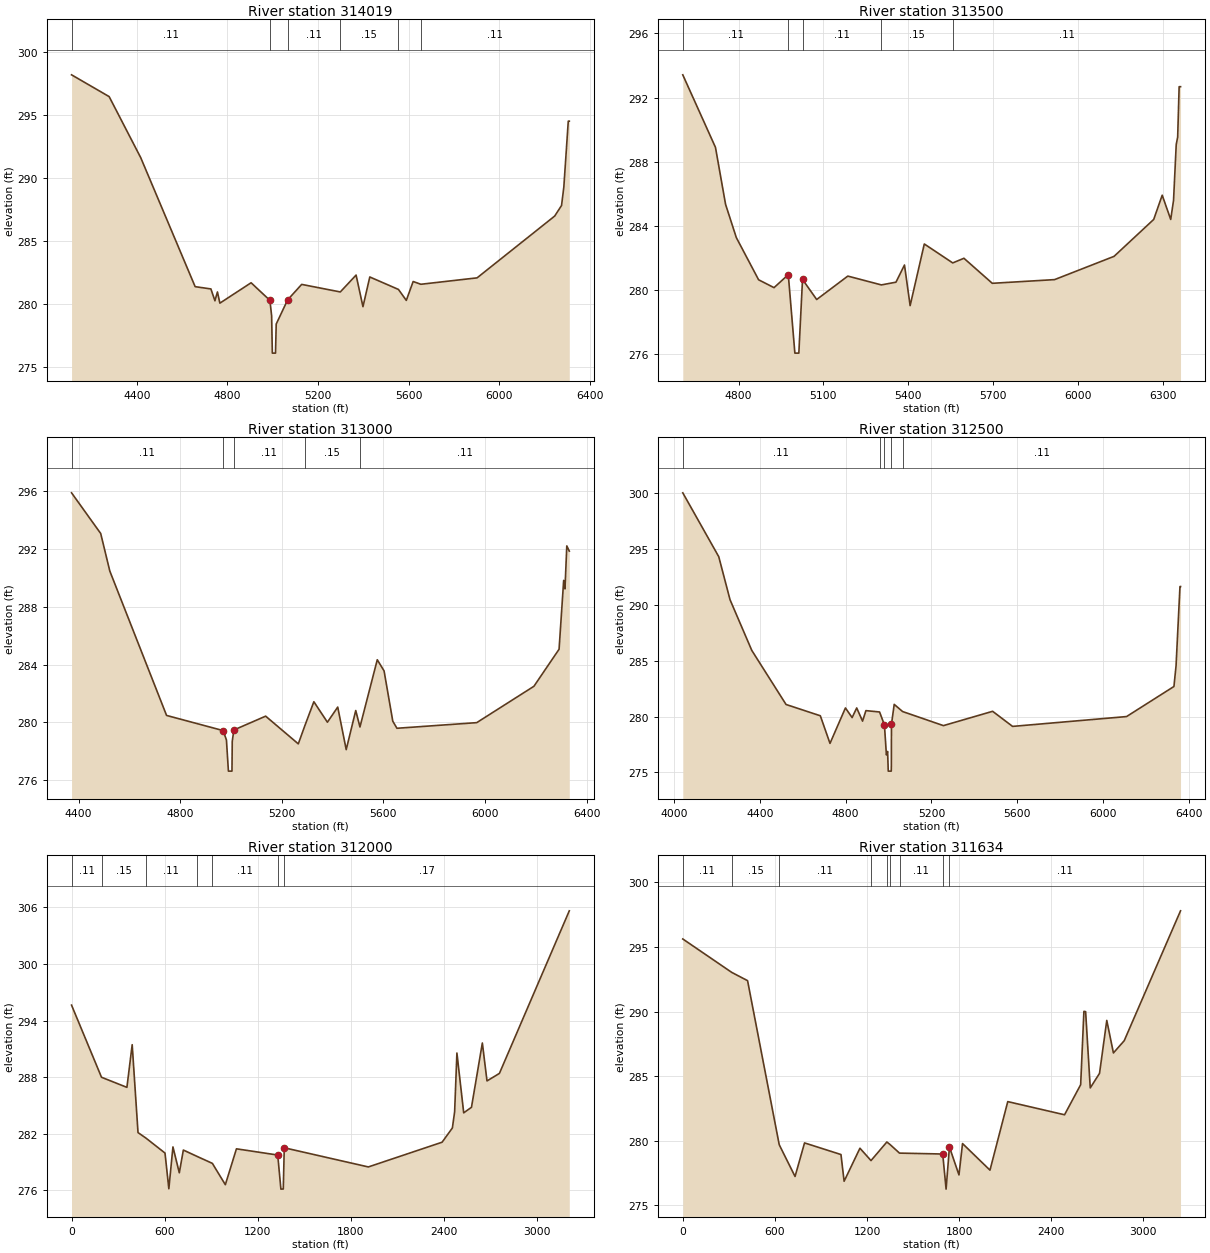
Type RM Length L Ch R = 1 ,314019  ,519,519,519
BEGIN DESCRIPTION:
LAKE CREEK 606.0
END DESCRIPTION:
XS GIS Cut Line= 3
      3708367.88     10199711.06      3707685.78     10200008.21
      3706243.88     10199834.07
#Sta/Elev= 30
  4112.4  298.21  4278.3  296.48  4417.9  291.62  4657.8  281.38  4727.3   281.2
  4745.1  280.26  4756.2  280.96  4766.9  280.07  4904.7  281.69 4987.69280.2928
  4995.3  279.06  4998.4   276.1  5012.4   276.1  5015.5  278.41  5065.9  280.33
  5127.9  281.56  5298.3  280.96    5368   282.3  5398.3  279.79  5428.5  282.15
  5554.9  281.16  5589.6  280.29  5619.8  281.79  5653.8  281.57  5901.9  282.08
  6244.4  286.99  6274.6  287.83  6284.7  289.29  6304.3  294.53  6308.8  294.53
#Mann= 6 ,-1 , 0
  4112.4     .11       0 4987.69     .06       0  5065.9     .11       0
  5298.3     .15       0  5554.9     .17       0  5653.8     .11       0
Bank Sta=4987.69,5065.9
XS Rating Curve= 0 ,0
Exp/Cntr=0.3,0.1

Type RM Length L Ch R = 1 ,313500  ,500,500,500
BEGIN DESCRIPTION:
LAKE CREEK 605.0
END DESCRIPTION:
XS GIS Cut Line= 3
      3708067.82     10199511.08      3707674.09     10199562.76
      3706313.19     10199485.47
#Sta/Elev= 30
  4602.9  293.42  4718.5   288.9  4754.2  285.35  4792.2  283.28    4871  280.65
  4925.6  280.16    4976  280.97  4999.3  276.08  5013.3  276.08  5026.3  280.67
  5076.4  279.42  5186.5  280.88  5305.1  280.33  5356.8   280.5  5386.9  281.57
  5406.9  279.04    5457  282.88  5557.6   281.7  5597.2  281.99  5697.4  280.43
  5917.7  280.66  6128.1  282.11  6268.3  284.41  6298.3  285.92  6328.4  284.41
  6338.4   285.6  6347.9  289.08    6353  289.54  6358.2  292.68  6363.1  292.68
#Mann= 5 ,-1 , 0
  4602.9     .11       0    4976     .06       0  5026.3     .11       0
  5305.1     .15       0  5557.6     .11       0
Bank Sta=4976,5026.3
XS Rating Curve= 0 ,0
Exp/Cntr=0.3,0.1

Type RM Length L Ch R = 1 ,313000  ,500,500,500
BEGIN DESCRIPTION:
LAKE CREEK 604.0
END DESCRIPTION:
XS GIS Cut Line= 3
      3708167.88     10199461.09      3707652.31     10199102.69
      3706338.23     10199319.19
#Sta/Elev= 30
  4372.1   295.9  4486.9  293.08  4522.7  290.48  4746.2  280.47  4968.9  279.42
  4981.9  278.77  4989.7  276.61  5003.7  276.61  5004.8  278.68 5011.14279.4613
  5136.3  280.42  5264.9   278.5  5289.8  279.72  5326.1  281.42  5379.5     280
  5420.1  281.05  5453.5   278.1    5491  280.81  5507.6  279.67  5575.8  284.33
  5602.5  283.56  5636.9  280.07  5653.2  279.58  5967.3  279.97  6192.5  282.49
  6291.6  285.06  6309.7  289.83  6314.8  289.24    6322  292.22  6331.8  291.86
#Mann= 5 ,-1 , 0
  4372.1     .11       0  4968.9     .06       0 5011.14     .11       0
  5289.8     .15       0  5507.6     .11       0
Bank Sta=4968.9,5011.14
XS Rating Curve= 0 ,0
Exp/Cntr=0.3,0.1

Type RM Length L Ch R = 1 ,312500  ,500,500,500
BEGIN DESCRIPTION:
LAKE CREEK 603.0
END DESCRIPTION:
XS GIS Cut Line= 3
      3708517.85     10199211.07      3707693.11      10198721.5
      3706387.88     10199106.06
#Sta/Elev= 30
  4040.9  300.01  4208.5   294.3  4261.1  290.45  4362.4  285.92  4522.2  281.08
    4682  280.07    4727   277.6  4798.9  280.77  4830.1  279.91  4851.5  280.77
  4878.8  279.59  4894.4  280.53  4958.1  280.41 4980.69279.2533  4989.9  276.57
  4995.5  276.88  4998.5  275.12  5012.5  275.12    5013  275.62  5013.4   279.3
  5026.3  281.09  5065.3  280.45  5255.7  279.19    5485  280.47    5578  279.12
  6109.2     280    6330  282.69  6339.9  284.55  6358.1  291.63  6360.7  291.63
#Mann= 5 ,-1 , 0
  4040.9     .11       0  4958.1     .17       0 4980.69     .09       0
  5013.4     .17       0  5065.3     .11       0
Bank Sta=4980.69,5013.4
XS Rating Curve= 0 ,0
Exp/Cntr=0.3,0.1

Type RM Length L Ch R = 1 ,312000  ,366,366,366
BEGIN DESCRIPTION:
LAKE CREEK 602.0
END DESCRIPTION:
XS GIS Cut Line= 4
      3708786.51     10198648.05        3707462.      10198362.4
       3706440.1     10198843.83      3705717.97     10198871.08
#Sta/Elev= 30
       0  295.63     193  287.99   356.7  286.92   390.7  291.44   428.3  282.13
     479  281.55   602.2  279.96   626.9  276.18   653.3  280.61   694.3  277.87
   720.4  280.28   806.8  279.62   907.3  278.87   990.9  276.61  1062.5  280.41
  1328.5  279.75    1349  276.14  1364.3  276.15  1370.6  280.52  1912.3  278.49
  2387.6  281.11  2453.9  282.62  2468.4  284.33  2483.1  290.56  2526.9  284.22
  2576.9  284.81    2647  291.62    2677   287.6    2757   288.4  3207.2  305.62
#Mann= 7 ,-1 , 0
       0     .11       0     193     .15       0     479     .11       0
   806.8     .17       0   907.3     .11       0  1328.5     .06       0
  1370.6     .17       0
Bank Sta=1328.5,1370.6
XS Rating Curve= 0 ,0
Exp/Cntr=0.3,0.1

Type RM Length L Ch R = 1 ,311634  ,741,741,741
BEGIN DESCRIPTION:
LAKE CREEK 601.0
END DESCRIPTION:
XS GIS Cut Line= 4
      3708977.17     10198385.44      3707555.57     10198029.04
      3706504.36     10198499.92      3705883.45     10198568.91
#Sta/Elev= 30
       0  295.62   318.9  293.03     422  292.39   628.2  279.68   731.3  277.22
   793.1  279.82  1030.4  278.92  1050.9  276.85    1154  279.41    1226  278.45
  1329.2  279.89  1349.6   279.7  1411.7  279.03  1693.2  278.96  1715.1  276.24
    1737   279.5    1799  277.34  1822.2  279.77    2001  277.71  2116.9  283.02
  2486.7     282  2591.7  284.33  2612.8  290.01    2624  289.99  2654.2  284.08
  2714.6  285.21  2761.8  289.31  2805.1  286.79  2875.5  287.74  3242.2   297.8
#Mann= 9 ,-1 , 0
       0     .11       0   318.9     .15       0   628.2     .11       0
    1226     .17       0  1329.2     .11       0  1349.6     .06       0
  1411.7     .11       0  1693.2     .06       0    1737     .11       0
Bank Sta=1693.2,1737
XS Rating Curve= 0 ,0
Exp/Cntr=0.3,0.1

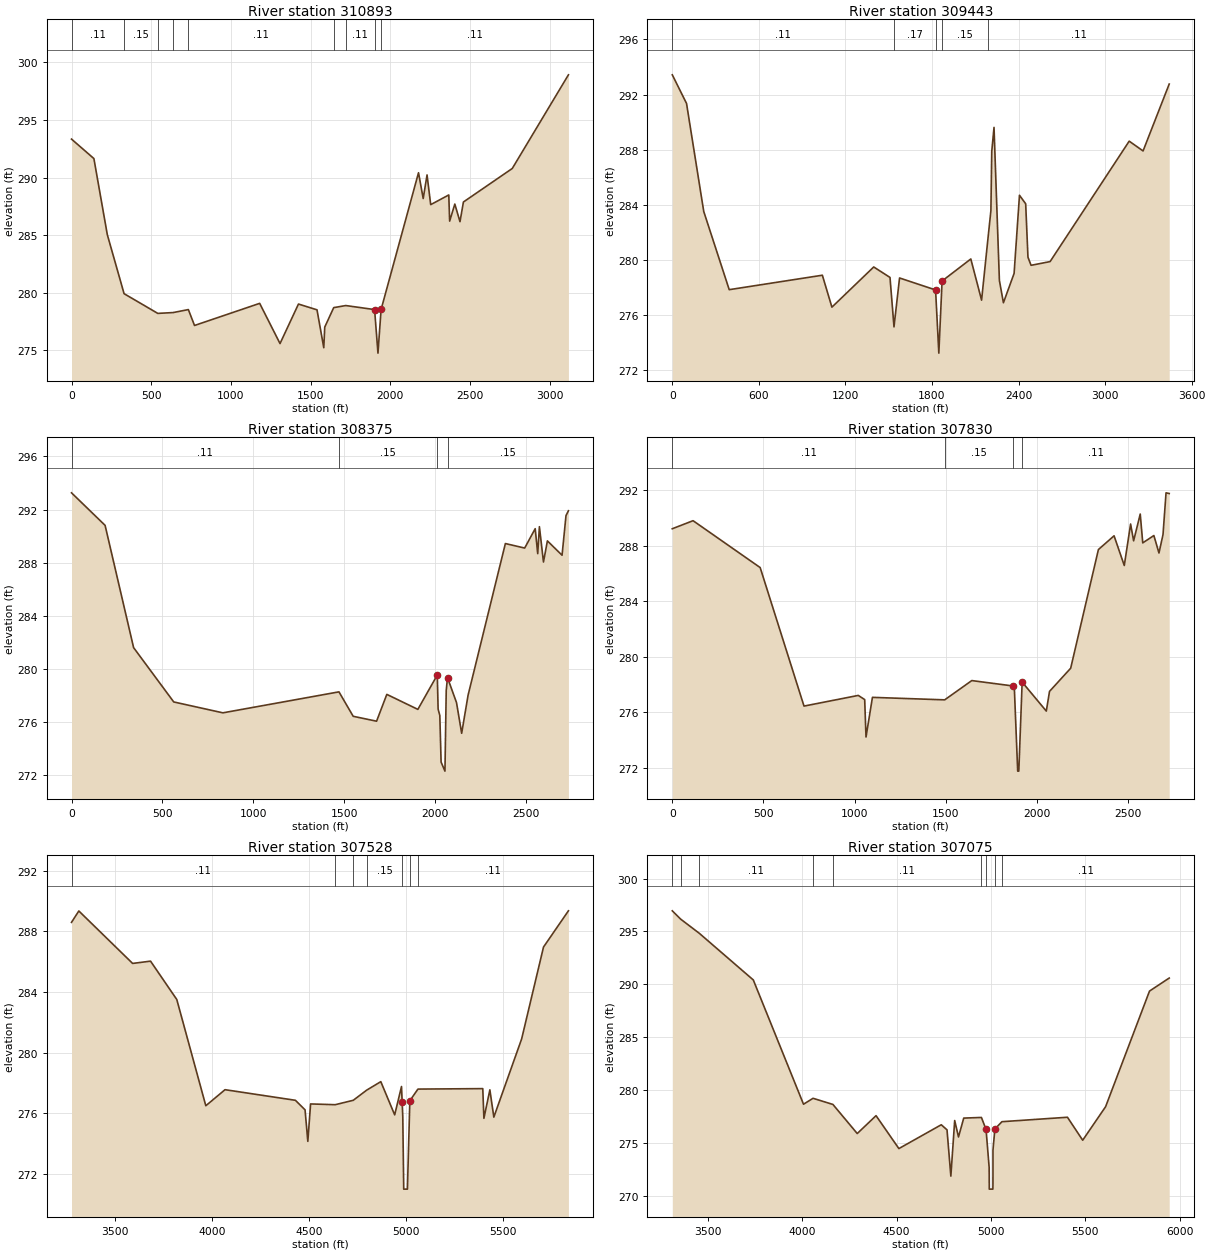
Type RM Length L Ch R = 1 ,310893  ,1450,1450,1450
BEGIN DESCRIPTION:
LAKE CREEK 600.0
END DESCRIPTION:
XS GIS Cut Line= 4
       3708701.4      10198272.1      3707286.47     10197812.03
      3706649.58     10198039.86      3705768.34     10198399.83
#Sta/Elev= 30
       0  293.34   140.4  291.65   224.6  285.04   329.7  279.92   541.1  278.21
   636.9  278.28   732.8  278.54   771.4  277.16    1180  279.08  1307.6  275.59
  1423.3  279.02  1539.5  278.52    1582  275.23  1588.1  277.02  1644.3  278.71
    1720  278.89  1900.6  278.54  1921.8  274.76  1941.5  278.55  2176.1  290.42
  2205.5  288.18  2229.6  290.23  2252.5  287.65  2365.9  288.49  2371.4  286.22
  2403.8   287.7  2436.2  286.17  2457.8  287.88  2764.1  290.79  3116.2  298.92
#Mann= 9 ,-1 , 0
       0     .11       0   329.7     .15       0   541.1     .11       0
   636.9     .15       0   732.8     .11       0  1644.3     .15       0
    1720     .11       0  1900.6     .06       0  1941.5     .11       0
Bank Sta=1900.6,1941.5
XS Rating Curve= 0 ,0
Exp/Cntr=0.3,0.1

Type RM Length L Ch R = 1 ,309443  ,1068,1068,1068
BEGIN DESCRIPTION:
LAKE CREEK 599.0
END DESCRIPTION:
XS GIS Cut Line= 3
      3708675.36     10198237.38      3706930.57     10197325.92
      3705653.22     10198065.28
#Sta/Elev= 30
       0  293.43    98.7  291.35     218   283.5   394.6  277.82  1040.1  278.87
  1106.4  276.55  1396.2  279.47    1509  278.71  1536.7  275.12  1575.2  278.67
  1824.9   277.8  1847.5  273.21    1870  278.45  2069.2  280.05  2143.8  277.06
  2186.9  281.42  2208.4  283.56  2214.3  287.86    2230  289.61  2267.3  278.49
  2295.2  276.87  2369.2     279  2406.5  284.68  2449.5  284.06  2465.3  280.18
  2486.8  279.59  2618.7  279.86    3167  288.61  3263.2   287.9  3444.4  292.76
#Mann= 5 ,-1 , 0
       0     .11       0  1536.7     .17       0  1824.9     .09       0
    1870     .15       0  2186.9     .11       0
Bank Sta=1824.9,1870
XS Rating Curve= 0 ,0
Exp/Cntr=0.3,0.1

Type RM Length L Ch R = 1 ,308375  ,545,545,545
BEGIN DESCRIPTION:
LAKE CREEK 597.0
END DESCRIPTION:
XS GIS Cut Line= 5
      3708727.44     10198211.34      3708059.04     10197673.14
      3707321.19     10196779.04      3706973.97     10196431.82
      3706779.19     10196320.56
#Sta/Elev= 30
       0  293.26   184.7  290.81   341.5   281.6   562.2  277.51   832.6  276.69
  1470.8  278.27    1549  276.43  1677.7  276.06    1734  278.08  1904.7  276.95
  2011.5  279.54  2016.1  276.97  2025.4  276.49  2032.5  272.98  2053.7   272.3
  2060.7  278.38  2067.8  279.34  2117.3  277.46  2145.6  275.15  2180.9  278.02
    2386  289.44  2492.1   289.1    2550  290.56  2563.8  288.68  2573.1  290.71
  2595.5  288.05  2617.1  289.64  2697.7  288.56  2719.3  291.54  2732.7  291.91
#Mann= 4 ,-1 , 0
       0     .11       0  1470.8     .15       0  2011.5     .09       0
  2067.8     .15       0
Bank Sta=2011.5,2067.8
XS Rating Curve= 0 ,0
Exp/Cntr=0.3,0.1

Type RM Length L Ch R = 1 ,307830  ,302,302,302
BEGIN DESCRIPTION:
LAKE CREEK 596.0
END DESCRIPTION:
XS GIS Cut Line= 4
      3708935.78     10197864.11      3707546.89     10196570.71
      3707008.69     10196362.38      3706786.39     10196248.62
#Sta/Elev= 30
       0  289.22   113.9   289.8   481.8  286.42   722.2  276.43  1019.7   277.2
  1054.9   276.9  1062.2   274.2  1097.4  277.06  1493.6  276.88  1642.2  278.27
  1868.9  277.88  1875.7  277.67  1893.9  271.74    1900  271.74  1918.3  278.16
  2050.8  276.07  2068.4  277.49  2184.4  279.16  2336.5  287.72  2422.3  288.71
  2478.3  286.57    2513  289.56  2529.6  288.35  2565.8  290.28  2579.6   288.2
  2640.6  288.73  2668.5  287.47  2690.7   288.8  2707.3  291.81  2724.7  291.76
#Mann= 4 ,-1 , 0
       0     .11       0  1493.6     .15       0  1868.9     .09       0
  1918.3     .11       0
Bank Sta=1868.9,1918.3
XS Rating Curve= 0 ,0
Exp/Cntr=0.3,0.1

Type RM Length L Ch R = 1 ,307528  ,453,453,453
BEGIN DESCRIPTION:
LAKE CREEK 595.0
END DESCRIPTION:
XS GIS Cut Line= 3
      3708944.46     10197838.08      3707746.54     10196431.82
      3707052.46     10196284.33
#Sta/Elev= 30
  3278.2   288.6  3315.9  289.35  3592.6  285.89  3684.9  286.04  3819.9  283.51
  3969.3   276.5  4068.1  277.56  4430.3  276.86  4479.9  276.23  4494.2  274.15
  4508.4  276.62  4635.1  276.57    4728  276.86    4797  277.53  4869.7  278.09
  4941.1   275.9  4976.2  277.77 4979.61276.7367  4982.8  275.77  4987.6     271
  5006.6     271  5019.1  276.83  5060.8   277.6  5394.4  277.63  5400.2  275.67
  5430.9  277.55  5451.3  275.75  5594.4  280.91  5706.9  286.97  5835.1  289.36
#Mann= 7 ,-1 , 0
  3278.2     .11       0  4635.1     .15       0    4728     .11       0
    4797     .15       0 4979.61     .09       0  5019.1     .15       0
  5060.8     .11       0
Bank Sta=4979.61,5019.1
XS Rating Curve= 0 ,0
Exp/Cntr=0.3,0.1

Type RM Length L Ch R = 1 ,307075  ,575,575,575
BEGIN DESCRIPTION:
LAKE CREEK 594.0
END DESCRIPTION:
XS GIS Cut Line= 3
      3709630.21     10196657.51      3708024.32     10196371.06
       3707034.7     10196223.48
#Sta/Elev= 30
    3312  296.95    3356  296.17  3455.5  294.82    3741  290.42  4006.9  278.68
  4057.5  279.24  4162.7  278.66  4291.5  275.91  4391.1   277.6    4512  274.49
  4736.5  276.74    4767  276.26  4787.3  271.89  4807.6  277.14  4827.9  275.59
  4855.5  277.37  4949.2  277.43 4973.73276.2943  4990.2   272.7  4990.8  270.66
  5009.8  270.66  5010.3  271.16  5010.4  274.35  5020.5  276.34  5057.9  277.03
  5404.8  277.45  5485.6  275.28    5607  278.45  5839.5  289.37  5943.8   290.6
#Mann= 9 ,-1 , 0
    3312     .11       0    3356     .17       0  3455.5     .11       0
  4057.5     .17       0  4162.7     .11       0  4949.2     .15       0
 4973.73     .09       0  5020.5     .15       0  5057.9     .11       0
Bank Sta=4973.73,5020.5
XS Rating Curve= 0 ,0
Exp/Cntr=0.3,0.1

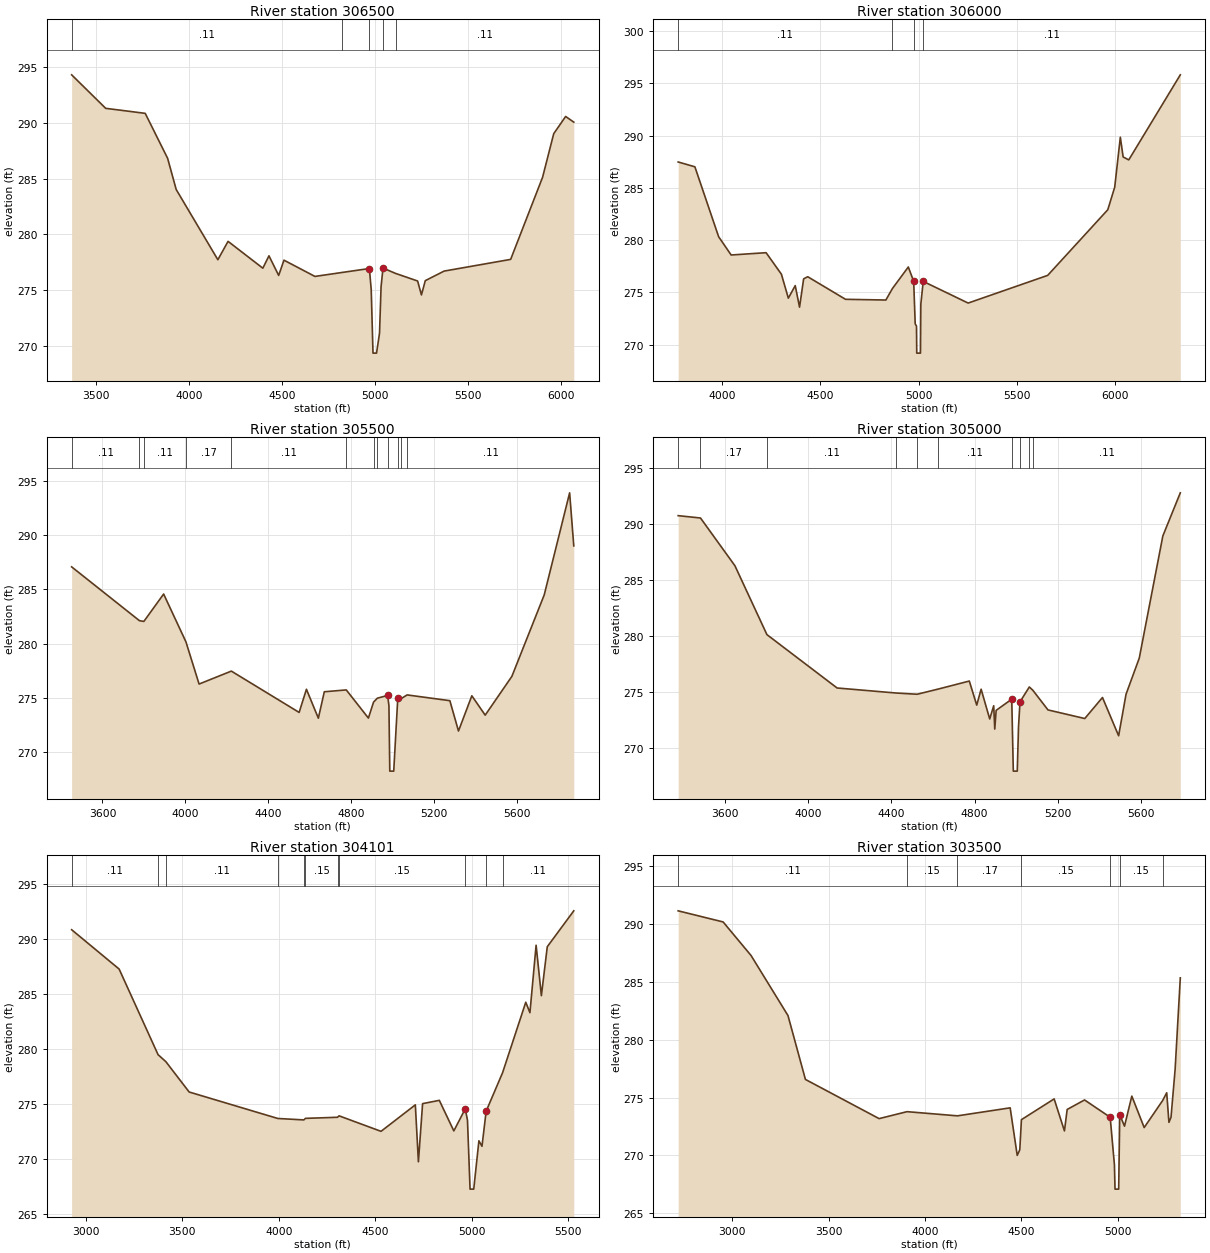
Type RM Length L Ch R = 1 ,306500  ,500,500,500
BEGIN DESCRIPTION:
LAKE CREEK 593.0
END DESCRIPTION:
XS GIS Cut Line= 3
      3709612.83      10196570.7      3708128.23       10195891.
      3707095.48     10196162.73
#Sta/Elev= 30
  3367.2  294.32  3550.3  291.31  3762.9  290.86  3883.4  286.82  3929.5  284.02
  4153.6  277.71  4208.5  279.36  4395.5  276.95  4428.5  278.06  4480.7   276.3
  4509.2  277.67  4675.7  276.21  4823.4  276.57  4968.4  276.92  4978.4  275.05
    4988  269.32    5007  269.32  5023.1  271.11  5031.4  275.28  5041.8  276.96
  5109.5  276.48  5227.9   275.8  5248.6  274.55  5269.2  275.83  5370.6  276.69
  5728.4  277.74    5900  285.11    5960  289.03  6024.1  290.58  6067.9  290.07
#Mann= 5 ,-1 , 0
  3367.2     .11       0  4823.4     .17       0  4968.4     .09       0
  5041.8     .17       0  5109.5     .11       0
Bank Sta=4968.4,5041.8
XS Rating Curve= 0 ,0
Exp/Cntr=0.3,0.1

Type RM Length L Ch R = 1 ,306000  ,500,500,500
BEGIN DESCRIPTION:
LAKE CREEK 592.0
END DESCRIPTION:
XS GIS Cut Line= 3
      3709117.82     10196211.04      3708188.23     10195415.85
      3707167.85     10194561.07
#Sta/Elev= 30
  3776.7  287.48  3861.7  287.02  3982.5  280.33  4046.2  278.58    4224   278.8
  4301.9  276.74  4337.1  274.45  4372.2  275.65  4394.1  273.59    4415   276.3
  4435.8   276.5    4628  274.34  4833.2  274.27  4866.6  275.37  4947.4  277.43
  4974.8  276.06  4982.5  271.99  4989.1  271.77  4990.3  269.19  5009.3  269.19
  5011.1  273.88  5023.3276.0534  5251.8  273.98  5656.5  276.63  5962.2  282.91
  5997.4  285.07    6026  289.85  6040.3  287.96  6068.9  287.68  6331.1  295.82
#Mann= 4 ,-1 , 0
  3776.7     .11       0  4866.6     .17       0  4974.8     .09       0
  5023.3     .11       0
Bank Sta=4974.8,5023.3
XS Rating Curve= 0 ,0
Exp/Cntr=0.3,0.1

Type RM Length L Ch R = 1 ,305500  ,500,500,500
BEGIN DESCRIPTION:
LAKE CREEK 591.0
END DESCRIPTION:
XS GIS Cut Line= 3
      3709497.46     10195975.67      3708293.99     10195001.08
      3707764.25     10194305.54
#Sta/Elev= 30
  3451.4  287.06  3778.5  282.11  3799.8  282.04  3895.3  284.56  4002.9  280.16
  4066.3  276.28    4222  277.47  4549.1  273.67  4584.3   275.8  4641.8  273.14
  4670.6  275.57  4776.5  275.74  4883.3  273.15  4908.2  274.62  4926.5  274.98
    4976  275.23  4982.4  274.29  4986.5  268.27  5005.5  268.27  5025.2  275.04
  5039.4  274.92  5070.3  275.28  5276.4  274.75    5318  271.96  5382.4   275.2
  5446.9  273.42  5575.7  276.99  5731.7  284.48  5854.3  293.87  5874.3  288.99
#Mann= 12 ,-1 , 0
  3451.4     .11       0  3778.5     .17       0  3799.8     .11       0
  4002.9     .17       0    4222     .11       0  4776.5     .17       0
  4908.2     .15       0  4926.5     .17       0    4976     .09       0
  5025.2     .17       0  5039.4     .15       0  5070.3     .11       0
Bank Sta=4976,5025.2
XS Rating Curve= 0 ,0
Exp/Cntr=0.3,0.1

Type RM Length L Ch R = 1 ,305000  ,899,899,899
BEGIN DESCRIPTION:
LAKE CREEK 590.0
END DESCRIPTION:
XS GIS Cut Line= 3
      3710177.05     10195103.69      3708604.91     10194700.16
      3708032.99     10194157.51
#Sta/Elev= 30
  3376.9  290.73  3484.1  290.52  3649.3  286.26  3803.1   280.1  4140.1  275.33
  4423.5  274.88  4524.4  274.77  4625.3  275.23  4775.1  275.95  4810.7   273.8
  4831.8  275.22  4873.1  272.56  4892.2  273.74  4897.3  271.66    4904  273.33
  4978.9  274.33  4986.4   267.9  5005.4   267.9  5011.3  271.82  5018.5  274.09
  5063.3  275.42  5080.1  275.13  5152.9  273.37  5329.6   272.6  5414.6  274.48
  5492.2  271.06  5527.8  274.77  5591.3     278  5704.6  288.92  5788.4  292.77
#Mann= 10 ,-1 , 0
  3376.9     .11       0  3484.1     .17       0  3803.1     .11       0
  4423.5     .17       0  4524.4     .15       0  4625.3     .11       0
  4978.9     .06       0  5018.5     .11       0  5063.3     .17       0
  5080.1     .11       0
Bank Sta=4978.9,5018.5
XS Rating Curve= 0 ,0
Exp/Cntr=0.3,0.1

Type RM Length L Ch R = 1 ,304101  ,601,601,601
BEGIN DESCRIPTION:
LAKE CREEK 588.0
END DESCRIPTION:
XS GIS Cut Line= 4
      3710246.52      10194921.4      3709357.73     10194568.73
       3709013.9     10194235.64      3707998.27     10193662.72
#Sta/Elev= 30
  2927.1  290.87  3173.1  287.29  3374.7   279.5  3415.2  278.86  3535.8   276.1
    3995  273.69  4129.9  273.56  4138.3   273.7  4304.3   273.8  4312.4  273.93
  4529.7  272.52  4707.4  274.93  4723.3  269.75    4745  275.04  4831.6  275.34
  4906.8  272.56    4966  274.57  4977.5  273.53  4990.9  267.26  5009.9  267.26
  5036.7  271.66  5052.6  271.16  5074.3  274.36  5159.2  277.85  5279.4  284.27
    5301  283.32  5332.9  289.46  5360.3  284.87  5390.8  289.32  5528.1  292.59
#Mann= 11 ,-1 , 0
  2927.1     .11       0  3374.7     .17       0  3415.2     .11       0
    3995     .15       0  4129.9     .17       0  4138.3     .15       0
  4304.3     .17       0  4312.4     .15       0    4966     .09       0
  5074.3     .15       0  5159.2     .11       0
Bank Sta=4966,5074.3
XS Rating Curve= 0 ,0
Exp/Cntr=0.3,0.1

Type RM Length L Ch R = 1 ,303500  ,500,500,500
BEGIN DESCRIPTION:
LAKE CREEK 587.0
END DESCRIPTION:
XS GIS Cut Line= 4
      3710402.83     10194912.74      3709274.26     10194435.32
      3708786.45     10193498.62      3708482.73     10193382.42
#Sta/Elev= 30
  2718.5   291.1  2951.9  290.14  3096.7  287.25  3288.5  282.07  3379.1  276.56
  3761.6  273.18  3906.7  273.78  4168.5  273.42    4442  274.11  4478.6  270.01
  4491.9  270.49  4500.4  273.09  4670.3  274.88  4723.7  272.12  4737.9  273.97
  4828.1  274.79  4961.1   273.3  4983.2   269.2  4986.3   267.1  5005.3   267.1
  5010.8  273.51  5035.5  272.53  5073.5  275.12  5137.7  272.41  5233.9  274.75
  5254.6  275.41  5266.2  272.86  5276.9  273.29  5298.3  277.43  5325.2  285.32
#Mann= 7 ,-1 , 0
  2718.5     .11       0  3906.7     .15       0  4168.5     .17       0
  4500.4     .15       0  4961.1     .09       0  5010.8     .15       0
  5233.9     .11       0
Bank Sta=4961.1,5010.8
XS Rating Curve= 0 ,0
Exp/Cntr=0.3,0.1

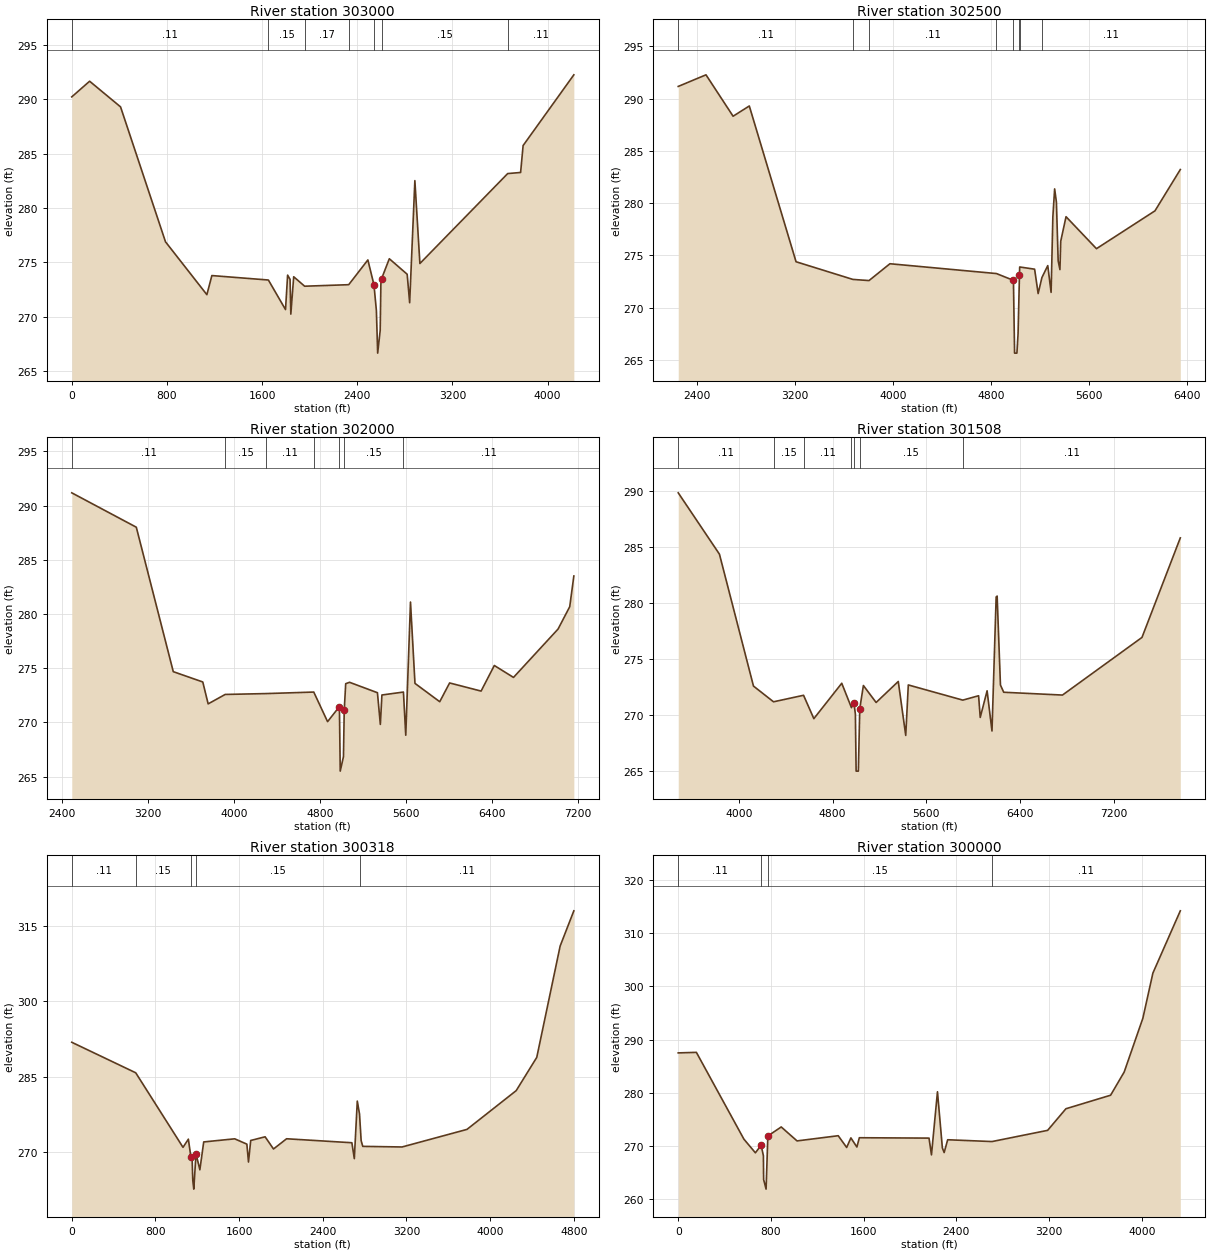
Type RM Length L Ch R = 1 ,303000  ,500,500,500
BEGIN DESCRIPTION:
LAKE CREEK 586.0
END DESCRIPTION:
XS GIS Cut Line= 5
       3710576.4     10194860.64      3709323.41      10194338.6
      3709068.23     10193132.91      3708829.53     10192955.26
       3707714.5     10192223.19
#Sta/Elev= 30
       0  290.23   150.1  291.67   410.1  289.31   787.9  276.89  1135.9  272.02
  1177.9  273.78  1653.1  273.37  1797.1  270.65  1814.8  273.82  1835.3  273.43
  1841.7  270.23  1865.9  273.67  1957.9   272.8  2328.5  272.94  2489.5  275.22
  2540.6  272.93    2561  270.57  2571.9  266.64  2593.1  268.73  2598.9  273.02
  2605.1   273.5  2669.8  275.33  2819.9   273.9  2840.8  271.28  2884.6  282.52
  2926.8  274.89  3665.1  283.17  3773.6  283.27  3794.7  285.75  4221.2  292.26
#Mann= 7 ,-1 , 0
       0     .11       0  1653.1     .15       0  1957.9     .17       0
  2328.5     .11       0  2540.6     .09       0  2605.1     .15       0
  3665.1     .11       0
Bank Sta=2540.6,2605.1
XS Rating Curve= 0 ,0
Exp/Cntr=0.3,0.1

Type RM Length L Ch R = 1 ,302500  ,500,500,500
BEGIN DESCRIPTION:
LAKE CREEK 585.0
END DESCRIPTION:
XS GIS Cut Line= 4
      3710749.97      10194825.9      3709550.62     10194166.38
      3709382.64     10192792.43      3708332.61     10191956.25
#Sta/Elev= 30
  2247.1  291.17  2473.5  292.28  2694.6  288.32  2826.8   289.3  3208.1   274.4
  3671.8  272.71  3803.2   272.6  3973.8  274.21    4843  273.27  4981.2  272.62
  4990.5  265.66  5009.5  265.66  5018.9   267.5  5030.3273.0894  5032.2   273.9
  5153.9  273.69  5182.7  271.36  5213.5  272.89  5261.2  274.03  5288.4  271.47
  5302.8  278.71  5317.3  281.37  5331.7   280.1  5346.1  274.48  5360.5  273.65
  5366.9  276.36  5410.2  278.71  5658.4  275.65  6135.7  279.27  6342.3  283.22
#Mann= 8 ,-1 , 0
  2247.1     .11       0  3671.8     .17       0  3803.2     .11       0
    4843     .15       0  4981.2     .09       0  5030.3     .12       0
  5032.2     .15       0  5213.5     .11       0
Bank Sta=4981.2,5030.3
XS Rating Curve= 0 ,0
Exp/Cntr=0.3,0.1

Type RM Length L Ch R = 1 ,302000  ,492,492,492
BEGIN DESCRIPTION:
LAKE CREEK 584.0
END DESCRIPTION:
XS GIS Cut Line= 4
      3710750.04     10194825.94      3709848.98     10194183.48
      3709783.06     10192781.67      3708512.33     10191032.28
#Sta/Elev= 30
    2490  291.17  3090.5     288  3434.7  274.68  3709.2  273.73  3759.2  271.71
  3917.7  272.58    4300  272.66  4741.9   272.8  4870.5  270.07  4980.6  271.46
  4988.3  265.51  5018.3  266.84  5025.5  271.12  5039.2  273.57  5074.9   273.7
  5334.5  272.74  5361.5  269.82  5376.2  272.53  5576.4   272.8    5598  268.82
  5642.1   281.1  5683.8   273.6  5914.2  271.91  6006.2  273.64  6299.1  272.89
  6422.1  275.25  6600.6  274.15  7015.4  278.61  7123.9  280.67  7162.2   283.5
#Mann= 7 ,-1 , 0
    2490     .11       0  3917.7     .15       0    4300     .11       0
  4741.9     .15       0  4980.6     .09       0  5025.5     .15       0
  5576.4     .11       0
Bank Sta=4980.6,5025.5
XS Rating Curve= 0 ,0
Exp/Cntr=0.3,0.1

Type RM Length L Ch R = 1 ,301508  ,1190,1190,1190
BEGIN DESCRIPTION:
LAKE CREEK 583.0
END DESCRIPTION:
XS GIS Cut Line= 5
      3710645.81     10194279.01      3710041.95     10193750.39
      3709947.58     10193205.45      3710133.69     10192881.47
      3708615.94     10190826.66
#Sta/Elev= 30
  3483.8   289.8  3835.4  284.34  4125.8   272.6  4296.8   271.2  4553.1  271.78
  4640.9   269.7    4879  272.85  4961.7  270.68  4982.8  271.11  4995.3   270.1
  5001.6  265.03  5020.6  265.03  5032.7  270.59  5063.6  272.65  5172.2  271.14
  5361.2  273.01  5424.9  268.21  5446.8   272.7  5911.7  271.35  6046.5  271.74
  6060.6  269.81  6119.1  272.18  6160.8   268.6  6196.3  280.53  6204.7  280.61
    6233  272.69    6261  272.05  6762.1   271.8  7440.6  276.93  7767.6  285.79
#Mann= 7 ,-1 , 0
  3483.8     .11       0  4296.8     .15       0  4553.1     .11       0
  4961.7     .15       0  4982.8     .09       0  5032.7     .15       0
  5911.7     .11       0
Bank Sta=4982.8,5032.7
XS Rating Curve= 0 ,0
Exp/Cntr=0.3,0.1

Type RM Length L Ch R = 1 ,300318  ,318,318,318
BEGIN DESCRIPTION:
LAKE CREEK 581.0
END DESCRIPTION:
XS GIS Cut Line= 5
      3711142.77     10194248.49      3710690.44     10193619.56
       3710489.6      10193315.5      3708921.52     10190739.88
      3708570.67     10190197.88
#Sta/Elev= 30
       0  291.84   611.5  285.78  1063.6  270.98  1114.8   272.6  1138.8  269.08
  1151.1  268.42    1157  264.43  1166.6  262.68  1187.9  269.72  1224.7  266.52
  1261.4  272.05  1557.9  272.67  1674.1  271.61  1689.6  268.06  1710.9  272.34
  1848.5  273.07  1928.7  270.65  2053.8  272.68    2678  271.89  2701.4  268.73
  2729.8  280.16  2751.1  277.59  2766.6  272.32  2782.1  271.17    3158  271.05
  3778.5  274.54  4249.2  282.24  4445.7  288.84  4669.3  310.95  4800.2  317.94
#Mann= 5 ,-1 , 0
       0     .11       0   611.5     .15       0  1138.8     .09       0
  1187.9     .15       0  2751.1     .11       0
Bank Sta=1138.8,1187.9
XS Rating Curve= 0 ,0
Exp/Cntr=0.3,0.1

Type RM Length L Ch R = 1 ,300000  ,500,500,500
BEGIN DESCRIPTION:
LAKE CREEK 580.0
END DESCRIPTION:
XS GIS Cut Line= 4
      3711131.96     10193558.56      3710614.67     10193036.61
      3708990.97     10190465.58      3708714.57     10189982.04
#Sta/Elev= 30
       0  287.48   156.7  287.58   566.8  271.23   665.8  268.66   715.3  270.08
   734.9  268.12   736.9  263.62   758.1  261.82   773.3  271.83   888.7  273.53
  1025.3   270.9  1380.5  271.88  1453.4  269.67  1489.9  271.47  1541.7  269.75
  1562.8   271.5  2164.1  271.43  2185.3  268.27    2237  280.16  2279.4  269.57
  2294.7  268.71  2325.2  271.12  2707.7  270.78  3187.7  272.89  3345.4  276.96
  3731.2  279.51  3848.4  283.88  4009.6  294.02    4096  302.51  4332.6  314.24
#Mann= 4 ,-1 , 0
       0     .11       0   715.3     .09       0   773.3     .15       0
  2707.7     .11       0
Bank Sta=715.3,773.3
XS Rating Curve= 0 ,0
Exp/Cntr=0.3,0.1