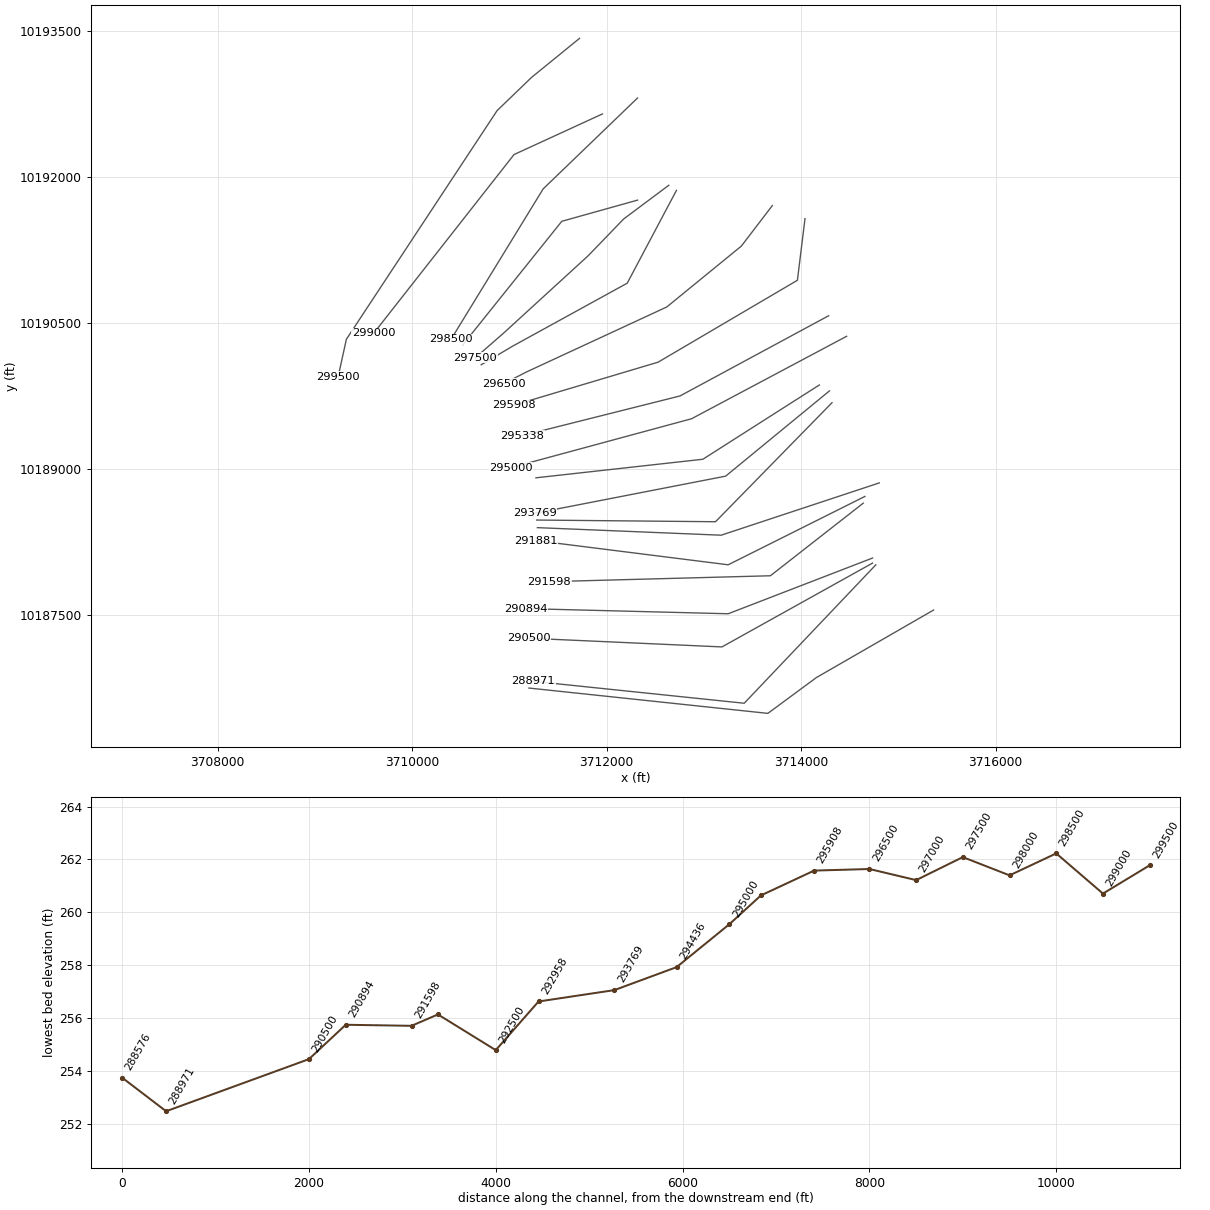
HEC-RAS study LAKE CREEK.prj: LAKE CREEK Base Level Engineering

--- LAKE CREEK.g01 (geometry) --- (continued)

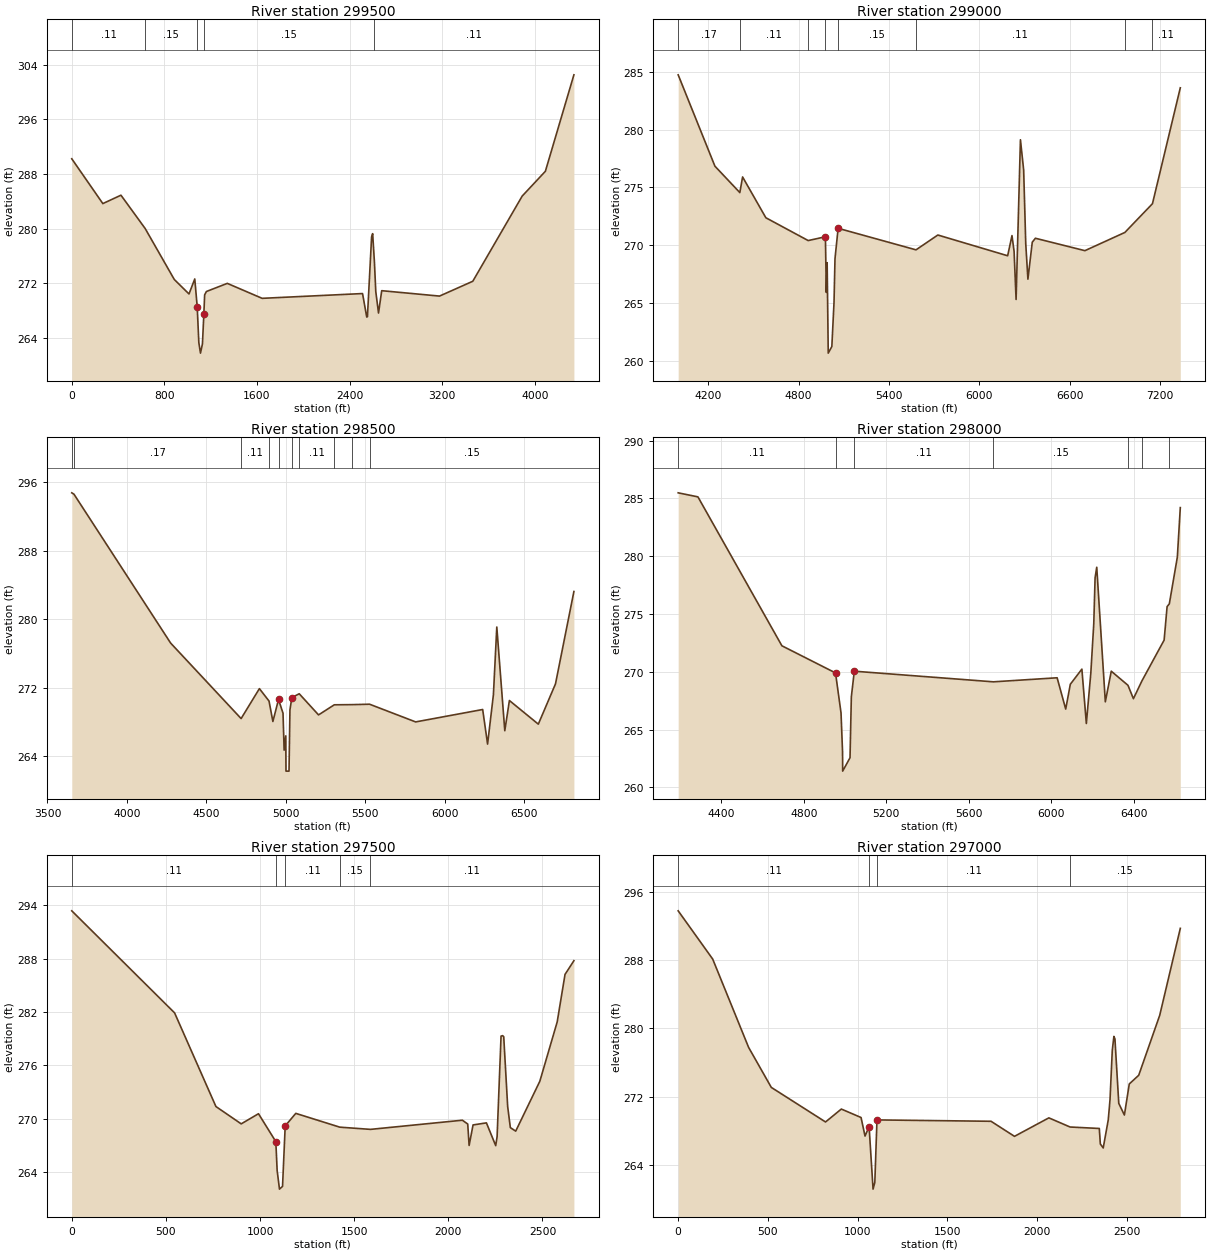
Type RM Length L Ch R = 1 ,299500  ,500,500,500
BEGIN DESCRIPTION:
LAKE CREEK 579.0
END DESCRIPTION:
XS GIS Cut Line= 5
      3711721.95      10193424.7      3711228.08     10193022.73
      3710873.77     10192681.12       3709324.3     10190330.16
      3709239.78     10189946.06
#Sta/Elev= 30
       0  290.23   268.4  283.67   424.9   284.9   634.1  280.02   885.7  272.56
  1012.8  270.44  1062.5  272.64  1083.6   268.6  1097.7  263.32  1111.9  261.78
  1128.9  263.13    1141  267.47  1147.9  270.31    1163   270.8  1343.6  271.99
  1644.7   269.8    2512   270.5  2548.1  267.06  2554.2  267.11  2590.2  278.79
  2599.3  279.27  2614.1  275.27  2626.4  270.78    2650  267.65  2677.6  270.92
    3177  270.13  3464.4   272.3  3891.2  284.77  4091.5   288.4  4337.9  302.52
#Mann= 5 ,-1 , 0
       0     .11       0   634.1     .15       0  1083.6     .09       0
    1141     .15       0  2614.1     .11       0
Bank Sta=1083.6,1141
XS Rating Curve= 0 ,0
Exp/Cntr=0.3,0.1

Type RM Length L Ch R = 1 ,299000  ,500,500,500
BEGIN DESCRIPTION:
LAKE CREEK 578.0
END DESCRIPTION:
XS GIS Cut Line= 3
      3711956.64     10192647.12      3711048.07     10192229.64
      3709605.53     10190392.63
#Sta/Elev= 30
  4000.1  284.72  4244.2  276.84  4409.7  274.56    4428  275.91  4582.5  272.39
  4863.8  270.42  4978.2  270.75  4984.2  265.95  4989.7  268.51    4997  260.71
  5020.9  261.28  5035.4  265.09  5041.8  268.85  5062.6  271.48    5580  269.62
  5725.1   270.9  6188.7  269.11  6217.6  270.85  6231.5  269.49  6244.8  265.34
  6273.7  279.12  6295.1  276.51    6309  270.14  6323.4  267.09  6352.3  270.28
  6373.1  270.62    6702  269.55  6967.3  271.12  7150.7   273.6  7335.7   283.6
#Mann= 8 ,-1 , 0
  4000.1     .17       0  4409.7     .11       0  4863.8     .15       0
  4978.2     .09       0  5062.6     .15       0    5580     .11       0
  6967.3     .15       0  7150.7     .11       0
Bank Sta=4978.2,5062.6
XS Rating Curve= 0 ,0
Exp/Cntr=0.3,0.1

Type RM Length L Ch R = 1 ,298500  ,500,500,500
BEGIN DESCRIPTION:
LAKE CREEK 577.0
END DESCRIPTION:
XS GIS Cut Line= 3
      3712317.84     10192811.06      3711347.71     10191876.72
      3710400.68     10190330.14
#Sta/Elev= 30
  3653.1  294.75  3666.9  294.59  4275.5  277.19    4719  268.37    4834  271.87
  4894.6  270.42  4918.9  268.03  4954.4   270.6  4982.7     269  4989.7  264.68
    5000  266.35  5001.4  262.23  5020.4  262.23  5026.3  269.39 5038.21 270.824
  5084.7  271.27  5206.3   268.8  5305.3  269.98  5419.7     270  5527.3  270.05
  5817.6  267.98  6239.3  269.43  6270.2  265.39  6306.9  271.16  6328.2  279.07
  6378.5  266.95  6407.5  270.48  6589.6  267.72  6697.7  272.43  6813.5  283.22
#Mann= 10 ,-1 , 0
  3653.1     .11       0  3666.9     .17       0    4719     .11       0
  4894.6     .15       0  4954.4     .09       0 5038.21     .15       0
  5084.7     .11       0  5305.3     .15       0  5419.7     .11       0
  5527.3     .15       0
Bank Sta=4954.4,5038.21
XS Rating Curve= 0 ,0
Exp/Cntr=0.3,0.1

Type RM Length L Ch R = 1 ,298000  ,500,500,500
BEGIN DESCRIPTION:
LAKE CREEK 576.0
END DESCRIPTION:
XS GIS Cut Line= 3
      3712317.83     10191761.07      3711539.16     10191543.45
      3710523.15     10190275.77
#Sta/Elev= 30
  4191.5  285.49  4287.2  285.14  4694.1  272.25  4953.9   269.9  4980.6  266.44
    4988  263.06  4988.6   261.4  5024.2  262.56  5030.6  267.83    5045  270.05
  5718.9  269.13  6027.7  269.48  6069.3  266.77  6091.7  268.92  6147.7  270.23
  6169.3  265.52  6190.9  269.87  6205.3  274.16  6211.7  278.14  6219.7  279.05
  6261.3   267.4  6290.1  270.05    6371  268.83  6397.4  267.67  6438.6  269.21
  6546.2  272.74  6560.6  275.64  6571.4  275.88  6610.2  279.92  6624.6  284.21
#Mann= 7 ,-1 , 0
  4191.5     .11       0  4953.9     .06       0    5045     .11       0
  5718.9     .15       0    6371     .17       0  6438.6     .15       0
  6571.4     .17       0
Bank Sta=4953.9,5045
XS Rating Curve= 0 ,0
Exp/Cntr=0.3,0.1

Type RM Length L Ch R = 1 ,297500  ,500,500,500
BEGIN DESCRIPTION:
LAKE CREEK 575.0
END DESCRIPTION:
XS GIS Cut Line= 5
      3712639.27     10191913.81      3712175.98     10191567.73
      3711809.67     10191188.51      3710940.68     10190393.65
      3710649.94     10190140.32
#Sta/Elev= 30
       0  293.39   546.2  281.91   765.6  271.38   899.9  269.43   991.7  270.57
  1083.8  267.43  1090.8  264.18  1103.2  262.09  1119.4   262.4  1133.6   269.2
  1189.7  270.61  1423.4  269.06  1586.2  268.81  2074.6  269.84    2103  269.41
  2110.4     267  2131.3  269.31  2202.3  269.54  2251.6  266.98    2259  267.99
    2280   279.3  2288.4  279.35  2294.2  279.23  2315.1  271.39  2329.3  269.01
  2357.8  268.61  2485.9  274.22  2578.1  280.89  2619.8  286.24  2666.9  287.78
#Mann= 5 ,-1 , 0
       0     .11       0  1083.8     .06       0  1133.6     .11       0
  1423.4     .15       0  1586.2     .11       0
Bank Sta=1083.8,1133.6
XS Rating Curve= 0 ,0
Exp/Cntr=0.3,0.1

Type RM Length L Ch R = 1 ,297000  ,500,500,500
BEGIN DESCRIPTION:
LAKE CREEK 574.0
END DESCRIPTION:
XS GIS Cut Line= 4
      3712717.85     10191861.07      3712212.16     10190907.25
      3711033.59     10190259.44      3710711.09     10190068.37
#Sta/Elev= 30
       0  293.75   192.4  288.11   392.7  277.78     519  273.11   821.3  269.07
   909.2  270.58  1019.2  269.59  1041.3  267.42  1063.9  268.53  1086.1  261.22
  1095.9  262.01  1107.9  269.31  1743.5  269.15  1874.2  267.39  2065.8  269.55
    2184  268.48  2346.9  268.31  2352.6   266.5  2368.7  266.03  2396.8  269.32
  2406.6  271.68  2419.2  277.43  2428.2  279.07    2434  278.78  2455.4  271.24
  2486.7  269.88  2513.9  273.51  2566.6  274.53  2683.6  281.54  2798.3   291.7
#Mann= 4 ,-1 , 0
       0     .11       0  1063.9     .06       0  1107.9     .11       0
    2184     .15       0
Bank Sta=1063.9,1107.9
XS Rating Curve= 0 ,0
Exp/Cntr=0.3,0.1

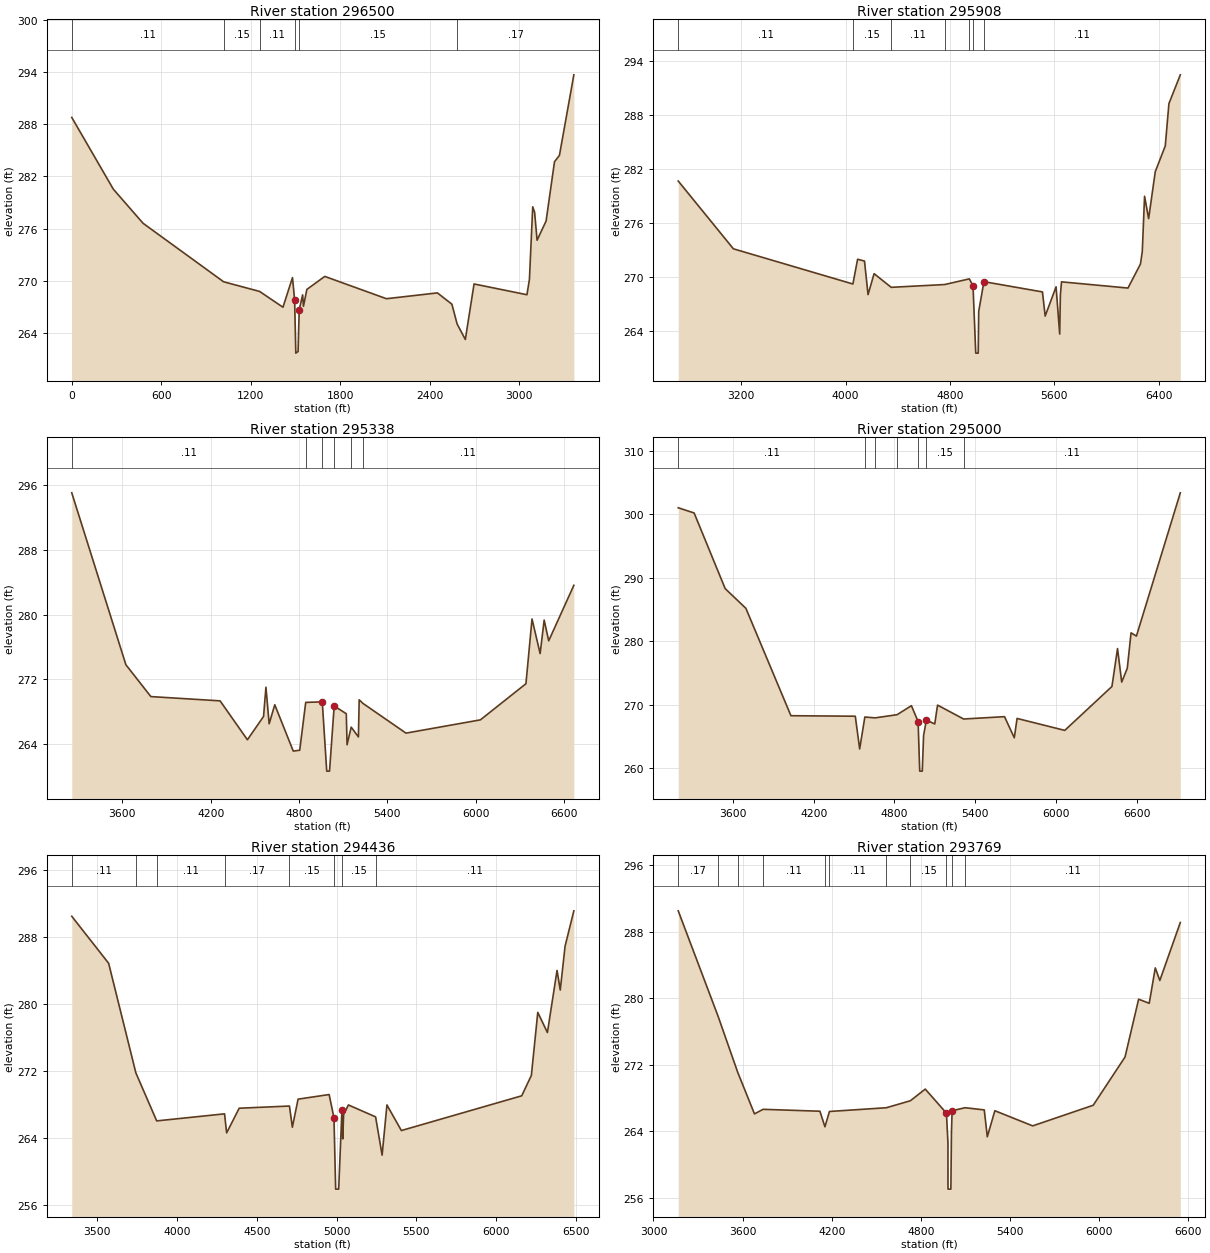
Type RM Length L Ch R = 1 ,296500  ,592,592,592
BEGIN DESCRIPTION:
LAKE CREEK 573.0
END DESCRIPTION:
XS GIS Cut Line= 5
      3713704.09     10191705.17       3713385.5     10191288.73
      3712618.45     10190662.48      3711182.39     10189997.24
      3710941.32     10189874.12
#Sta/Elev= 30
       0   288.8   278.8  280.53   478.3   276.6  1018.5  269.86  1259.7  268.75
  1416.3  266.93  1480.2  270.34  1494.5  267.79  1502.4  261.64  1517.6  261.82
  1525.3  266.64  1548.2  268.35  1553.7  267.04  1576.6  268.98  1696.7  270.48
  2110.3  267.91    2452  268.58  2549.2  267.28  2584.2     265  2639.3  263.21
  2697.8  269.61  3052.5  268.37  3069.2  270.14  3091.2   278.5  3103.9  277.88
  3120.5  274.65  3180.9  276.86  3237.2  283.69  3270.4  284.43    3367  293.71
#Mann= 6 ,-1 , 0
       0     .11       0  1018.5     .15       0  1259.7     .11       0
  1494.5     .09       0  1525.3     .15       0  2584.2     .17       0
Bank Sta=1494.5,1525.3
XS Rating Curve= 0 ,0
Exp/Cntr=0.3,0.1

Type RM Length L Ch R = 1 ,295908  ,570,570,570
BEGIN DESCRIPTION:
LAKE CREEK 572.0
END DESCRIPTION:
XS GIS Cut Line= 4
      3714039.94     10191570.68      3713961.82     10190937.03
      3712529.53     10190095.02      3711045.14     10189652.31
#Sta/Elev= 30
  2716.5   280.7  3139.3  273.17  4055.5  269.26  4091.5  272.01  4144.3  271.81
  4171.6  268.08  4217.9  270.41  4349.1  268.89  4758.9   269.2  4948.1  269.83
  4976.3  269.05  4997.2  261.58  5016.2  261.58  5019.9  266.21  5059.9  269.52
  5508.6  268.38  5529.5   265.7    5613  268.95  5640.8   263.7    5646  268.03
  5654.7   269.5  6164.1  268.81  6259.9  271.48    6274  272.88  6291.3  279.01
  6322.6  276.53  6373.4  281.74  6450.1   284.6  6478.1   289.3  6565.4   292.5
#Mann= 7 ,-1 , 0
  2716.5     .11       0  4055.5     .15       0  4349.1     .11       0
  4758.9     .15       0  4948.1     .11       0  4976.3     .06       0
  5059.9     .11       0
Bank Sta=4976.3,5059.9
XS Rating Curve= 0 ,0
Exp/Cntr=0.3,0.1

Type RM Length L Ch R = 1 ,295338  ,338,338,338
BEGIN DESCRIPTION:
LAKE CREEK 571.0
END DESCRIPTION:
XS GIS Cut Line= 3
      3714282.96     10190572.42      3712755.22     10189747.79
      3711132.38     10189339.91
#Sta/Elev= 30
  3256.6  295.06  3624.1   273.8  3793.6  269.86  4263.8  269.33  4449.4  264.52
  4558.9   267.4  4575.1  271.02    4597  266.49  4635.1  268.85  4760.7  263.12
  4804.5  263.22  4845.3  269.14  4957.7  269.21  4987.9  260.64  5006.9  260.64
  5038.6   268.7  5120.8  267.74    5126   263.9  5154.1  266.08  5203.1  264.87
  5208.3  269.46  5233.7  269.02  5526.1  265.34  6031.4  266.98  6340.7  271.45
    6382  279.46  6437.1  275.18  6464.4  279.32  6495.4  276.76    6666  283.62
#Mann= 6 ,-1 , 0
  3256.6     .11       0  4845.3     .15       0  4957.7     .09       0
  5038.6     .11       0  5154.1     .15       0  5233.7     .11       0
Bank Sta=4957.7,5038.6
XS Rating Curve= 0 ,0
Exp/Cntr=0.3,0.1

Type RM Length L Ch R = 1 ,295000  ,564,564,564
BEGIN DESCRIPTION:
LAKE CREEK 570.0
END DESCRIPTION:
XS GIS Cut Line= 3
      3714467.87     10190361.08      3712873.66     10189513.33
      3711017.83     10189011.07
#Sta/Elev= 30
  3194.4  300.99  3312.5  300.17  3542.9  288.27  3696.7  285.17  4031.3  268.27
  4509.1  268.19  4541.7  263.04  4580.1  268.06  4656.6  267.93  4819.5  268.43
    4926  269.85  4975.6  267.33  4987.6  259.55  5006.6  259.55  5016.4  265.17
  5037.1  267.58  5099.2  266.97    5120  269.94  5313.4  267.75  5617.2  268.12
  5689.8   264.8  5710.5  267.84  6064.6  265.96  6414.9  272.87  6456.4  278.83
  6487.5  273.56  6528.9  275.74  6556.9  281.31  6596.7   280.8  6922.6  303.34
#Mann= 7 ,-1 , 0
  3194.4     .11       0  4580.1     .17       0  4656.6     .11       0
  4819.5     .15       0  4975.6     .09       0  5037.1     .15       0
  5313.4     .11       0
Bank Sta=4975.6,5037.1
XS Rating Curve= 0 ,0
Exp/Cntr=0.3,0.1

Type RM Length L Ch R = 1 ,294436  ,667,667,667
BEGIN DESCRIPTION:
LAKE CREEK 569.0
END DESCRIPTION:
XS GIS Cut Line= 3
      3714187.48     10189860.62       3712989.6     10189096.75
      3711273.17     10188906.04
#Sta/Elev= 30
  3339.4  290.44  3570.6  284.84  3741.3  271.78  3871.8  266.06  4297.3   266.9
  4310.3  264.63    4389  267.57  4704.1  267.83  4722.4  265.31  4758.2  268.65
    4953   269.2  4983.2  266.42  4993.8  257.93  5012.8  257.93  5033.2  267.34
  5038.2  263.91  5043.6   266.8  5073.8  267.96  5244.2  266.54  5285.1  261.98
  5315.3  267.96  5405.8  264.91  6160.4  269.05  6220.8  271.48    6261  278.99
  6321.4  276.59  6381.8  283.99  6401.9  281.65  6432.1  286.87  6487.1  291.09
#Mann= 8 ,-1 , 0
  3339.4     .11       0  3741.3     .15       0  3871.8     .11       0
  4297.3     .17       0  4704.1     .15       0  4983.2     .09       0
  5033.2     .15       0  5244.2     .11       0
Bank Sta=4983.2,5033.2
XS Rating Curve= 0 ,0
Exp/Cntr=0.3,0.1

Type RM Length L Ch R = 1 ,293769  ,811,811,811
BEGIN DESCRIPTION:
LAKE CREEK 568.0
END DESCRIPTION:
XS GIS Cut Line= 3
      3714291.72     10189799.91      3713223.97     10188923.14
      3711262.49     10188541.26
#Sta/Elev= 30
    3167   290.5  3435.7  277.81    3567  271.12  3680.2   266.1  3738.2  266.65
  4120.8  266.42  4154.5  264.55    4185  266.39  4568.2  266.84  4729.9  267.68
  4829.9  269.08  4972.5  266.19  4982.7  262.62  4982.9  257.66  4983.4  257.06
  5002.4  257.06  5006.2  263.86  5010.7266.4778  5097.6  266.84  5227.2  266.58
  5247.6  263.35  5298.5  266.48  5553.2  264.66  5960.7  267.14  6174.7  272.93
  6266.4  279.88  6337.7  279.39  6378.4  283.64    6409  282.13  6546.9   289.1
#Mann= 11 ,-1 , 0
    3167     .17       0  3435.7     .11       0    3567     .15       0
  3738.2     .11       0  4154.5     .17       0    4185     .11       0
  4568.2     .17       0  4729.9     .15       0  4972.5     .09       0
  5010.7     .15       0  5097.6     .11       0
Bank Sta=4972.5,5010.7
XS Rating Curve= 0 ,0
Exp/Cntr=0.3,0.1

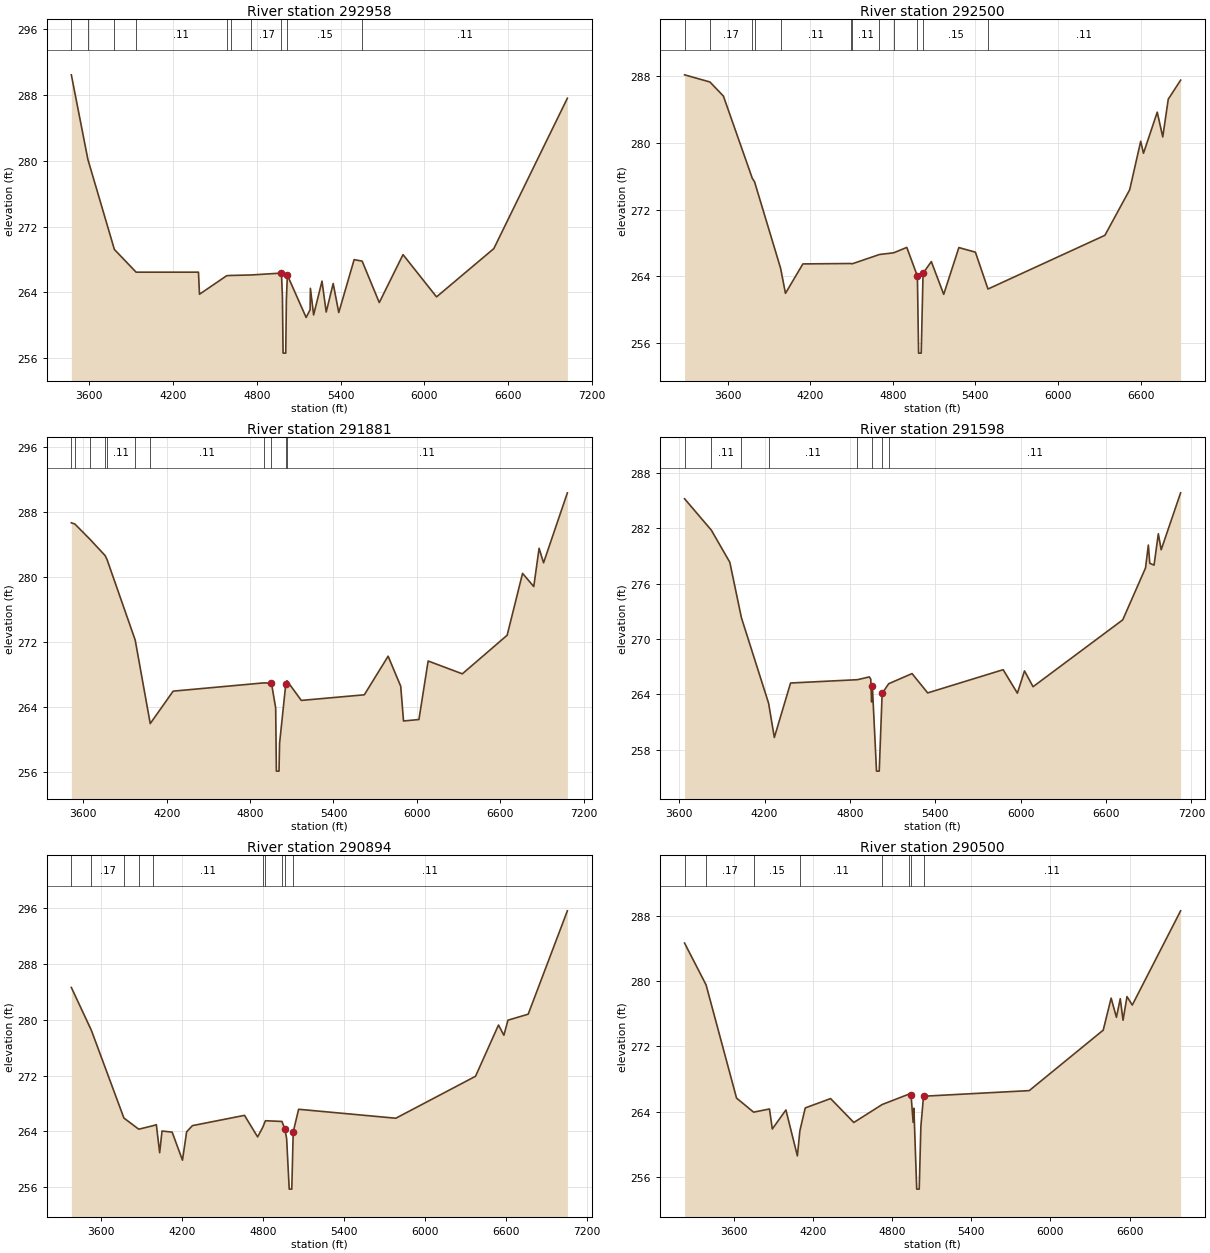
Type RM Length L Ch R = 1 ,292958  ,458,458,458
BEGIN DESCRIPTION:
LAKE CREEK 567.0
END DESCRIPTION:
XS GIS Cut Line= 3
      3714317.74     10189678.37       3713119.8     10188454.39
      3711281.24     10188471.74
#Sta/Elev= 30
  3472.2  290.42  3590.5  280.16  3780.3  269.22  3935.9  266.46  4382.4  266.46
  4389.6  263.78  4584.5  266.03  4611.8  266.06  4760.9  266.12  4976.5  266.35
  4983.5  263.46  4988.1  256.63  5007.1  256.63  5011.8  263.18  5018.9   266.1
  5153.2  260.96  5181.5  261.89  5183.7   264.5  5206.8  261.27  5266.8  265.37
  5296.8  261.62  5346.8  265.08  5386.8  261.56  5496.8  267.98  5554.2   267.8
  5676.8  262.77  5846.8  268.59  6086.8  263.46  6496.9  269.32  7023.5  287.58
#Mann= 10 ,-1 , 0
  3472.2     .17       0  3590.5     .11       0  3780.3     .15       0
  3935.9     .11       0  4584.5     .17       0  4611.8     .11       0
  4760.9     .17       0  4976.5     .09       0  5018.9     .15       0
  5554.2     .11       0
Bank Sta=4976.5,5018.9
XS Rating Curve= 0 ,0
Exp/Cntr=0.3,0.1

Type RM Length L Ch R = 1 ,292500  ,619,619,619
BEGIN DESCRIPTION:
LAKE CREEK 566.0
END DESCRIPTION:
XS GIS Cut Line= 3
      3714803.82     10188853.69      3713178.04     10188315.94
      3711288.24     10188393.63
#Sta/Elev= 30
  3287.6  288.17  3471.9  287.31  3569.8  285.62  3779.8  275.75  3795.8  275.35
  3985.1  264.98  4020.6  261.96    4147  265.49  4498.4  265.54  4504.7   265.5
  4703.7  266.62  4806.3  266.82  4902.1  267.47  4979.1  264.03  4987.8  254.79
  5006.8  254.79  5020.2  264.37  5080.3  265.77  5170.3  261.84  5280.4  267.45
  5400.5   266.9  5491.9  262.48  6341.3  268.92  6521.5  274.39  6601.5   280.2
  6621.6  278.76  6721.6  283.69  6761.7  280.72  6801.7  285.25  6891.4  287.53
#Mann= 12 ,-1 , 0
  3287.6     .11       0  3471.9     .17       0  3779.8     .15       0
  3795.8     .17       0  3985.1     .11       0  4498.4     .17       0
  4504.7     .11       0  4703.7     .17       0  4806.3     .15       0
  4979.1     .09       0  5020.2     .15       0  5491.9     .11       0
Bank Sta=4979.1,5020.2
XS Rating Curve= 0 ,0
Exp/Cntr=0.3,0.1

Type RM Length L Ch R = 1 ,291881  ,283,283,283
BEGIN DESCRIPTION:
LAKE CREEK 565.0
END DESCRIPTION:
XS GIS Cut Line= 3
      3714656.29     10188714.82      3713250.01     10188011.68
       3711267.8     10188261.08
#Sta/Elev= 30
  3513.6  286.69  3538.4  286.55  3648.5  284.65  3756.8  282.66  3770.6  282.17
  3973.3  272.26  4081.5  261.99  4246.4  265.98  4900.8     267  4954.1  266.94
  4984.3  263.91  4989.3  256.14  5008.3  256.14  5012.3  259.56    5057  266.85
  5065.5  267.26  5168.7  264.84  5622.2  265.53  5793.6  270.28  5884.3  266.58
  5904.4  262.31  6015.3  262.49  6081.6  269.69  6327.7  268.11  6650.3  272.86
  6761.1  280.47  6841.8  278.85  6880.2  283.56  6912.3  281.77  7083.7  290.38
#Mann= 11 ,-1 , 0
  3513.6     .11       0  3538.4     .17       0  3648.5     .11       0
  3756.8     .17       0  3770.6     .11       0  3973.3     .15       0
  4081.5     .11       0  4900.8     .15       0  4954.1     .09       0
    5057     .11       0  5065.5     .11       0
Bank Sta=4954.1,5057
XS Rating Curve= 0 ,0
Exp/Cntr=0.3,0.1

Type RM Length L Ch R = 1 ,291598  ,704,704,704
BEGIN DESCRIPTION:
LAKE CREEK 564.0
END DESCRIPTION:
XS GIS Cut Line= 3
      3714638.89     10188645.36      3713684.04     10187898.84
      3711411.29     10187838.11
#Sta/Elev= 30
  3638.2  285.17  3826.4  281.77  3956.1   278.3  4037.5  272.31  4228.7  263.05
    4269  259.35    4383  265.24  4852.8   265.6  4936.5   265.9  4946.5  265.65
  4952.6  263.19  4957.6  264.95    4987  255.71    5006  255.71  5026.5  264.11
  5072.2  265.16  5236.6  266.26  5346.6  264.17  5876.8  266.68  5976.8  264.14
  6026.8  266.55  6086.9  264.84  6717.1  272.07  6877.1  277.68  6897.2  280.16
  6907.2  278.19  6937.2  277.99  6967.2  281.38  6987.2  279.65  7123.8  285.81
#Mann= 8 ,-1 , 0
  3638.2     .17       0  3826.4     .11       0  4037.5     .15       0
  4228.7     .11       0  4852.8     .15       0  4957.6     .09       0
  5026.5     .15       0  5072.2     .11       0
Bank Sta=4957.6,5026.5
XS Rating Curve= 0 ,0
Exp/Cntr=0.3,0.1

Type RM Length L Ch R = 1 ,290894  ,394,394,394
BEGIN DESCRIPTION:
LAKE CREEK 563.0
END DESCRIPTION:
XS GIS Cut Line= 3
      3714734.41     10188081.14      3713250.01     10187508.21
      3711167.81     10187561.07
#Sta/Elev= 30
  3381.5  284.59  3529.9  278.46  3770.8  265.92  3880.7  264.32    3985  264.81
  4011.1  264.97  4035.7  260.96  4053.1  264.06  4128.1   263.9  4204.7  259.89
  4235.3  263.94  4278.2  264.83  4664.1   266.3  4761.2  263.22  4799.3  264.59
  4818.9  265.53  4941.3  265.43  4964.2   264.3  4976.2  262.95  4995.3  255.75
  5014.3  255.75  5024.8  263.92  5064.8  267.17  5785.1  265.89  6375.2  271.89
  6545.3  279.22  6585.3  277.76  6615.3  279.91  6765.4  280.77  7055.5  295.55
#Mann= 10 ,-1 , 0
  3381.5     .11       0  3529.9     .17       0  3770.8     .15       0
  3880.7     .17       0    3985     .11       0  4799.3     .15       0
  4818.9     .11       0  4941.3     .15       0  4964.2     .06       0
  5024.8     .11       0
Bank Sta=4964.2,5024.8
XS Rating Curve= 0 ,0
Exp/Cntr=0.3,0.1

Type RM Length L Ch R = 1 ,290500  ,1529,1529,1529
BEGIN DESCRIPTION:
LAKE CREEK 562.0
END DESCRIPTION:
XS GIS Cut Line= 3
      3714734.37     10188029.04      3713185.98     10187167.17
      3711202.09     10187256.44
#Sta/Elev= 30
  3227.9  284.72  3390.8  279.58  3621.7  265.65    3751  263.92    3871  264.31
  3892.7  261.85  3995.6  264.19  4082.5  258.54  4101.3  261.62    4142  264.44
  4334.1  265.59  4510.1  262.65    4725  264.86  4924.7  266.12  4943.5  266.08
  4959.5  262.66  4965.2  264.41  4986.6  254.45  5005.6  254.45  5018.1  262.16
  5038.2  265.88    5839  266.57  6399.5  274.01  6459.6  277.95  6499.6  275.59
  6528.7  277.88  6549.7  275.23  6579.7  278.14  6619.8   277.1  6985.9  288.69
#Mann= 8 ,-1 , 0
  3227.9     .11       0  3390.8     .17       0    3751     .15       0
  4101.3     .11       0    4725     .15       0  4924.7     .11       0
  4943.5     .06       0  5038.2     .11       0
Bank Sta=4943.5,5038.2
XS Rating Curve= 0 ,0
Exp/Cntr=0.3,0.1

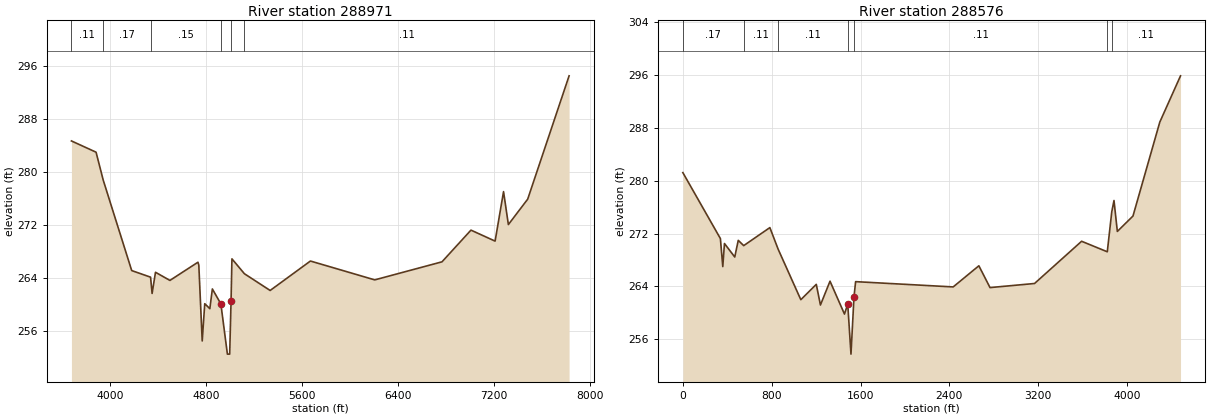
Type RM Length L Ch R = 1 ,288971  ,471,471,471
BEGIN DESCRIPTION:
LAKE CREEK 560.0
END DESCRIPTION:
XS GIS Cut Line= 3
      3714767.83     10188011.05      3713414.94     10186588.07
      3711244.81     10186813.77
#Sta/Elev= 30
  3680.3   284.7  3885.5     283    3945  278.79  4182.4  265.11  4339.5  264.11
  4352.3  261.65  4380.6  264.85  4500.8  263.62  4734.2  266.37  4741.4  265.94
  4769.7  254.47  4790.8   260.1  4833.2  259.35  4854.3  262.33  4925.1  260.07
  4979.5  252.48  4998.5  252.48    5010  260.56  5017.3  266.88  5121.2  264.63
  5335.6   262.1    5671  266.55  6206.7   263.7  6766.9  266.43  7008.2  271.22
  7209.3  269.56  7279.6  277.04  7319.8  272.06  7480.7   275.9  7825.6  294.54
#Mann= 6 ,-1 , 0
  3680.3     .11       0    3945     .17       0  4339.5     .15       0
  4925.1     .09       0    5010     .15       0  5121.2     .11       0
Bank Sta=4925.1,5010
XS Rating Curve= 0 ,0
Exp/Cntr=0.3,0.1

Type RM Length L Ch R = 1 ,288576  ,319,319,319
BEGIN DESCRIPTION:
LAKE CREEK 559.0
END DESCRIPTION:
XS GIS Cut Line= 4
      3715362.46     10187546.63      3714157.35     10186852.35
        3713658.     10186483.91       3711201.4     10186744.32
#Sta/Elev= 30
       0  281.22     338  271.24   359.5     267   374.6  270.49   467.3  268.45
   498.9  270.97   547.8  270.17   783.4   272.9     858  269.63  1062.1  261.99
  1201.4  264.31  1238.8  261.18    1325  264.79  1455.2  259.81  1484.5  261.33
  1513.8  253.75  1540.8  262.39  1555.5  264.72  2433.9  263.92  2665.2  267.12
  2765.7  263.82  3166.6  264.44  3590.3  270.83  3821.6  269.24  3861.8  275.28
  3881.9     277  3912.1  272.32  4052.9  274.65  4294.2  288.86    4481  295.87
#Mann= 7 ,-1 , 0
       0     .17       0   547.8     .11       0     858     .11       0
  1484.5     .09       0  1540.8     .11       0  3821.6     .17       0
  3861.8     .11       0
Bank Sta=1484.5,1540.8
XS Rating Curve= 0 ,0
Exp/Cntr=0.3,0.1