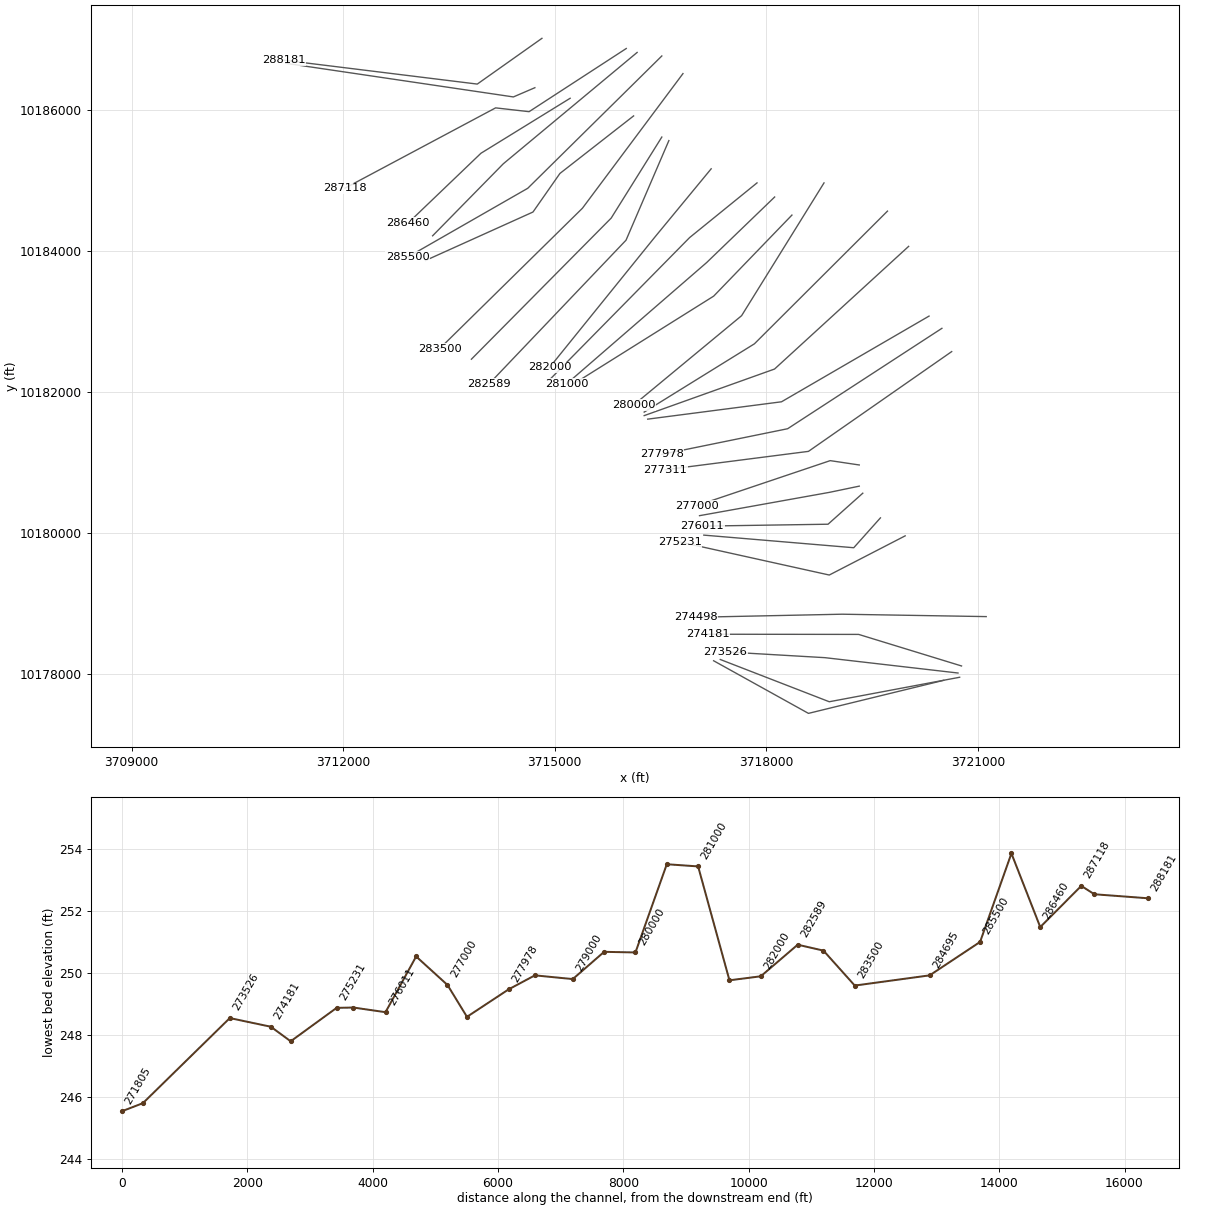
HEC-RAS study LAKE CREEK.prj: LAKE CREEK Base Level Engineering

--- LAKE CREEK.g01 (geometry) --- (continued)

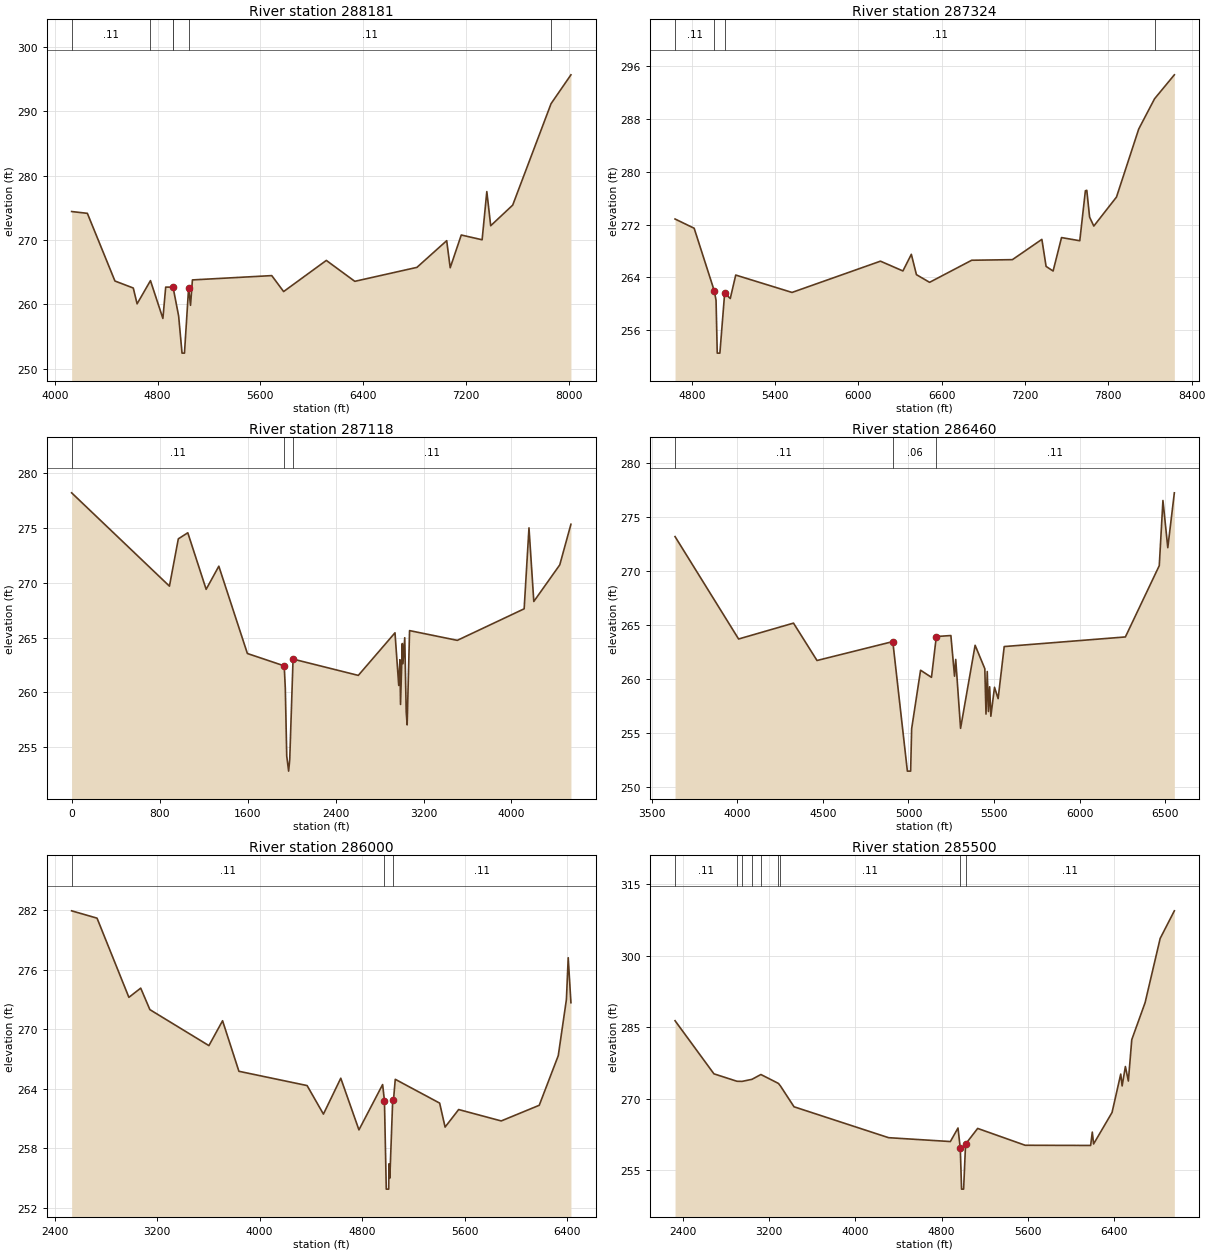
Type RM Length L Ch R = 1 ,288181  ,857,857,857
BEGIN DESCRIPTION:
LAKE CREEK 558.0
END DESCRIPTION:
XS GIS Cut Line= 3
      3714817.85     10187011.07      3713901.05     10186362.38
      3711157.95     10186700.93
#Sta/Elev= 30
  4130.7  274.43  4253.2  274.15  4467.9  263.63  4610.7  262.54  4640.3  260.08
  4744.4  263.69  4841.2  257.81    4863  262.68  4918.6  262.68  4919.6  262.74
  4963.7   258.2  4990.2  252.42  5009.2  252.42  5041.5  262.58  5056.3  259.85
    5071   263.8  5688.7  264.47    5781  261.99  6113.5  266.83  6335.1  263.58
  6818.8  265.75  7050.5   269.9  7077.9  265.69    7164  270.78  7326.3  270.04
  7362.9  277.53  7393.1  272.22  7564.4  275.43  7863.1   291.2  8017.7  295.68
#Mann= 6 ,-1 , 0
  4130.7     .11       0  4744.4     .15       0  4918.6     .11       0
  4919.6     .06       0  5041.5     .11       0  7863.1     .17       0
Bank Sta=4919.6,5041.5
XS Rating Curve= 0 ,0
Exp/Cntr=0.3,0.1

Type RM Length L Ch R = 1 ,287324  ,209,209,209
BEGIN DESCRIPTION:
LAKE CREEK 557.0
END DESCRIPTION:
XS GIS Cut Line= 3
      3714717.87     10186311.08      3714413.21     10186180.09
      3711184.04     10186657.52
#Sta/Elev= 30
  4679.5  272.84  4817.2  271.44  4962.5  261.94  4974.8  260.53  4983.4  252.55
  5002.4  252.55  5036.8  261.62  5077.2  260.81  5116.5  264.36    5522  261.73
  6158.8  266.46  6320.6  264.98  6381.2   267.5    6418  264.42  6512.6  263.26
  6815.9   266.6  7109.1  266.69  7321.3  269.76  7351.7  265.67  7402.2  264.97
  7462.9  270.03  7594.3  269.55  7634.7  277.11  7644.8  277.18    7665  273.13
  7695.4  271.77  7858.7  276.16  8018.8  286.45  8132.9  291.03  8275.4  294.65
#Mann= 4 ,-1 , 0
  4679.5     .11       0  4962.5     .06       0  5036.8     .11       0
  8132.9     .17       0
Bank Sta=4962.5,5036.8
XS Rating Curve= 0 ,0
Exp/Cntr=0.3,0.1

Type RM Length L Ch R = 1 ,287118  ,655,655,655
BEGIN DESCRIPTION:
LAKE CREEK 556.0
END DESCRIPTION:
XS GIS Cut Line= 4
      3716013.58     10186866.73       3714635.8       10185971.
      3714160.95     10186024.96      3712026.05     10184886.68
#Sta/Elev= 30
       0  278.23   889.5  269.71   970.3  274.03  1056.5  274.58  1223.4  269.42
  1338.6  271.53  1598.3  263.56  1933.2  262.43  1943.2  260.39  1956.2   254.2
  1973.4  252.82  1983.5  253.89  2013.7  263.05  2607.1  261.56  2940.7  265.45
  2974.7  260.64  2985.4  262.99    2991  258.91  3007.3  264.47    3013  262.63
  3029.3     265  3042.7  258.23  3051.2  257.04  3073.2  265.65  3507.4  264.76
  4115.3  267.64  4159.2  275.03  4203.1  268.31    4439  271.65  4540.7  275.36
#Mann= 3 ,-1 , 0
       0     .11       0  1933.2     .06       0  2013.7     .11       0
Bank Sta=1933.2,2013.7
XS Rating Curve= 0 ,0
Exp/Cntr=0.3,0.1

Type RM Length L Ch R = 1 ,286460  ,460,460,460
BEGIN DESCRIPTION:
LAKE CREEK 555.0
END DESCRIPTION:
XS GIS Cut Line= 3
      3715217.89      10186161.1      3713953.14     10185381.47
      3712921.48     10184393.16
#Sta/Elev= 30
  3637.4   273.2  4008.3  263.72  4328.8  265.19    4466  261.73  4908.4  263.48
  4993.5  251.49  5012.5  251.49  5018.4  255.41  5070.5  260.83  5134.2  260.17
  5162.5  263.95  5247.4  264.04  5268.8  260.28  5275.7  261.83    5304  255.45
  5388.9  263.14  5445.5  260.97  5452.4  256.77  5459.7  260.71  5466.6  257.01
  5473.8   259.3  5480.7  256.57  5502.1  259.25  5523.2   258.2  5558.7  263.02
    6266  263.91  6463.8  270.51  6485.2  276.54  6513.5  272.17  6551.8  277.25
#Mann= 3 , 0 , 0
  3637.4     .11       0  4908.4     .06       0  5162.5     .11       0
Bank Sta=4908.4,5162.5
XS Rating Curve= 0 ,0
Exp/Cntr=0.3,0.1

Type RM Length L Ch R = 1 ,286000  ,500,500,500
BEGIN DESCRIPTION:
LAKE CREEK 554.0
END DESCRIPTION:
XS GIS Cut Line= 3
      3716167.82     10186811.05      3714270.08     10185232.26
      3713267.88      10184211.1
#Sta/Elev= 30
  2531.4  281.95  2729.9  281.21  2978.6  273.22    3071  274.15  3142.6  271.98
  3603.5  268.35  3710.2  270.86  3837.8  265.76  4370.3  264.32  4497.9  261.44
  4633.3  265.06  4775.2  259.85  4960.1  264.42  4974.4  262.79  4988.7  253.87
  5007.7  253.87  5009.5  256.42  5016.5  254.98  5037.8  262.47  5044.8  262.84
  5058.9  264.95  5405.5  262.55    5448  260.13    5554   261.9  5886.3  260.75
  6183.3  262.33  6331.9  267.34  6395.5     273  6409.6  277.22  6430.8  272.68
#Mann= 3 , 0 , 0
  2531.4     .11       0  4974.4     .06       0  5044.8     .11       0
Bank Sta=4974.4,5044.8
XS Rating Curve= 0 ,0
Exp/Cntr=0.3,0.1

Type RM Length L Ch R = 1 ,285500  ,805,805,805
BEGIN DESCRIPTION:
LAKE CREEK 553.0
END DESCRIPTION:
XS GIS Cut Line= 3
      3716517.84     10186761.06      3714616.59     10184884.59
      3712917.87     10183911.08
#Sta/Elev= 30
  2328.7  286.33  2689.3  275.19  2903.1  273.63  2951.1  273.61    3042  274.04
  3124.6  275.05  3287.3  273.18  3305.4  272.66  3431.8  268.28  4308.7   261.8
  4881.4  260.99  4952.1  263.83  4973.3  259.54  4985.1  251.01  5004.1  251.01
  5022.3  260.46  5134.5  263.74  5574.7  260.21  6181.8  260.17  6197.2  262.97
  6209.1  260.48  6380.3  267.09  6460.9  275.14  6473.8  272.65    6504  276.73
  6531.5  273.68    6563  282.35  6686.7  290.12  6826.3  303.58  6957.9  309.38
#Mann= 9 ,-1 , 0
  2328.7     .11       0  2903.1     .17       0  2951.1     .11       0
    3042     .17       0  3124.6     .11       0  3287.3     .17       0
  3305.4     .11       0  4973.3     .06       0  5022.3     .11       0
Bank Sta=4973.3,5022.3
XS Rating Curve= 0 ,0
Exp/Cntr=0.3,0.1

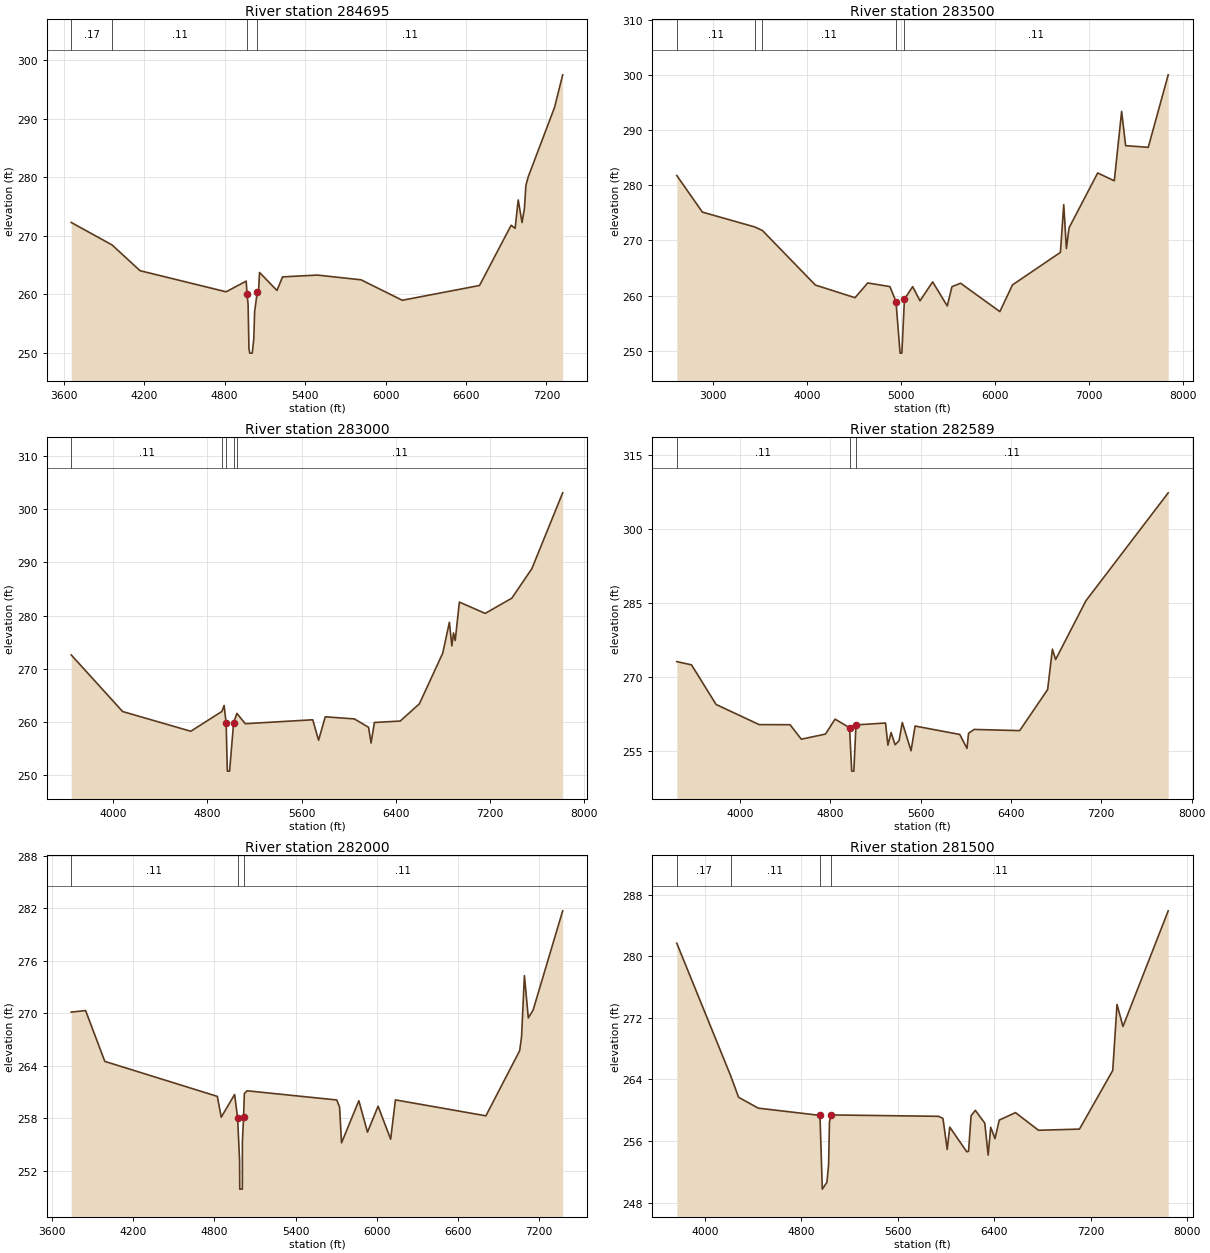
Type RM Length L Ch R = 1 ,284695  ,1195,1195,1195
BEGIN DESCRIPTION:
LAKE CREEK 552.0
END DESCRIPTION:
XS GIS Cut Line= 4
      3716117.83     10185911.05      3715072.93     10185095.02
      3714690.98     10184548.14      3713167.83     10183861.06
#Sta/Elev= 30
    3657  272.28  3961.7  268.43  4169.8  264.03  4811.6  260.42  4961.2  262.25
  4967.5   260.1  4975.6  258.25  4981.9  250.78  4987.5  249.93  5006.5  249.93
    5018  252.39  5024.2  257.03 5043.77 260.344  5053.7  260.65  5060.8  263.73
  5190.7  260.65  5232.5  262.97  5491.6  263.28  5817.8  262.47    6125  258.97
  6700.8   261.5  6936.8  271.81  6966.2  271.27  6989.3  276.13  7017.9  272.26
  7035.5  274.64  7046.5  278.61  7064.2   280.1  7260.2  291.96  7320.8  297.53
#Mann= 4 ,-1 , 0
    3657     .17       0  3961.7     .11       0  4967.5     .06       0
 5043.77     .11       0
Bank Sta=4967.5,5043.77
XS Rating Curve= 0 ,0
Exp/Cntr=0.3,0.1

Type RM Length L Ch R = 1 ,283500  ,500,500,500
BEGIN DESCRIPTION:
LAKE CREEK 550.0
END DESCRIPTION:
XS GIS Cut Line= 3
      3716817.87      10186511.1      3715391.86     10184601.62
      3713367.86     10182611.08
#Sta/Elev= 30
  2616.8  281.77  2888.9  275.14  3445.7  272.45  3527.5   271.8  4089.6  261.93
  4510.7  259.64  4646.2  262.31  4881.7  261.65  4946.4  258.92  4989.7   249.6
  5008.7   249.6 5035.85259.3777  5123.4  261.64  5201.3  259.08  5335.6   262.5
  5491.2  258.14  5540.6  261.63  5632.6  262.26  6049.8  257.12  6184.1  261.96
  6693.2  267.84  6728.7  276.49    6757  268.53  6785.2  272.29  7089.3  282.23
    7266  280.81  7343.9  293.38  7386.3  287.17  7626.7  286.87  7838.8     300
#Mann= 5 ,-1 , 0
  2616.8     .11       0  3445.7     .17       0  3527.5     .11       0
  4946.4     .09       0 5035.85     .11       0
Bank Sta=4946.4,5035.85
XS Rating Curve= 0 ,0
Exp/Cntr=0.3,0.1

Type RM Length L Ch R = 1 ,283000  ,411,411,411
BEGIN DESCRIPTION:
LAKE CREEK 549.0
END DESCRIPTION:
XS GIS Cut Line= 3
      3716517.83     10185611.04       3715800.1     10184462.33
      3713817.85     10182461.07
#Sta/Elev= 30
  3645.5  272.59  4081.7  261.94  4660.3  258.23  4923.8  261.95  4943.3  263.08
  4960.4259.7102  4970.4  250.73  4989.4  250.73  5023.7  259.81  5051.5  261.59
  5122.7  259.65  5695.4  260.39    5745  256.54  5801.5  260.95    6049  260.55
  6169.3  258.97  6190.4  256.02  6218.7  259.88  6437.9  260.15  6600.6  263.39
  6798.6  272.91  6855.1  278.73  6876.3  274.29  6890.5  276.72  6904.6   275.3
    6940  282.53  7159.2   280.4  7385.4  283.27  7555.2  288.81  7816.8  303.08
#Mann= 5 ,-1 , 0
  3645.5     .11       0  4923.8     .17       0  4960.4     .09       0
  5023.7     .17       0  5051.5     .11       0
Bank Sta=4960.4,5023.7
XS Rating Curve= 0 ,0
Exp/Cntr=0.3,0.1

Type RM Length L Ch R = 1 ,282589  ,589,589,589
BEGIN DESCRIPTION:
LAKE CREEK 548.0
END DESCRIPTION:
XS GIS Cut Line= 3
      3716617.87     10185561.12      3716010.43     10184148.84
      3714067.86     10182111.08
#Sta/Elev= 30
  3439.6  273.12  3570.3  272.46    3788  264.43    4169  260.35    4443  260.33
  4542.6  257.39  4756.8  258.43  4841.4  261.46    4970  259.72    4989  250.92
    5008  250.92  5026.8  260.29  5288.5  260.67  5309.6  256.19  5337.9  258.74
  5373.4  256.26  5408.7  257.09    5437  260.78  5514.7  255.05  5550.2  260.06
  5946.2  258.35  6010.1  255.53  6023.9  258.59  6073.6  259.37  6476.8  259.13
  6724.3  267.45  6766.8  275.64  6795.1  273.54  7063.7  285.46  7792.3  307.33
#Mann= 3 , 0 , 0
  3439.6     .11       0    4970     .06       0  5026.8     .11       0
Bank Sta=4970,5026.8
XS Rating Curve= 0 ,0
Exp/Cntr=0.3,0.1

Type RM Length L Ch R = 1 ,282000  ,500,500,500
BEGIN DESCRIPTION:
LAKE CREEK 547.0
END DESCRIPTION:
XS GIS Cut Line= 3
      3717217.82     10185161.03      3716417.42     10184190.38
      3714926.46     10182344.64
#Sta/Elev= 30
  3741.9  270.13    3848  270.31    3990   264.5  4821.3   260.5    4850  258.12
    4949  260.72  4971.2  258.02  4985.6   253.2  4986.8   249.9  5005.8   249.9
  5006.3   250.7  5006.4  255.28  5015.1258.1126  5020.8  260.82  5041.6  261.14
  5703.6  260.09  5724.4  259.28  5738.8  255.19  5866.7     260  5930.7  256.41
    6009  259.38  6101.8  255.61    6137   260.1  6805.4  258.28  7054.8  265.72
  7068.8  267.29    7090   274.3  7118.8  269.47    7154  270.35  7372.7  281.71
#Mann= 3 , 0 , 0
  3741.9     .11       0  4971.2     .06       0  5015.1     .11       0
Bank Sta=4971.2,5015.1
XS Rating Curve= 0 ,0
Exp/Cntr=0.3,0.1

Type RM Length L Ch R = 1 ,281500  ,500,500,500
BEGIN DESCRIPTION:
LAKE CREEK 546.0
END DESCRIPTION:
XS GIS Cut Line= 3
      3717867.86     10184961.08      3716911.33     10184185.11
      3714917.85     10182161.06
#Sta/Elev= 30
  3768.3  281.69  4213.8  264.53  4280.6  261.69  4443.6  260.28  4955.1  259.34
  4974.4  249.77  5012.4  250.65  5026.5  252.94  5033.6  258.48  5045.8259.3994
  5938.7  259.22  5974.1  258.95  6009.4  254.92  6030.6  257.82    6172  254.61
  6186.2  254.68  6207.4   259.3  6242.7  259.99  6320.6  258.34  6348.9  254.19
    6370   257.8  6405.4  256.32  6440.8  258.73  6575.2   259.7    6766  257.41
  7105.5  257.56  7381.2  265.17  7416.6  273.74  7466.1  270.88  7840.9  285.89
#Mann= 4 ,-1 , 0
  3768.3     .17       0  4213.8     .11       0  4955.1     .06       0
  5045.8     .11       0
Bank Sta=4955.1,5045.8
XS Rating Curve= 0 ,0
Exp/Cntr=0.3,0.1

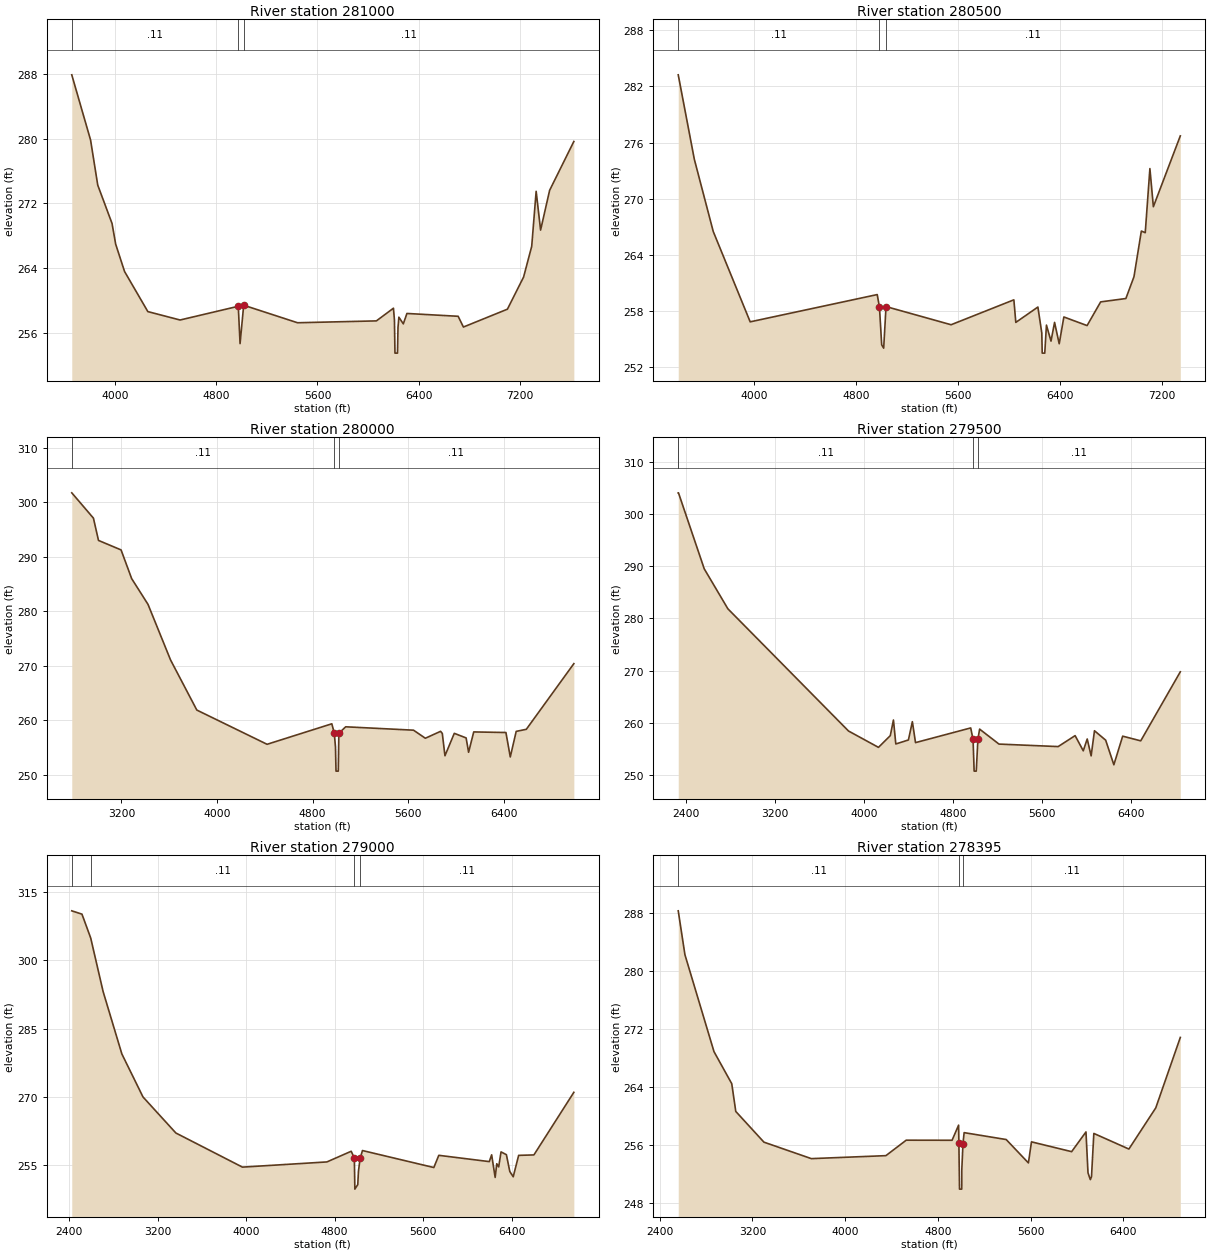
Type RM Length L Ch R = 1 ,281000  ,500,500,500
BEGIN DESCRIPTION:
LAKE CREEK 545.0
END DESCRIPTION:
XS GIS Cut Line= 3
      3718117.88      10184761.1      3717152.37     10183830.33
      3715167.83     10182111.05
#Sta/Elev= 30
  3658.9   287.9  3807.5  279.83  3864.1  274.25  3977.3  269.49  4005.6  266.95
  4076.1  263.55    4260  258.59  4514.7  257.55  4974.4  259.25  4988.6  254.63
  5017.2  259.38  5442.6  257.21  6065.7  257.44  6200.5  259.01  6208.2  257.55
  6212.4  253.45  6232.4  253.45  6236.4  256.63  6243.3   257.9  6278.4  257.07
  6306.9  258.36  6711.6  258.01  6753.3  256.68  7100.9  258.89  7228.7  262.87
  7292.8  266.67  7327.9  273.48    7363  268.68  7434.3   273.6  7625.7  279.65
#Mann= 3 , 0 , 0
  3658.9     .11       0  4974.4     .06       0  5017.2     .11       0
Bank Sta=4974.4,5017.2
XS Rating Curve= 0 ,0
Exp/Cntr=0.3,0.1

Type RM Length L Ch R = 1 ,280500  ,500,500,500
BEGIN DESCRIPTION:
LAKE CREEK 544.0
END DESCRIPTION:
XS GIS Cut Line= 3
      3718362.87     10184504.75      3717253.51     10183355.54
      3715267.85     10182111.07
#Sta/Elev= 30
  3402.7  283.23  3529.1  274.21  3677.6   266.5  3967.5  256.86  4964.6  259.77
 4982.06  258.42  4999.6  254.41  5015.2  254.05 5033.62  258.49  5544.4  256.55
    6037  259.21  6052.3   256.8  6225.6  258.44  6256.2  255.67  6259.5  253.52
  6279.5  253.52  6292.7  256.51  6328.5   254.8  6356.4   256.8  6392.9  254.52
  6429.4  257.38  6611.7  256.46  6718.2  258.99  6916.2  259.35  6979.8  261.68
  7037.6  266.55  7068.2  266.38  7104.7  273.22  7131.9  269.15  7343.4  276.71
#Mann= 3 , 0 , 0
  3402.7     .11       0 4982.06     .06       0 5033.62     .11       0
Bank Sta=4982.06,5033.62
XS Rating Curve= 0 ,0
Exp/Cntr=0.3,0.1

Type RM Length L Ch R = 1 ,280000  ,500,500,500
BEGIN DESCRIPTION:
LAKE CREEK 543.0
END DESCRIPTION:
XS GIS Cut Line= 3
      3718817.85     10184961.06      3717649.51     10183078.43
      3716117.86     10181811.08
#Sta/Elev= 30
  2784.3  301.71  2965.6  297.07  3008.1  292.98  3197.1  291.24  3285.7  285.98
  3422.7  281.25  3611.6  271.05  3831.3  261.87  4419.5  255.59  4961.6  259.35
  4982.2257.6608  4992.3  255.06  4996.7  250.67  5015.7  250.67  5020.5  257.62
  5077.8   258.8  5645.7  258.18  5744.7   256.7  5872.4  257.97  5886.7  257.58
  5908.9  253.49    5987   257.6    6086  256.76  6106.8  254.13  6149.8  257.86
  6419.4  257.75  6455.8  253.27  6505.4  257.96  6590.1  258.34    6988  270.38
#Mann= 3 , 0 , 0
  2784.3     .11       0  4982.2     .06       0  5020.5     .11       0
Bank Sta=4982.2,5020.5
XS Rating Curve= 0 ,0
Exp/Cntr=0.3,0.1

Type RM Length L Ch R = 1 ,279500  ,500,500,500
BEGIN DESCRIPTION:
LAKE CREEK 542.0
END DESCRIPTION:
XS GIS Cut Line= 3
      3719717.85     10184561.07      3717830.62     10182678.99
      3716267.88     10181711.09
#Sta/Elev= 30
  2334.7   304.1  2336.9   304.1    2568  289.51  2780.2  281.84    3862  258.39
  4130.7  255.25  4236.8   257.5  4265.1   260.5  4286.3   255.9  4399.4  256.67
  4434.8  260.18  4463.1  256.16  4958.1  258.98  4979.3  256.76  4988.9  250.69
  5007.9  250.69  5022.7  256.82  5038.1  258.75  5211.8  255.88  5742.3   255.4
  5894.7   257.5  5967.8  254.59  6003.1  256.86  6038.4  253.62  6068.4  258.44
  6168.8  256.63  6242.1  251.91  6321.3   257.4  6483.2   256.5  6838.2  269.75
#Mann= 4 ,-1 , 0
  2334.7     .17       0  2336.9     .11       0  4979.3     .06       0
  5022.7     .11       0
Bank Sta=4979.3,5022.7
XS Rating Curve= 0 ,0
Exp/Cntr=0.3,0.1

Type RM Length L Ch R = 1 ,279000  ,605,605,605
BEGIN DESCRIPTION:
LAKE CREEK 541.0
END DESCRIPTION:
XS GIS Cut Line= 3
      3720017.87     10184061.08      3718116.51     10182321.61
      3716267.87     10181661.08
#Sta/Elev= 30
    2423   310.9  2515.2  310.17  2594.2  304.94  2706.4  293.18    2876  279.48
  3067.1  270.04  3364.4  262.13  3966.3  254.64  4730.3  255.78  4949.8  258.12
  4978.2  256.64  4982.9  249.81  5009.2   250.8  5015.5  253.76  5030.4  256.54
  5051.7  258.28  5697.1  254.55  5741.9  257.23  6198.5  255.85  6219.8  257.34
  6251.6  252.38  6266.1  255.38  6283.5  254.69  6304.7  257.98  6353.2  257.37
    6384  253.68  6414.8  252.52    6464  257.22  6602.1  257.32  6963.1  271.06
#Mann= 4 ,-1 , 0
    2423     .17       0  2594.2     .11       0  4978.2     .06       0
  5030.4     .11       0
Bank Sta=4978.2,5030.4
XS Rating Curve= 0 ,0
Exp/Cntr=0.3,0.1

Type RM Length L Ch R = 1 ,278395  ,417,417,417
BEGIN DESCRIPTION:
LAKE CREEK 540.0
END DESCRIPTION:
XS GIS Cut Line= 3
      3720307.28     10183072.43      3718215.29     10181857.17
      3716317.84     10181611.07
#Sta/Elev= 30
  2559.4  288.26  2617.1  282.22  2867.9  268.87  3021.3  264.45    3056  260.63
  3298.9   256.4  3708.1  254.13  4351.3  254.54  4526.8  256.67  4922.5  256.66
  4978.8  258.74 4981.32256.2481  4986.8  249.93  5005.8  249.93  5006.3  250.73
  5006.4  252.56  5016.5  256.19  5026.6  257.71  5389.6  256.76  5581.2  253.54
  5607.8  256.44  5954.3  255.09    6078  257.81  6095.5  252.18  6115.6  251.24
  6125.7  251.65  6145.9   257.6  6448.4  255.45  6680.3  261.12  6892.1  270.82
#Mann= 3 , 0 , 0
  2559.4     .11       0 4981.32     .06       0  5016.5     .11       0
Bank Sta=4981.32,5016.5
XS Rating Curve= 0 ,0
Exp/Cntr=0.3,0.1

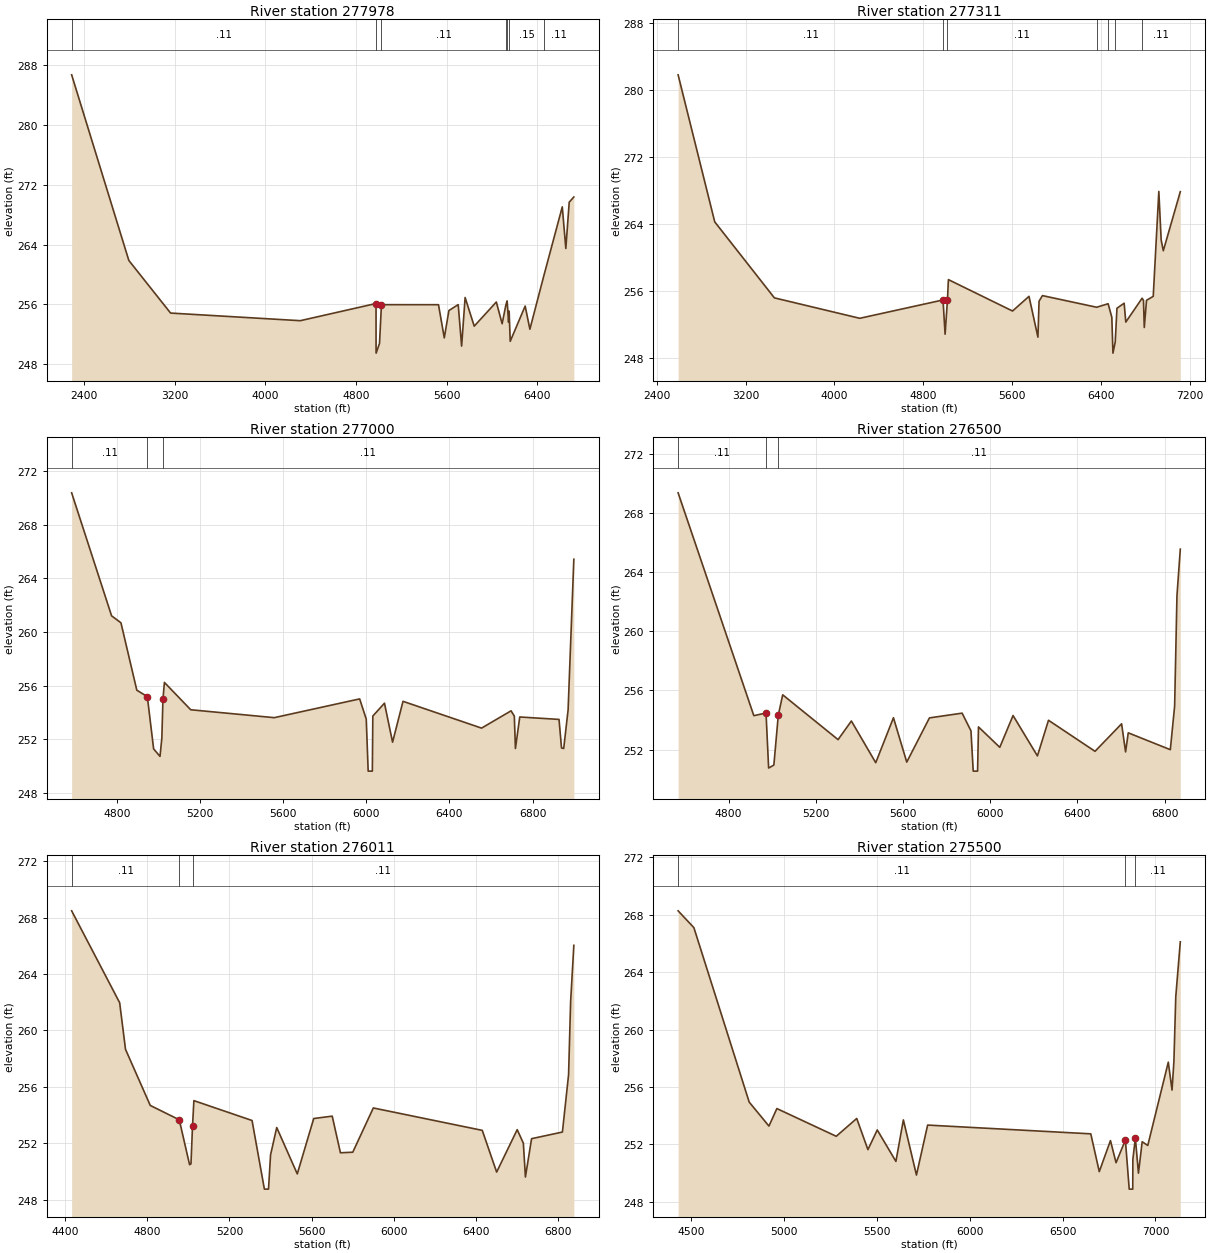
Type RM Length L Ch R = 1 ,277978  ,667,667,667
BEGIN DESCRIPTION:
LAKE CREEK 539.0
END DESCRIPTION:
XS GIS Cut Line= 3
      3720489.56     10182898.81       3718302.1     10181475.22
      3716517.88     10181111.08
#Sta/Elev= 30
  2290.6  286.72  2795.2  261.88  3163.6  254.84  4307.7  253.82  4976.3  256.12
  4976.5  250.28    4977  249.48  5006.9  250.78    5024 255.965  5527.4  255.96
  5578.4  251.52  5619.3  255.18  5701.2  255.97  5731.5  250.42  5762.2  256.92
  5842.6  253.09  6037.7  256.32  6088.8  253.41    6122  255.93  6132.9  256.47
  6145.7  253.61  6150.6   255.1  6160.2  251.06  6292.1  255.78  6333.7  252.68
  6455.5  259.76  6619.5  269.05  6650.9  263.49  6680.7  269.68  6721.5  270.37
#Mann= 7 ,-1 , 0
  2290.6     .11       0  4976.3     .06       0    5024     .11       0
    6122     .15       0  6132.9     .11       0  6150.6     .15       0
  6455.5     .11       0
Bank Sta=4976.3,5024
XS Rating Curve= 0 ,0
Exp/Cntr=0.3,0.1

Type RM Length L Ch R = 1 ,277311  ,311,311,311
BEGIN DESCRIPTION:
LAKE CREEK 538.0
END DESCRIPTION:
XS GIS Cut Line= 3
      3720628.46     10182568.96      3718597.23     10181154.04
      3716566.01     10180893.63
#Sta/Elev= 30
  2592.7  281.83  2922.5  264.27  3459.9  255.19  4228.7  252.75 4978.68  254.94
  4997.5  250.85  5018.7  254.93  5027.2  257.37  5604.8  253.62  5753.1  255.37
  5833.6   250.5  5843.8  254.79  5874.1  255.46  6362.7  254.07  6465.9  254.49
  6499.2  252.87  6509.3  248.59  6529.9  249.91  6545.4  253.95  6610.1  254.55
  6625.1   252.3  6772.2  255.15  6784.4  254.88  6791.5  251.65  6811.7   254.9
  6872.2  255.37  6922.6   267.9  6943.7   262.1  6962.9  260.82    7116  267.87
#Mann= 7 ,-1 , 0
  2592.7     .11       0 4978.68     .06       0  5018.7     .11       0
  6362.7     .15       0  6465.9     .11       0  6529.9     .15       0
  6772.2     .11       0
Bank Sta=4978.68,5018.7
XS Rating Curve= 0 ,0
Exp/Cntr=0.3,0.1

Type RM Length L Ch R = 1 ,277000  ,500,500,500
BEGIN DESCRIPTION:
LAKE CREEK 537.0
END DESCRIPTION:
XS GIS Cut Line= 3
       3719317.8     10180961.08      3718905.68      10181022.7
      3717011.68     10180384.61
#Sta/Elev= 30
  4583.3  270.39  4775.4  261.21  4820.4  260.69  4896.7  255.66  4947.3  255.18
  4977.6  251.28  5008.3  250.72  5017.1  252.09  5022.4  254.98  5029.4  256.24
    5156   254.2  5557.7  253.61  5968.5  255.01  6000.2   253.5  6009.5  249.62
  6029.5  249.62  6031.8  253.73  6087.8  254.69  6126.8  251.78    6177  254.83
  6554.8  252.83  6696.6  254.12  6712.3  253.73  6717.7  251.31  6738.5  253.66
  6927.4  253.48  6939.3  251.35  6949.9  251.31    6971  254.19  6998.6  265.43
#Mann= 3 , 0 , 0
  4583.3     .11       0  4947.3     .06       0  5022.4     .11       0
Bank Sta=4947.3,5022.4
XS Rating Curve= 0 ,0
Exp/Cntr=0.3,0.1

Type RM Length L Ch R = 1 ,276500  ,489,489,489
BEGIN DESCRIPTION:
LAKE CREEK 536.0
END DESCRIPTION:
XS GIS Cut Line= 3
      3719317.84     10180661.07      3718895.31     10180573.05
      3717052.77     10180242.28
#Sta/Elev= 30
  4568.4  269.36  4915.7  254.29 4971.66  254.47  4983.6  250.75  5007.6  250.95
  5027.9  254.32  5048.2   255.7  5302.2  252.67  5363.2  253.93  5474.9  251.11
  5556.2  254.15  5617.2  251.15  5721.3  254.14  5871.2  254.46  5911.8  253.26
  5922.1  250.54  5942.1  250.54  5946.2  253.53  6043.9  252.15  6104.8   254.3
  6216.6  251.57  6267.4  253.98  6480.8  251.88  6602.7  253.74    6621  251.84
  6633.2  253.13  6826.2  251.99    6846  254.94  6856.7  262.42    6872  265.55
#Mann= 3 , 0 , 0
  4568.4     .11       0 4971.66     .06       0  5027.9     .11       0
Bank Sta=4971.66,5027.9
XS Rating Curve= 0 ,0
Exp/Cntr=0.3,0.1

Type RM Length L Ch R = 1 ,276011  ,511,511,511
BEGIN DESCRIPTION:
LAKE CREEK 535.0
END DESCRIPTION:
XS GIS Cut Line= 3
      3719367.83     10180561.06      3718875.01     10180121.06
      3717092.28     10180094.05
#Sta/Elev= 30
    4432  268.49  4665.6  261.97  4694.1  258.66  4814.5  254.68  4955.7  253.66
  5005.9  250.47  5012.6  250.53  5020.1  253.19  5026.8  255.02  5309.8  253.61
  5369.9  248.74  5389.9  248.74  5399.9  251.17  5429.9  253.11  5529.9  249.82
  5609.9  253.75  5699.9  253.92  5739.9  251.32  5799.9  251.36  5899.9   254.5
    6430  252.91    6500  249.95    6600  252.96    6630     252    6640   249.6
    6670  252.32    6820  252.79    6850  256.86    6860  262.05  6875.6  266.04
#Mann= 3 ,-1 , 0
    4432     .11       0  4955.7     .06       0  5020.1     .11       0
Bank Sta=4955.7,5020.1
XS Rating Curve= 0 ,0
Exp/Cntr=0.3,0.1

Type RM Length L Ch R = 1 ,275500  ,269,269,269
BEGIN DESCRIPTION:
LAKE CREEK 534.0
END DESCRIPTION:
XS GIS Cut Line= 3
      3719617.84     10180211.06      3719239.51     10179787.67
      3717113.52     10179966.46
#Sta/Elev= 30
  4432.2  268.27    4517   267.1  4814.6  254.95  4920.8  253.28  4963.4   254.5
  5282.7  252.57    5393  253.81  5453.2  251.64  5503.4  253.01  5603.8  250.82
  5643.9  253.71  5714.2  249.87  5774.4  253.35    6652  252.74  6697.6  250.11
  6757.8  252.27  6787.9  250.73  6838.1  252.31  6858.7  248.89  6877.7  248.89
  6878.3  250.96  6891.7  252.45  6908.4     250  6928.4  252.19  6958.5  251.93
  7068.9  257.73    7089  255.79    7099  257.76  7109.1  262.29  7133.5  266.11
#Mann= 3 , 0 , 0
  4432.2     .11       0  6838.1     .06       0  6891.7     .11       0
Bank Sta=6838.1,6891.7
XS Rating Curve= 0 ,0
Exp/Cntr=0.3,0.1

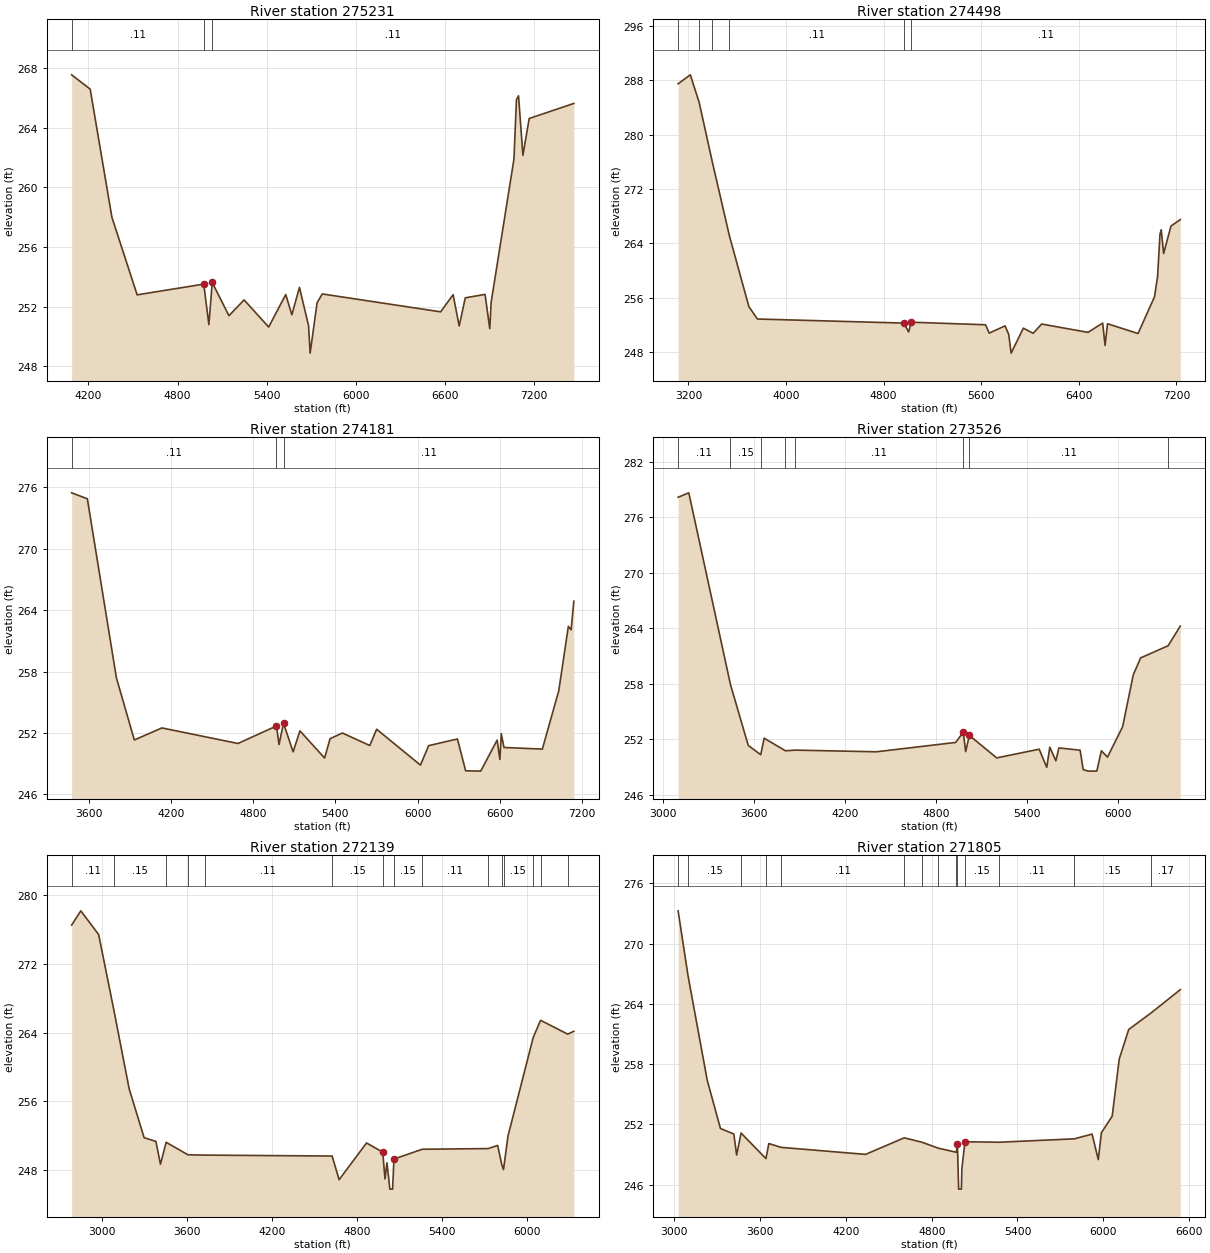
Type RM Length L Ch R = 1 ,275231  ,733,733,733
BEGIN DESCRIPTION:
LAKE CREEK 533.0
END DESCRIPTION:
XS GIS Cut Line= 3
       3719968.8     10179956.14      3718892.37     10179400.57
      3716774.36     10179869.31
#Sta/Elev= 30
  4086.6  267.55  4211.4  266.59  4357.7  257.99  4527.5  252.79  4975.9  253.51
  5010.4  250.79  5032.9  253.62  5145.5  251.39  5247.4  252.45    5413  250.63
  5527.9  252.81  5568.9  251.45  5620.1  253.29  5681.5  250.72    5692  248.88
  5738.9  252.26  5773.7  252.85  6570.2  251.65  6654.5   252.8  6695.5   250.7
  6736.4  252.59  6869.6  252.82  6901.2  250.52  6910.6   252.3  7064.2   261.9
  7080.8  265.88  7094.9  266.14  7124.4  262.15  7166.6  264.62  7467.2  265.63
#Mann= 3 , 0 , 0
  4086.6     .11       0  4975.9     .06       0  5032.9     .11       0
Bank Sta=4975.9,5032.9
XS Rating Curve= 0 ,0
Exp/Cntr=0.3,0.1

Type RM Length L Ch R = 1 ,274498  ,317,317,317
BEGIN DESCRIPTION:
LAKE CREEK 532.0
END DESCRIPTION:
XS GIS Cut Line= 3
      3721117.85     10178811.07      3719074.67     10178845.02
      3717001.38     10178801.64
#Sta/Elev= 30
  3115.1  287.51  3215.1  288.83    3287  284.81  3396.6   275.9  3535.7  265.09
  3695.2  254.66  3765.2  252.83  4965.4  252.23  5005.4  250.92  5025.4  252.36
  5635.5  251.98  5665.5  250.75  5795.5  251.82  5825.5  250.57  5845.4   247.8
  5945.6  251.48  6025.6  250.72  6095.6  252.09  6475.7  250.86  6595.7  252.23
  6615.7  248.93  6635.7  252.13  6885.8  250.69  7020.7   256.1  7045.8  259.06
  7065.8  265.34  7075.8  265.99  7095.8  262.49  7155.8  266.54  7232.3  267.48
#Mann= 6 ,-1 , 0
  3115.1     .15       0    3287     .11       0  3396.6     .15       0
  3535.7     .11       0  4965.4     .06       0  5025.4     .11       0
Bank Sta=4965.4,5025.4
XS Rating Curve= 0 ,0
Exp/Cntr=0.3,0.1

Type RM Length L Ch R = 1 ,274181  ,655,655,655
BEGIN DESCRIPTION:
LAKE CREEK 531.0
END DESCRIPTION:
XS GIS Cut Line= 3
      3720767.84     10178111.08      3719309.04     10178558.56
      3717167.83     10178561.07
#Sta/Elev= 30
  3473.9  275.45  3588.5  274.87  3800.6  257.39  3931.6  251.31  4132.9  252.49
  4688.4  250.97  4969.6  252.68  4988.3  250.87    5021  252.95    5091  250.15
    5141   252.2    5321  249.55    5361  251.44    5451  251.99    5651  250.77
    5701  252.36    6021  248.86    6081  250.76    6291  251.41    6351   248.3
  6460.9  248.27    6581   251.3    6601  249.41    6611  251.93    6631  250.58
    6911  250.42    7031  256.12    7101  262.41    7121  262.07    7141  264.87
#Mann= 3 ,-1 , 0
  3473.9     .11       0  4969.6     .06       0    5021     .11       0
Bank Sta=4969.6,5021
XS Rating Curve= 0 ,0
Exp/Cntr=0.3,0.1

Type RM Length L Ch R = 1 ,273526  ,1387,1387,1387
BEGIN DESCRIPTION:
LAKE CREEK 530.0
END DESCRIPTION:
XS GIS Cut Line= 3
       3720717.9     10178011.07      3718831.61      10178228.7
      3717417.81     10178311.07
#Sta/Elev= 30
  3097.8  278.15  3168.3  278.63  3443.5   257.9  3560.9  251.32  3643.1  250.33
  3665.8  252.11  3806.2  250.75    3872  250.82  4406.5  250.64  4929.9  251.65
  4980.3  252.76    4996  250.66  5020.4  252.41  5200.7  249.98  5481.2  250.92
  5531.3  248.96  5551.3  251.14  5591.4  249.67  5611.4  251.06  5751.6  250.81
  5771.7  248.72  5803.8  248.55  5861.8  248.56  5891.9  250.75  5931.9  250.06
  6032.1  253.35  6102.2  258.95  6151.1  260.79  6332.3   262.1  6412.8  264.23
#Mann= 8 ,-1 , 0
  3097.8     .11       0  3443.5     .15       0  3643.1     .11       0
  3806.2     .15       0    3872     .11       0  4980.3     .06       0
  5020.4     .11       0  6332.3     .17       0
Bank Sta=4980.3,5020.4
XS Rating Curve= 0 ,0
Exp/Cntr=0.3,0.1

Type RM Length L Ch R = 1 ,272139  ,334,334,334
BEGIN DESCRIPTION:
LAKE CREEK 529.0
END DESCRIPTION:
XS GIS Cut Line= 3
      3720741.35     10177950.92      3718892.37      10177603.7
       3717347.2     10178202.67
#Sta/Elev= 30
  2789.3  276.53  2853.9  278.19  2979.6  275.43    3086   266.7  3194.8  257.46
  3299.9  251.79    3383  251.35  3415.1   248.7  3455.1  251.25  3608.4   249.8
  3725.8  249.76  4624.7  249.65  4673.9   246.9    4867  251.17  4981.3  250.11
  4997.2  246.99  5011.2  248.87  5031.6   245.8  5050.8   245.8  5060.3   249.3
  5259.5  250.44  5724.7  250.52  5790.9  250.89  5819.1  248.72  5832.2  248.07
  5863.7  251.97  6041.5  263.45  6093.4  265.45  6284.6  263.84  6327.8  264.17
#Mann= 15 ,-1 , 0
  2789.3     .11       0    3086     .15       0  3455.1     .11       0
  3608.4     .15       0  3725.8     .11       0  4624.7     .15       0
  4981.3     .09       0  5060.3     .15       0  5259.5     .11       0
  5724.7     .15       0  5819.1     .11       0  5832.2     .15       0
  6041.5     .17       0  6093.4     .15       0  6284.6     .17       0
Bank Sta=4981.3,5060.3
XS Rating Curve= 0 ,0
Exp/Cntr=0.3,0.1

Type RM Length L Ch R = 1 ,271805  ,305,305,305
BEGIN DESCRIPTION:
LAKE CREEK 528.0
END DESCRIPTION:
XS GIS Cut Line= 3
      3720515.68     10177907.53      3718597.23     10177438.77
      3717252.27       10178185.
#Sta/Elev= 30
    3026  273.26  3094.8  266.84  3229.6  256.39  3322.1  251.58  3415.7  251.03
  3435.5  248.94  3466.3  251.13  3640.4  248.58  3660.5  250.08  3746.4   249.7
  4337.2     249  4607.9  250.65    4732  250.21  4846.2  249.62  4972.3  249.21
  4979.7  250.07  4988.4  245.54  5007.6  245.54  5010.9  247.57  5032.7  250.26
    5272  250.21  5797.6  250.55  5921.8  251.02  5965.3  248.48    5987  251.16
  6062.6  252.81  6111.8   258.5  6178.1  261.44  6335.6   263.1    6539  265.41
#Mann= 14 ,-1 , 0
    3026     .11       0  3094.8     .15       0  3466.3     .11       0
  3640.4     .15       0  3746.4     .11       0  4607.9     .15       0
    4732     .11       0  4846.2     .15       0  4972.3     .12       0
  4979.7     .09       0  5032.7     .15       0    5272     .11       0
  5797.6     .15       0  6335.6     .17       0
Bank Sta=4979.7,5032.7
XS Rating Curve= 0 ,0
Exp/Cntr=0.3,0.1