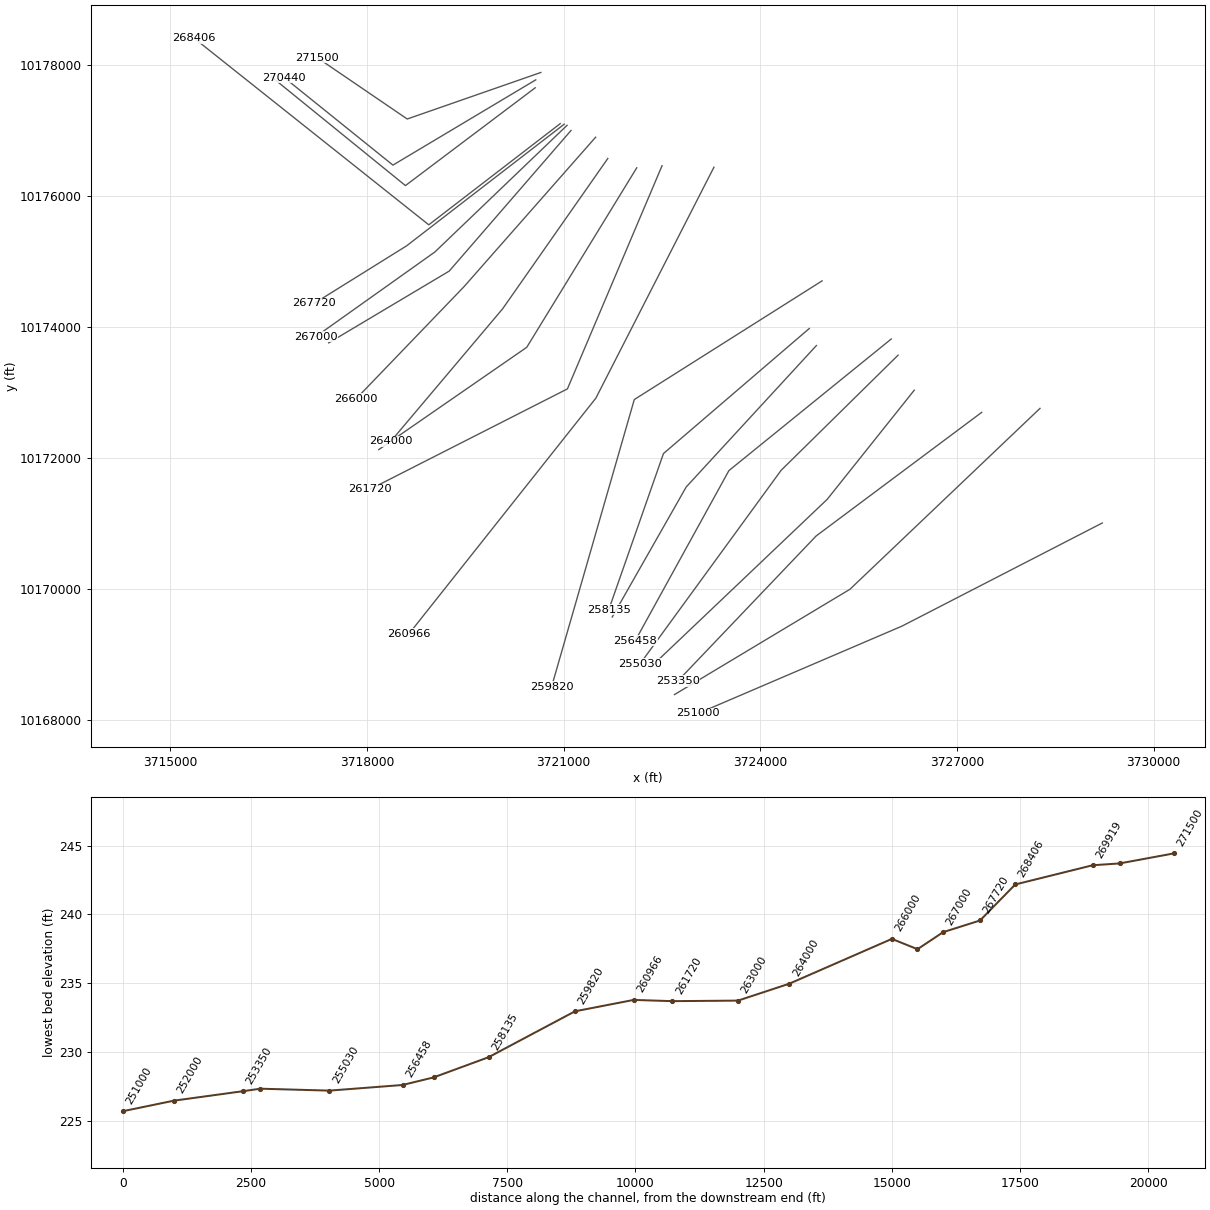
HEC-RAS study LAKE CREEK.prj: LAKE CREEK Base Level Engineering

--- LAKE CREEK.g01 (geometry) --- (continued)

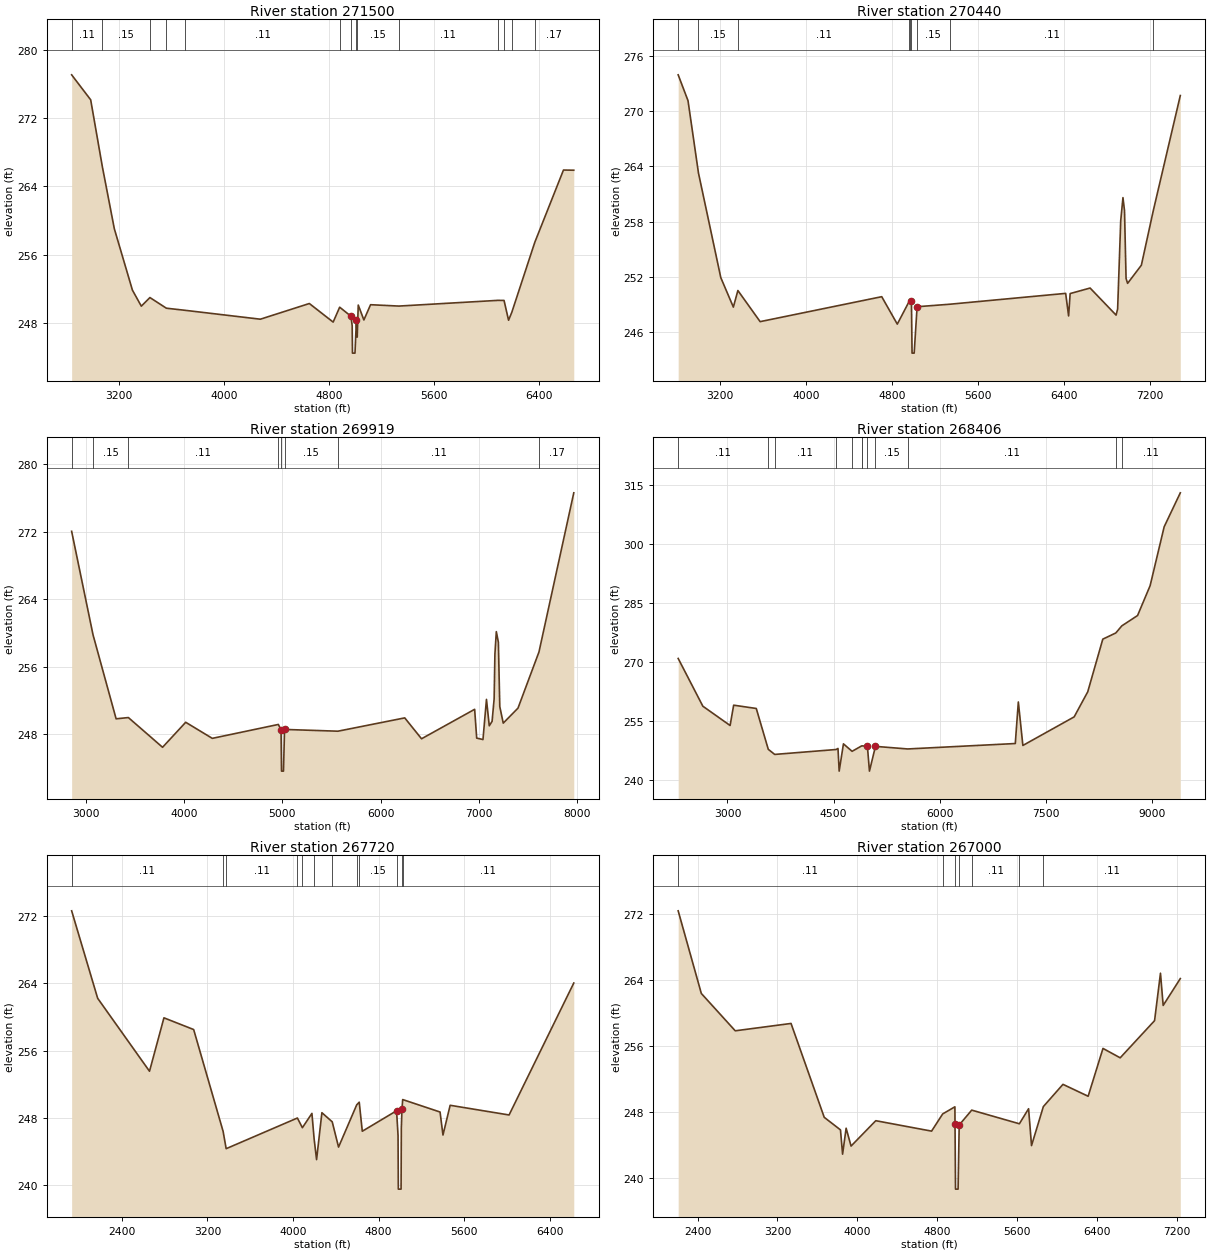
Type RM Length L Ch R = 1 ,271500  ,1060,1060,1060
BEGIN DESCRIPTION:
LAKE CREEK 527.0
END DESCRIPTION:
XS GIS Cut Line= 3
      3720654.57     10177890.17      3718615.82     10177179.39
      3717243.11     10178115.82
#Sta/Elev= 30
  2840.9  277.09  2985.7  274.16  3074.7   266.3  3165.7  259.03  3303.4  251.83
    3371  249.95  3436.5  250.96  3561.7  249.71  3705.9  249.46  4276.7  248.42
  4649.6  250.26  4830.8  248.08  4880.4  249.83  4966.1  248.77  4975.5  247.65
  4977.7  244.44  4996.9  244.44  5007.7   248.3  5013.8  246.32  5021.7  250.08
  5064.6  248.33  5115.4  250.12  5330.9  249.96  6084.8  250.63  6131.1  250.62
  6165.5   248.3  6190.4  249.24  6364.6  257.42  6583.3  265.92  6661.7   265.9
#Mann= 14 ,-1 , 0
  2840.9     .11       0  3074.7     .15       0  3436.5     .11       0
  3561.7     .15       0  3705.9     .11       0  4880.4     .15       0
  4966.1     .09       0  5007.7     .12       0  5013.8     .15       0
  5330.9     .11       0  6084.8     .15       0  6131.1     .17       0
  6190.4     .15       0  6364.6     .17       0
Bank Sta=4966.1,5007.7
XS Rating Curve= 0 ,0
Exp/Cntr=0.3,0.1

Type RM Length L Ch R = 1 ,270440  ,521,521,521
BEGIN DESCRIPTION:
LAKE CREEK 526.0
END DESCRIPTION:
XS GIS Cut Line= 3
      3720576.43     10177777.32      3718397.58     10176475.22
      3716739.56     10177812.06
#Sta/Elev= 30
  2813.5  273.94    2905  271.13  3002.1  263.28  3209.8  251.91  3326.5  248.71
  3368.6  250.51  3575.5  247.13  4705.9  249.84  4850.5  246.86  4963.3  249.38
    4967   249.5  4982.1  249.32  4987.8  243.71  5007.5  243.71  5034.7  248.75
  5337.2  249.02  6415.9   250.2  6443.3  247.75  6457.5  250.18    6643  250.78
  6884.5  247.84  6898.9   248.5  6927.7   258.1  6948.5   260.6  6962.9  259.18
  6977.3  251.82  6991.7  251.29  7119.6  253.26  7230.1  259.17  7481.6  271.69
#Mann= 9 ,-1 , 0
  2813.5     .11       0  3002.1     .15       0  3368.6     .11       0
  4963.3     .15       0    4967     .12       0  4982.1     .09       0
  5034.7     .15       0  5337.2     .11       0  7230.1     .17       0
Bank Sta=4982.1,5034.7
XS Rating Curve= 0 ,0
Exp/Cntr=0.3,0.1

Type RM Length L Ch R = 1 ,269919  ,1513,1513,1513
BEGIN DESCRIPTION:
LAKE CREEK 525.0
END DESCRIPTION:
XS GIS Cut Line= 3
      3720567.71     10177655.77      3718588.55     10176162.72
      3716548.62     10177820.71
#Sta/Elev= 30
  2856.6  272.05    3074  259.77    3309  249.79  3433.6  249.94  3781.5  246.41
  4016.8  249.38  4287.4  247.47  4959.2  249.12  4986.8  248.48  4991.6  243.58
  5011.3  243.58  5022.4248.5301    5565  248.32    6245   249.9  6415.9  247.42
  6956.1  250.92  6976.9   247.5  7040.8  247.33  7076.3   252.1  7104.8  248.96
  7133.5  249.49  7154.3  252.15  7162.2  257.46  7176.6  260.14  7197.4  258.88
  7211.8  251.24    7247  249.28  7397.1  251.06  7610.5  257.73  7964.5  276.62
#Mann= 8 ,-1 , 0
  2856.6     .11       0    3074     .15       0  3433.6     .11       0
  4959.2     .15       0  4986.8     .09       0  5022.4     .15       0
    5565     .11       0  7610.5     .17       0
Bank Sta=4986.8,5022.4
XS Rating Curve= 0 ,0
Exp/Cntr=0.3,0.1

Type RM Length L Ch R = 1 ,268406  ,686,686,686
BEGIN DESCRIPTION:
LAKE CREEK 524.0
END DESCRIPTION:
XS GIS Cut Line= 3
       3720949.7     10177108.93      3718944.46     10175563.77
      3715367.84     10178411.08
#Sta/Elev= 30
  2302.7  270.85  2651.8   258.7  3037.3  253.79  3087.6  258.96  3407.4  258.12
  3577.3  247.73  3668.1  246.43  4536.2  247.68  4563.4  247.95  4580.2  242.18
  4640.6  249.12  4762.8  247.22  4897.6  248.59  4904.1  248.61  4979.6  248.48
  5008.5  242.18  5093.4  248.48  5549.5  247.82  7071.4   249.2  7114.6  259.78
  7178.7  248.71  7904.2  255.98  8096.4  262.36  8309.4  275.76  8493.2  277.33
  8578.4  279.14  8801.2  281.77  8978.9  289.37  9177.5  304.35  9405.8  312.99
#Mann= 12 ,-1 , 0
  2302.7     .11       0  3577.3     .15       0  3668.1     .11       0
  4536.2     .15       0  4762.8     .15       0  4897.6     .17       0
  4904.1     .15       0  4979.6     .09       0  5093.4     .15       0
  5549.5     .11       0  8493.2     .17       0  8578.4     .11       0
Bank Sta=4979.6,5093.4
XS Rating Curve= 0 ,0
Exp/Cntr=0.3,0.1

Type RM Length L Ch R = 1 ,267720  ,720,720,720
BEGIN DESCRIPTION:
LAKE CREEK 523.0
END DESCRIPTION:
XS GIS Cut Line= 3
       3721010.4      10177100.2      3718605.92     10175242.59
       3717199.7     10174365.87
#Sta/Elev= 30
  1929.9  272.59  2173.2  262.21    2658  253.55    2793  259.89    3071   258.5
  3346.4  246.41  3374.7  244.36  4040.9     248  4087.7  246.85  4176.8  248.55
  4197.4  245.52  4220.3  243.06  4270.1  248.63  4366.6  247.55  4425.9  244.55
  4595.9  249.57  4619.2  249.88  4647.8  246.43  4968.4  248.86  4982.2  245.93
  4984.7  239.56  5010.5  239.56  5012.9  246.84  5018.8  249.02  5025.6  250.19
  5375.1  248.71  5402.3  245.98  5469.5  249.51  6020.5  248.36  6625.5  264.02
#Mann= 12 ,-1 , 0
  1929.9     .11       0  3346.4     .15       0  3374.7     .11       0
  4040.9     .17       0  4087.7     .11       0  4197.4     .17       0
  4366.6     .15       0  4595.9     .11       0  4619.2     .15       0
  4968.4     .09       0  5018.8     .15       0  5025.6     .11       0
Bank Sta=4968.4,5018.8
XS Rating Curve= 0 ,0
Exp/Cntr=0.3,0.1

Type RM Length L Ch R = 1 ,267000  ,500,500,500
BEGIN DESCRIPTION:
LAKE CREEK 521.0
END DESCRIPTION:
XS GIS Cut Line= 3
      3721053.86     10177082.89      3719037.81      10175149.2
      3717217.05     10173853.71
#Sta/Elev= 30
  2206.5  272.39  2438.3  262.39  2777.9  257.87  3336.7  258.76  3669.1   247.4
  3831.7  245.88  3852.8  242.94  3888.3  246.08  3937.7  243.92  4185.2  246.99
    4744  245.73  4855.1  247.81  4977.4  248.67  4978.7246.6261  4983.6  238.71
  5009.4  238.71  5020.5  246.47  5145.9  248.27  5623.2  246.62  5715.3  248.44
  5744.8  243.98  5863.3   248.7  6059.6  251.39  6311.7  249.95  6460.4  255.74
  6632.6   254.6  6976.9   259.1    7036  264.84    7063  260.94  7234.6  264.19
#Mann= 7 ,-1 , 0
  2206.5     .11       0  4855.1     .15       0  4978.7     .09       0
  5020.5     .15       0  5145.9     .11       0  5623.2     .15       0
  5863.3     .11       0
Bank Sta=4978.7,5020.5
XS Rating Curve= 0 ,0
Exp/Cntr=0.3,0.1

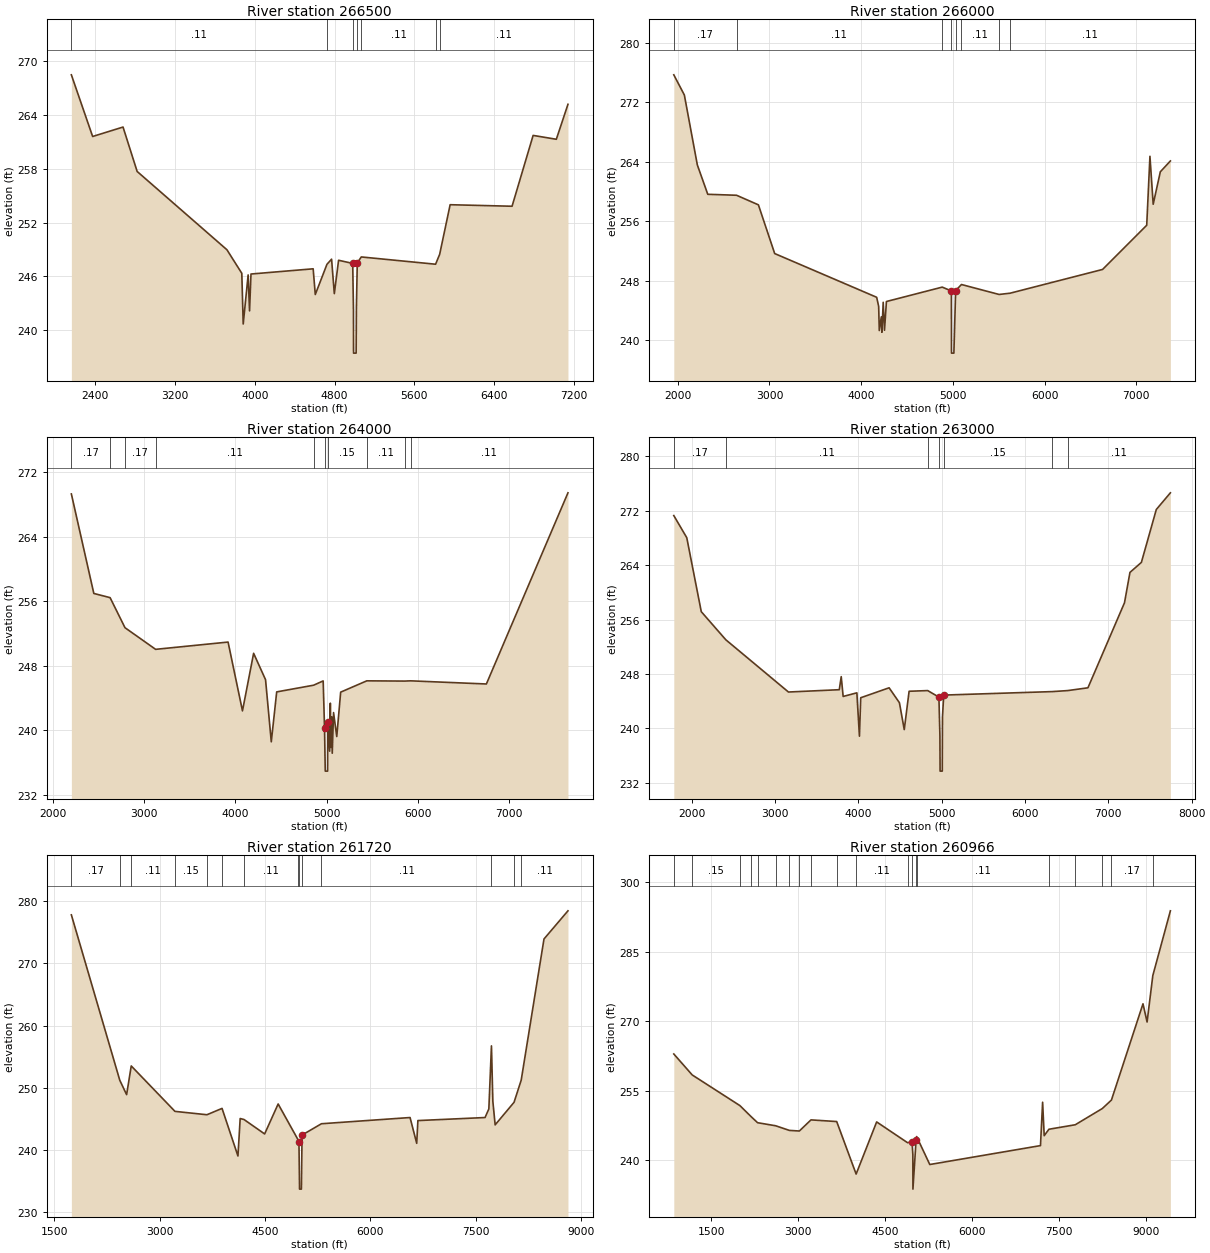
Type RM Length L Ch R = 1 ,266500  ,500,500,500
BEGIN DESCRIPTION:
LAKE CREEK 520.0
END DESCRIPTION:
XS GIS Cut Line= 3
      3721114.63     10177004.77      3719256.28     10174857.32
      3717417.82     10173761.05
#Sta/Elev= 30
  2160.1  268.43  2373.4  261.57  2678.3  262.62  2819.8  257.68  3720.2  248.97
  3869.4  246.35  3883.6  240.71    3933  246.17  3947.2  242.17  3961.5  246.27
  4585.1  246.85  4606.4  243.99  4723.4  247.35  4769.8  247.92  4797.3  244.09
    4840   247.8  4981.8  247.45  4989.2  242.27  4990.3  237.47  5016.1  237.47
  5018.8  242.56 5027.56247.5106  5067.8  248.17  5812.9  247.36  5853.8  248.46
  5958.9  253.98  6579.9  253.81  6791.2  261.69    7024  261.26  7140.5  265.15
#Mann= 7 ,-1 , 0
  2160.1     .11       0  4723.4     .15       0  4981.8     .09       0
 5027.56     .15       0  5067.8     .11       0  5812.9     .15       0
  5853.8     .11       0
Bank Sta=4981.8,5027.56
XS Rating Curve= 0 ,0
Exp/Cntr=0.3,0.1

Type RM Length L Ch R = 1 ,266000  ,2000,2000,2000
BEGIN DESCRIPTION:
LAKE CREEK 255.0
END DESCRIPTION:
XS GIS Cut Line= 3
      3721489.74     10176901.51      3719479.51     10174616.64
      3717836.48     10172907.23
#Sta/Elev= 30
  1956.7   275.7  2071.8  272.98  2213.2  263.57    2327  259.61  2640.9  259.48
  2879.2  258.19  3056.6  251.63  4168.6  245.74  4190.4  244.51  4197.1  241.26
  4218.9  243.09  4225.5  241.03  4239.8  245.07    4254   241.3  4274.9  245.17
  4883.3  247.11  4983.6  246.59    4984  239.22  4984.5  238.22  5010.4  238.22
 5029.64246.6437  5093.1  247.46  5503.5  246.12    5623  246.29  6631.7  249.49
  7112.8  255.44    7148  264.73  7183.5  258.27  7261.2  262.64    7371   264.1
#Mann= 8 ,-1 , 0
  1956.7     .17       0  2640.9     .11       0  4883.3     .15       0
  4983.6     .09       0 5029.64     .15       0  5093.1     .11       0
  5503.5     .15       0    5623     .11       0
Bank Sta=4983.6,5029.64
XS Rating Curve= 0 ,0
Exp/Cntr=0.3,0.1

Type RM Length L Ch R = 1 ,264000  ,1000,1000,1000
BEGIN DESCRIPTION:
LAKE CREEK 254.0
END DESCRIPTION:
XS GIS Cut Line= 3
      3721675.03     10176576.09      3720071.77     10174282.38
      3718367.83     10172261.05
#Sta/Elev= 30
  2201.5  269.28  2447.6  256.96  2625.9  256.44  2789.1  252.72  3124.8  250.04
  3918.9  250.94  4076.7  242.42  4198.8  249.55  4329.6  246.28  4392.4  238.59
  4451.7  244.77  4856.6   245.6    4961  246.13  4975.9  240.33  4983.9  234.96
  5009.8  234.96    5011  240.99  5031.9  237.43  5039.6  243.37  5046.2   237.9
  5053.9  241.68  5060.5  237.18  5074.8  242.21  5109.9  239.24  5152.8  244.74
  5439.1  246.14  5855.1  246.11  5919.5  246.14  6749.7  245.75  7643.7  269.42
#Mann= 10 ,-1 , 0
  2201.5     .17       0  2625.9     .11       0  2789.1     .17       0
  3124.8     .11       0  4856.6     .15       0  4975.9     .09       0
    5011     .15       0  5439.1     .11       0  5855.1     .15       0
  5919.5     .11       0
Bank Sta=4975.9,5011
XS Rating Curve= 0 ,0
Exp/Cntr=0.3,0.1

Type RM Length L Ch R = 1 ,263000  ,1280,1280,1280
BEGIN DESCRIPTION:
LAKE CREEK 253.0
END DESCRIPTION:
XS GIS Cut Line= 3
      3722116.78     10176434.31      3720438.75      10173693.5
      3718181.58     10172131.55
#Sta/Elev= 30
  1786.3  271.27  1941.9  268.02    2116  257.15  2410.8  253.02    3162  245.35
    3772  245.69  3795.1  247.61  3818.3   244.7  3982.9  245.23  4013.7  238.86
  4029.2  244.51  4369.7  245.97  4493.5  243.78  4551.5  239.83  4609.6  245.46
    4833  245.56  4967.4   244.6  4979.4  238.92  4981.6  233.73  5007.5  233.73
  5010.1  241.66    5025   244.9  6324.9  245.41  6512.9  245.56  6755.6  245.97
  7194.1  258.46  7259.7  262.92  7396.8  264.39  7575.9  272.16  7744.9  274.61
#Mann= 7 ,-1 , 0
  1786.3     .17       0  2410.8     .11       0    4833     .15       0
  4967.4     .06       0    5025     .15       0  6324.9     .15       0
  6512.9     .11       0
Bank Sta=4967.4,5025
XS Rating Curve= 0 ,0
Exp/Cntr=0.3,0.1

Type RM Length L Ch R = 1 ,261720  ,754,754,754
BEGIN DESCRIPTION:
LAKE CREEK 252.0
END DESCRIPTION:
XS GIS Cut Line= 3
      3722502.44     10176465.64      3721059.32     10173058.56
       3718053.7     10171528.63
#Sta/Elev= 30
  1740.6  277.82  2430.1  251.21  2527.5  248.89  2593.4  253.51  3216.3   246.2
  3671.8  245.66  3886.5  246.68  4113.1  239.02  4144.9  245.05  4199.5  244.89
  4493.2  242.57  4685.7  247.39  4966.4  241.69  4981.9   241.3  4990.6  233.69
  5016.6  233.69  5026.1  242.39  5302.1  244.21  6564.4  245.21  6659.2  241.06
  6675.9  244.72  7632.3  245.21  7686.5  246.59  7723.7  256.74  7743.5  247.83
  7776.3  244.03  8045.5  247.66  8147.5  251.23    8472  273.94  8813.3  278.47
#Mann= 14 ,-1 , 0
  1740.6     .17       0  2430.1     .15       0  2593.4     .11       0
  3216.3     .15       0  3671.8     .11       0  3886.5     .15       0
  4199.5     .11       0  4966.4     .15       0  4981.9     .09       0
  5026.1     .15       0  5302.1     .11       0  7723.7     .15       0
  8045.5     .17       0  8147.5     .11       0
Bank Sta=4981.9,5026.1
XS Rating Curve= 0 ,0
Exp/Cntr=0.3,0.1

Type RM Length L Ch R = 1 ,260966  ,1146,1146,1146
BEGIN DESCRIPTION:
LAKE CREEK 251.0
END DESCRIPTION:
XS GIS Cut Line= 3
      3723294.58     10176444.01      3721493.35     10172917.51
      3718640.03     10169315.61
#Sta/Elev= 30
     858  262.94    1175  258.42    1996  251.81  2190.8  249.41  2301.7  248.11
  2612.9  247.45  2849.3  246.45  3020.7  246.32  3221.3  248.72  3664.4  248.36
  3999.1  237.03  4352.6  248.28  4886.1  243.79  4961.8  244.03  4976.3  241.24
  4977.7  233.78  5032.3  244.44  5041.6  245.12  5267.9  239.09  7174.9  243.17
  7211.7  252.53    7239  245.31  7320.4   246.7  7774.5  247.67  8240.3  251.17
  8397.4     253  8940.9  273.77  9011.4  269.84  9110.4  279.87    9413  293.83
#Mann= 20 ,-1 , 0
     858     .17       0    1175     .15       0    1996     .17       0
  2190.8     .11       0  2301.7     .15       0  2612.9     .17       0
  2849.3     .11       0  3020.7     .15       0  3221.3     .17       0
  3664.4     .15       0  3999.1     .11       0  4886.1     .15       0
  4961.8     .09       0  5032.3     .15       0  5041.6     .11       0
  7320.4     .15       0  7774.5     .11       0  8240.3     .15       0
  8397.4     .17       0  9110.4     .11       0
Bank Sta=4961.8,5032.3
XS Rating Curve= 0 ,0
Exp/Cntr=0.3,0.1

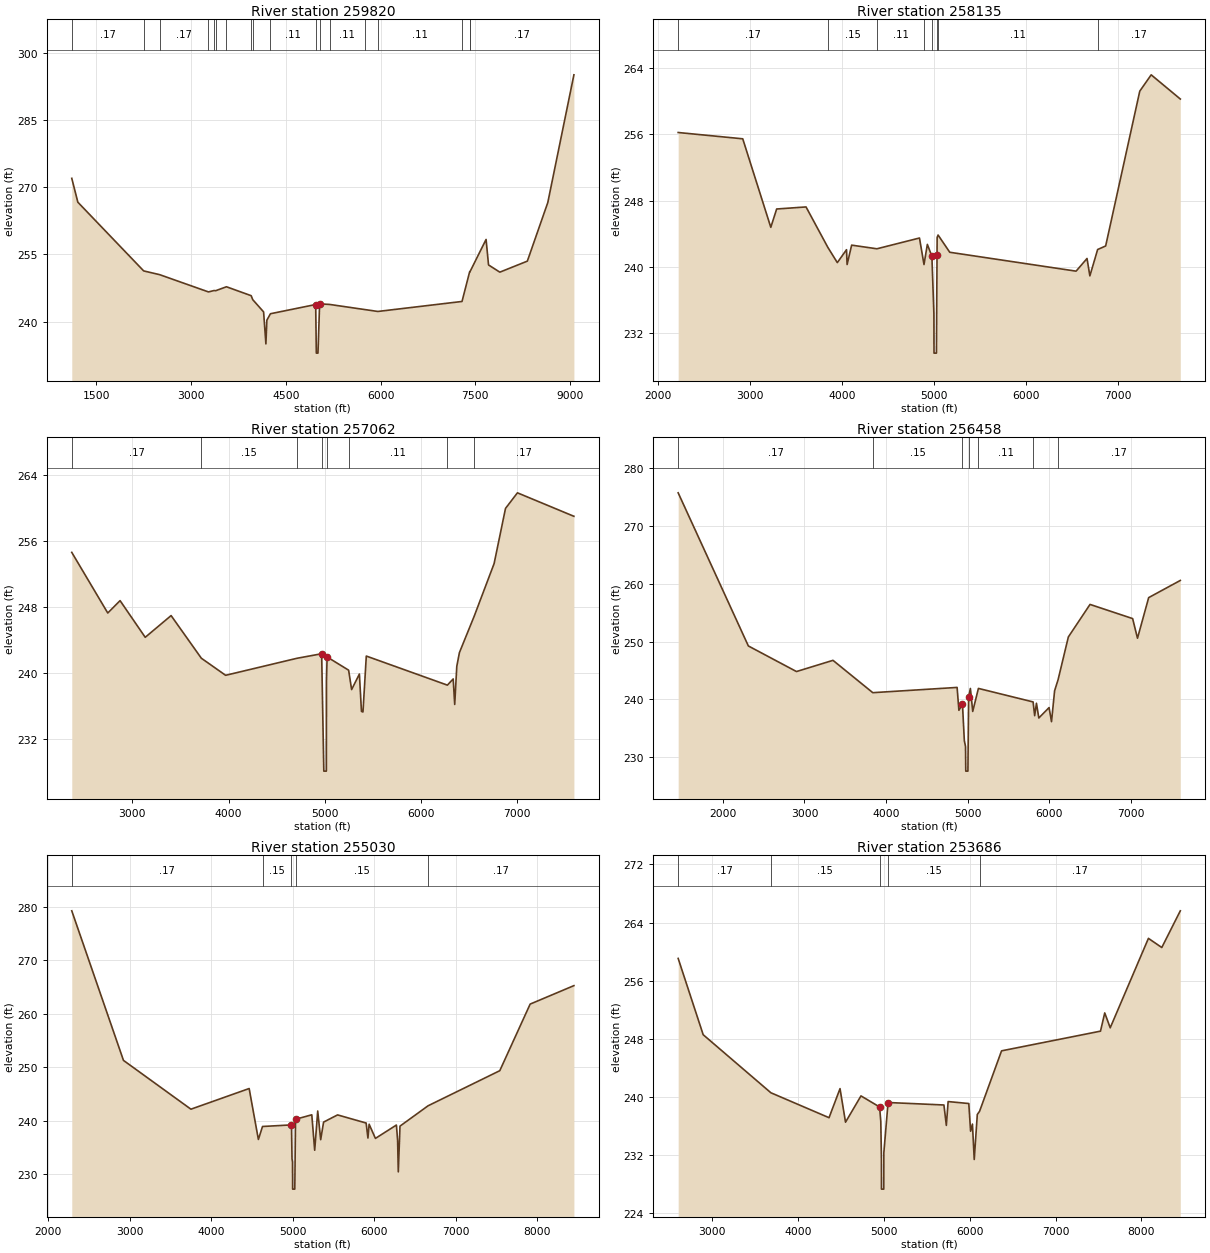
Type RM Length L Ch R = 1 ,259820  ,1685,1685,1685
BEGIN DESCRIPTION:
LAKE CREEK 250.0
END DESCRIPTION:
XS GIS Cut Line= 3
      3724943.88     10174707.88      3722079.28      10172895.8
      3720817.85     10168511.07
#Sta/Elev= 30
  1109.5  271.96  1205.9  266.63  2248.1   251.3  2501.6  250.46  3274.1  246.61
  3363.3  246.92  3388.1  246.88  3559.1  247.76  3950.8  245.77  3975.2  244.89
  4147.5  242.15  4183.9  235.01  4199.2   240.3  4255.8  241.74  4972.3   243.8
  4982.5  232.95  5008.5  232.95  5034.7  243.94  5191.3  243.82  5755.7  242.66
  5957.1  242.25  7289.7  244.48  7411.1  251.13  7415.7  251.11  7670.9  258.32
  7709.8  252.63  7888.6  251.02  8324.2  253.48  8648.2  266.55  9061.7  295.06
#Mann= 18 ,-1 , 0
  1109.5     .17       0  2248.1     .15       0  2501.6     .17       0
  3274.1     .11       0  3363.3     .17       0  3388.1     .11       0
  3559.1     .17       0  3950.8     .11       0  3975.2     .15       0
  4255.8     .11       0  4972.3     .09       0  5034.7     .15       0
  5191.3     .11       0  5755.7     .15       0  5957.1     .11       0
  7289.7     .17       0  7411.1     .15       0  7415.7     .17       0
Bank Sta=4972.3,5034.7
XS Rating Curve= 0 ,0
Exp/Cntr=0.3,0.1

Type RM Length L Ch R = 1 ,258135  ,1073,1073,1073
BEGIN DESCRIPTION:
LAKE CREEK 248.0
END DESCRIPTION:
XS GIS Cut Line= 3
      3724748.54     10173980.86      3722524.16     10172071.15
      3721689.03     10169685.08
#Sta/Elev= 30
  2216.9  256.23    2919  255.47  3224.1  244.79  3287.7     247  3607.1  247.25
  3844.4  242.37  3947.3  240.53  4047.2  242.09  4053.7   240.3  4103.1  242.64
  4377.7   242.2  4840.6   243.5  4889.8   240.3  4926.2  242.73  4975.6   241.3
  4997.5  234.34  4998.7  229.61  5024.9  229.61 5031.43241.4558  5032.6  243.56
  5042.8  243.86  5169.9  241.78  6543.5   239.5  6662.3  241.03  6693.3  238.93
  6777.7  242.11    6865  242.54  7235.9  261.22    7360  263.19  7676.6  260.27
#Mann= 8 ,-1 , 0
  2216.9     .17       0  3844.4     .15       0  4377.7     .11       0
  4889.8     .15       0  4975.6     .09       0 5031.43     .15       0
  5042.8     .11       0  6777.7     .17       0
Bank Sta=4975.6,5031.43
XS Rating Curve= 0 ,0
Exp/Cntr=0.3,0.1

Type RM Length L Ch R = 1 ,257062  ,604,604,604
BEGIN DESCRIPTION:
LAKE CREEK 247.0
END DESCRIPTION:
XS GIS Cut Line= 3
      3724857.05     10173720.45      3722871.38     10171561.17
      3721743.07     10169575.78
#Sta/Elev= 30
  2370.2  254.62  2744.3  247.28    2872  248.78  3133.4  244.34  3402.2  246.97
  3716.2  241.81  3968.8  239.74  4709.9   241.8  4966.4  242.35    4989  228.14
  5015.2  228.14  5015.7  229.14  5016.3  238.95  5023.1  241.96  5246.7  240.36
  5277.7  238.01  5358.5  239.89  5380.1  235.37  5395.8   235.3  5430.3  242.07
  6272.7  238.55  6333.1   239.3  6348.9  236.21  6370.6  240.83  6397.9  242.49
  6551.9  246.91  6758.4  253.27  6876.6  259.94  7000.6  261.83  7587.3  258.99
#Mann= 8 ,-1 , 0
  2370.2     .17       0  3716.2     .15       0  4709.9     .11       0
  4966.4     .09       0  5023.1     .11       0  5246.7     .11       0
  6272.7     .15       0  6551.9     .17       0
Bank Sta=4966.4,5023.1
XS Rating Curve= 0 ,0
Exp/Cntr=0.3,0.1

Type RM Length L Ch R = 1 ,256458  ,1428,1428,1428
BEGIN DESCRIPTION:
LAKE CREEK 246.0
END DESCRIPTION:
XS GIS Cut Line= 3
      3725998.52     10173820.26      3723522.43     10171810.73
      3722092.56     10169211.38
#Sta/Elev= 30
  1452.1  275.77  2312.5  249.26  2902.3  244.83  3349.9  246.77  3837.9  241.17
  4871.5  242.08  4893.3  238.12  4937.4  239.15  4960.2  232.86  4974.7  231.86
  4977.7  227.59  5003.9  227.59  5012.6  240.42  5034.4   241.9  5062.9  237.92
  5132.7  241.91  5803.1  239.57  5822.3  237.19  5844.1  239.34  5873.3  236.79
  5998.8  238.59  6028.8  236.15  6066.7   241.5  6109.7  243.43  6235.3  250.82
    6501  256.45  7023.2     254  7082.9   250.6    7220  257.63  7607.7   260.6
#Mann= 7 ,-1 , 0
  1452.1     .17       0  3837.9     .15       0  4937.4     .09       0
  5012.6     .15       0  5132.7     .11       0  5803.1     .15       0
  6109.7     .17       0
Bank Sta=4937.4,5012.6
XS Rating Curve= 0 ,0
Exp/Cntr=0.3,0.1

Type RM Length L Ch R = 1 ,255030  ,1344,1344,1344
BEGIN DESCRIPTION:
LAKE CREEK 245.0
END DESCRIPTION:
XS GIS Cut Line= 3
      3726102.73      10173572.9      3724318.87     10171815.07
      3722167.85     10168861.07
#Sta/Elev= 30
    2288   279.3  2922.1  251.29  3749.4  242.15  4463.6  246.02  4576.8  236.48
  4627.5  238.91  4982.9  239.21  4989.3  232.87  4995.5  232.25    4997  227.18
  5023.3  227.18  5032.4  240.26  5231.9   241.1  5267.5  234.46  5304.6  241.81
  5340.9  236.44  5376.4  239.73  5547.9  241.08  5898.3  239.56  5920.4  236.75
  5935.1  239.33  6012.3  236.68  6269.6  239.18  6284.3  236.36  6292.8  230.41
  6313.7  238.98  6658.2  242.79  7537.6  249.36    7910  261.83  8446.6  265.29
#Mann= 5 ,-1 , 0
    2288     .17       0  4627.5     .15       0  4982.9     .06       0
  5032.4     .15       0  6658.2     .17       0
Bank Sta=4982.9,5032.4
XS Rating Curve= 0 ,0
Exp/Cntr=0.3,0.1

Type RM Length L Ch R = 1 ,253686  ,336,336,336
BEGIN DESCRIPTION:
LAKE CREEK 244.0
END DESCRIPTION:
XS GIS Cut Line= 3
      3726350.14     10173039.06      3725021.99     10171372.37
      3722326.66     10168807.24
#Sta/Elev= 30
  2601.3  259.07  2892.8  248.57    3682  240.58  4359.5  237.15  4487.6  241.15
  4551.6  236.53  4731.8  240.15  4948.4  238.63  4962.6  236.67  4969.8  231.86
  4970.8  227.32  4997.1  227.32  4998.1  232.33  5047.5  239.24  5698.3   238.9
  5726.6  236.09  5747.6  239.37  5988.3   239.1  6009.3  235.29  6030.7  236.27
  6051.8   231.4  6087.4  237.59  6113.8  238.03  6370.1  246.35  7523.2  249.06
  7572.6  251.57  7636.5  249.52  8081.8  261.83  8237.5  260.57  8453.3  265.62
#Mann= 5 ,-1 , 0
  2601.3     .17       0    3682     .15       0  4948.4     .06       0
  5047.5     .15       0  6113.8     .17       0
Bank Sta=4948.4,5047.5
XS Rating Curve= 0 ,0
Exp/Cntr=0.3,0.1

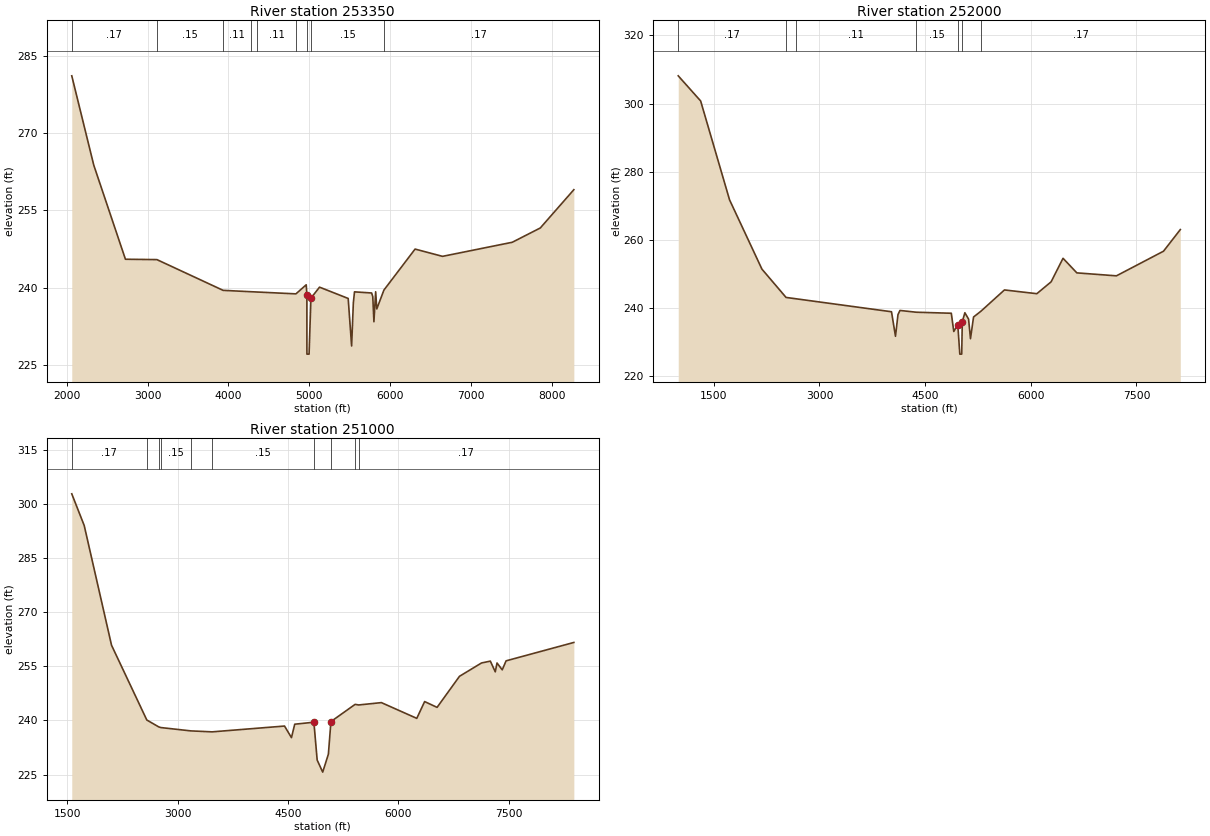
Type RM Length L Ch R = 1 ,253350  ,1350,1350,1350
BEGIN DESCRIPTION:
LAKE CREEK 243.0
END DESCRIPTION:
XS GIS Cut Line= 3
      3727378.75     10172700.48      3724852.72     10170812.47
      3722743.34     10168598.92
#Sta/Elev= 30
  2061.1  281.08  2333.2  263.77    2725  245.53  3114.2  245.46  3933.7   239.5
    4284  239.23  4353.3  239.18  4834.1  238.82  4961.5  240.58  4969.9   238.6
    4970  228.14  4970.5  227.14  4996.8  227.14  5019.9  237.99  5126.2  240.12
  5480.7  237.93  5523.2  228.72  5544.6  237.09  5558.8  239.21  5770.7  238.99
  5784.9  238.29  5799.1  233.42  5820.5  239.23  5834.6   235.9  5922.7  239.55
  6308.3   247.5    6648  246.09  7510.7  248.82  7857.3  251.59  8272.4  259.01
#Mann= 9 ,-1 , 0
  2061.1     .17       0  3114.2     .15       0  3933.7     .11       0
    4284     .15       0  4353.3     .11       0  4834.1     .15       0
  4969.9     .06       0  5019.9     .15       0  5922.7     .17       0
Bank Sta=4969.9,5019.9
XS Rating Curve= 0 ,0
Exp/Cntr=0.3,0.1

Type RM Length L Ch R = 1 ,252000  ,1000,1000,1000
BEGIN DESCRIPTION:
LAKE CREEK 242.0
END DESCRIPTION:
XS GIS Cut Line= 3
      3728267.82     10172761.04      3725368.33     10169998.69
      3722692.06     10168391.07
#Sta/Elev= 30
   995.3  308.14  1313.4  300.76  1723.9  271.73  2183.4   251.4  2525.8  243.09
  2664.8   242.7  4022.5  238.89  4079.1  231.69  4114.6  238.06  4142.9  239.27
  4374.6  238.75  4871.4  238.45  4906.6   233.1  4963.2  235.12  4992.3  226.45
  5019.2  226.45  5027.1  235.93    5064   238.6  5116.5  236.73  5143.7  230.98
  5187.2  237.35  5291.6  239.04  5625.6  245.29  6085.4  244.19  6288.2  247.67
  6457.3  254.58  6653.5   250.3  7215.1  249.43  7883.5  256.66    8122  263.01
#Mann= 7 ,-1 , 0
   995.3     .17       0  2525.8     .15       0  2664.8     .11       0
  4374.6     .15       0  4963.2     .06       0  5027.1     .15       0
  5291.6     .17       0
Bank Sta=4963.2,5027.1
XS Rating Curve= 0 ,0
Exp/Cntr=0.3,0.1

Type RM Length L Ch R = 1 ,251000  ,1000,1000,1000
BEGIN DESCRIPTION:
LAKE CREEK 241.0
END DESCRIPTION:
XS GIS Cut Line= 3
      3729217.86     10171011.07      3726163.48     10169436.82
      3723055.88     10168104.15
#Sta/Elev= 30
  1563.8  302.75  1732.8  293.97    2104  260.81  2582.9  240.11  2744.4  238.21
  2773.4  238.02  3179.9   237.1  3469.2  236.83  4452.7  238.44    4547  235.23
  4591.3  238.95  4851.6   239.5    4896  229.03  4971.2  225.68  5048.4  230.66
  5082.9  239.68  5411.1  244.44  5460.5  244.28  5768.1  244.93  6248.6  240.57
  6355.3  245.22  6524.1  243.61  6828.7  252.22  7127.8  255.91  7247.6  256.42
  7314.5  253.45  7338.1   255.9  7408.8  254.01  7461.4   256.5  8381.3  261.59
#Mann= 10 ,-1 , 0
  1563.8     .17       0  2582.9     .15       0  2744.4     .11       0
  2773.4     .15       0  3179.9     .11       0  3469.2     .15       0
  4851.6     .06       0  5082.9     .15       0  5411.1     .11       0
  5460.5     .17       0
Bank Sta=4851.6,5082.9
XS Rating Curve= 0 ,0
Exp/Cntr=0.3,0.1