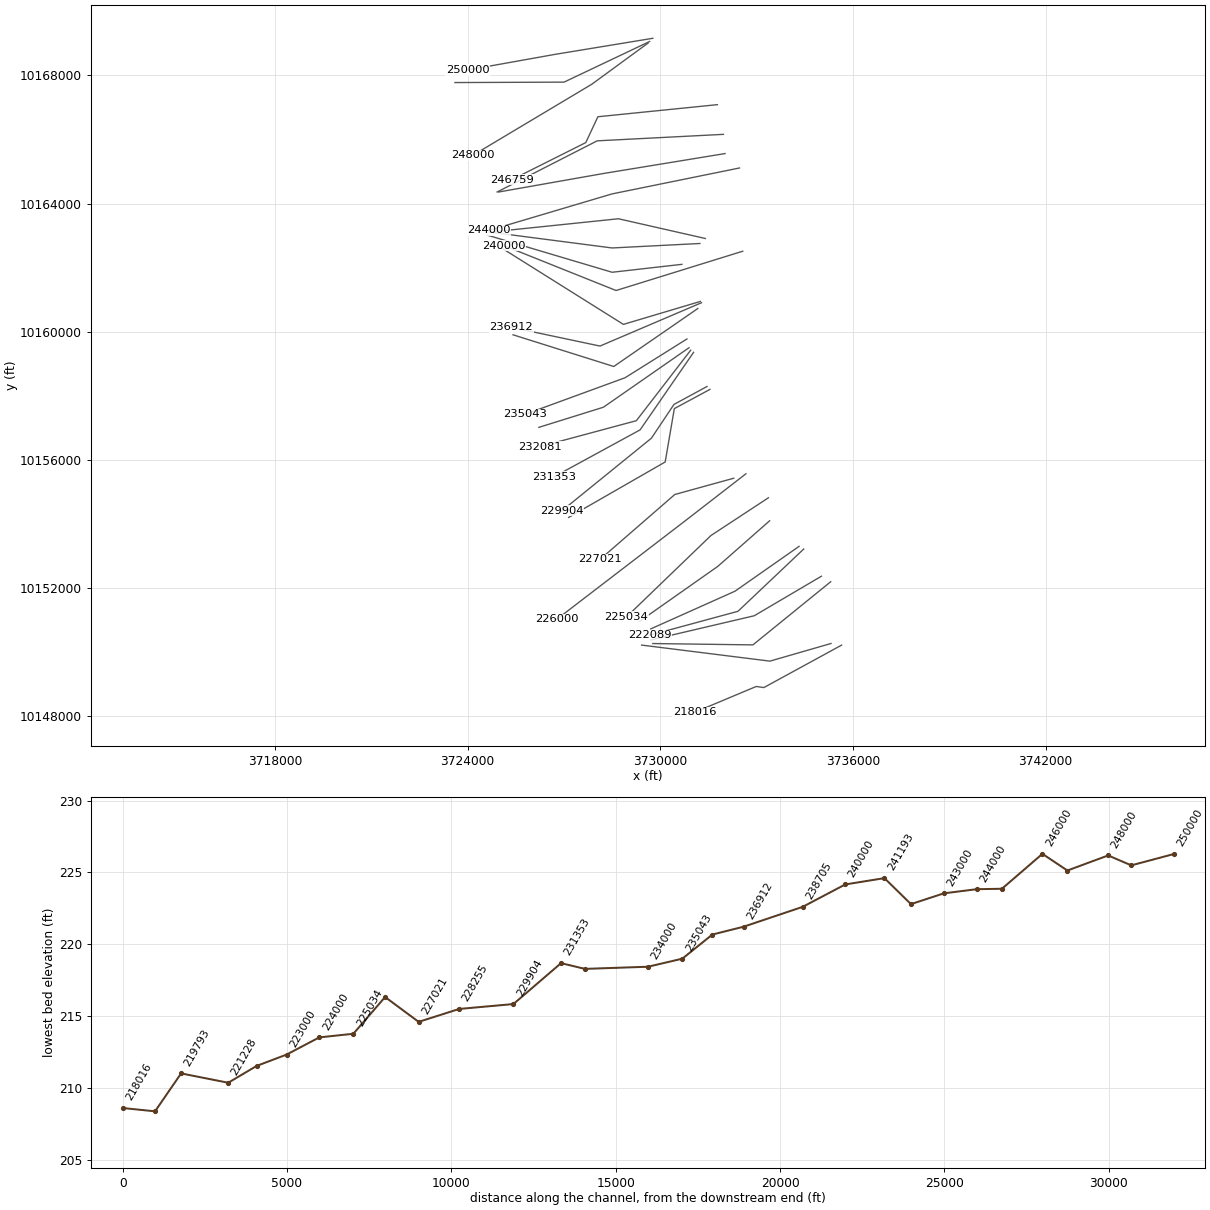
HEC-RAS study LAKE CREEK.prj: LAKE CREEK Base Level Engineering

--- LAKE CREEK.g01 (geometry) --- (continued)

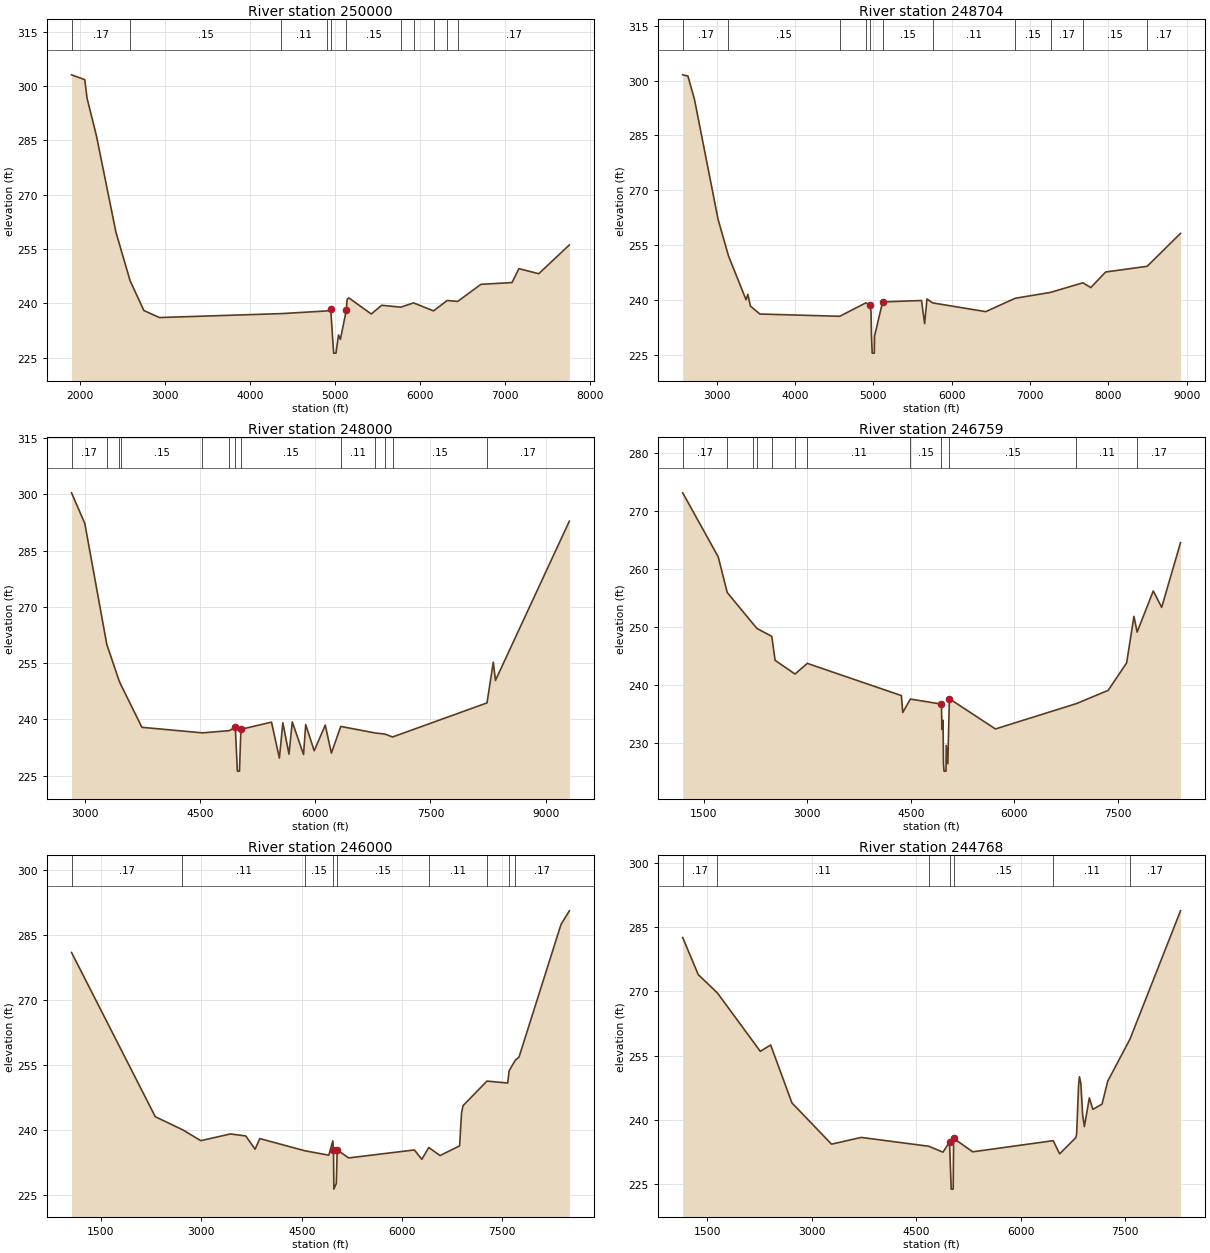
Type RM Length L Ch R = 1 ,250000  ,1296,1296,1296
BEGIN DESCRIPTION:
LAKE CREEK 240.0
END DESCRIPTION:
XS GIS Cut Line= 3
      3729767.86     10169161.07      3726708.35     10168656.69
      3723993.36     10168169.25
#Sta/Elev= 30
  1899.2   303.1  2054.6  301.77  2081.6  296.68  2193.1  286.16  2421.5  259.67
  2588.6  246.24  2750.5  238.04    2933   236.1  4369.9  237.19  4904.8  237.93
  4949.8  238.35  4984.3  226.28  5011.2  226.28  5041.1   231.3  5063.3  230.08
  5132.6  238.09  5142.7  241.13  5163.1  241.53  5427.2  237.08  5549.1  239.49
  5773.6  238.97  5924.9  240.14  6159.5  237.94  6320.5  240.81  6443.5  240.55
  6717.5  245.27  7083.3  245.76  7164.6   249.6  7398.2   248.2  7758.4  256.16
#Mann= 11 ,-1 , 0
  1899.2     .17       0  2588.6     .15       0  4369.9     .11       0
  4904.8     .15       0  4949.8     .06       0  5132.6     .15       0
  5773.6     .17       0  5924.9     .15       0  6159.5     .17       0
  6320.5     .15       0  6443.5     .17       0
Bank Sta=4949.8,5132.6
XS Rating Curve= 0 ,0
Exp/Cntr=0.3,0.1

Type RM Length L Ch R = 1 ,248704  ,704,704,704
BEGIN DESCRIPTION:
LAKE CREEK 239.0
END DESCRIPTION:
XS GIS Cut Line= 3
      3729667.88     10169061.09      3727001.16     10167791.64
      3723602.74     10167778.62
#Sta/Elev= 30
  2568.4  301.56  2634.9  301.22  2718.8  294.81  3019.5  262.07    3152   252.1
  3376.9  240.07  3399.5  241.54  3432.3  238.35  3552.9  236.18    4572  235.56
  4905.8  239.24  4960.7   238.6  4971.3  236.68  4976.9  230.36  4986.1  225.49
  5013.1  225.49  5016.1  230.15  5118.7  239.49  5615.2  239.87  5655.2  233.55
  5685.2   240.3    5757  239.22  6435.2  236.83  6810.6  240.48  7262.7   242.1
  7674.9  244.72  7775.2  243.41  7965.2  247.67  8494.5  249.22  8920.3  258.22
#Mann= 11 ,-1 , 0
  2568.4     .17       0    3152     .15       0    4572     .11       0
  4905.8     .15       0  4960.7     .06       0  5118.7     .15       0
    5757     .11       0  6810.6     .15       0  7262.7     .17       0
  7674.9     .15       0  8494.5     .17       0
Bank Sta=4960.7,5118.7
XS Rating Curve= 0 ,0
Exp/Cntr=0.3,0.1

Type RM Length L Ch R = 1 ,248000  ,1241,1241,1241
BEGIN DESCRIPTION:
LAKE CREEK 238.0
END DESCRIPTION:
XS GIS Cut Line= 3
      3729617.87     10169011.09      3727865.05     10167725.39
      3724167.83     10165511.06
#Sta/Elev= 30
  2826.2  300.42  2998.7  292.27  3284.8  260.03  3441.8  250.51  3464.7  249.39
  3742.7  237.87  4529.6  236.39  4880.4  236.98  4959.1  237.86  4985.8  226.18
  5013.1  226.18  5031.7  237.33  5430.3  239.25  5532.9  229.67  5578.1  239.08
  5657.9  230.72  5700.6  239.31  5847.6  230.62  5875.6   238.6  5986.5  231.61
  6130.4  238.47  6210.1  230.99  6332.6   238.1  6782.3  236.35  6905.6  236.07
  7007.2  235.29  8236.9  244.38  8318.8  255.24  8347.1  250.38  9309.6  292.87
#Mann= 13 ,-1 , 0
  2826.2     .17       0  3284.8     .15       0  3441.8     .17       0
  3464.7     .15       0  4529.6     .11       0  4880.4     .15       0
  4959.1     .06       0  5031.7     .15       0  6332.6     .11       0
  6782.3     .15       0  6905.6     .11       0  7007.2     .15       0
  8236.9     .17       0
Bank Sta=4959.1,5031.7
XS Rating Curve= 0 ,0
Exp/Cntr=0.3,0.1

Type RM Length L Ch R = 1 ,246759  ,759,759,759
BEGIN DESCRIPTION:
LAKE CREEK 237.0
END DESCRIPTION:
XS GIS Cut Line= 4
      3731779.83     10167088.52      3728055.85     10166710.91
      3727678.24     10165903.62      3725374.85     10164745.42
#Sta/Elev= 30
  1193.5  273.17  1708.1  262.11  1838.2  255.97  2209.6   250.6  2270.8  249.75
  2483.9  248.39  2532.3  244.25  2820.5  241.89  2998.7  243.73  4361.6  238.17
  4381.7  235.26    4492  237.57  4942.8   236.7  4948.3  232.32  4965.6  233.92
  4971.1  226.49  4979.7  225.13  5008.2  225.13  5011.3  229.57  5034.1  226.41
    5057  237.63  5724.1  232.41  6895.9  236.78  7357.2  239.07  7625.1  243.81
  7731.1  251.85  7777.4  249.13  8010.9  256.23  8132.9   253.4    8406  264.57
#Mann= 12 ,-1 , 0
  1193.5     .17       0  1838.2     .15       0  2209.6     .17       0
  2270.8     .11       0  2483.9     .17       0  2820.5     .15       0
  2998.7     .11       0    4492     .15       0  4942.8     .06       0
    5057     .15       0  6895.9     .11       0  7777.4     .17       0
Bank Sta=4942.8,5057
XS Rating Curve= 0 ,0
Exp/Cntr=0.3,0.1

Type RM Length L Ch R = 1 ,246000  ,1232,1232,1232
BEGIN DESCRIPTION:
LAKE CREEK 236.0
END DESCRIPTION:
XS GIS Cut Line= 3
      3731967.84     10166161.07      3728033.16     10165958.36
      3724917.87     10164361.08
#Sta/Elev= 30
  1060.1  280.89  2311.8     243  2718.1     240  2992.7  237.47  3433.2  239.02
  3663.5  238.56  3803.7   235.5  3873.5  237.95  4549.4  235.13  4905.2  234.12
  4965.3  237.42  4975.3  235.35  4980.9  226.29  5017.2  227.61  5030.5  235.35
  5202.4  233.49  6184.4  235.33  6295.4  233.17  6399.8  235.89    6568  234.04
  6860.2  236.27  6889.1  243.81  6911.3  245.54    7269  251.22  7579.4  250.77
  7600.7  253.61  7691.3  255.99  7749.2   256.8    8376  287.36  8500.9   290.5
#Mann= 9 ,-1 , 0
  1060.1     .17       0  2718.1     .11       0  4549.4     .15       0
  4975.3     .06       0  5030.5     .15       0  6399.8     .11       0
    7269     .17       0  7600.7     .11       0  7691.3     .17       0
Bank Sta=4975.3,5030.5
XS Rating Curve= 0 ,0
Exp/Cntr=0.3,0.1

Type RM Length L Ch R = 1 ,244768  ,768,768,768
BEGIN DESCRIPTION:
LAKE CREEK 235.0
END DESCRIPTION:
XS GIS Cut Line= 3
       3732017.9     10165561.08      3728238.14     10164940.07
      3724967.83     10164361.07
#Sta/Elev= 30
  1145.7  282.58  1368.7  273.94  1644.5  269.65  2260.5  256.02  2408.8  257.51
    2715  243.98    3284  234.36  3710.1  235.93    4680  233.87  4885.2  232.49
  4978.8  234.87  5002.7  223.86  5031.3  223.86  5037.4  235.71  5311.6  232.57
  6468.2  235.17  6560.7  232.09  6794.3   235.9  6804.4  236.68  6832.2   247.9
    6845  250.09  6865.4  248.56  6891.4  241.15  6916.1  238.46  6987.2  245.15
    7038  242.48    7170  243.71  7251.3  249.05  7571.3  258.88  8297.3  288.82
#Mann= 7 ,-1 , 0
  1145.7     .17       0  1644.5     .11       0    4680     .15       0
  4978.8     .06       0  5037.4     .15       0  6468.2     .11       0
  7571.3     .17       0
Bank Sta=4978.8,5037.4
XS Rating Curve= 0 ,0
Exp/Cntr=0.3,0.1

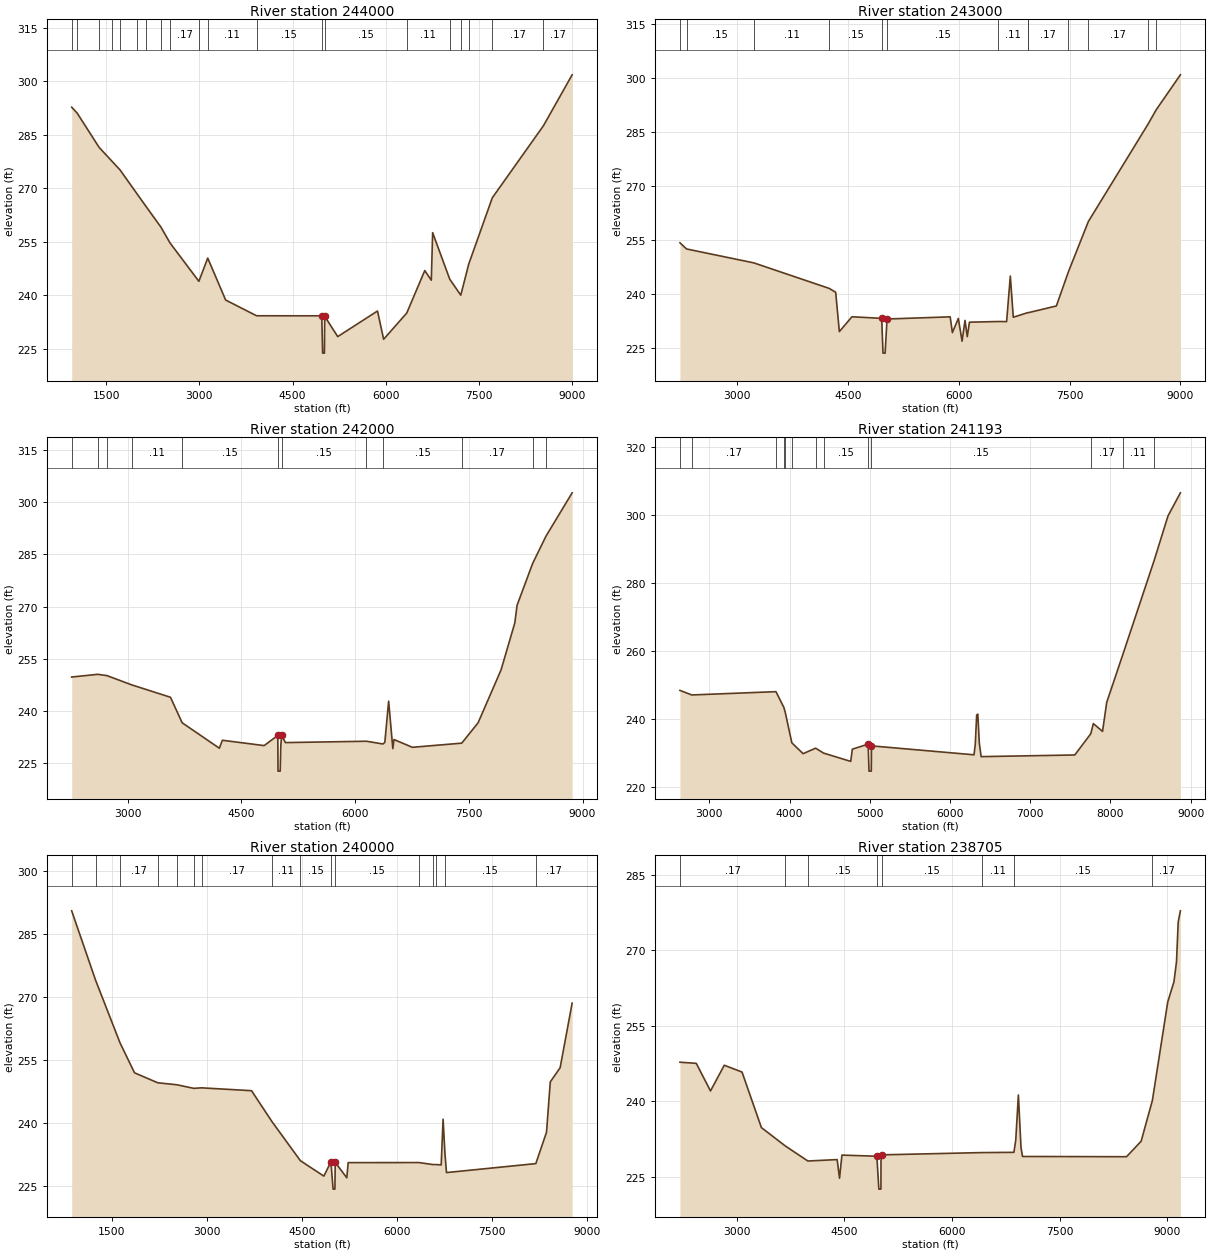
Type RM Length L Ch R = 1 ,244000  ,1000,1000,1000
BEGIN DESCRIPTION:
LAKE CREEK 234.0
END DESCRIPTION:
XS GIS Cut Line= 3
       3732467.9     10165111.08      3728496.57     10164301.02
      3724667.87     10163161.08
#Sta/Elev= 30
   946.9  292.74  1034.4   291.1  1388.1  281.48  1588.9  277.71  1725.7  275.14
  1992.9  268.58  2140.1  264.99    2384  259.09  2527.7  254.72  2992.3  243.96
  3134.7  250.46  3422.8  238.71  3919.7   234.3  4968.1  234.28  4982.5  223.83
  5011.1  223.83  5015.8  234.15  5225.3  228.46  5864.7  235.63  5963.7  227.72
  6335.3  235.06  6625.2  246.97    6730  244.26  6751.6  257.58  7026.9  244.54
  7204.1  240.07  7332.3   248.8    7711  267.35  8532.4  287.52  8994.8  301.81
#Mann= 20 ,-1 , 0
   946.9     .17       0  1034.4     .11       0  1388.1     .17       0
  1588.9     .11       0  1725.7     .17       0  1992.9     .11       0
  2140.1     .17       0    2384     .11       0  2527.7     .17       0
  2992.3     .17       0  3134.7     .11       0  3919.7     .15       0
  4968.1     .06       0  5015.8     .15       0  6335.3     .11       0
  7026.9     .17       0  7204.1     .17       0  7332.3     .11       0
    7711     .17       0  8532.4     .17       0
Bank Sta=4968.1,5015.8
XS Rating Curve= 0 ,0
Exp/Cntr=0.3,0.1

Type RM Length L Ch R = 1 ,243000  ,1000,1000,1000
BEGIN DESCRIPTION:
LAKE CREEK 233.0
END DESCRIPTION:
XS GIS Cut Line= 3
      3731402.21     10162908.82      3728696.07     10163524.97
      3724717.84     10163111.07
#Sta/Elev= 30
  2224.6  254.16  2314.1  252.45    3226  248.58  4244.5  241.51    4333  240.43
  4382.8  229.52  4553.3  233.63    4956  233.19  4973.6  223.54  5002.2  223.54
  5028.4  233.01    5883  233.61  5913.1  229.24  5993.5  233.17  6043.8  226.85
    6084  232.62  6114.2  228.12  6144.1  232.13  6530.5  232.31  6647.1  232.29
  6697.3  244.92  6737.5   233.5  6935.4  234.79  6940.1  234.76  7320.7  236.63
  7483.9  246.12  7753.6  260.06  8556.9  286.93  8674.5  291.15  8999.7  300.78
#Mann= 13 ,-1 , 0
  2224.6     .17       0  2314.1     .15       0    3226     .11       0
  4244.5     .15       0    4956     .06       0  5028.4     .15       0
  6530.5     .11       0  6935.4     .15       0  6940.1     .17       0
  7483.9     .11       0  7753.6     .17       0  8556.9     .11       0
  8674.5     .17       0
Bank Sta=4956,5028.4
XS Rating Curve= 0 ,0
Exp/Cntr=0.3,0.1

Type RM Length L Ch R = 1 ,242000  ,807,807,807
BEGIN DESCRIPTION:
LAKE CREEK 232.0
END DESCRIPTION:
XS GIS Cut Line= 3
      3731232.97     10162752.58      3728498.23     10162613.01
      3724667.88     10163111.07
#Sta/Elev= 30
  2261.7   249.8    2605  250.58  2726.6  250.21  3053.7  247.55    3565  243.99
  3718.7  236.67  4209.4  229.37  4249.4  231.65  4800.1  230.12  4980.4  233.03
  4983.4  222.79    5012  222.79  5019.6  229.89  5030.6  233.08  5081.1  230.98
  6149.5  231.37  6368.3  230.58    6392  231.06  6442.4  242.87  6497.6  229.26
    6513  231.86    6755  229.63  7406.5  230.82  7622.3  236.67  7924.8  251.83
  8106.3  265.32  8136.6  270.41  8341.6  282.39  8516.8   290.2  8862.6  302.68
#Mann= 12 ,-1 , 0
  2261.7     .15       0    2605     .17       0  2726.6     .15       0
  3053.7     .11       0  3718.7     .15       0  4980.4     .06       0
  5030.6     .15       0  6149.5     .11       0  6368.3     .15       0
  7406.5     .17       0  8341.6     .11       0  8516.8     .17       0
Bank Sta=4980.4,5030.6
XS Rating Curve= 0 ,0
Exp/Cntr=0.3,0.1

Type RM Length L Ch R = 1 ,241193  ,1193,1193,1193
BEGIN DESCRIPTION:
LAKE CREEK 231.0
END DESCRIPTION:
XS GIS Cut Line= 3
        3730673.     10162101.53      3728498.55     10161854.14
      3724617.81     10163011.08
#Sta/Elev= 30
  2633.8  248.39  2781.6  247.04  3830.6  248.01  3929.5  243.35  3947.6  241.81
  4028.4  232.94  4168.8  229.74  4325.1  231.36    4424  229.91  4762.6  227.47
  4782.7  231.07  4979.5  232.54  4990.5   224.6  5019.1   224.6  5021.3  232.04
  6299.3  229.41  6315.2  232.54  6332.5  241.12  6346.5  241.39  6365.6  232.78
  6388.2  228.87  7555.5  229.36  7754.8  235.61  7786.5  238.61  7901.3   236.3
  7953.5  244.86  8153.2  258.87  8541.4  286.42  8717.4  299.79  8871.8  306.59
#Mann= 13 ,-1 , 0
  2633.8     .15       0  2781.6     .17       0  3830.6     .11       0
  3929.5     .15       0  3947.6     .11       0  4028.4     .15       0
  4325.1     .11       0    4424     .15       0  4979.5     .06       0
  5021.3     .15       0  7754.8     .17       0  8153.2     .11       0
  8541.4     .17       0
Bank Sta=4979.5,5021.3
XS Rating Curve= 0 ,0
Exp/Cntr=0.3,0.1

Type RM Length L Ch R = 1 ,240000  ,1295,1295,1295
BEGIN DESCRIPTION:
LAKE CREEK 230.0
END DESCRIPTION:
XS GIS Cut Line= 3
      3732567.88     10162511.08      3728622.21     10161284.24
      3725127.87     10162686.78
#Sta/Elev= 30
     868  290.46  1244.4  273.96  1630.1  259.03  1859.6  251.87  2224.9   249.5
  2528.1  249.02  2794.3  248.17  2916.7  248.29    3706  247.61  4029.5  240.23
  4477.4  230.93  4847.5  227.26  4958.8  230.66  4993.1  224.16  5021.9  224.16
  5026.2  230.55  5209.4  226.86    5231  230.47  6348.5  230.49  6567.1  230.01
  6620.5  230.01    6699  229.93  6728.8  240.82  6757.4  232.82  6782.6   228.1
  8192.3  230.24    8361  237.72  8420.5   249.7  8576.1  253.09  8765.3  268.47
#Mann= 16 ,-1 , 0
     868     .17       0  1244.4     .11       0  1630.1     .17       0
  2224.9     .15       0  2528.1     .17       0  2794.3     .15       0
  2916.7     .17       0  4029.5     .11       0  4477.4     .15       0
  4958.8     .06       0  5026.2     .15       0  6348.5     .11       0
  6567.1     .15       0  6620.5     .11       0  6757.4     .15       0
  8192.3     .17       0
Bank Sta=4958.8,5026.2
XS Rating Curve= 0 ,0
Exp/Cntr=0.3,0.1

Type RM Length L Ch R = 1 ,238705  ,1793,1793,1793
BEGIN DESCRIPTION:
LAKE CREEK 229.0
END DESCRIPTION:
XS GIS Cut Line= 3
      3731245.96     10160942.68      3728850.12     10160226.53
      3725061.99     10162608.75
#Sta/Elev= 30
  2208.3  247.78  2435.8  247.56  2634.2  242.08  2826.2  247.18  3073.6  245.83
  3343.7  234.81  3679.2  231.14  3991.8  228.18  4399.8  228.46  4432.9  224.76
    4466  229.35    4953  229.13    4981   222.6  5009.8   222.6  5010.7  228.12
  5018.7   229.4  6418.2  229.85  6863.5   229.9    6889  232.32  6925.6  241.28
  6962.1  230.88  6983.3  229.08    8433  229.03  8636.7   232.1  8793.5  240.21
  9007.6  259.74  9094.2  263.75  9129.6  267.72  9153.3   275.6  9183.8  277.82
#Mann= 8 ,-1 , 0
  2208.3     .17       0  3679.2     .11       0  3991.8     .15       0
    4953     .06       0  5018.7     .15       0  6418.2     .11       0
  6863.5     .15       0  8793.5     .17       0
Bank Sta=4953,5018.7
XS Rating Curve= 0 ,0
Exp/Cntr=0.3,0.1

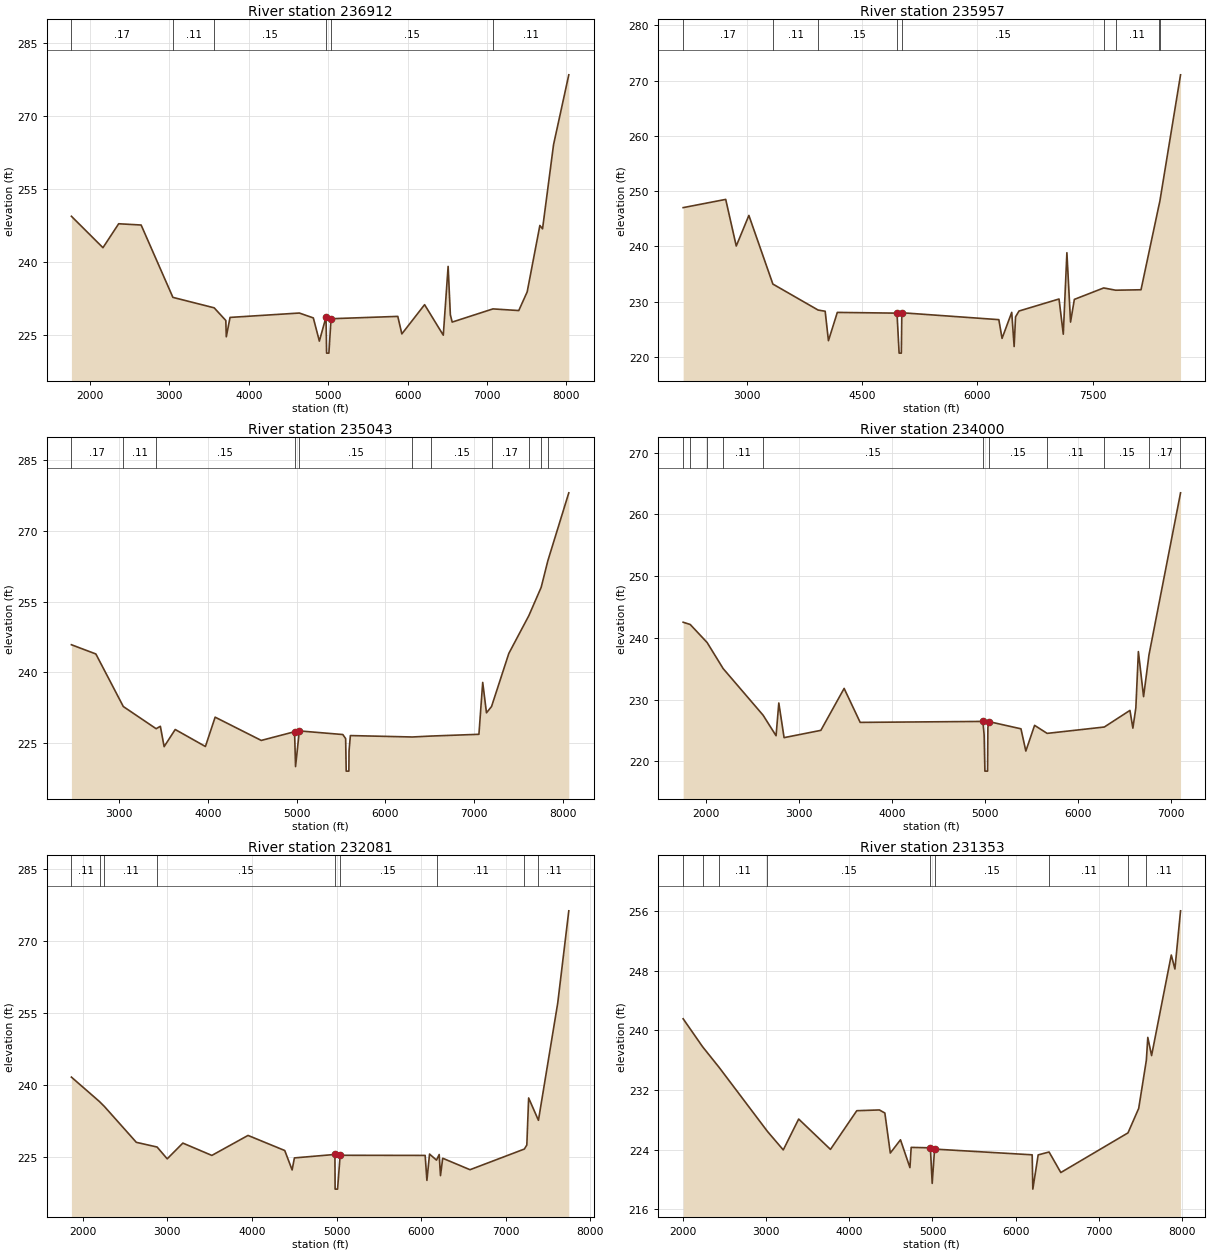
Type RM Length L Ch R = 1 ,236912  ,955,955,955
BEGIN DESCRIPTION:
LAKE CREEK 227.0
END DESCRIPTION:
XS GIS Cut Line= 3
      3731285.02     10160903.62      3728120.95     10159549.45
       3725361.7     10160135.14
#Sta/Elev= 30
  1767.5  249.35  2164.7  242.89  2362.7  247.81  2645.4  247.55  3045.4  232.68
    3565  230.53  3711.5  227.93  3717.6  224.58  3764.8  228.56  4637.3  229.46
  4813.3  228.46  4889.5  223.69  4973.2  228.64  4980.6  221.22  5009.4  221.22
  5036.5  228.29  5876.8  228.77  5927.9  225.17  6214.2  231.18  6449.7  224.91
  6510.6  239.05  6538.8  229.08  6561.8   227.6  7074.8  230.31    7400  229.97
    7506  233.81  7665.8  247.46  7699.4  246.77  7838.1  264.08  8029.9  278.42
#Mann= 6 ,-1 , 0
  1767.5     .17       0  3045.4     .11       0    3565     .15       0
  4973.2     .06       0  5036.5     .15       0  7074.8     .11       0
Bank Sta=4973.2,5036.5
XS Rating Curve= 0 ,0
Exp/Cntr=0.3,0.1

Type RM Length L Ch R = 1 ,235957  ,914,914,914
BEGIN DESCRIPTION:
LAKE CREEK 226.0
END DESCRIPTION:
XS GIS Cut Line= 3
       3731167.8     10160721.31      3728550.64     10158911.43
      3725412.78     10159900.96
#Sta/Elev= 30
    2172  247.01  2725.7   248.5  2862.9  240.06  3027.1   245.6  3339.5  233.17
  3927.7  228.47    4020  228.25  4062.5  222.92    4178  228.04  4954.7227.9086
  4982.1  220.67  5010.9  220.67  5017.4  227.98  6279.7  226.73  6321.6  223.34
  6447.4  228.05  6478.9  221.86  6497.3  227.24  6541.8  228.29    7063  230.47
  7118.5   224.1  7165.3  238.85  7212.9  226.29  7262.4   230.4  7644.4  232.47
  7799.8  232.06  8129.8  232.14  8359.3  247.18  8374.6  248.14  8644.2  271.05
#Mann= 9 ,-1 , 0
    2172     .17       0  3339.5     .11       0  3927.7     .15       0
  4954.7     .06       0  5017.4     .15       0  7644.4     .17       0
  7799.8     .11       0  8359.3     .15       0  8374.6     .11       0
Bank Sta=4954.7,5017.4
XS Rating Curve= 0 ,0
Exp/Cntr=0.3,0.1

Type RM Length L Ch R = 1 ,235043  ,1043,1043,1043
BEGIN DESCRIPTION:
LAKE CREEK 225.0
END DESCRIPTION:
XS GIS Cut Line= 3
      3730829.25     10159770.79       3728902.2     10158559.87
      3725777.18     10157414.03
#Sta/Elev= 30
    2462  245.83  2737.6  243.87  3046.8  232.71  3416.5     228  3464.3  228.51
  3506.7  224.19  3631.6  227.83    3972  224.22  4081.5  230.45  4601.3  225.51
  4976.5  227.36  4987.5  219.95  5030.1  227.53  5520.1  226.76    5552   225.9
  5558.4  218.99  5588.2  218.99  5590.3  223.28  5605.3  226.54  6303.8  226.24
  6516.4  226.44  7053.8  226.81  7096.4  237.83    7139  231.37    7196  232.71
  7390.8  243.99  7616.4  252.01  7755.1  258.02  7831.3  263.72  8066.4  278.09
#Mann= 11 ,-1 , 0
    2462     .17       0  3046.8     .11       0  3416.5     .15       0
  4976.5     .06       0  5030.1     .15       0  6303.8     .11       0
  6516.4     .15       0    7196     .17       0  7616.4     .11       0
  7755.1     .17       0  7831.3     .11       0
Bank Sta=4976.5,5030.1
XS Rating Curve= 0 ,0
Exp/Cntr=0.3,0.1

Type RM Length L Ch R = 1 ,234000  ,1919,1919,1919
BEGIN DESCRIPTION:
LAKE CREEK 224.0
END DESCRIPTION:
XS GIS Cut Line= 3
      3730894.36     10159497.35      3728227.93     10157639.57
       3726217.9     10157011.09
#Sta/Elev= 30
  1750.2  242.53    1826  242.17  2008.1  239.25  2180.3  235.04  2611.2  227.48
  2750.5  224.16  2780.2  229.46  2836.9  223.85  3232.9  225.03  3483.5  231.82
  3656.3  226.32  4977.7226.4758  4991.3  224.25  4999.3  218.43  5028.2  218.43
  5031.5  225.48    5041  226.45  5387.7  225.28  5440.1  221.68  5534.4  225.84
  5669.5  224.54  6285.2  225.57  6561.2  228.26  6592.7  225.39  6624.7  228.67
    6652  237.78  6707.9  230.49  6765.8  237.22  7101.4  263.11    7106  263.48
#Mann= 11 ,-1 , 0
  1750.2     .17       0    1826     .11       0  2008.1     .17       0
  2180.3     .11       0  2611.2     .15       0  4977.7     .06       0
    5041     .15       0  5669.5     .11       0  6285.2     .15       0
  6765.8     .17       0  7101.4     .11       0
Bank Sta=4977.7,5041
XS Rating Curve= 0 ,0
Exp/Cntr=0.3,0.1

Type RM Length L Ch R = 1 ,232081  ,728,728,728
BEGIN DESCRIPTION:
LAKE CREEK 223.0
END DESCRIPTION:
XS GIS Cut Line= 3
      3730946.45     10159419.21      3729253.76     10157218.72
      3726258.98     10156411.43
#Sta/Elev= 30
  1865.8  241.64  2198.3  236.53    2255  235.53  2633.1  228.04  2878.4  227.06
    2998   224.6  3182.8  227.88  3525.4  225.31  3953.1  229.48  4387.1  226.33
  4474.1  222.28  4501.2  224.79  4979.9225.5112  4982.1  218.28    5011  218.28
  5041.7  225.34  6046.3  225.31    6067   220.1  6098.1  225.59  6180.4  224.33
    6212   225.5  6227.5  221.09  6253.5  224.72  6576.5  222.33  7218.8  226.64
  7247.7  227.48  7269.2  237.29    7385  232.63    7613  257.09  7743.7  276.32
#Mann= 9 ,-1 , 0
  1865.8     .11       0  2198.3     .17       0    2255     .11       0
  2878.4     .15       0  4979.9     .06       0  5041.7     .15       0
  6180.4     .11       0  7218.8     .15       0    7385     .11       0
Bank Sta=4979.9,5041.7
XS Rating Curve= 0 ,0
Exp/Cntr=0.3,0.1

Type RM Length L Ch R = 1 ,231353  ,1449,1449,1449
BEGIN DESCRIPTION:
LAKE CREEK 222.0
END DESCRIPTION:
XS GIS Cut Line= 3
      3731037.61     10159354.14      3729370.95     10156932.26
       3726702.3     10155474.27
#Sta/Elev= 30
  2002.5  241.57  2235.8  237.82  2435.7  235.03  3015.1  226.45  3206.2  223.95
  3391.5   228.1  3773.7  224.02  4090.2  229.22  4362.1  229.32  4427.8  228.91
  4493.4  223.53  4615.8  225.31  4729.4  221.57  4744.3  224.29  4975.3  224.23
  4997.2  219.45  5025.7  224.06  6199.4  223.29  6207.1  218.68  6271.4  223.28
  6402.5  223.67  6543.7  220.91  7351.6  226.24  7480.2  229.53  7572.3     236
  7589.6  239.07  7635.2  236.63  7872.1  250.14  7915.7  248.26  7983.4  256.08
#Mann= 9 ,-1 , 0
  2002.5     .11       0  2235.8     .17       0  2435.7     .11       0
  3015.1     .15       0  4975.3     .06       0  5025.7     .15       0
  6402.5     .11       0  7351.6     .15       0  7572.3     .11       0
Bank Sta=4975.3,5025.7
XS Rating Curve= 0 ,0
Exp/Cntr=0.3,0.1

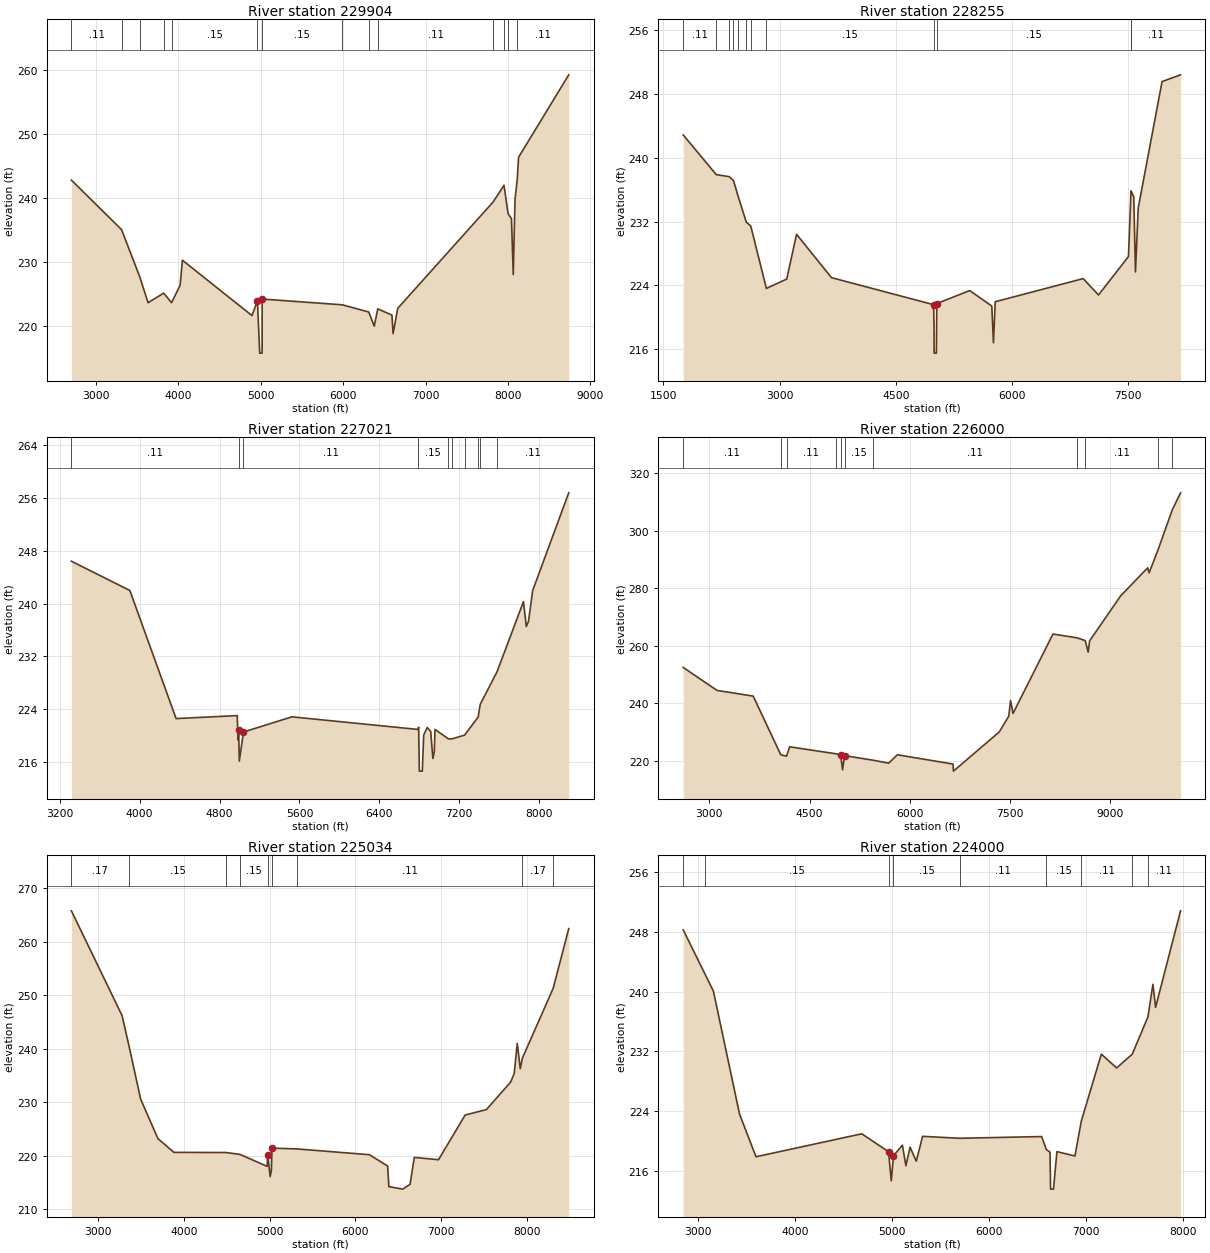
Type RM Length L Ch R = 1 ,229904  ,1649,1649,1649
BEGIN DESCRIPTION:
LAKE CREEK 221.0
END DESCRIPTION:
XS GIS Cut Line= 4
       3731454.3     10158286.44      3730425.64     10157726.53
      3729722.51     10156671.85      3726936.09     10154406.25
#Sta/Elev= 30
  2706.4  242.79  3314.5  235.08  3534.6  227.74    3636  223.69  3825.5  225.18
  3920.8  223.69  4024.6  226.41  4052.4  230.31  4895.9  221.68    4962  223.98
  4989.6  215.83  5018.5  215.83    5019  216.83  5019.1  224.26  5990.6  223.36
  6311.9  222.24  6378.4  220.03  6420.9  222.73  6592.5  221.76  6606.9  218.87
  6662.9  222.81  7819.9  239.39  7951.8  241.99  8000.6  237.57  8041.9   236.8
  8063.9  228.07    8085  239.78  8111.4  242.83  8128.1  246.35  8736.4   259.2
#Mann= 14 ,-1 , 0
  2706.4     .11       0  3314.5     .17       0  3534.6     .15       0
  3825.5     .11       0  3920.8     .15       0    4962     .06       0
  5019.1     .15       0  5990.6     .11       0  6311.9     .15       0
  6420.9     .11       0  7819.9     .17       0  7951.8     .11       0
  8000.6     .17       0  8111.4     .11       0
Bank Sta=4962,5019.1
XS Rating Curve= 0 ,0
Exp/Cntr=0.3,0.1

Type RM Length L Ch R = 1 ,228255  ,1234,1234,1234
BEGIN DESCRIPTION:
LAKE CREEK 220.0
END DESCRIPTION:
XS GIS Cut Line= 4
      3731545.44     10158195.29      3730437.29     10157596.61
       3730152.2     10155929.66       3727144.4      10154197.9
#Sta/Elev= 30
  1756.5  242.87  2182.8  237.89  2351.3  237.63  2405.6  237.14  2461.2  235.31
  2571.1  231.92  2628.3  231.45  2830.5  223.61  3092.7  224.78  3219.9   230.4
  3670.9  224.96  4989.1  221.57  4994.9  218.93  4996.3  215.49  5025.2  215.49
 5030.76221.7109  5456.2  223.34  5740.7   221.4  5762.3  216.79  5785.3  221.94
  6920.4  224.84  7118.7  222.79  7505.3  227.61  7537.7  235.67  7538.7  235.85
  7573.9   235.1  7595.8  225.68  7631.6   233.7  7939.2  249.56  8177.9  250.41
#Mann= 12 ,-1 , 0
  1756.5     .11       0  2182.8     .17       0  2351.3     .11       0
  2405.6     .17       0  2461.2     .11       0  2571.1     .17       0
  2628.3     .11       0  2830.5     .15       0  4989.1     .06       0
 5030.76     .15       0  7537.7     .17       0  7538.7     .11       0
Bank Sta=4989.1,5030.76
XS Rating Curve= 0 ,0
Exp/Cntr=0.3,0.1

Type RM Length L Ch R = 1 ,227021  ,1021,1021,1021
BEGIN DESCRIPTION:
LAKE CREEK 218.0
END DESCRIPTION:
XS GIS Cut Line= 3
       3732287.6     10155421.84      3730451.68     10154914.03
      3728134.14     10152895.95
#Sta/Elev= 30
  3317.2  246.42  3902.3  241.98  4364.9  222.56    4977  223.01  4985.8  219.29
    4991  220.84  4997.8  216.11  5039.3  220.52  5524.5  222.82  6786.3  220.91
  6792.9  221.26  6799.8  214.59  6829.8  214.59  6843.3  220.06  6878.4  221.21
  6913.5   220.6  6935.3  216.51  6949.6  217.55  6956.2  220.92  7090.7  219.48
  7126.9  219.48  7252.5  220.05  7388.4  222.78  7409.1  224.71  7578.2  229.68
    7842  240.29  7870.5  236.52  7892.4   237.3  7934.1  241.97  8295.1  256.79
#Mann= 10 ,-1 , 0
  3317.2     .11       0    4991     .06       0  5039.3     .11       0
  6786.3     .15       0  7090.7     .11       0  7126.9     .15       0
  7252.5     .11       0  7388.4     .15       0  7409.1     .17       0
  7578.2     .11       0
Bank Sta=4991,5039.3
XS Rating Curve= 0 ,0
Exp/Cntr=0.3,0.1

Type RM Length L Ch R = 1 ,226000  ,966,966,966
BEGIN DESCRIPTION:
LAKE CREEK 217.0
END DESCRIPTION:
XS GIS Cut Line= 3
      3732667.82     10155561.05      3730778.52     10154094.01
      3726767.82     10151011.04
#Sta/Elev= 30
    2608  252.39  3114.4   244.4  3656.1  242.42    4071  221.95  4155.4  221.55
  4203.6  224.78  4894.3  222.36  4966.6  221.95  4995.6  216.78  5024.6   221.7
  5456.2  220.11    5687  219.09  5815.7  222.01  6650.4  218.78  6656.2  216.32
  7341.8  229.93    7485  235.44  7512.1  240.84  7548.7  236.37  8147.4  264.01
  8510.1  262.68  8630.9  261.73  8674.8  257.71  8696.5  261.63  9160.6  277.27
  9566.7  287.05  9588.3  285.31  9718.9  293.13  9934.3  307.18 10058.7  313.13
#Mann= 11 ,-1 , 0
    2608     .11       0    4071     .15       0  4155.4     .11       0
  4894.3     .15       0  4966.6     .06       0  5024.6     .15       0
  5456.2     .11       0  8510.1     .17       0  8630.9     .11       0
  9718.9     .17       0  9934.3     .11       0
Bank Sta=4966.6,5024.6
XS Rating Curve= 0 ,0
Exp/Cntr=0.3,0.1

Type RM Length L Ch R = 1 ,225034  ,1034,1034,1034
BEGIN DESCRIPTION:
LAKE CREEK 216.0
END DESCRIPTION:
XS GIS Cut Line= 3
      3733367.89      10154811.1      3731579.53     10153634.24
      3728941.95     10151086.89
#Sta/Elev= 30
  2684.6  265.76  3276.5  246.17    3356   240.6  3493.4  230.57  3695.2  223.19
    3882  220.63  4491.3   220.6    4654  220.24  4970.3  218.02  4977.5  220.18
  5005.8  216.08  5019.9  217.27  5026.9  221.42  5321.7  221.27  6165.4  220.19
  6377.7  218.07  6391.8  214.23  6553.6  213.76  6639.3  214.66  6688.9  219.69
  6971.7  219.25  7282.9  227.61  7530.4  228.62  7813.4  233.75  7855.8  235.37
  7891.1  240.99  7926.6  236.26  7950.3   238.2    8311   251.3  8492.3  262.43
#Mann= 9 ,-1 , 0
  2684.6     .17       0    3356     .15       0  4491.3     .11       0
    4654     .15       0  4977.5     .06       0  5026.9     .15       0
  5321.7     .11       0  7950.3     .17       0    8311     .11       0
Bank Sta=4977.5,5026.9
XS Rating Curve= 0 ,0
Exp/Cntr=0.3,0.1

Type RM Length L Ch R = 1 ,224000  ,1000,1000,1000
BEGIN DESCRIPTION:
LAKE CREEK 215.0
END DESCRIPTION:
XS GIS Cut Line= 3
      3733405.93     10154092.59      3731788.02     10152666.65
      3729357.27     10150953.66
#Sta/Elev= 30
  2843.4  248.28  3067.7  242.36  3154.9  240.05  3424.3  223.58  3594.1  217.85
  4685.1  220.93  4961.2  218.53  4989.7  214.62  5012.3  217.98  5104.7  219.41
  5140.4  216.65  5183.7  219.14  5247.5  217.26  5312.8  220.59  5693.8  220.33
  6540.8  220.56    6590   218.8    6627  218.47  6632.9  213.51  6662.9  213.51
  6698.4  218.54  6884.2  217.95  6950.1  222.64  7156.5  231.61  7314.2  229.76
  7475.7  231.61  7637.6  236.61  7688.6  240.98  7716.1  237.88  7973.7  250.83
#Mann= 9 ,-1 , 0
  2843.4     .17       0  3067.7     .15       0  4961.2     .06       0
  5012.3     .15       0  5693.8     .11       0    6590     .15       0
  6950.1     .11       0  7475.7     .17       0  7637.6     .11       0
Bank Sta=4961.2,5012.3
XS Rating Curve= 0 ,0
Exp/Cntr=0.3,0.1

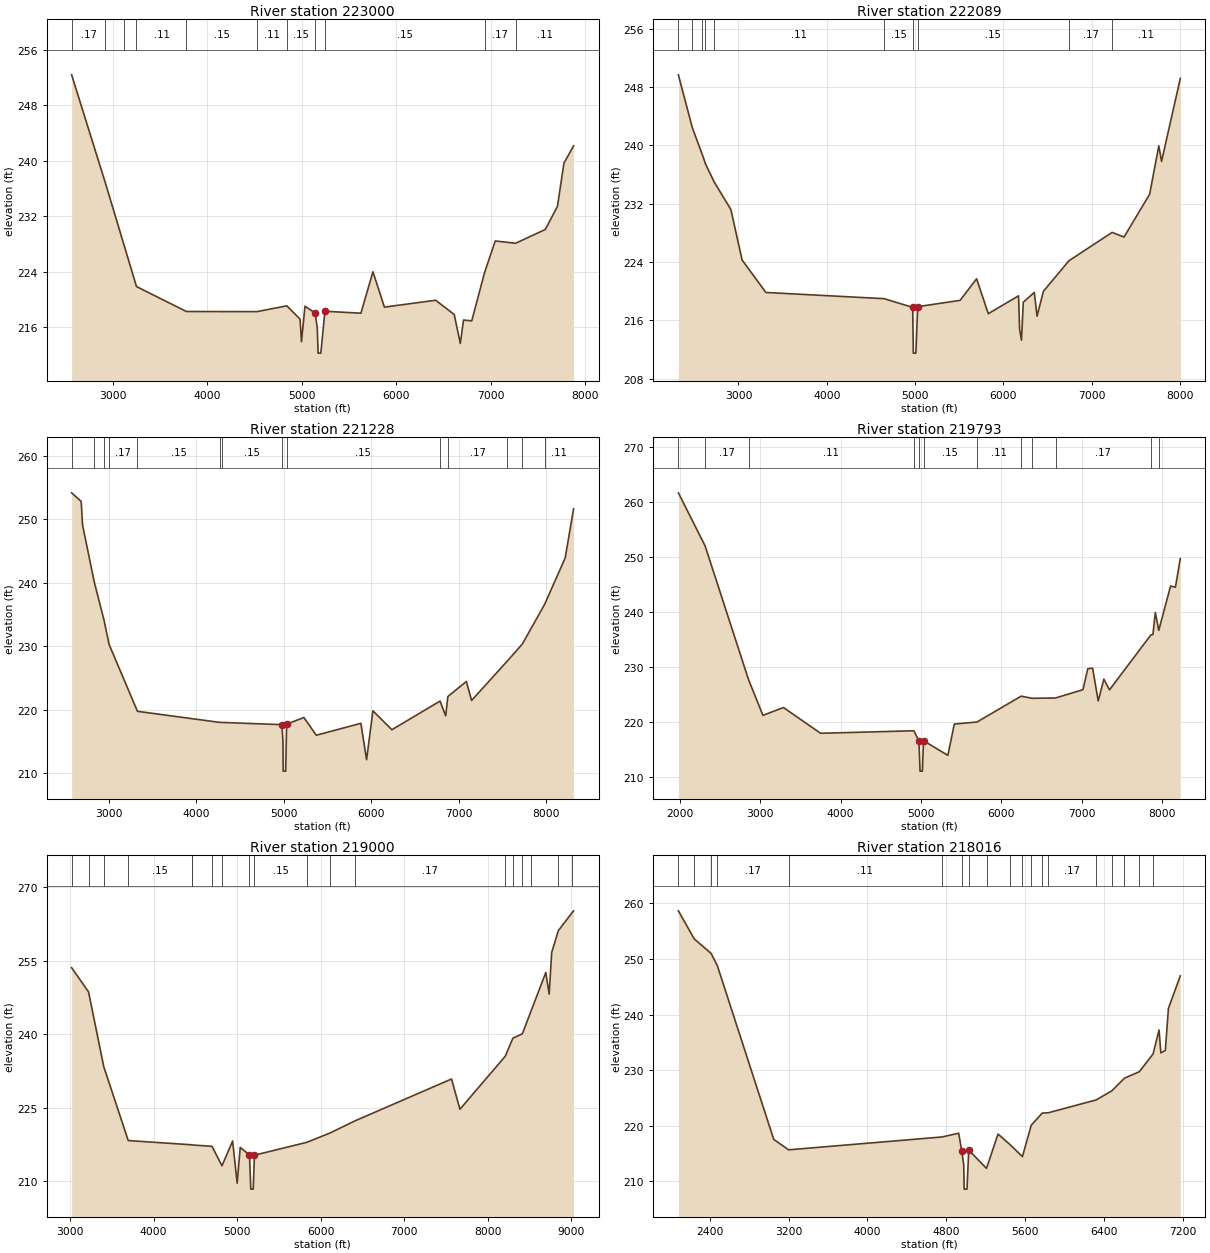
Type RM Length L Ch R = 1 ,223000  ,911,911,911
BEGIN DESCRIPTION:
LAKE CREEK 214.0
END DESCRIPTION:
XS GIS Cut Line= 3
      3734322.55     10153293.94      3732327.21      10151894.1
      3729704.52     10150717.57
#Sta/Elev= 30
  2562.6  252.36  2917.5   236.9  3114.9  227.96    3249  221.89  3777.6   218.3
  4524.5  218.28  4839.7  219.12    4980   217.2  4994.8  213.95  5032.2  219.06
    5139  218.09  5162.2  215.94  5170.9  212.31  5199.9  212.31  5242.7  218.33
    5624  218.06  5751.3  224.02  5872.7  218.93  6415.4  219.92  6611.8  217.86
  6675.8   213.7    6710  217.07  6796.8  216.95  6931.8  223.87  7045.4  228.45
  7260.8  228.12  7574.9   230.1    7704  233.43  7772.2  239.63  7874.5  242.14
#Mann= 11 ,-1 , 0
  2562.6     .17       0  2917.5     .11       0  3114.9     .15       0
    3249     .11       0  3777.6     .15       0  4524.5     .11       0
  4839.7     .15       0    5139     .06       0  5242.7     .15       0
  6931.8     .17       0  7260.8     .11       0
Bank Sta=5139,5242.7
XS Rating Curve= 0 ,0
Exp/Cntr=0.3,0.1

Type RM Length L Ch R = 1 ,222089  ,861,861,861
BEGIN DESCRIPTION:
LAKE CREEK 213.0
END DESCRIPTION:
XS GIS Cut Line= 3
      3734467.88      10153211.1      3732419.81     10151266.19
      3729662.91      10150516.2
#Sta/Elev= 30
  2320.3  249.69    2478  242.45  2592.9  238.69  2626.8  237.49  2724.2  235.02
  2914.4  231.22  3041.8  224.29  3310.7  219.84  4649.2  218.99  4972.8  217.79
  4979.7  211.52  5008.7  211.52  5029.4  217.89  5509.5  218.76    5696  221.72
  5828.2  216.93  6170.6  219.38  6183.1  214.73  6203.8   213.3  6224.5  218.51
  6348.9  219.84    6380  216.59  6452.5     220  6741.2  224.19  7229.9  228.08
  7364.5  227.44  7654.5  233.31  7758.3  239.95  7789.4  237.82  8001.8  249.21
#Mann= 10 ,-1 , 0
  2320.3     .11       0    2478     .17       0  2592.9     .11       0
  2626.8     .17       0  2724.2     .11       0  4649.2     .15       0
  4972.8     .06       0  5029.4     .15       0  6741.2     .17       0
  7229.9     .11       0
Bank Sta=4972.8,5029.4
XS Rating Curve= 0 ,0
Exp/Cntr=0.3,0.1

Type RM Length L Ch R = 1 ,221228  ,1435,1435,1435
BEGIN DESCRIPTION:
LAKE CREEK 212.0
END DESCRIPTION:
XS GIS Cut Line= 3
      3735017.85     10152361.07      3732926.75      10151127.3
       3729704.5     10150370.35
#Sta/Elev= 30
  2573.6  254.18  2682.9  252.83  2698.5   249.1  2833.1  240.09  2945.2  234.04
  3001.5  230.31  3326.2  219.77  4270.1  218.02  4289.5  218.02    4977  217.67
  4989.4  215.03  4991.7  210.35  5020.7  210.35  5031.2  217.75  5228.5  218.79
  5370.2     216  5880.1  217.88  5945.4  212.15  6017.6  219.85  6234.7  216.87
  6784.9  221.38  6849.4  219.06  6874.5   222.1  7085.7  224.47  7145.9  221.48
  7555.4  227.71  7725.5  230.36  7979.6  236.59  8215.6  243.92  8311.5  251.66
#Mann= 14 ,-1 , 0
  2573.6     .11       0  2833.1     .17       0  2945.2     .15       0
  3001.5     .17       0  3326.2     .15       0  4270.1     .11       0
  4289.5     .15       0    4977     .06       0  5031.2     .15       0
  6784.9     .11       0  6874.5     .17       0  7555.4     .11       0
  7725.5     .17       0  7979.6     .11       0
Bank Sta=4977,5031.2
XS Rating Curve= 0 ,0
Exp/Cntr=0.3,0.1

Type RM Length L Ch R = 1 ,219793  ,793,793,793
BEGIN DESCRIPTION:
LAKE CREEK 211.0
END DESCRIPTION:
XS GIS Cut Line= 3
      3735308.68     10152189.78      3732885.08     10150217.57
      3729767.01     10150259.24
#Sta/Elev= 30
    1982  261.68  2314.9     252  2854.9  227.65  3033.7  221.16  3289.3  222.58
  3751.1  217.89  4910.7  218.35  4974.1  216.51  4987.8     211  5016.8     211
    5031  216.55  5333.9  213.87  5413.9  219.57  5696.7  219.95    6245  224.65
  6383.9  224.26  6673.3  224.32    7014  225.83  7074.1  229.65  7134.1  229.76
  7204.1  223.78  7274.1  227.75  7344.1   225.8  7858.3  235.79  7884.1  235.86
  7914.1  239.89    7957  236.64  8104.1  244.71  8164.1  244.49    8225  249.71
#Mann= 12 ,-1 , 0
    1982     .11       0  2314.9     .17       0  2854.9     .11       0
  4910.7     .15       0  4974.1     .06       0    5031     .15       0
  5696.7     .11       0    6245     .17       0  6383.9     .11       0
  6673.3     .17       0  7858.3     .11       0    7957     .17       0
Bank Sta=4974.1,5031
XS Rating Curve= 0 ,0
Exp/Cntr=0.3,0.1

Type RM Length L Ch R = 1 ,219000  ,984,984,984
BEGIN DESCRIPTION:
LAKE CREEK 210.0
END DESCRIPTION:
XS GIS Cut Line= 3
      3735317.88     10150261.08      3733414.27     10149709.89
      3729417.87     10150211.07
#Sta/Elev= 30
  3018.2  253.57  3220.3  248.65    3403  233.36    3696  218.28    4457  217.41
  4461.5  217.38  4698.7   217.1  4817.9  213.12  4945.6  218.18    5000  209.57
  5036.7  216.88  5147.6  215.33  5163.3  208.36  5192.3  208.36  5206.7  215.29
  5834.2  217.92  6115.6  219.85  6411.8  222.31  7566.4  230.85  7667.1  224.67
  8209.9   235.5  8301.1  239.18  8414.7  240.08  8515.8  244.61  8695.1  252.59
  8735.5  248.19  8765.7  256.68  8845.7  261.16  9005.7  264.72  9027.7  265.19
#Mann= 19 ,-1 , 0
  3018.2     .17       0  3220.3     .11       0    3403     .17       0
    3696     .15       0    4457     .11       0  4461.5     .15       0
  4698.7     .11       0  4817.9     .15       0  5147.6     .06       0
  5206.7     .15       0  5834.2     .17       0  6115.6     .11       0
  6411.8     .17       0  8209.9     .11       0  8301.1     .17       0
  8414.7     .11       0  8515.8     .17       0  8845.7     .11       0
  9005.7     .17       0
Bank Sta=5147.6,5206.7
XS Rating Curve= 0 ,0
Exp/Cntr=0.3,0.1

Type RM Length L Ch R = 1 ,218016  ,963,963,963
BEGIN DESCRIPTION:
LAKE CREEK 209.0
END DESCRIPTION:
XS GIS Cut Line= 4
      3735648.94     10150210.61      3733225.36     10148884.24
      3732989.25     10148918.96      3731067.83     10148111.06
#Sta/Elev= 30
  2084.2  258.65  2245.4  253.59  2415.8  250.99  2478.9   248.8  3050.3  217.54
  3201.4  215.66  4754.7  217.97  4924.3  218.65  4955.7  215.42  4975.9  212.89
  4979.5  208.59  5008.5  208.59  5026.4  215.61  5206.3  212.32  5322.8   218.5
  5445.2  216.59  5570.1  214.44  5659.4  220.08    5771  222.27  5834.2  222.33
    6318  224.64  6475.5  226.26    6604  228.54  6754.8  229.71  6893.8   232.9
  6954.6  237.22  6972.9   233.1  7018.1  233.54  7049.6  241.11    7170  246.96
#Mann= 19 ,-1 , 0
  2084.2     .11       0  2245.4     .17       0  2415.8     .15       0
  2478.9     .17       0  3201.4     .11       0  4754.7     .15       0
  4955.7     .06       0  5026.4     .15       0  5206.3     .11       0
  5445.2     .17       0  5570.1     .15       0  5659.4     .17       0
    5771     .15       0  5834.2     .17       0    6318     .11       0
  6475.5     .17       0    6604     .11       0  6754.8     .17       0
  6893.8     .11       0
Bank Sta=4955.7,5026.4
XS Rating Curve= 0 ,0
Exp/Cntr=0.3,0.1