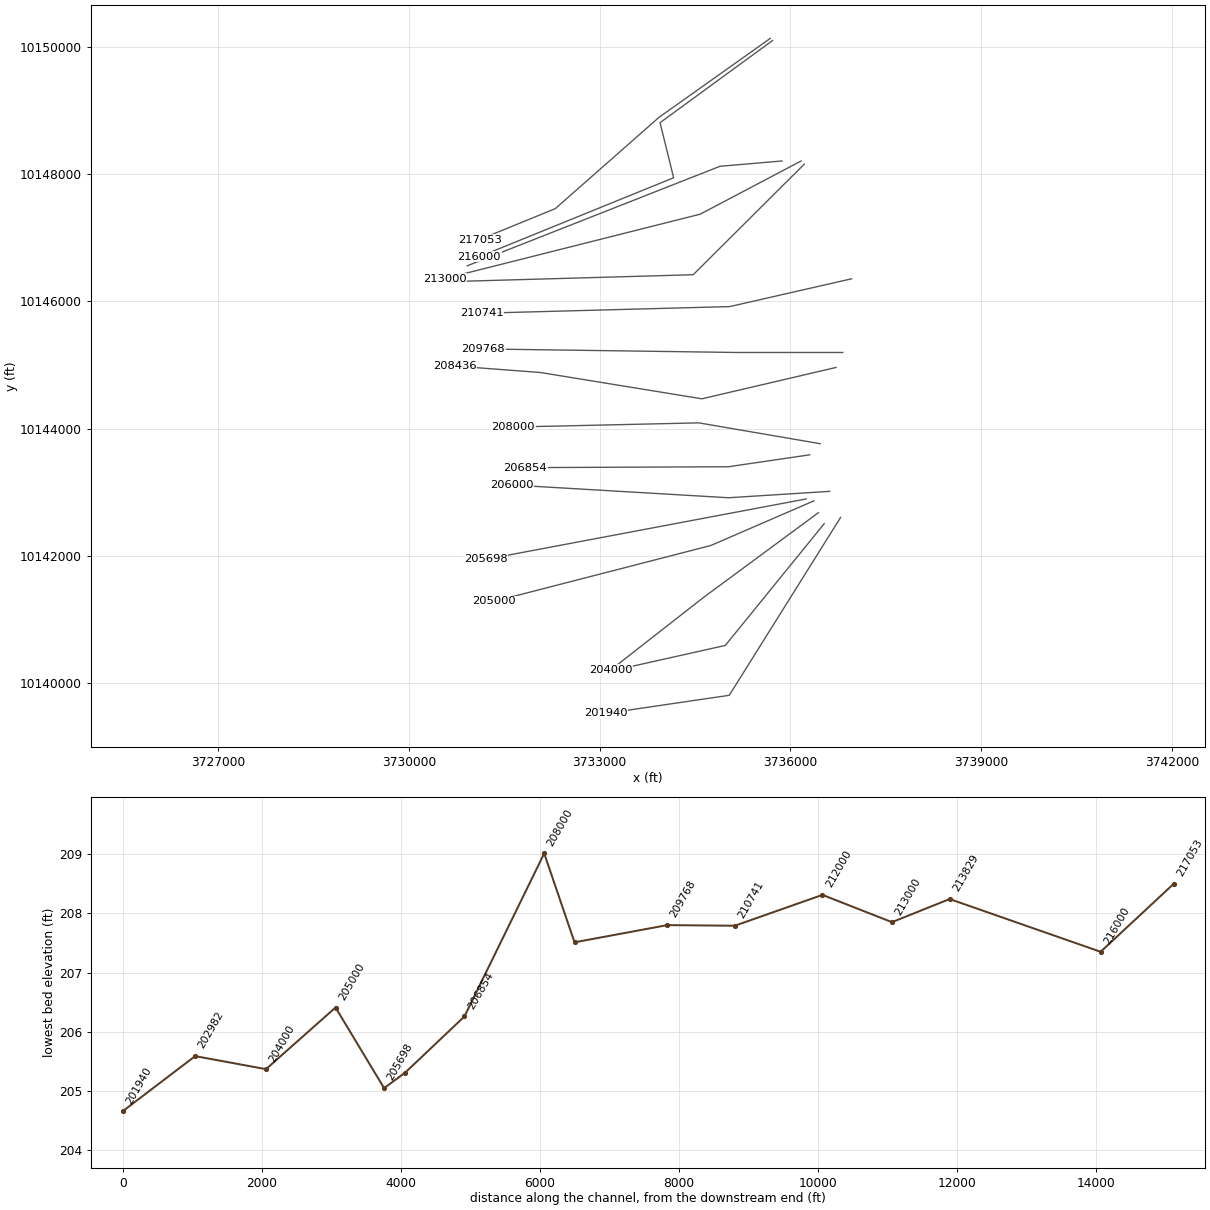
HEC-RAS study LAKE CREEK.prj: LAKE CREEK Base Level Engineering

--- LAKE CREEK.g01 (geometry) --- (continued)

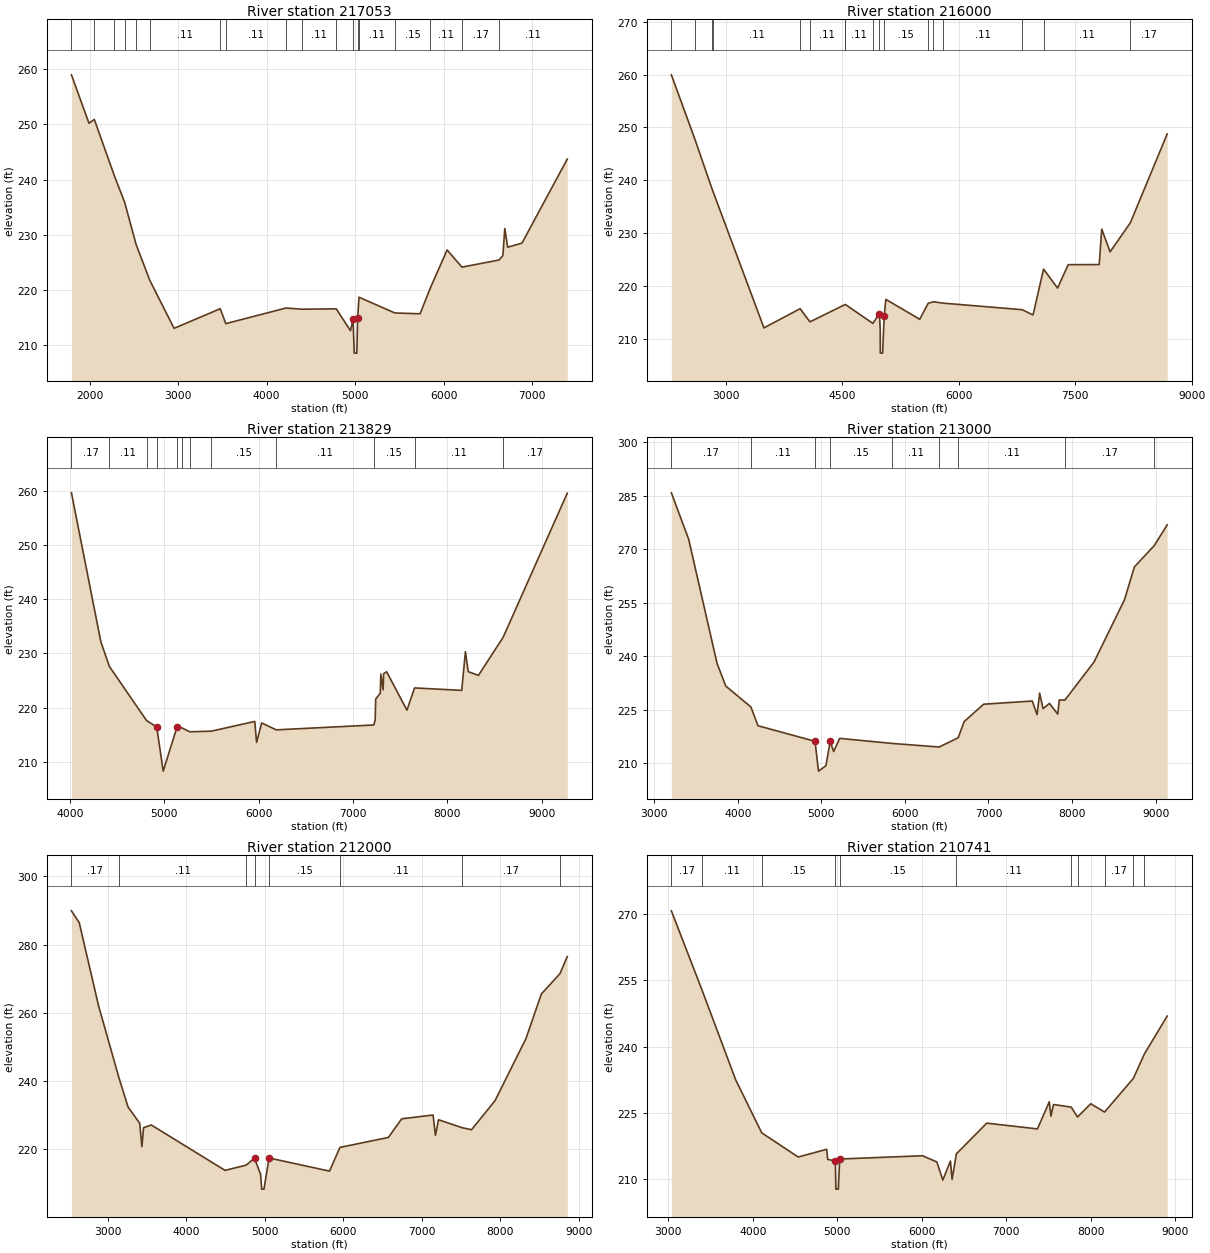
Type RM Length L Ch R = 1 ,217053  ,1053,1053,1053
BEGIN DESCRIPTION:
LAKE CREEK 208.0
END DESCRIPTION:
XS GIS Cut Line= 4
      3735683.72      10150141.2       3733933.7     10148898.13
      3732301.97     10147460.38      3731114.26     10146974.52
#Sta/Elev= 30
  1794.3  259.01  1992.4  250.22    2053  250.91    2279   240.7  2395.9  235.87
  2524.3  228.26  2678.4  221.76  2954.3     213  3476.6  216.56  3538.6  213.85
  4218.4  216.68  4402.5  216.47  4787.5  216.54  4948.6  212.57  4977.1  214.61
    4991   208.5    5020   208.5 5029.48214.9212  5044.7  218.65    5449  215.79
  5735.1  215.64  5847.9   220.2  6040.5  227.23  6207.8  224.11  6627.7   225.4
  6671.1  226.18  6692.7  231.12  6725.2  227.72  6887.2  228.47  7398.9  243.72
#Mann= 18 ,-1 , 0
  1794.3     .11       0    2053     .15       0    2279     .17       0
  2395.9     .11       0  2524.3     .17       0  2678.4     .11       0
  3476.6     .15       0  3538.6     .11       0  4218.4     .15       0
  4402.5     .11       0  4787.5     .15       0  4977.1     .06       0
 5029.48     .15       0  5044.7     .11       0    5449     .15       0
  5847.9     .11       0  6207.8     .17       0  6627.7     .11       0
Bank Sta=4977.1,5029.48
XS Rating Curve= 0 ,0
Exp/Cntr=0.3,0.1

Type RM Length L Ch R = 1 ,216000  ,2171,2171,2171
BEGIN DESCRIPTION:
LAKE CREEK 207.0
END DESCRIPTION:
XS GIS Cut Line= 5
      3735718.41     10150106.45      3733949.24     10148813.49
      3734071.31     10148321.17      3734162.86     10147946.74
       3731107.3     10146703.68
#Sta/Elev= 30
  2301.5  259.95  2602.7  247.84  2826.4  238.33  2840.4  237.78    3493  212.12
  3958.8  215.75  4085.4  213.26  4533.1   216.5    4542  216.54  4895.3  212.97
  4979.5   214.8  4989.8  211.91  4991.4  207.35  5020.4  207.35  5041.3  214.32
  5061.9  217.51  5498.8  213.75    5607  216.75  5675.3  217.06  5797.2   216.8
  6817.6  215.56  6957.3  214.56  7092.5  223.23  7273.1  219.65  7409.7  224.07
  7809.1  224.09  7841.5  230.78  7949.5   226.5  8209.7  231.98  8684.2  248.78
#Mann= 17 ,-1 , 0
  2301.5     .11       0  2602.7     .15       0  2826.4     .17       0
  2840.4     .11       0  3958.8     .15       0  4085.4     .11       0
  4533.1     .15       0    4542     .11       0  4895.3     .15       0
  4979.5     .06       0  5041.3     .15       0    5607     .11       0
  5675.3     .15       0  5797.2     .11       0  6817.6     .15       0
  7092.5     .11       0  8209.7     .17       0
Bank Sta=4979.5,5041.3
XS Rating Curve= 0 ,0
Exp/Cntr=0.3,0.1

Type RM Length L Ch R = 1 ,213829  ,829,829,829
BEGIN DESCRIPTION:
LAKE CREEK 205.0
END DESCRIPTION:
XS GIS Cut Line= 3
      3735867.87     10148211.07      3734892.03      10148127.3
      3730917.85     10146561.07
#Sta/Elev= 30
    4018  259.69  4329.2  232.16  4419.4   227.6  4812.9   217.6  4921.3   216.4
  4989.5  208.24  5136.7  216.43  5185.6  216.25  5271.7  215.51  5500.2  215.63
  5959.6  217.43  5978.6  213.55  6032.8  217.15    6187  215.87  7219.8  216.77
  7234.7  217.68  7240.1  221.56  7288.9  222.66  7294.3  226.18  7318.6  223.29
    7324  226.25  7355.9  226.62  7570.8  219.51  7651.9  223.62  8151.3  223.17
  8190.3  230.32  8220.1  226.63  8328.4  225.94    8590  232.99  9269.1  259.62
#Mann= 12 ,-1 , 0
    4018     .17       0  4419.4     .11       0  4812.9     .15       0
  4921.3     .06       0  5136.7     .11       0  5185.6     .15       0
  5271.7     .11       0  5500.2     .15       0    6187     .11       0
  7219.8     .15       0  7651.9     .11       0    8590     .17       0
Bank Sta=4921.3,5136.7
XS Rating Curve= 0 ,0
Exp/Cntr=0.3,0.1

Type RM Length L Ch R = 1 ,213000  ,1000,1000,1000
BEGIN DESCRIPTION:
LAKE CREEK 204.0
END DESCRIPTION:
XS GIS Cut Line= 3
      3736167.87     10148211.08      3734581.25     10147373.57
      3730567.89     10146361.08
#Sta/Elev= 30
  3205.9  285.75  3412.3   272.8  3753.3  237.93  3857.7  231.64  4157.5  225.81
  4242.7  220.55  4924.7   216.2  4966.7  207.85  5055.1  209.38  5106.6  216.17
  5147.9  213.34  5220.1  217.02  5848.5   215.6  6410.4   214.6  6638.6   217.2
  6708.6   221.7  6942.4  226.58  7524.7  227.47  7581.8  223.67  7612.8  229.69
    7654  225.35  7730.1   226.8  7829.4  223.81  7848.1  227.76  7915.4  227.75
  8263.9   238.4  8628.4  255.84  8746.4     265    8985     271  9139.1   276.8
#Mann= 9 ,-1 , 0
  3205.9     .17       0  4157.5     .11       0  4924.7     .06       0
  5106.6     .15       0  5848.5     .11       0  6410.4     .15       0
  6638.6     .11       0  7915.4     .17       0    8985     .11       0
Bank Sta=4924.7,5106.6
XS Rating Curve= 0 ,0
Exp/Cntr=0.3,0.1

Type RM Length L Ch R = 1 ,212000  ,1259,1259,1259
BEGIN DESCRIPTION:
LAKE CREEK 203.0
END DESCRIPTION:
XS GIS Cut Line= 3
      3736217.88      10148161.1      3734470.78     10146420.47
      3730617.83     10146311.07
#Sta/Elev= 30
  2533.8  289.92  2632.8  286.47  2880.3  261.99  3137.6  241.09  3255.1  232.42
  3403.6  227.63  3431.9  220.79  3453.1  226.33  3552.1  227.12  4492.5   213.8
  4760.7  215.35  4867.3  217.38  4945.1  212.62  4958.9  208.31  4987.9  208.31
  5052.9  217.44  5823.3  213.59  5956.5  220.54  6573.6  223.46  6743.6  228.93
  7143.8  230.04  7173.8  224.13  7213.8  228.66  7509.6  226.35    7634  225.73
  7934.1  234.26  8327.6  252.44  8524.3  265.53  8762.4  271.54  8854.5  276.51
#Mann= 8 ,-1 , 0
  2533.8     .17       0  3137.6     .11       0  4760.7     .15       0
  4867.3     .06       0  5052.9     .15       0  5956.5     .11       0
  7509.6     .17       0  8762.4     .11       0
Bank Sta=4867.3,5052.9
XS Rating Curve= 0 ,0
Exp/Cntr=0.3,0.1

Type RM Length L Ch R = 1 ,210741  ,973,973,973
BEGIN DESCRIPTION:
LAKE CREEK 202.0
END DESCRIPTION:
XS GIS Cut Line= 3
      3736961.47     10146356.46      3735044.81     10145918.96
      3731142.46     10145814.81
#Sta/Elev= 30
  3037.4  270.64    3405  252.51  3799.1  232.46  4107.3   220.5  4538.7  215.04
  4876.8  216.79  4887.4   214.5    4973   214.2  4979.7  213.02  4984.7  207.79
  5013.7  207.79  5030.3  214.59  6010.7  215.33  6180.7  213.92  6250.8  209.83
  6340.8  214.13  6360.8  209.99  6411.3  215.76    6771  222.69  7371.2  221.39
  7511.2  227.51  7531.2  224.28  7561.2   226.9  7771.1  226.31  7845.3  224.08
  8001.4  227.07  8165.9   225.2  8507.3  232.82  8637.3  238.32  8907.1  246.88
#Mann= 11 ,-1 , 0
  3037.4     .17       0    3405     .11       0  4107.3     .15       0
    4973     .06       0  5030.3     .15       0  6411.3     .11       0
  7771.1     .17       0  7845.3     .11       0  8165.9     .17       0
  8507.3     .11       0  8637.3     .17       0
Bank Sta=4973,5030.3
XS Rating Curve= 0 ,0
Exp/Cntr=0.3,0.1

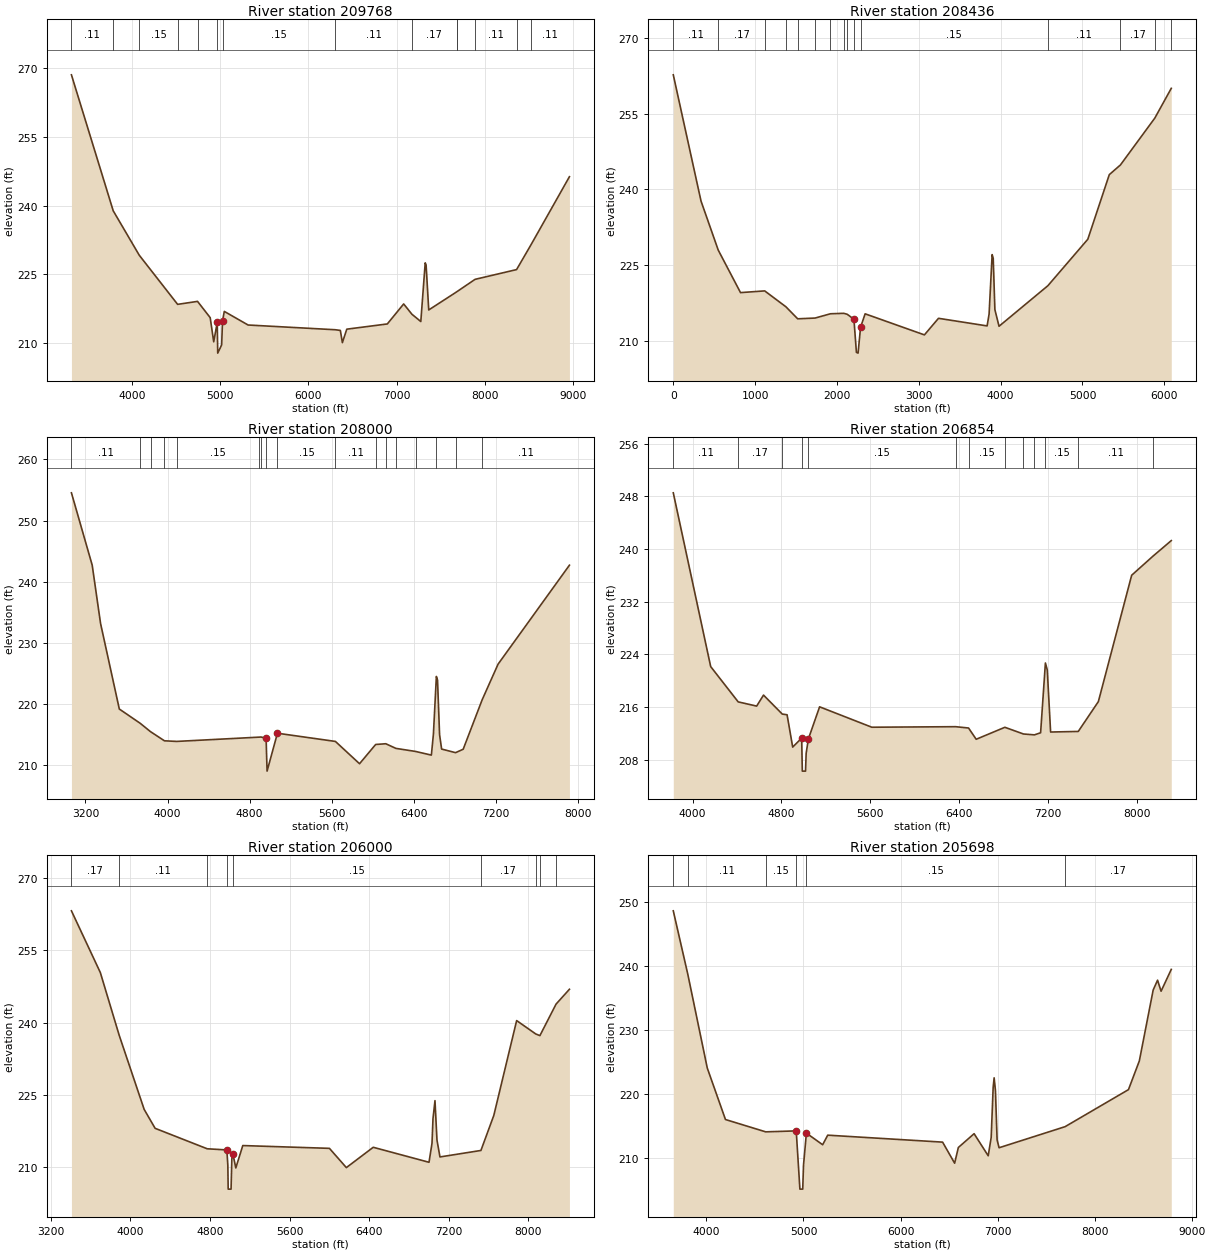
Type RM Length L Ch R = 1 ,209768  ,1332,1332,1332
BEGIN DESCRIPTION:
LAKE CREEK 201.0
END DESCRIPTION:
XS GIS Cut Line= 3
       3736822.6     10145196.74      3735155.92     10145196.74
      3731171.28     10145252.28
#Sta/Elev= 30
  3309.8  268.57  3783.7  238.89  4079.8  229.17  4514.8  218.45  4740.9   219.1
  4884.5  215.55  4924.5  210.27  4964.5  214.53    4970   207.8  5014.5  209.59
  5024.5  214.84  5044.6  216.91  5314.6  213.94  6301.5  212.91  6361.6  212.76
  6384.7  210.09  6434.7  213.03  6894.7  214.17  7080.4  218.54    7174  216.29
  7274.8   214.7  7324.8  227.52  7334.8  227.06  7364.8  217.23  7682.7  221.19
    7684  221.21  7890.5  223.91  8361.6  226.04  8522.7  231.37  8961.5  246.32
#Mann= 14 ,-1 , 0
  3309.8     .11       0  3783.7     .17       0  4079.8     .15       0
  4514.8     .17       0  4740.9     .15       0  4964.5     .06       0
  5024.5     .15       0  6301.5     .11       0    7174     .17       0
  7682.7     .11       0    7684     .17       0  7890.5     .11       0
  8361.6     .17       0  8522.7     .11       0
Bank Sta=4964.5,5024.5
XS Rating Curve= 0 ,0
Exp/Cntr=0.3,0.1

Type RM Length L Ch R = 1 ,208436  ,436,436,436
BEGIN DESCRIPTION:
LAKE CREEK 200.0
END DESCRIPTION:
XS GIS Cut Line= 4
      3736717.85     10144961.07      3734607.31     10144467.57
      3732067.97     10144881.53      3730726.72     10144983.32
#Sta/Elev= 30
       0  262.74   338.9  237.69   549.2  227.96   821.6  219.52  1117.1  219.86
  1376.1  216.71  1520.2  214.32  1732.7  214.47  1920.4  215.32  2082.9  215.41
  2125.4  215.22  2207.4  214.24  2237.8  207.67  2258.1  207.51  2288.5  212.65
  2344.4  215.31  3068.7  211.13  3240.9  214.42  3834.9  212.91    3859  215.25
  3896.4  227.06  3909.6  226.33  3929.9  216.15  3980.5  212.84  4577.7  220.89
  5065.5  230.11    5328  242.93  5464.3  244.86  5883.7  254.14  6085.4  260.06
#Mann= 15 ,-1 , 0
       0     .11       0   549.2     .17       0  1117.1     .11       0
  1376.1     .15       0  1520.2     .11       0  1732.7     .15       0
  1920.4     .17       0  2082.9     .11       0  2125.4     .17       0
  2207.4     .06       0  2288.5     .15       0  4577.7     .11       0
  5464.3     .17       0  5883.7     .11       0  6085.4     .17       0
Bank Sta=2207.4,2288.5
XS Rating Curve= 0 ,0
Exp/Cntr=0.3,0.1

Type RM Length L Ch R = 1 ,208000  ,1146,1146,1146
BEGIN DESCRIPTION:
LAKE CREEK 199.0
END DESCRIPTION:
XS GIS Cut Line= 3
       3736467.8     10143761.08      3734559.34     10144088.84
      3731642.48     10144023.14
#Sta/Elev= 30
  3063.6  254.54  3265.9  242.71  3347.7  233.15  3530.3  219.17  3733.4  216.84
  3834.2  215.47  3970.1  213.97  4089.6  213.87  4893.1  214.57  4909.9  214.59
  4960.9  214.42  4970.5  209.01  5071.5  215.21  5636.4  213.87  5871.7  210.22
    6029  213.37  6127.6  213.49  6226.3  212.73  6417.8  212.23  6571.9  211.63
  6591.9  215.07  6620.7   224.5  6631.9  223.91  6651.9  214.97  6671.9  212.62
  6807.6  212.03    6882  212.59  7067.2  220.69  7222.1  226.51  7917.6   242.7
#Mann= 17 ,-1 , 0
  3063.6     .11       0  3733.4     .17       0  3834.2     .15       0
  3970.1     .17       0  4089.6     .15       0  4893.1     .17       0
  4909.9     .15       0  4960.9     .06       0  5071.5     .15       0
  5636.4     .11       0    6029     .15       0  6127.6     .11       0
  6226.3     .15       0  6417.8     .11       0  6620.7     .15       0
  6807.6     .17       0  7067.2     .11       0
Bank Sta=4960.9,5071.5
XS Rating Curve= 0 ,0
Exp/Cntr=0.3,0.1

Type RM Length L Ch R = 1 ,206854  ,854,854,854
BEGIN DESCRIPTION:
LAKE CREEK 198.0
END DESCRIPTION:
XS GIS Cut Line= 3
       3736301.7     10143585.62      3735023.97     10143398.13
      3731831.22     10143384.25
#Sta/Elev= 30
  3825.8  248.54  4162.6  222.14  4410.3  216.78  4576.5  216.14  4638.3  217.81
    4807  214.93  4850.5  214.82    4901  209.91  4981.9  211.28  4987.6  206.26
  5016.6  206.26  5022.3  208.98  5042.5  211.16  5143.3  216.03  5613.3  212.93
  6368.2  213.01  6484.6  212.81  6553.3   211.1  6811.6  212.92  6979.2   211.9
  7077.9  211.77  7133.4  212.09  7176.6  222.69  7193.4  221.63  7223.4   212.2
  7472.6  212.29  7653.4  216.82  7953.4  236.02  8147.4  238.95    8310  241.28
#Mann= 13 ,-1 , 0
  3825.8     .11       0  4410.3     .17       0    4807     .15       0
  4981.9     .06       0  5042.5     .15       0  6368.2     .11       0
  6484.6     .15       0  6811.6     .11       0  6979.2     .15       0
  7077.9     .11       0  7176.6     .15       0  7472.6     .11       0
  8147.4     .17       0
Bank Sta=4981.9,5042.5
XS Rating Curve= 0 ,0
Exp/Cntr=0.3,0.1

Type RM Length L Ch R = 1 ,206000  ,302,302,302
BEGIN DESCRIPTION:
LAKE CREEK 197.0
END DESCRIPTION:
XS GIS Cut Line= 3
      3736617.89     10143011.07      3735027.18     10142910.24
      3731617.89     10143111.07
#Sta/Elev= 30
  3406.1  263.25  3696.7   250.4  3886.6  237.33  4137.6  221.91  4247.8  217.97
  4771.8  213.71  4969.3  213.47  4979.3  210.27  4982.7  205.31  5011.7  205.31
  5019.4   211.6  5029.4  212.72  5059.4  209.72  5129.6  214.38  6001.1   213.8
  6171.4  209.79  6441.8  214.02  7002.8   210.9  7032.8  214.84  7042.9     220
  7062.9  223.73  7082.9  215.52    7113  212.01    7525  213.36  7654.5  220.65
  7884.3   240.4  8076.8  237.61  8118.2  237.27  8280.8  243.83  8415.2  246.92
#Mann= 9 ,-1 , 0
  3406.1     .17       0  3886.6     .11       0  4771.8     .15       0
  4969.3     .09       0  5029.4     .15       0    7525     .17       0
  8076.8     .11       0  8118.2     .17       0  8280.8     .11       0
Bank Sta=4969.3,5029.4
XS Rating Curve= 0 ,0
Exp/Cntr=0.3,0.1

Type RM Length L Ch R = 1 ,205698  ,698,698,698
BEGIN DESCRIPTION:
Mapping XS c31493c1
END DESCRIPTION:
XS GIS Cut Line= 2
      3736246.16     10142891.18      3731204.54      10141939.8
#Sta/Elev= 30
  3658.8  248.63  3808.5  238.69    4009  224.01  4196.4  215.95  4610.7  214.02
  4925.4  214.17  4963.3  205.05  4992.3  205.05  5000.4  208.79  5030.2  213.82
  5197.6     212    5250   213.5  6433.4  212.41  6557.4  209.11  6595.7  211.57
    6758  213.73  6903.4  210.27  6933.9  213.14  6954.3  220.97  6964.4  222.48
  6977.8  220.49    6995  212.76  7015.3  211.53  7695.4  214.83  8348.4  220.63
  8460.4  225.13  8602.9  236.23  8648.2  237.77  8684.3  236.04  8789.4  239.46
#Mann= 6 ,-1 , 0
  3658.8     .17       0  3808.5     .11       0  4610.7     .15       0
  4925.4     .09       0  5030.2     .15       0  7695.4     .17       0
Bank Sta=4925.4,5030.2
XS Rating Curve= 0 ,0
Exp/Cntr=0.3,0.1

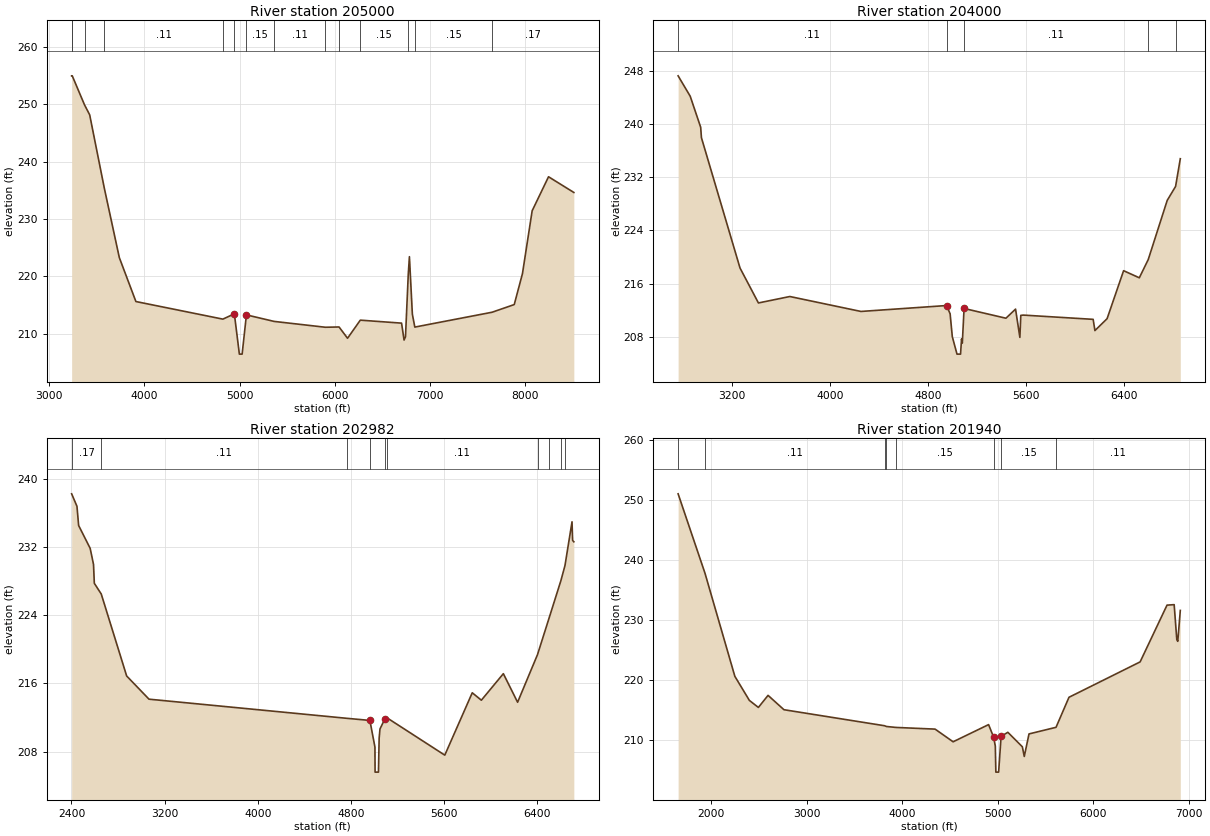
Type RM Length L Ch R = 1 ,205000  ,1000,1000,1000
BEGIN DESCRIPTION:
LAKE CREEK 196.0
END DESCRIPTION:
XS GIS Cut Line= 3
       3736367.9     10142861.09      3734748.24     10142158.69
      3731343.38     10141280.07
#Sta/Elev= 30
  3234.6  254.99    3241  254.99  3370.1  249.92  3424.3  248.18  3578.4  235.36
    3736  223.26  3910.4  215.59    4825  212.52  4945.9  213.44  4998.7  206.41
  5027.7  206.41  5072.7  213.26  5364.2  212.12  5903.9   211.1    6047  211.15
  6136.4  209.18  6270.7  212.34  6704.5  211.82  6730.8  208.87  6745.8  209.44
  6775.3  220.45  6787.1  223.42  6818.1  213.38    6844  211.13    7656  213.72
  7889.5  215.06    7976  220.46    8078  231.43  8250.3  237.37  8516.4  234.63
#Mann= 14 ,-1 , 0
  3234.6     .17       0    3241     .11       0  3370.1     .17       0
  3578.4     .11       0    4825     .15       0  4945.9     .09       0
  5072.7     .15       0  5364.2     .11       0  5903.9     .15       0
    6047     .11       0  6270.7     .15       0  6775.3     .11       0
    6844     .15       0    7656     .17       0
Bank Sta=4945.9,5072.7
XS Rating Curve= 0 ,0
Exp/Cntr=0.3,0.1

Type RM Length L Ch R = 1 ,204000  ,1018,1018,1018
BEGIN DESCRIPTION:
LAKE CREEK 195.0
END DESCRIPTION:
XS GIS Cut Line= 3
      3736440.61     10142675.88      3734637.83     10141344.85
      3733171.36     10140197.95
#Sta/Elev= 30
  2759.1   247.3  2857.8  244.23  2943.4  239.55  2949.6  237.98  3264.9  218.34
  3415.2  213.08    3672  214.05  4252.6   211.8    4952  212.69  4981.2  211.45
    4999  208.01  5037.4  205.37  5066.4  205.37  5074.5  207.65  5080.8  207.03
  5095.3  212.25  5437.1  210.78  5515.8  212.15  5551.1  207.89  5558.6  211.21
    5580  211.25  6149.7  210.61  6164.2  208.92  6263.6  210.71  6398.4  217.94
  6526.8  216.87  6599.8  219.62  6754.7  228.53  6823.2  230.64  6861.7  234.81
#Mann= 5 ,-1 , 0
  2759.1     .11       0    4952     .06       0  5095.3     .11       0
  6599.8     .17       0  6823.2     .11       0
Bank Sta=4952,5095.3
XS Rating Curve= 0 ,0
Exp/Cntr=0.3,0.1

Type RM Length L Ch R = 1 ,202982  ,1042,1042,1042
BEGIN DESCRIPTION:
LAKE CREEK 194.0
END DESCRIPTION:
XS GIS Cut Line= 3
      3736530.89     10142502.26      3734975.36     10140585.63
      3733176.74     10140182.85
#Sta/Elev= 30
  2401.5  238.21  2447.1  236.75  2461.4   234.5  2560.5  231.82  2589.3  229.93
  2596.2  227.72  2655.6  226.47  2873.8  216.86  3065.6  214.14  4762.2   211.9
  4962.1  211.65  5005.5  208.52  5006.6  205.59  5035.6  205.59  5041.6  209.58
  5048.8  210.65  5092.2  211.87  5110.7  211.94  5605.2  207.58  5840.9  214.89
  5919.1  214.02    6108  217.13  6230.3  213.78  6401.1  219.36    6502  223.71
  6602.3  228.05    6637   229.8  6697.5  234.93  6702.6  232.75  6713.1  232.59
#Mann= 10 ,-1 , 0
  2401.5     .17       0  2655.6     .11       0  4762.2     .15       0
  4962.1     .09       0  5092.2     .15       0  5110.7     .11       0
  6401.1     .17       0    6502     .11       0  6602.3     .17       0
    6637     .11       0
Bank Sta=4962.1,5092.2
XS Rating Curve= 0 ,0
Exp/Cntr=0.3,0.1

Type RM Length L Ch R = 1 ,201940  ,709,709,709
BEGIN DESCRIPTION:
LAKE CREEK 193.0
END DESCRIPTION:
XS GIS Cut Line= 3
      3736787.89     10142599.56      3735037.86     10139800.91
      3733101.62     10139516.37
#Sta/Elev= 30
  1651.9  250.99  1933.3  237.77  2245.9  220.61    2398   216.6  2492.3  215.43
  2593.6  217.44    2760  215.05    3814  212.38  3831.7  212.26  3932.9   212.1
  4342.4  211.82    4531  209.71  4902.5  212.57  4955.2  210.48  4972.9  208.99
  4978.6  204.66  5007.6  204.66  5033.5  210.62  5104.3  211.29  5255.9  208.88
  5276.1  207.27  5325.7  211.02  5608.6  212.12  5744.3  217.12    6489  223.01
  6770.6  232.46  6845.4  232.54  6873.1  226.71  6883.2  226.43  6909.7  231.58
#Mann= 8 ,-1 , 0
  1651.9     .17       0  1933.3     .11       0    3814     .15       0
  3831.7     .11       0  3932.9     .15       0  4955.2     .09       0
  5033.5     .15       0  5608.6     .11       0
Bank Sta=4955.2,5033.5
XS Rating Curve= 0 ,0
Exp/Cntr=0.3,0.1