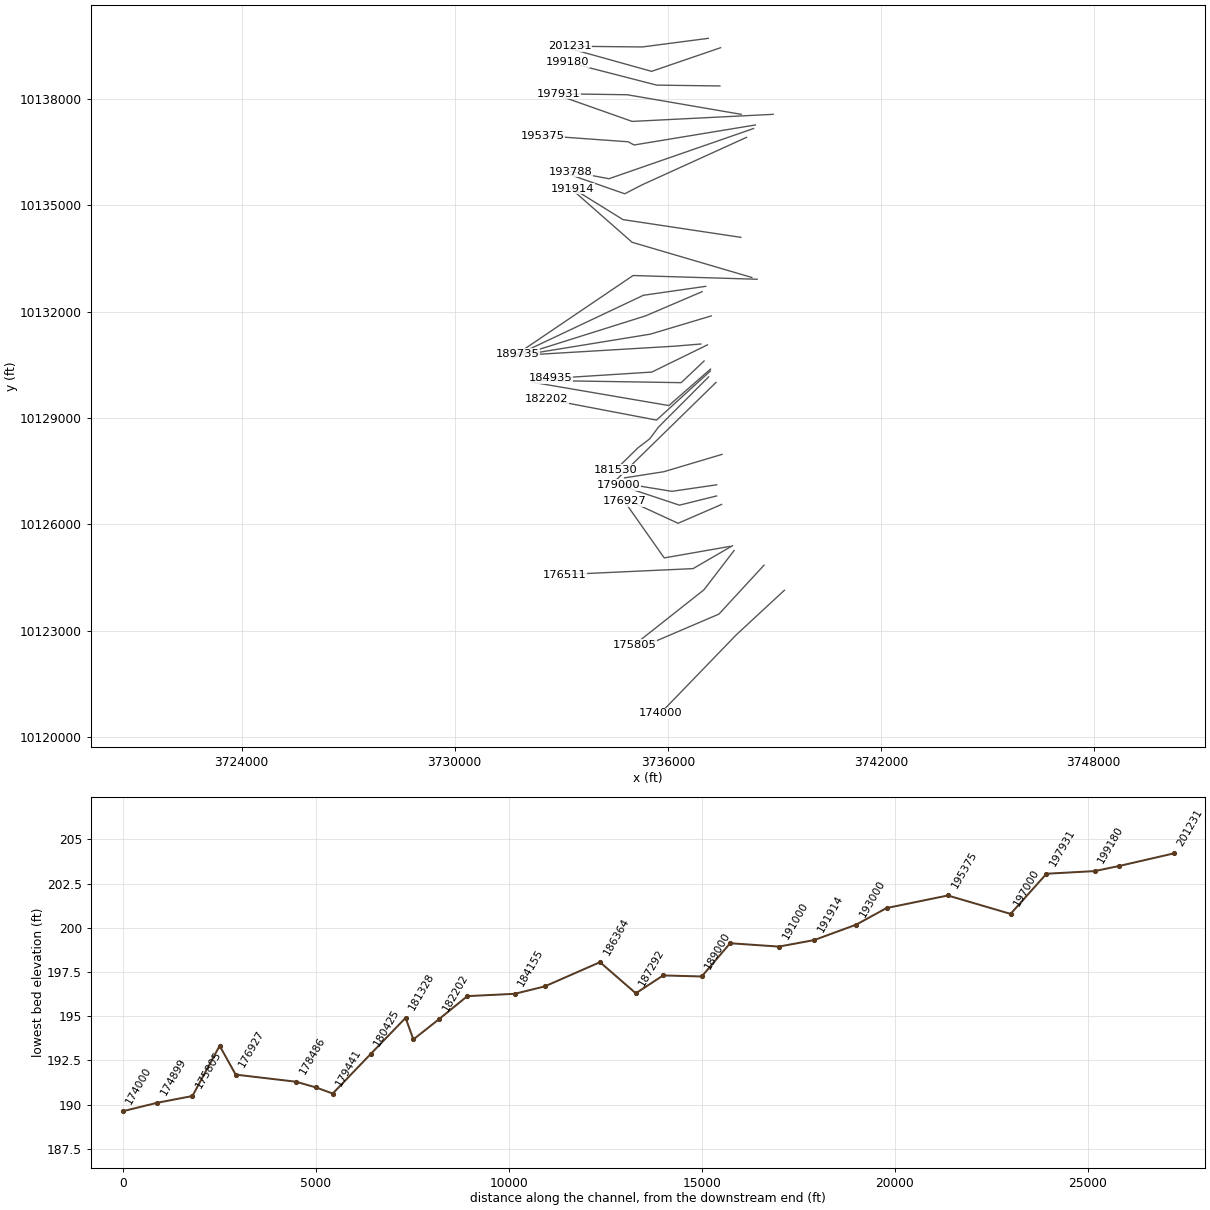
HEC-RAS study LAKE CREEK.prj: LAKE CREEK Base Level Engineering

--- LAKE CREEK.g01 (geometry) --- (continued)

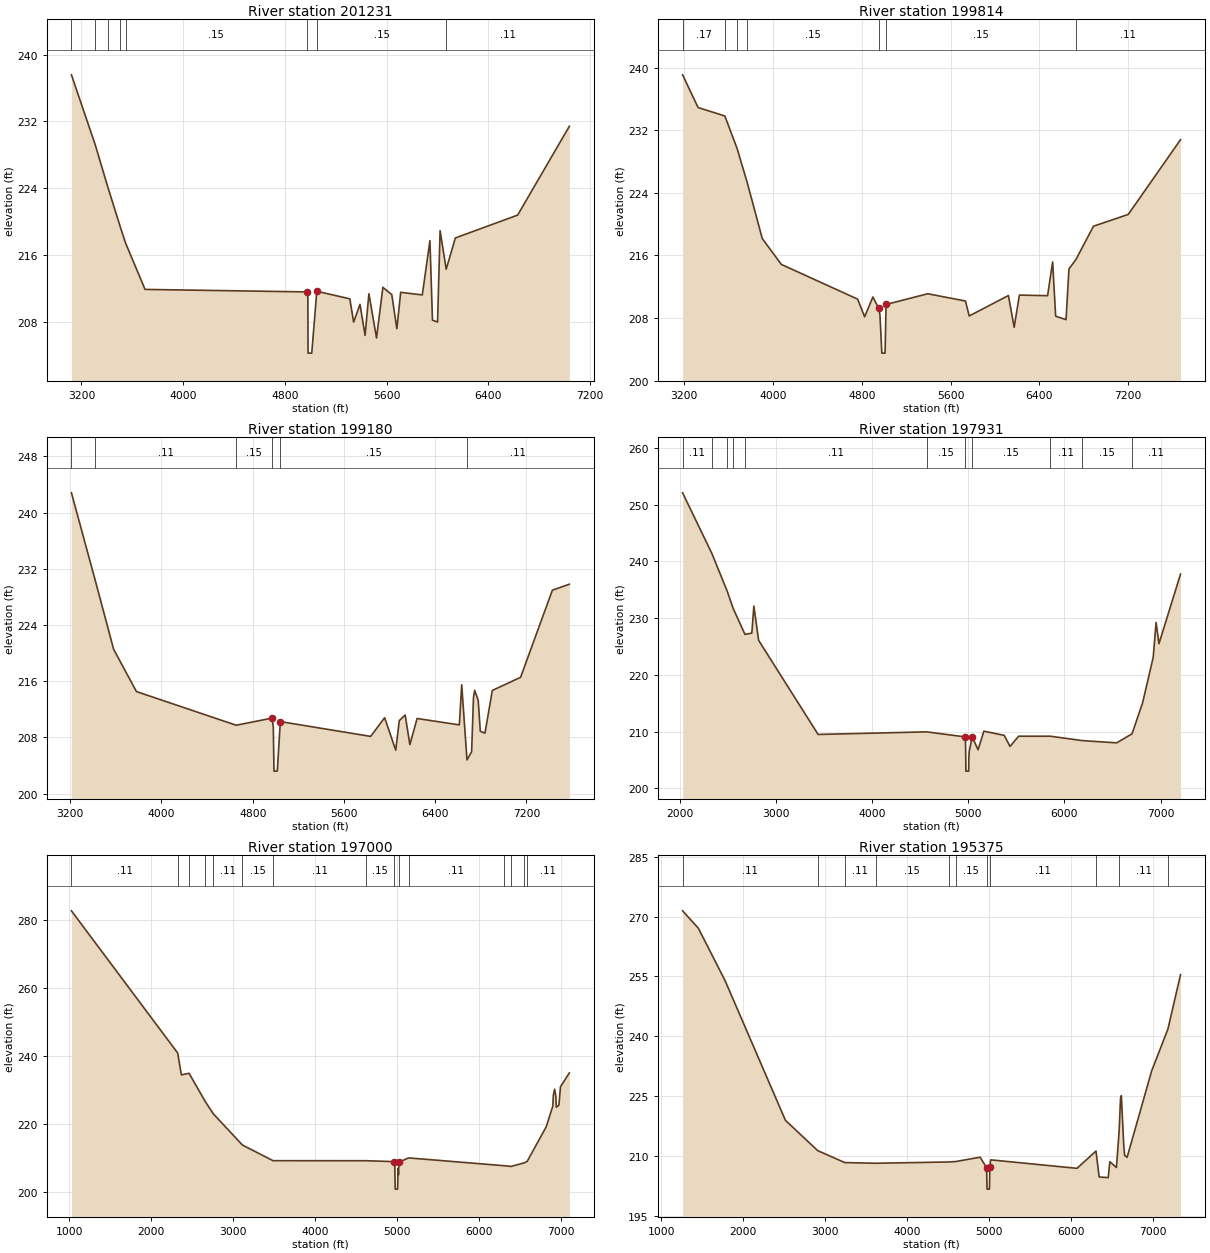
Type RM Length L Ch R = 1 ,201231  ,1417,1417,1417
BEGIN DESCRIPTION:
LAKE CREEK 192.0
END DESCRIPTION:
XS GIS Cut Line= 3
      3737142.06     10139703.69      3735280.92     10139460.63
      3733241.07     10139481.45
#Sta/Elev= 30
  3121.1  237.58  3308.4  229.19  3407.4  224.12  3506.4   219.3  3546.7  217.42
  3700.2  211.85  4970.9  211.55    4981  210.91  4982.6  204.21  5011.6  204.21
  5051.1  211.63  5311.1  210.72  5341.1  207.93  5391.1  210.06  5431.1  206.34
  5461.1  211.33  5521.1  206.03  5571.1   212.1  5641.1  211.23  5681.1  207.14
  5711.1   211.5  5881.2  211.19  5941.2   217.7  5961.2  208.16  6001.2  207.94
  6021.2  218.89  6069.2  214.27  6141.2  218.02  6631.2  220.76    7038  231.41
#Mann= 8 ,-1 , 0
  3121.1     .17       0  3308.4     .15       0  3407.4     .11       0
  3506.4     .17       0  3546.7     .15       0  4970.9     .09       0
  5051.1     .15       0  6069.2     .11       0
Bank Sta=4970.9,5051.1
XS Rating Curve= 0 ,0
Exp/Cntr=0.3,0.1

Type RM Length L Ch R = 1 ,199814  ,634,634,634
BEGIN DESCRIPTION:
LAKE CREEK 191.0
END DESCRIPTION:
XS GIS Cut Line= 3
      3737489.22     10139439.79      3735544.81     10138773.13
      3733204.56      10139425.9
#Sta/Elev= 30
  3186.7  239.07  3326.2  234.89  3567.3  233.81  3678.8  229.61  3767.9  225.35
  3904.5  218.14  4076.1  214.84  4763.3   210.4  4826.7  208.14  4900.7  210.67
    4952  209.28  4964.1  208.43  4981.4   203.5  5010.4   203.5  5019.8  209.72
  5394.8  211.09  5734.6  210.16  5768.5  208.25  6121.5  210.86  6173.4   206.8
  6220.5  210.92  6474.5  210.84  6519.9  215.15  6547.2  208.22  6640.6  207.78
    6667  214.27  6729.6  215.46  6887.7  219.72  7201.2  221.23  7671.8  230.78
#Mann= 7 ,-1 , 0
  3186.7     .17       0  3567.3     .15       0  3678.8     .11       0
  3767.9     .15       0    4952     .09       0  5019.8     .15       0
  6729.6     .11       0
Bank Sta=4952,5019.8
XS Rating Curve= 0 ,0
Exp/Cntr=0.3,0.1

Type RM Length L Ch R = 1 ,199180  ,1249,1249,1249
BEGIN DESCRIPTION:
LAKE CREEK 190.0
END DESCRIPTION:
XS GIS Cut Line= 3
      3737467.88     10138361.07      3735690.64     10138384.24
      3733183.68     10139030.08
#Sta/Elev= 30
  3210.3  242.81  3421.2  230.23  3580.4  220.54  3780.4  214.53  4655.2  209.74
  4970.5  210.76  4980.5  209.43  4986.4  203.21  5015.4  203.21  5042.2  210.26
  5834.5  208.15  5956.6  210.81  6054.2  206.19  6085.2   210.4  6136.8  211.19
  6178.1  206.98  6241.4   210.7  6611.8  209.79  6632.5  215.49  6678.9   204.8
  6719.5  205.97  6735.7  213.69  6746.1   214.7  6777.1  213.29  6795.7  208.88
  6836.4  208.61    6901  214.69  7148.8  216.56  7427.6  228.95  7576.5  229.81
#Mann= 6 ,-1 , 0
  3210.3     .17       0  3421.2     .11       0  4655.2     .15       0
  4970.5     .09       0  5042.2     .15       0  6678.9     .11       0
Bank Sta=4970.5,5042.2
XS Rating Curve= 0 ,0
Exp/Cntr=0.3,0.1

Type RM Length L Ch R = 1 ,197931  ,931,931,931
BEGIN DESCRIPTION:
LAKE CREEK 189.0
END DESCRIPTION:
XS GIS Cut Line= 3
      3738067.88     10137561.07      3734857.31     10138113.41
      3732933.65     10138141.19
#Sta/Elev= 30
  2025.8  252.09  2329.9  241.43  2489.4  234.79  2551.9  231.73  2674.5  227.16
  2746.3  227.37  2767.4  232.14  2817.1   226.1  3436.3  209.52  4565.4  209.98
  4969.4209.0821  4974.2  203.06  5003.2  203.06  5004.1  205.18  5009.2  206.59
  5039.5  209.12  5100.3  206.82  5161.2   210.1    5373  209.36    5433  207.41
    5523  209.21  5852.7  209.21  6183.6  208.44  6543.1  208.04  6703.2  209.64
  6813.2  215.12  6923.2  223.12  6953.2  229.26  6983.2  225.51  7207.4  237.77
#Mann= 11 ,-1 , 0
  2025.8     .11       0  2329.9     .15       0  2489.4     .11       0
  2551.9     .15       0  2674.5     .11       0  4565.4     .15       0
  4969.4     .09       0  5039.5     .15       0  5852.7     .11       0
  6183.6     .15       0  6703.2     .11       0
Bank Sta=4969.4,5039.5
XS Rating Curve= 0 ,0
Exp/Cntr=0.3,0.1

Type RM Length L Ch R = 1 ,197000  ,1625,1625,1625
BEGIN DESCRIPTION:
LAKE CREEK 188.0
END DESCRIPTION:
XS GIS Cut Line= 3
      3738967.83     10137561.07      3734997.56     10137361.28
       3733017.9     10138061.06
#Sta/Elev= 30
  1024.7  282.69    2321  240.85  2366.4  234.42    2460  234.88  2657.2  226.58
  2755.9  222.95  3110.9  213.77  3484.2  209.16  4618.5  209.15  4959.7  208.88
  4969.7  207.84  4975.2  200.79  5004.2  200.79  5009.7  206.82    5015  205.03
  5020.9  208.72  5137.5  209.98    6299  207.69  6388.7  207.47  6549.2  208.52
  6585.2  208.96  6816.7   219.1  6898.2  225.24  6904.1  228.38  6919.4  230.19
    6935  228.11  6940.7  224.88  6972.5  225.53  6991.6  230.92  7099.7     235
#Mann= 15 ,-1 , 0
  1024.7     .11       0    2321     .15       0    2460     .11       0
  2657.2     .15       0  2755.9     .11       0  3110.9     .15       0
  3484.2     .11       0  4618.5     .15       0  4959.7     .09       0
  5020.9     .15       0  5137.5     .11       0    6299     .15       0
  6388.7     .11       0  6549.2     .15       0  6585.2     .11       0
Bank Sta=4959.7,5020.9
XS Rating Curve= 0 ,0
Exp/Cntr=0.3,0.1

Type RM Length L Ch R = 1 ,195375  ,1587,1587,1587
BEGIN DESCRIPTION:
LAKE CREEK 187.0
END DESCRIPTION:
XS GIS Cut Line= 4
      3738467.87     10137261.07      3735051.75     10136696.74
      3734885.08     10136787.02       3732467.8     10136961.08
#Sta/Elev= 30
  1261.2  271.42  1453.8  267.06  1777.9  254.04    2516  219.04  2909.4  211.46
  3240.2  208.47  3619.4   208.3  4509.3  208.62  4597.9  208.74  4891.6  209.81
  4970.5  207.19  4976.1  201.83  5005.1  201.83  5010.2  207.43  5020.7  209.15
  6073.4  207.03  6305.2  211.35  6344.1  204.87  6454.4   204.7  6474.4  208.68
  6554.6  207.24  6587.6  216.31  6604.8  224.59  6614.8   225.2  6644.9   212.5
  6654.9  210.28    6685  209.78  6984.6  231.39  7182.9  241.85  7336.7  255.46
#Mann= 11 ,-1 , 0
  1261.2     .11       0  2909.4     .15       0  3240.2     .11       0
  3619.4     .15       0  4509.3     .11       0  4597.9     .15       0
  4970.5     .09       0  5010.2     .11       0  6305.2     .15       0
  6587.6     .11       0  7182.9     .17       0
Bank Sta=4970.5,5010.2
XS Rating Curve= 0 ,0
Exp/Cntr=0.3,0.1

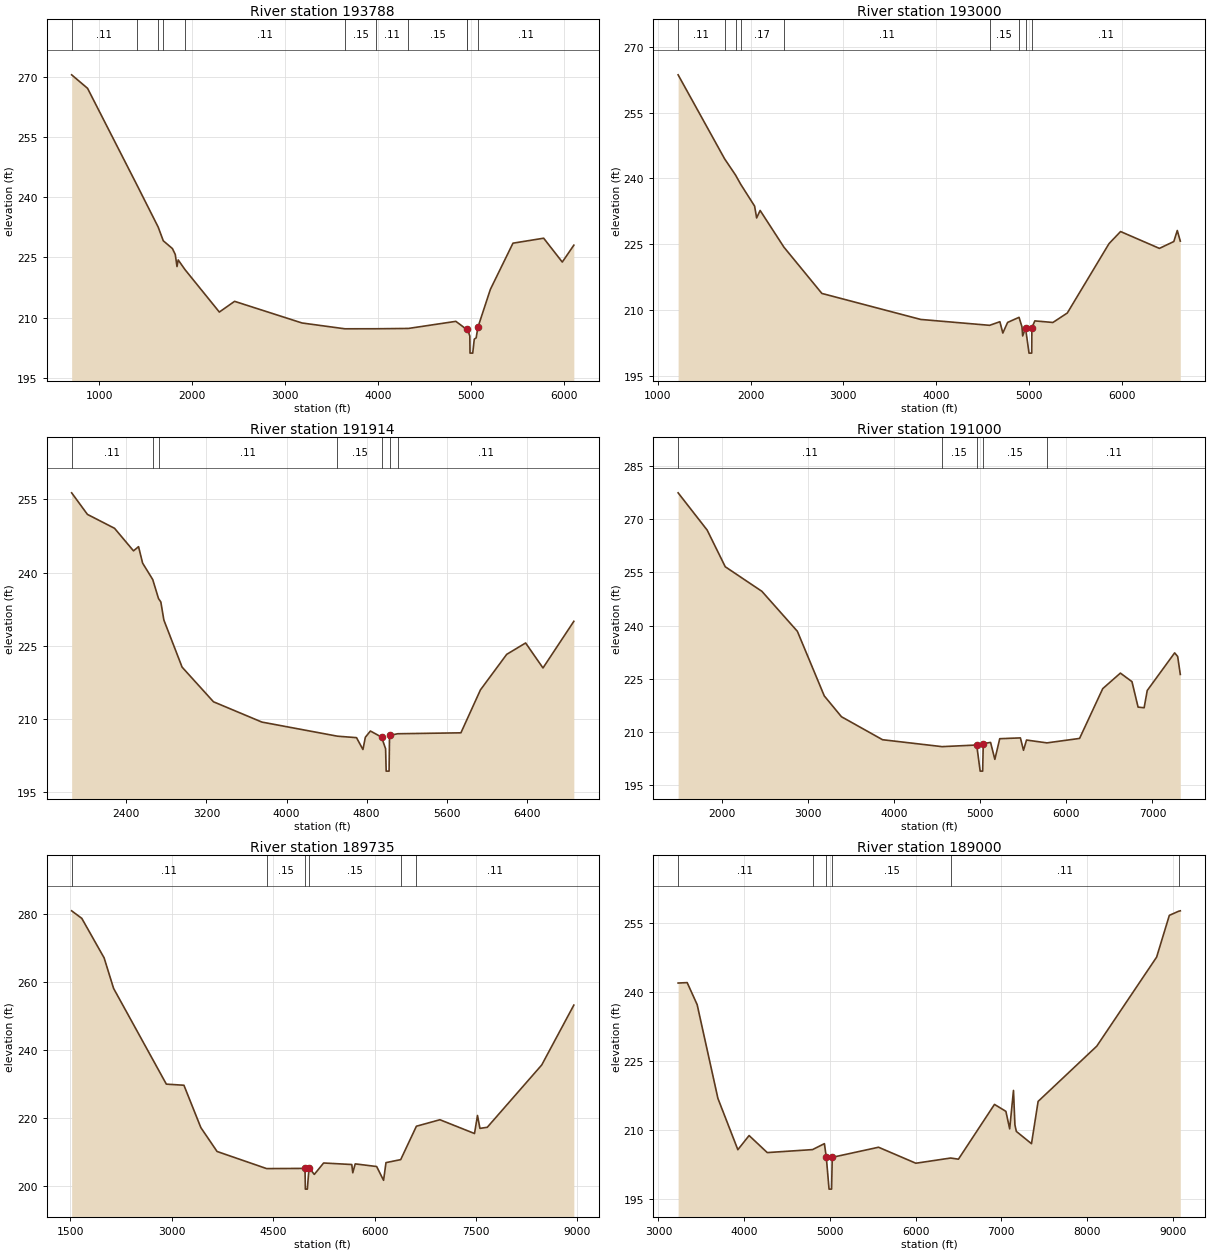
Type RM Length L Ch R = 1 ,193788  ,788,788,788
BEGIN DESCRIPTION:
LAKE CREEK 186.0
END DESCRIPTION:
XS GIS Cut Line= 3
       3738417.9     10137161.09      3734343.42     10135745.35
      3733275.71     10135946.41
#Sta/Elev= 30
   702.1  270.55   873.3  267.18  1405.7     243  1633.1  232.54  1687.3  229.15
  1785.5  227.21  1816.6  225.71  1834.9  222.71  1847.7  224.37  1921.1  221.95
  2290.1  211.37  2454.1  214.04  3179.4  208.64  3639.9  207.19  3976.1   207.2
    4324  207.28  4833.3  209.05  4956.1  206.92  4957.9  207.18  4983.6  205.38
  4985.7  201.12  5014.7  201.12  5031.4  204.61  5051.7  204.92  5070.2  207.54
  5204.4  217.02  5447.6  228.55  5777.6  229.79  5977.7  223.84    6102  228.05
#Mann= 11 ,-1 , 0
   702.1     .11       0  1405.7     .17       0  1633.1     .11       0
  1687.3     .17       0  1921.1     .11       0  3639.9     .15       0
  3976.1     .11       0    4324     .15       0  4956.1     .11       0
  4957.9     .06       0  5070.2     .11       0
Bank Sta=4957.9,5070.2
XS Rating Curve= 0 ,0
Exp/Cntr=0.3,0.1

Type RM Length L Ch R = 1 ,193000  ,1086,1086,1086
BEGIN DESCRIPTION:
LAKE CREEK 185.0
END DESCRIPTION:
XS GIS Cut Line= 4
      3738218.39     10136912.01      3735273.97     10135571.74
      3734788.21     10135320.93      3733247.15     10135859.32
#Sta/Elev= 30
  1218.2  263.63  1719.7  244.47  1837.9  240.76  1893.3  238.67  2042.8   233.7
  2064.8     231  2102.4  232.71    2359  224.34    2768  213.79  3833.8  207.86
  4576.3  206.52  4687.3  207.34    4719  204.76  4770.3  207.18  4893.8  208.34
  4925.3  206.18  4932.9  204.09    4964  205.89  5001.4  200.18  5030.4  200.18
  5032.2  205.96  5063.9  207.53    5259  207.17  5414.3  209.33  5864.1  225.15
  5988.3   227.9  6407.1  224.06  6562.4  225.62  6599.9  228.14  6632.4  225.72
#Mann= 9 ,-1 , 0
  1218.2     .11       0  1719.7     .17       0  1837.9     .11       0
  1893.3     .17       0    2359     .11       0  4576.3     .15       0
  4893.8     .11       0    4964     .06       0  5032.2     .11       0
Bank Sta=4964,5032.2
XS Rating Curve= 0 ,0
Exp/Cntr=0.3,0.1

Type RM Length L Ch R = 1 ,191914  ,914,914,914
BEGIN DESCRIPTION:
LAKE CREEK 184.0
END DESCRIPTION:
XS GIS Cut Line= 3
      3738058.74     10134092.57      3734739.25     10134592.57
      3733329.55     10135467.56
#Sta/Elev= 30
  1853.8  256.34  2011.5  251.92  2282.3  249.07  2471.6  244.45  2522.1  245.31
  2562.6  241.94  2663.7  238.57  2721.5  234.67  2744.6  233.98    2775  230.27
    2957  220.62  3270.5  213.52    3754  209.36  4508.5  206.47  4699.3  206.17
  4763.2  203.74  4787.4  206.25    4838  207.53  4949.2  206.28  4989.7  203.89
  4995.4  199.31  5024.4  199.31  5028.9  206.62  5110.9  206.97    5742  207.16
  5937.1  215.96  6199.3  223.24  6388.2  225.57  6561.8  220.45  6869.9  230.01
#Mann= 7 ,-1 , 0
  1853.8     .11       0  2663.7     .17       0  2721.5     .11       0
  4508.5     .15       0  4949.2     .09       0  5028.9     .15       0
  5110.9     .11       0
Bank Sta=4949.2,5028.9
XS Rating Curve= 0 ,0
Exp/Cntr=0.3,0.1

Type RM Length L Ch R = 1 ,191000  ,1265,1265,1265
BEGIN DESCRIPTION:
LAKE CREEK 183.0
END DESCRIPTION:
XS GIS Cut Line= 3
      3738367.82     10132961.08        3734997.      10133952.9
      3733251.42      10135487.6
#Sta/Elev= 30
  1486.3  277.47  1823.9  266.96  2034.4  256.61  2460.7  249.67  2872.6   238.4
  3185.4  220.17  3385.1  214.29  3862.9   207.8  4554.1  205.85  4957.4  206.31
  4997.7  198.94  5026.7  198.94  5033.6  206.69  5118.7  207.04  5168.4  202.26
  5225.2  208.09  5465.4  208.32  5501.4  204.82  5536.5  207.71    5774  206.91
  6153.2  208.17  6422.7  222.22  6627.7   226.6  6762.4  224.19  6833.5     217
  6903.8  216.82  6939.8  221.69  7258.6  232.31  7293.7  231.29  7324.3  226.23
#Mann= 5 ,-1 , 0
  1486.3     .11       0  4554.1     .15       0  4957.4     .09       0
  5033.6     .15       0    5774     .11       0
Bank Sta=4957.4,5033.6
XS Rating Curve= 0 ,0
Exp/Cntr=0.3,0.1

Type RM Length L Ch R = 1 ,189735  ,735,735,735
BEGIN DESCRIPTION:
LAKE CREEK 182.0
END DESCRIPTION:
XS GIS Cut Line= 3
      3738517.87     10132911.07      3735023.97     10133016.19
      3731767.87     10130811.08
#Sta/Elev= 30
  1518.8  281.02  1668.9   278.8    1999  267.18  2139.1   258.2  2919.5  230.02
  3179.6   229.7  3429.7  217.24  3669.8  210.21  4402.9  205.17  4970.4  205.23
  4975.8  199.13    5005  199.13    5030  205.43    5108  203.46  5245.7  206.82
  5662.2  206.37  5677.1  203.94  5713.1  206.56  6030.6  205.78  6132.4  201.72
  6168.3  206.93  6385.9  207.81  6618.1  217.64  6966.1  219.55  7477.5  215.49
  7521.7   220.8  7557.9  217.01  7666.1  217.32    8472  235.67  8946.8  253.28
#Mann= 6 ,-1 , 0
  1518.8     .11       0  4402.9     .15       0  4970.4     .09       0
    5030     .15       0  6385.9     .17       0  6618.1     .11       0
Bank Sta=4970.4,5030
XS Rating Curve= 0 ,0
Exp/Cntr=0.3,0.1

Type RM Length L Ch R = 1 ,189000  ,1000,1000,1000
BEGIN DESCRIPTION:
LAKE CREEK 181.0
END DESCRIPTION:
XS GIS Cut Line= 3
      3737067.85     10132711.07      3735315.47     10132459.86
      3731617.86     10130711.08
#Sta/Elev= 30
  3229.7  241.98  3335.6  242.07    3452  237.29  3694.4  216.93  3926.8  205.81
  4058.1  208.88  4270.2  205.18  4798.8  205.83    4937  207.12  4959.2  204.14
  4991.2  197.25  5020.5  197.25  5028.6  204.15  5568.6  206.34    6004  202.87
  6410.6     204    6501  203.75  6921.7  215.64  7054.9  214.13  7099.1  210.33
  7143.4  218.67  7160.3  211.21  7176.6  209.78  7353.6  207.11    7431  216.29
  8115.5  228.28  8813.8   247.6  8962.4  256.67  9072.3  257.57  9090.3  257.65
#Mann= 6 ,-1 , 0
  3229.7     .11       0  4798.8     .15       0  4959.2     .09       0
  5028.6     .15       0  6410.6     .11       0  9072.3     .17       0
Bank Sta=4959.2,5028.6
XS Rating Curve= 0 ,0
Exp/Cntr=0.3,0.1

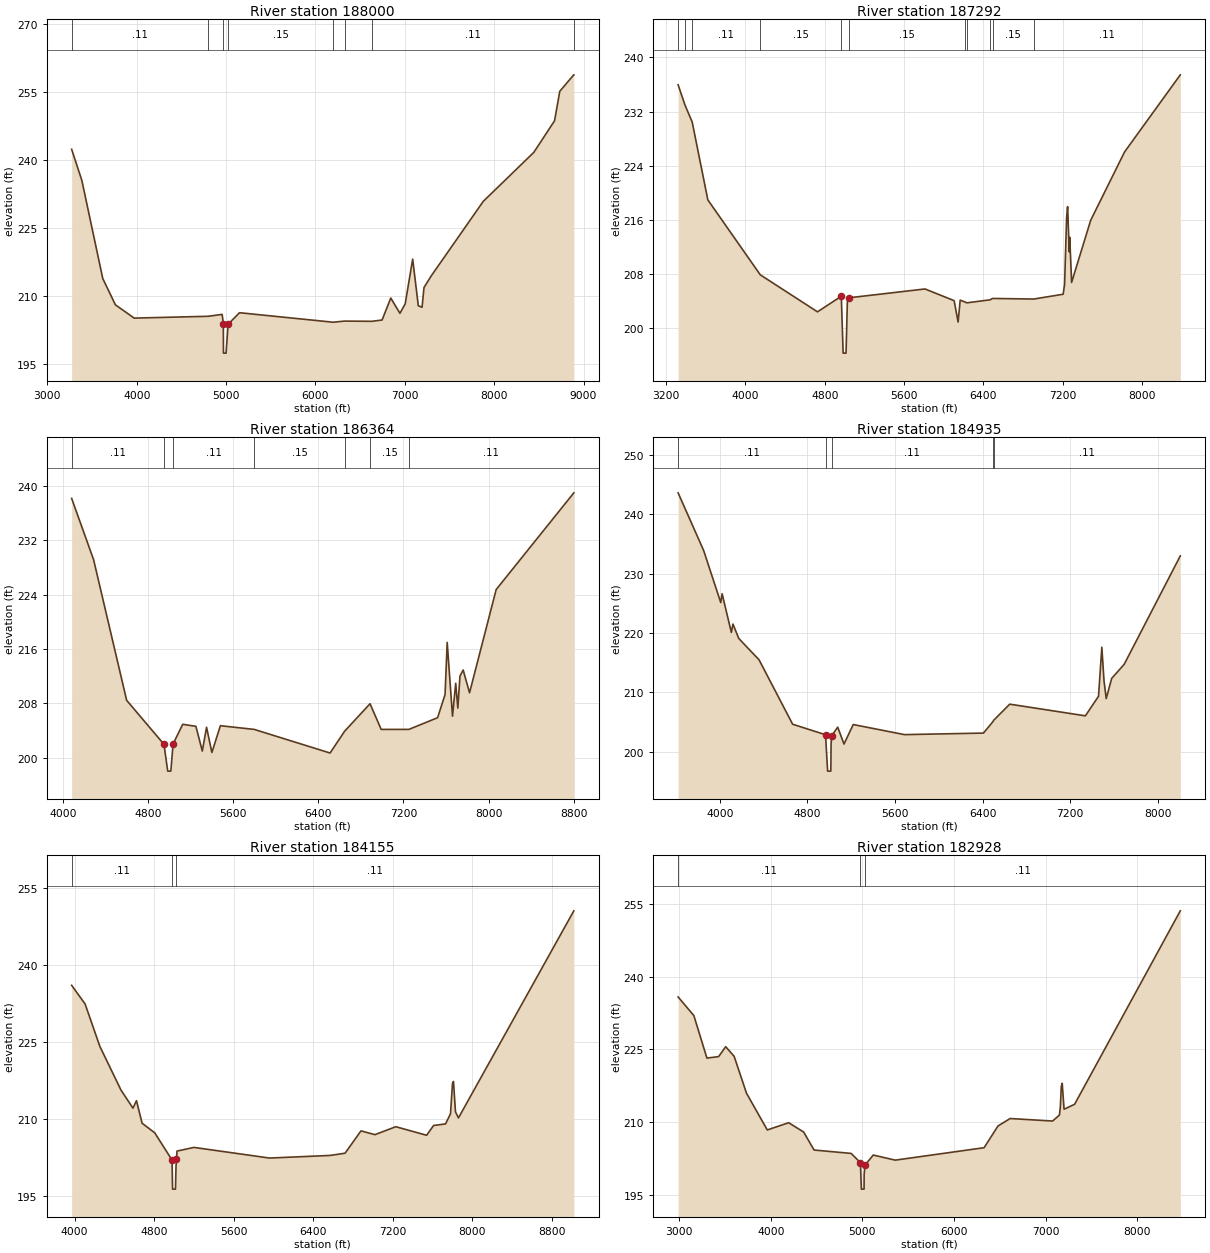
Type RM Length L Ch R = 1 ,188000  ,708,708,708
BEGIN DESCRIPTION:
LAKE CREEK 180.0
END DESCRIPTION:
XS GIS Cut Line= 3
      3736967.84     10132561.06      3735379.55     10131880.12
      3731667.81     10130711.06
#Sta/Elev= 30
  3271.9  242.35  3386.1  235.48  3620.1   213.8  3761.4  207.99  3971.7  205.05
  4798.2  205.45  4956.2  205.87  4969.2  203.82  4970.6  197.31  4999.9  197.31
  5022.8  203.69  5150.2  206.24    6198  204.14  6325.6  204.39  6632.2  204.34
  6745.9  204.63    6843  209.48  6945.4  206.12  7004.3  208.19  7088.2  218.09
  7151.1  207.78    7193  207.45  7214.8   211.8  7297.8  214.44    7878  230.85
    8444  241.68  8675.8  248.66  8734.2  255.17  8890.5  258.81  8891.5   258.8
#Mann= 8 ,-1 , 0
  3271.9     .11       0  4798.2     .15       0  4969.2     .09       0
  5022.8     .15       0    6198     .11       0  6325.6     .15       0
  6632.2     .11       0  8890.5     .17       0
Bank Sta=4969.2,5022.8
XS Rating Curve= 0 ,0
Exp/Cntr=0.3,0.1

Type RM Length L Ch R = 1 ,187292  ,928,928,928
BEGIN DESCRIPTION:
LAKE CREEK 179.0
END DESCRIPTION:
XS GIS Cut Line= 3
      3737225.34     10131877.29      3735510.08     10131363.41
       3732275.3     10130835.85
#Sta/Elev= 30
  3320.5  235.95  3389.1  232.98  3462.5  230.45  3620.6  218.94  4149.8  207.87
  4727.2   202.4  4967.5  204.71  4985.9   196.3  5015.2   196.3  5028.4  203.84
  5040.3  204.47  5812.5  205.78  6106.3  204.05  6146.2  200.89  6167.1  204.13
  6212.9  203.87  6234.7  203.73  6470.1  204.18  6493.4  204.38  6908.3  204.29
  7206.2     205  7220.8  206.45  7241.1  216.33  7251.2  217.94  7267.7  211.27
  7272.7  213.41  7291.7  206.75  7484.3  215.93  7825.9  226.02  8388.6  237.42
#Mann= 11 ,-1 , 0
  3320.5     .11       0  3389.1     .17       0  3462.5     .11       0
  4149.8     .15       0  4967.5     .09       0  5040.3     .15       0
  6212.9     .11       0  6234.7     .15       0  6470.1     .11       0
  6493.4     .15       0  6908.3     .11       0
Bank Sta=4967.5,5040.3
XS Rating Curve= 0 ,0
Exp/Cntr=0.3,0.1

Type RM Length L Ch R = 1 ,186364  ,1429,1429,1429
BEGIN DESCRIPTION:
LAKE CREEK 178.0
END DESCRIPTION:
XS GIS Cut Line= 3
      3736933.67     10131085.63      3736176.75     10131023.13
      3732218.38     10130787.02
#Sta/Elev= 30
    4078  238.12  4284.5  229.12  4595.6  208.46  4946.6     202    4982  198.06
  5011.3  198.06  5032.3202.0414    5123  204.94  5247.1  204.64  5307.2  201.01
  5347.3   204.5  5397.4   200.8  5477.5  204.73  5795.4  204.19  6509.4  200.72
  6646.1  203.92  6885.4  207.96  6990.2  204.19  7251.1  204.19  7521.2  205.91
  7591.3  209.31  7611.3  216.97  7661.4  206.13  7691.5  210.97  7711.5  207.32
  7731.5  212.01  7761.6  212.92  7821.7  209.57  8072.1  224.73  8802.9  238.94
#Mann= 7 ,-1 , 0
    4078     .11       0  4946.6     .06       0  5032.3     .11       0
  5795.4     .15       0  6646.1     .11       0  6885.4     .15       0
  7251.1     .11       0
Bank Sta=4946.6,5032.3
XS Rating Curve= 0 ,0
Exp/Cntr=0.3,0.1

Type RM Length L Ch R = 1 ,184935  ,780,780,780
BEGIN DESCRIPTION:
LAKE CREEK 177.0
END DESCRIPTION:
XS GIS Cut Line= 3
      3737117.86     10131061.08      3735551.75     10130293.96
      3732712.18     10130113.45
#Sta/Elev= 30
  3618.4  243.65  3851.9  233.91  4008.1  225.13  4020.5  226.62    4105  220.09
  4119.5  221.51  4172.5  219.08  4358.1  215.47  4665.1   204.6  4965.6  202.83
  4984.6  196.69  5013.9  196.69  5016.2  201.28  5021.8  202.66  5077.1  204.11
  5134.3  201.26  5218.7  204.55  5686.8  202.85  6408.3  203.11  6495.6  205.04
  6501.8  205.26  6648.8  207.99  7340.2  206.02  7460.4  209.33  7490.5   217.6
  7510.5  211.91  7530.6  208.93  7580.7  212.34  7694.7  214.71  8207.6  233.01
#Mann= 5 ,-1 , 0
  3618.4     .11       0  4965.6     .06       0  5021.8     .11       0
  6495.6     .15       0  6501.8     .11       0
Bank Sta=4965.6,5021.8
XS Rating Curve= 0 ,0
Exp/Cntr=0.3,0.1

Type RM Length L Ch R = 1 ,184155  ,1227,1227,1227
BEGIN DESCRIPTION:
LAKE CREEK 176.0
END DESCRIPTION:
XS GIS Cut Line= 3
      3737023.99     10130606.48      3736378.14     10129995.35
      3732217.82     10130061.07
#Sta/Elev= 30
  3970.8  236.08  4106.2  232.43  4254.7  224.14    4467  215.62  4587.2  212.09
  4622.8  213.54  4679.4  209.14  4806.4  207.27  4980.3  201.95  4985.6  196.27
  5014.9  196.27  5020.3  200.66    5025202.0889  5030.3   203.7  5200.3  204.42
  5960.4  202.34  6570.5  202.85  6720.5  203.29  6880.5  207.65  7020.5  206.91
  7230.5  208.46  7540.6  206.79  7610.6   208.7  7730.6  209.01  7780.6  210.99
  7800.6  216.94  7810.6   217.3  7830.6  211.36  7860.6  210.18  9020.8  250.63
#Mann= 3 , 0 , 0
  3970.8     .11       0  4980.3     .06       0    5025     .11       0
Bank Sta=4980.3,5025
XS Rating Curve= 0 ,0
Exp/Cntr=0.3,0.1

Type RM Length L Ch R = 1 ,182928  ,726,726,726
BEGIN DESCRIPTION:
LAKE CREEK 175.0
END DESCRIPTION:
XS GIS Cut Line= 3
       3737204.5     10130377.27      3736030.92     10129349.52
      3732167.84     10130011.07
#Sta/Elev= 30
  2989.8  235.85  3161.7     232    3304  223.22  3431.2  223.52    3509  225.57
  3601.1  223.59  3735.9  215.96  3962.7  208.37  4196.2  209.86  4359.4  207.94
  4473.3  204.22  4877.6  203.52    4979  201.61  4989.1  196.14  5018.6  196.14
  5019.6  199.22  5029.7  201.12  5118.9  203.18  5359.1  202.13  6328.4   204.7
    6480  209.19  6612.5  210.73  7075.5  210.21  7150.2  211.44  7160.3  213.12
  7170.5  217.34  7180.6     218  7200.9  212.65  7315.7  213.67  8469.1  253.65
#Mann= 3 , 0 , 0
  2989.8     .11       0    4979     .06       0  5029.7     .11       0
Bank Sta=4979,5029.7
XS Rating Curve= 0 ,0
Exp/Cntr=0.3,0.1

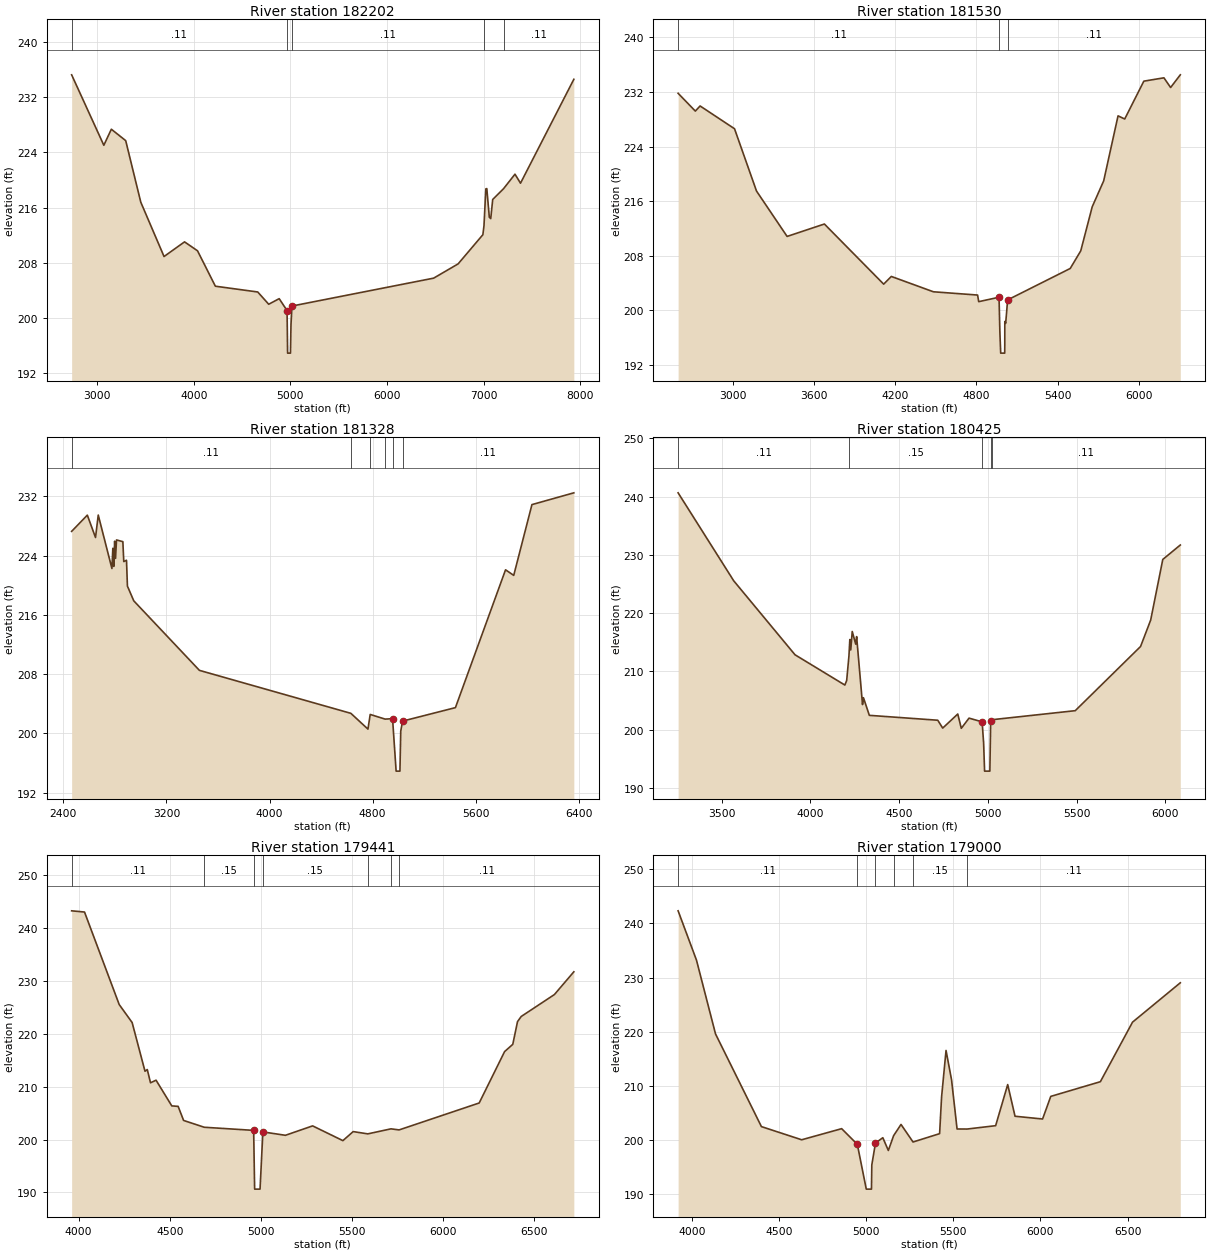
Type RM Length L Ch R = 1 ,182202  ,672,672,672
BEGIN DESCRIPTION:
LAKE CREEK 174.0
END DESCRIPTION:
XS GIS Cut Line= 3
      3737197.56     10130321.72       3735683.7      10128939.8
      3732593.42     10129530.07
#Sta/Elev= 30
  2737.1  235.27  3070.1  225.04  3147.8  227.37  3296.5  225.71  3452.5  216.77
    3693  208.88  3905.2  211.01  4039.6  209.71    4224  204.57  4662.5  203.73
    4776  201.95  4884.4  202.76  4965.9  201.03  4971.5  194.85    5001  194.85
  5006.6  199.02  5016.8  201.69  6482.8  205.74  6735.7  207.81  6991.9  212.05
  7003.3  213.35  7022.4   218.7  7032.6  218.75  7058.5  214.59  7073.3  214.39
  7093.7  217.17  7205.7  218.73  7324.1  220.84  7381.2  219.53    7933  234.62
#Mann= 5 ,-1 , 0
  2737.1     .11       0  4965.9     .06       0  5016.8     .11       0
  7003.3     .17       0  7205.7     .11       0
Bank Sta=4965.9,5016.8
XS Rating Curve= 0 ,0
Exp/Cntr=0.3,0.1

Type RM Length L Ch R = 1 ,181530  ,202,202,202
BEGIN DESCRIPTION:
Mapping XS e8a99cb2
END DESCRIPTION:
XS GIS Cut Line= 5
      3737150.56     10130158.39      3735737.78     10128741.27
      3735494.72     10128413.58      3735160.52     10128157.51
      3734529.87     10127537.71
#Sta/Elev= 30
  2593.5  231.81  2720.8   229.2  2756.2  229.95  3010.7  226.61  3173.3  217.47
  3399.6  210.81  3675.4  212.63  4113.8  203.81  4170.4  204.94  4481.5  202.69
  4808.5  202.21  4816.9  201.24  4967.1  201.89  4973.3  196.78  4979.4  193.69
    5009  193.69  5009.5  194.79  5009.9  198.33  5016.2  198.06  5030.7   201.5
  5493.7  206.11  5571.4  208.69  5656.3  215.16  5741.1  218.96  5847.3   228.5
  5896.7  228.04  6038.1  233.59  6186.6  234.08  6236.2  232.66  6307.8  234.52
#Mann= 3 , 0 , 0
  2593.5     .11       0  4967.1     .06       0  5030.7     .11       0
Bank Sta=4967.1,5030.7
XS Rating Curve= 0 ,0
Exp/Cntr=0.3,0.1

Type RM Length L Ch R = 1 ,181328  ,903,903,903
BEGIN DESCRIPTION:
Mapping XS f636fac7
END DESCRIPTION:
XS GIS Cut Line= 2
      3737358.85     10130002.11      3734572.62     10127276.63
#Sta/Elev= 30
  2464.1  227.27  2585.8  229.46  2649.3  226.44  2670.6  229.47  2776.6  222.26
  2783.8  224.99  2790.8  222.54  2797.9  225.94  2804.9  223.62  2812.1  226.11
  2861.5  225.88  2868.7  223.19  2889.8  223.37    2897  219.88  2946.4  217.89
  3455.6  208.51  4631.2  202.71  4763.7  200.58  4781.3  202.56  4897.3  201.93
  4954.8  201.99  4982.4  194.91    5012  194.91  5018.3  200.31  5032.5  201.66
  5442.7  203.48  5831.6  222.08  5895.2  221.33  6036.6  230.88  6361.7  232.47
#Mann= 6 ,-1 , 0
  2464.1     .11       0  4631.2     .15       0  4781.3     .11       0
  4897.3     .15       0  4954.8     .06       0  5032.5     .11       0
Bank Sta=4954.8,5032.5
XS Rating Curve= 0 ,0
Exp/Cntr=0.3,0.1

Type RM Length L Ch R = 1 ,180425  ,984,984,984
BEGIN DESCRIPTION:
LAKE CREEK 173.0
END DESCRIPTION:
XS GIS Cut Line= 3
      3737528.17     10127973.05      3735889.68     10127484.76
      3734782.91     10127311.15
#Sta/Elev= 30
  3254.8  240.66  3568.2  225.55  3913.6  212.85  4194.5  207.65  4204.7  208.43
  4217.4  212.63  4222.5  215.47  4227.7  213.68    4236  216.85  4255.6  214.67
  4260.8  215.97    4294   204.3  4299.2  205.48  4332.4  202.45    4718  201.61
  4745.9  200.26  4830.8  202.68  4850.6  200.22  4894.2  201.97    4968  201.33
  4976.5  197.66  4981.9  192.87  5011.6  192.87  5016.2  201.49  5020.9  201.69
  5492.7  203.25  5860.8  214.27  5917.8   218.8  5986.1  229.22  6084.8   231.7
#Mann= 5 ,-1 , 0
  3254.8     .11       0  4217.4     .15       0    4968     .06       0
  5016.2     .15       0  5020.9     .11       0
Bank Sta=4968,5016.2
XS Rating Curve= 0 ,0
Exp/Cntr=0.3,0.1

Type RM Length L Ch R = 1 ,179441  ,441,441,441
BEGIN DESCRIPTION:
LAKE CREEK 172.0
END DESCRIPTION:
XS GIS Cut Line= 3
      3737376.22     10127115.84      3736117.55     10126931.38
      3734652.79     10127170.08
#Sta/Elev= 30
  3961.7  243.26  4032.4  243.03  4222.8  225.53  4293.6  222.14  4364.3  212.92
  4376.7  213.25  4394.6  210.74    4425  211.23  4511.3  206.37  4546.2  206.28
  4576.1  203.62  4689.6  202.33  4960.6  201.74    4966  190.63  4995.7  190.63
  5011.2  201.45    5135  200.81  5284.2  202.59  5450.4   199.8  5506.8  201.51
  5587.1  201.08  5714.4  202.03    5759  201.83  6198.4  206.92  6337.9  216.64
  6382.8  218.01  6408.8  222.31  6429.1  223.28  6611.4  227.43  6717.9  231.73
#Mann= 7 ,-1 , 0
  3961.7     .11       0  4689.6     .15       0  4960.6     .06       0
  5011.2     .15       0  5587.1     .11       0  5714.4     .15       0
    5759     .11       0
Bank Sta=4960.6,5011.2
XS Rating Curve= 0 ,0
Exp/Cntr=0.3,0.1

Type RM Length L Ch R = 1 ,179000  ,514,514,514
BEGIN DESCRIPTION:
LAKE CREEK 171.0
END DESCRIPTION:
XS GIS Cut Line= 3
      3737376.27     10126801.18      3736328.23     10126541.61
      3734617.84     10127111.07
#Sta/Elev= 30
  3920.3   242.3  4025.8   233.2    4135   219.6  4398.4  202.51  4629.5  200.08
    4859  202.13  4948.9  199.24  5000.3  190.98    5030  190.98    5032  195.43
  5053.1  199.48  5095.3  200.46  5126.9  198.11  5157.4  200.85  5199.7  202.91
  5268.7  199.67  5421.2  201.21  5432.5  207.97  5458.1  216.55  5489.7  211.15
  5521.4  202.07  5578.8  202.06  5742.8  202.68    5812  210.26  5854.1  204.42
  6012.2  203.91  6059.2  208.08  6343.9  210.79  6528.5  221.77  6802.7  229.03
#Mann= 6 ,-1 , 0
  3920.3     .11       0  4948.9     .06       0  5053.1     .15       0
  5157.4     .11       0  5268.7     .15       0  5578.8     .11       0
Bank Sta=4948.9,5053.1
XS Rating Curve= 0 ,0
Exp/Cntr=0.3,0.1

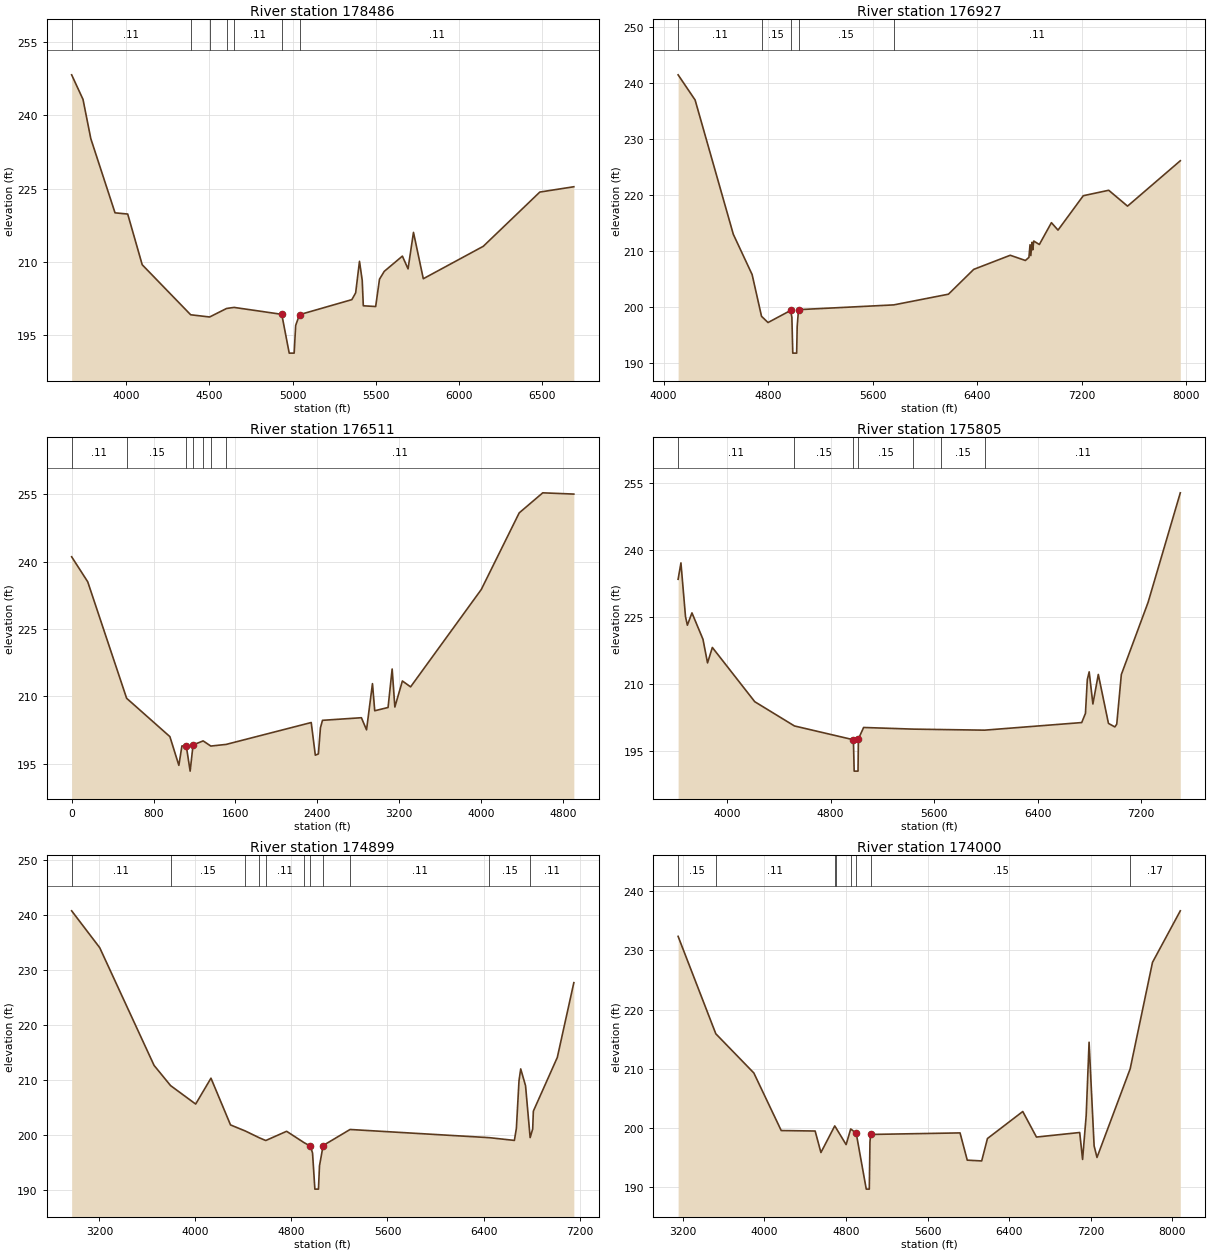
Type RM Length L Ch R = 1 ,178486  ,1559,1559,1559
BEGIN DESCRIPTION:
LAKE CREEK 170.0
END DESCRIPTION:
XS GIS Cut Line= 3
      3737517.25     10126562.44      3736291.16     10126030.77
      3734762.02     10126735.69
#Sta/Elev= 30
  3671.3  248.27  3739.5  243.25  3786.5  235.21  3932.2  220.02  4008.5  219.77
  4095.7  209.39  4387.2  199.15  4501.2   198.7    4603  200.44    4648  200.66
    4935  199.24  4979.8   191.3  5009.5   191.3  5018.6  196.97  5041.6  199.17
  5356.5  202.25  5379.4  203.64  5402.4   210.1  5418.8   206.2  5425.4  200.99
  5499.7  200.84  5522.7  206.43  5551.1  208.03  5660.4  211.16  5694.4  208.55
  5727.1  216.02  5786.2  206.53    6147  213.17  6486.9  224.27  6691.5  225.36
#Mann= 7 ,-1 , 0
  3671.3     .11       0  4387.2     .15       0  4501.2     .11       0
    4603     .15       0    4648     .11       0    4935     .06       0
  5041.6     .11       0
Bank Sta=4935,5041.6
XS Rating Curve= 0 ,0
Exp/Cntr=0.3,0.1

Type RM Length L Ch R = 1 ,176927  ,416,416,416
BEGIN DESCRIPTION:
LAKE CREEK 169.0
END DESCRIPTION:
XS GIS Cut Line= 3
      3737755.98     10125379.72      3735900.54     10125054.21
      3734772.48     10126659.51
#Sta/Elev= 30
  4110.8  241.38  4240.9  236.89  4533.6  212.91  4677.5  205.73  4749.6  198.27
  4799.3  197.16  4971.9  199.31    4982  198.11  4988.9   191.7  5018.6   191.7
  5022.6  196.47  5032.8  199.46  5762.2  200.31    6181  202.22  6374.5  206.65
  6654.2  209.17    6770  208.24  6797.4  208.79  6805.8  211.05  6811.9  209.11
  6820.6  211.48  6826.7  210.14  6834.1  211.71  6877.2  211.09  6969.6  214.99
  7020.1  213.66  7213.6   219.8  7408.5  220.77  7552.5  217.94  7956.6  226.04
#Mann= 5 ,-1 , 0
  4110.8     .11       0  4749.6     .15       0  4971.9     .06       0
  5032.8     .15       0  5762.2     .11       0
Bank Sta=4971.9,5032.8
XS Rating Curve= 0 ,0
Exp/Cntr=0.3,0.1

Type RM Length L Ch R = 1 ,176511  ,706,706,706
BEGIN DESCRIPTION:
LAKE CREEK 168.5
END DESCRIPTION:
XS GIS Cut Line= 3
      3737823.59     10125398.15      3736712.48     10124752.32
      3733094.43     10124585.65
#Sta/Elev= 30
       0  241.05     157  235.49   537.2  209.55   960.1  201.01  1047.6  194.62
  1077.6  198.95  1120.7  198.85  1157.9  193.33  1186.4  199.16    1285  200.06
  1359.9  198.91    1510  199.28  2340.9  204.15    2381  196.88    2411  197.16
    2431  202.97    2451  204.64  2831.4  205.22  2881.5  202.52  2939.4  212.81
  2961.6  206.77  3091.7   207.5  3131.8  216.07  3158.1   207.6  3231.9   213.4
    3312  212.09  4002.7  233.77  4373.1  250.82  4603.3  255.29  4907.1  255.01
#Mann= 7 ,-1 , 0
       0     .11       0   537.2     .15       0  1120.7     .06       0
  1186.4     .15       0    1285     .11       0  1359.9     .15       0
    1510     .11       0
Bank Sta=1120.7,1186.4
XS Rating Curve= 0 ,0
Exp/Cntr=0.3,0.1

Type RM Length L Ch R = 1 ,175805  ,906,906,906
BEGIN DESCRIPTION:
LAKE CREEK 168.0
END DESCRIPTION:
XS GIS Cut Line= 3
      3737867.87     10125261.09      3737018.16      10124153.6
      3735067.84     10122611.06
#Sta/Elev= 30
  3620.9  233.43  3642.7   237.1    3678  225.07  3692.5  223.15  3727.9  225.91
  3813.1     220  3848.4  214.71  3885.6  218.17  4213.3  206.03  4520.3   200.6
  4976.1  197.51    4982  190.49  5011.8  190.49 5014.52197.6909  5055.1  200.26
  5440.2  199.89  5649.6   199.8  5990.4  199.66  6741.2  201.36  6770.1  203.41
  6784.5  210.98    6799  212.71  6827.6  205.52  6869.5  212.13    6948  201.17
  6997.7  200.38  7012.1  201.02  7047.4   212.1  7254.1  228.25  7503.4  252.78
#Mann= 7 ,-1 , 0
  3620.9     .11       0  4520.3     .15       0  4976.1     .06       0
 5014.52     .15       0  5440.2     .11       0  5649.6     .15       0
  5990.4     .11       0
Bank Sta=4976.1,5014.52
XS Rating Curve= 0 ,0
Exp/Cntr=0.3,0.1

Type RM Length L Ch R = 1 ,174899  ,899,899,899
BEGIN DESCRIPTION:
LAKE CREEK 167.0
END DESCRIPTION:
XS GIS Cut Line= 3
      3738710.88     10124848.06      3737441.33     10123470.01
      3735317.89     10122561.09
#Sta/Elev= 30
  2968.9  240.78  3202.4  234.08  3655.5  212.64    3793  208.96    4002   205.6
  4129.6  210.31  4292.4   201.8    4416  200.69    4532  199.46  4585.9  198.96
  4759.6  200.64  4903.2   198.6  4957.4  197.94  4975.6   196.7  4995.1  190.11
  5024.9  190.11  5033.6  194.36  5063.9  198.05  5288.3  200.97  6448.3  199.48
  6657.2  198.98  6673.8  201.19  6695.6  209.84  6709.8     212    6750  208.95
  6788.5  199.49  6809.6  201.06  6815.2  204.31  7014.6  214.08  7152.4   227.7
#Mann= 11 ,-1 , 0
  2968.9     .11       0    3793     .15       0    4416     .11       0
    4532     .15       0  4585.9     .11       0  4903.2     .15       0
  4957.4     .06       0  5063.9     .15       0  5288.3     .11       0
  6448.3     .15       0  6788.5     .11       0
Bank Sta=4957.4,5063.9
XS Rating Curve= 0 ,0
Exp/Cntr=0.3,0.1

Type RM Length L Ch R = 1 ,174000  ,1000,1000,1000
BEGIN DESCRIPTION:
LAKE CREEK 166.0
END DESCRIPTION:
XS GIS Cut Line= 3
      3739285.94     10124142.74      3737931.44     10122886.77
      3735792.44     10120670.95
#Sta/Elev= 30
  3152.8  232.39  3522.7  215.91  3895.7  209.28  4164.4  199.54  4497.2  199.46
  4553.9  195.82  4689.4  200.32    4701  200.01  4801.1  197.16  4846.1  199.81
  4900.3  199.08  4998.7  189.63  5028.5  189.63    5035  197.61  5041.9  198.88
  5918.9  199.14  5989.6  194.53  6131.1   194.4  6187.7  198.19  6534.2  202.76
  6668.5  198.44  7092.8  199.21    7121  194.65  7156.5  202.11  7184.8  214.48
  7234.2  196.95  7262.5  194.99  7587.9  209.98  7807.1     228  8079.8  236.71
#Mann= 8 ,-1 , 0
  3152.8     .15       0  3522.7     .11       0  4689.4     .15       0
    4701     .11       0  4846.1     .15       0  4900.3     .06       0
  5041.9     .15       0  7587.9     .17       0
Bank Sta=4900.3,5041.9
XS Rating Curve= 0 ,0
Exp/Cntr=0.3,0.1