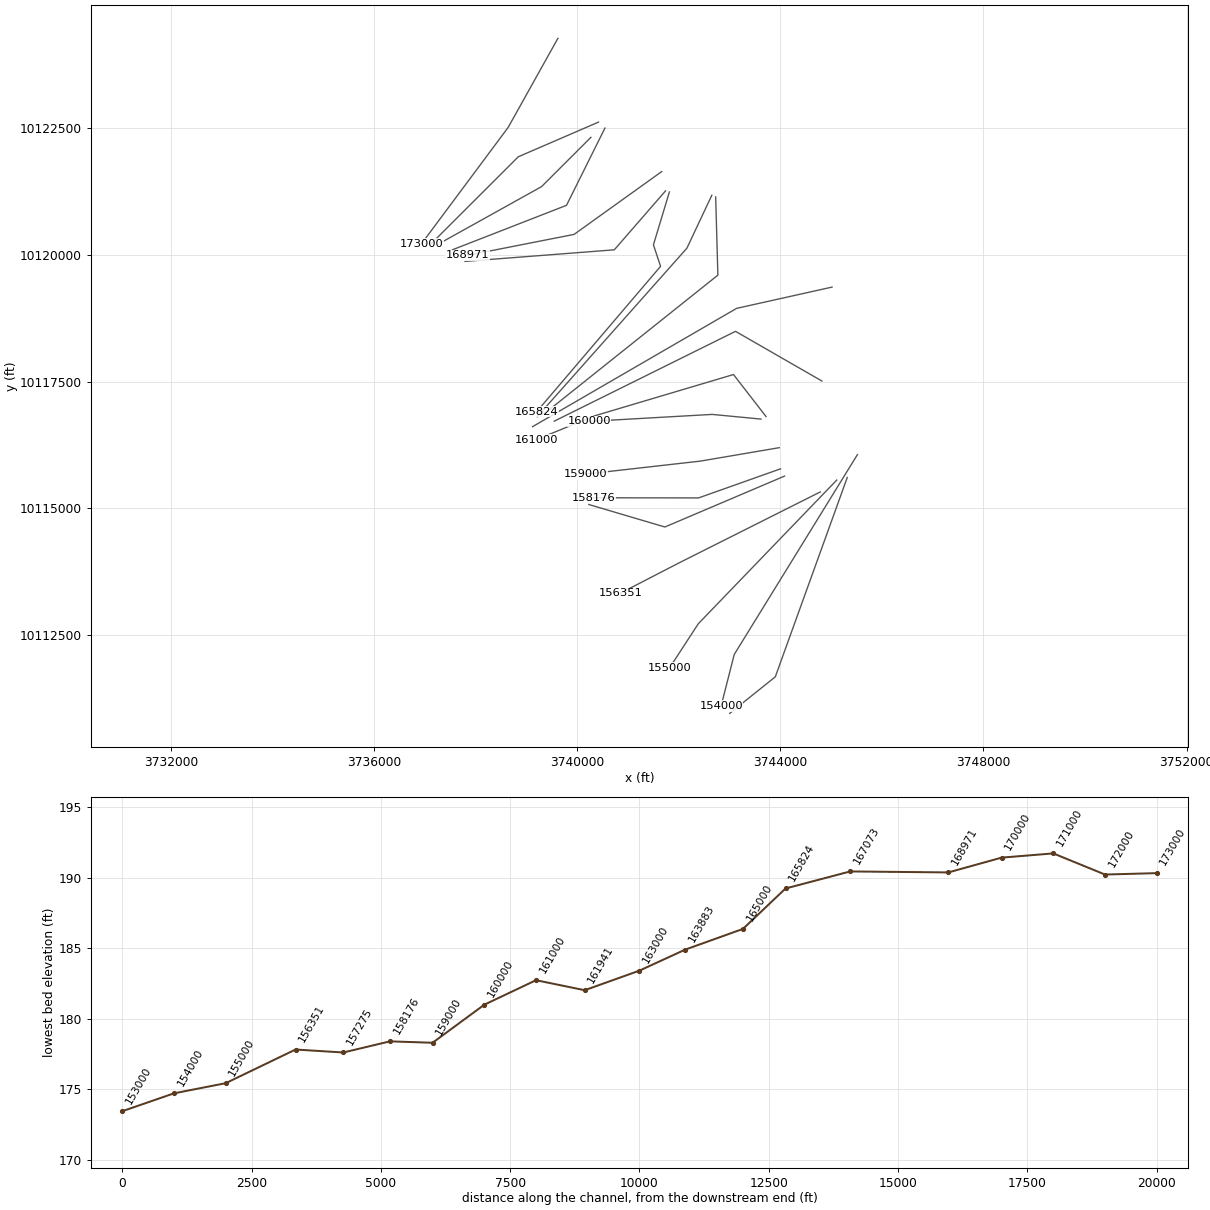
HEC-RAS study LAKE CREEK.prj: LAKE CREEK Base Level Engineering

--- LAKE CREEK.g01 (geometry) --- (continued)

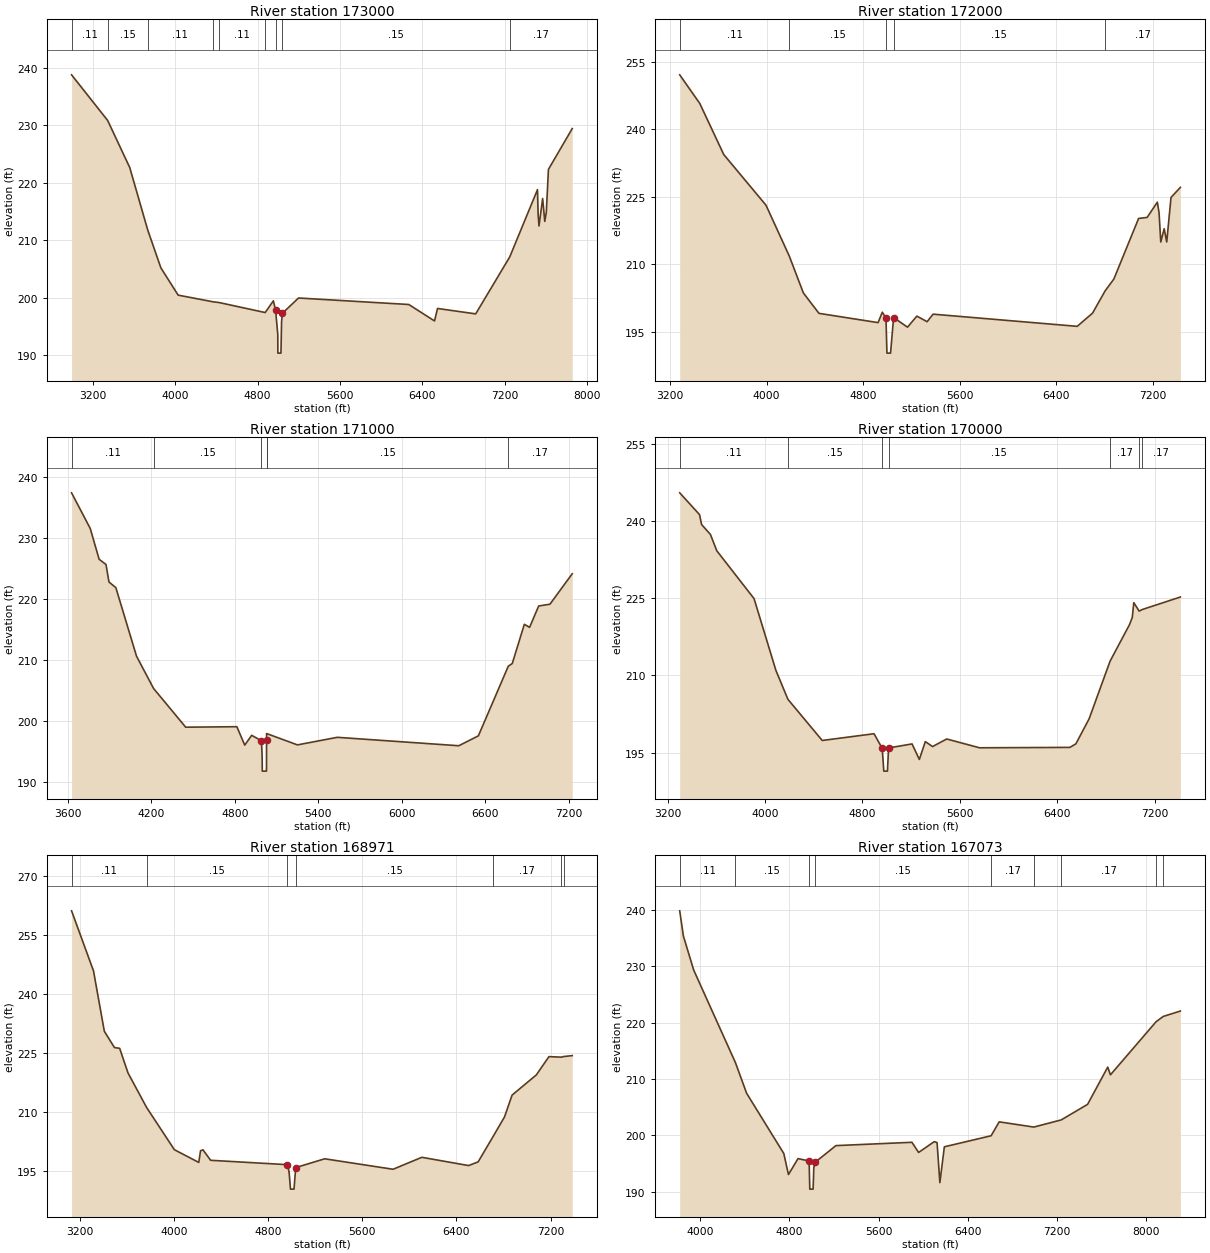
Type RM Length L Ch R = 1 ,173000  ,1000,1000,1000
BEGIN DESCRIPTION:
LAKE CREEK 165.0
END DESCRIPTION:
XS GIS Cut Line= 3
      3739617.85     10124261.07      3738638.49     10122506.95
      3736931.36     10120214.81
#Sta/Elev= 30
    2991  238.75  3341.9  230.81  3556.5  222.62  3731.4  211.75  3859.3  205.16
  4027.2  200.42  4366.7  199.26  4425.3  199.13  4873.1  197.39  4952.6  199.43
  4974.3  197.79  4995.5  193.61  4996.6  190.33  5026.4  190.33  5032.3  195.78
  5040.7  197.27  5197.1  199.92    6269  198.79  6519.2  195.93  6548.4   198.1
  6919.6  197.16  7250.5  207.07  7520.2  218.77  7526.5  214.44  7534.8  212.46
  7570.3  217.23  7591.1  213.25  7605.7  214.78  7626.6   222.3    7858   229.4
#Mann= 9 ,-1 , 0
    2991     .11       0  3341.9     .15       0  3731.4     .11       0
  4366.7     .15       0  4425.3     .11       0  4873.1     .15       0
  4974.3     .06       0  5040.7     .15       0  7250.5     .17       0
Bank Sta=4974.3,5040.7
XS Rating Curve= 0 ,0
Exp/Cntr=0.3,0.1

Type RM Length L Ch R = 1 ,172000  ,1000,1000,1000
BEGIN DESCRIPTION:
LAKE CREEK 164.0
END DESCRIPTION:
XS GIS Cut Line= 3
      3740417.85     10122611.07      3738838.09     10121928.29
      3737117.88      10120211.1
#Sta/Elev= 30
    3279  252.16  3445.3   245.8  3644.2  234.42    3995  223.13  4187.3  211.85
  4304.2  203.63  4433.8  199.08    4924  197.02  4958.7  199.33  4989.4  198.03
  4997.4  190.23  5027.3  190.23 5052.54198.1411  5167.9  196.01  5245.7  198.47
  5330.5  197.22    5380   198.9    6575  196.19  6702.3  199.13  6805.6  204.04
  6879.1  206.72  7084.2   220.2  7154.9  220.43  7239.7  223.83  7253.9  221.44
    7268  214.96  7296.3  217.91  7317.5  214.97  7352.9  224.87  7430.6  227.12
#Mann= 5 ,-1 , 0
    3279     .11       0  4187.3     .15       0  4989.4     .06       0
 5052.54     .15       0  6805.6     .17       0
Bank Sta=4989.4,5052.54
XS Rating Curve= 0 ,0
Exp/Cntr=0.3,0.1

Type RM Length L Ch R = 1 ,171000  ,1000,1000,1000
BEGIN DESCRIPTION:
LAKE CREEK 163.0
END DESCRIPTION:
XS GIS Cut Line= 3
      3740267.85     10122311.07      3739296.28     10121340.08
      3737352.75     10120258.32
#Sta/Elev= 30
  3626.4  237.34  3760.7  231.49  3824.4  226.45  3873.9  225.59  3895.1  222.73
  3944.6   221.8  4093.1  210.57  4215.6  205.28  4446.6  198.93  4814.3  199.01
  4870.9  195.99  4920.4   197.6  4991.1  196.71  4995.8  194.23  4996.9  191.73
  5026.8  191.73  5027.3  192.83 5027.69196.7782  5027.8  197.89  5249.6  196.03
  5536.1  197.27    6409  195.89  6549.7  197.51  6764.8  208.93  6793.2  209.36
  6880.1  215.79  6917.8  215.29    6983  218.79  7064.2  219.09  7224.3  224.08
#Mann= 6 ,-1 , 0
  3626.4     .11       0  4215.6     .15       0  4991.1     .06       0
 5027.69     .12       0  5027.8     .15       0  6764.8     .17       0
Bank Sta=4991.1,5027.69
XS Rating Curve= 0 ,0
Exp/Cntr=0.3,0.1

Type RM Length L Ch R = 1 ,170000  ,1029,1029,1029
BEGIN DESCRIPTION:
LAKE CREEK 162.0
END DESCRIPTION:
XS GIS Cut Line= 3
      3740544.64     10122493.46      3739787.41     10120971.76
      3737539.79     10120095.75
#Sta/Elev= 30
  3300.3  245.46  3463.2  241.23    3480  239.31  3552.8  237.37  3604.6  234.22
    3911  224.92  4090.2     211  4188.8  205.38  4470.9  197.38  4896.3  198.69
  4963.5  195.85  4976.5  191.43  5006.4  191.43  5015.6  195.93  5208.6  196.71
  5268.4   193.7  5317.4  197.16  5377.1   196.2  5493.2  197.67    5763  195.96
  6505.1  196.04  6554.1  196.73  6662.8  201.59    6835  212.78  6994.4  219.87
  7017.3  221.28  7029.6  224.14  7073.4   222.5  7098.7   222.8  7412.3  225.23
#Mann= 7 ,-1 , 0
  3300.3     .11       0  4188.8     .15       0  4963.5     .06       0
  5015.6     .15       0    6835     .17       0  7073.4     .11       0
  7098.7     .17       0
Bank Sta=4963.5,5015.6
XS Rating Curve= 0 ,0
Exp/Cntr=0.3,0.1

Type RM Length L Ch R = 1 ,168971  ,1898,1898,1898
BEGIN DESCRIPTION:
LAKE CREEK 161.0
END DESCRIPTION:
XS GIS Cut Line= 3
      3741662.29     10121636.27      3739936.99     10120399.26
      3737842.83     10119986.94
#Sta/Elev= 30
  3127.3  261.13  3313.8  245.86  3405.9  230.51  3491.9  226.37  3536.1  226.18
  3607.3  219.91  3765.4  211.14  4001.6   200.4  4209.1  197.17  4223.9  200.14
  4244.7  200.37  4309.8  197.71    4962   196.6  4976.7  194.79  4988.8  190.38
  5018.7  190.38  5033.2  195.86  5279.9  198.09  5860.9  195.43  6105.5  198.47
    6503  196.37  6584.5  197.31  6712.9  203.82  6808.7  208.74  6873.2  214.29
  7078.7   219.4  7186.5  224.06  7293.2  223.93  7310.8  224.08  7384.6  224.32
#Mann= 7 ,-1 , 0
  3127.3     .11       0  3765.4     .15       0    4962     .06       0
  5033.2     .15       0  6712.9     .17       0  7293.2     .11       0
  7310.8     .17       0
Bank Sta=4962,5033.2
XS Rating Curve= 0 ,0
Exp/Cntr=0.3,0.1

Type RM Length L Ch R = 1 ,167073  ,1249,1249,1249
BEGIN DESCRIPTION:
LAKE CREEK 160.0
END DESCRIPTION:
XS GIS Cut Line= 3
      3741738.22     10121256.48      3740729.09     10120095.44
       3737788.6     10119867.58
#Sta/Elev= 30
  3816.7  239.83  3849.6  235.37  3941.7  229.34  4315.9  212.91  4416.4  207.46
  4749.7  196.77  4791.5  193.04  4876.9  195.86  4976.6  195.45  4982.6  190.45
  5012.5  190.45  5018.4  194.24  5032.7  195.25  5216.9  198.17  5897.9  198.76
    5958  196.96  6098.5  198.88  6123.5   198.7  6148.6   191.6  6188.7  197.96
  6608.1  199.92  6680.2  202.39  6990.4  201.46    7236  202.73  7472.6  205.49
  7653.1   212.1  7677.4  210.73  8086.5  220.15  8150.8  221.09  8304.3  222.05
#Mann= 9 ,-1 , 0
  3816.7     .11       0  4315.9     .15       0  4976.6     .06       0
  5032.7     .15       0  6608.1     .17       0  6990.4     .11       0
    7236     .17       0  8086.5     .11       0  8150.8     .17       0
Bank Sta=4976.6,5032.7
XS Rating Curve= 0 ,0
Exp/Cntr=0.3,0.1

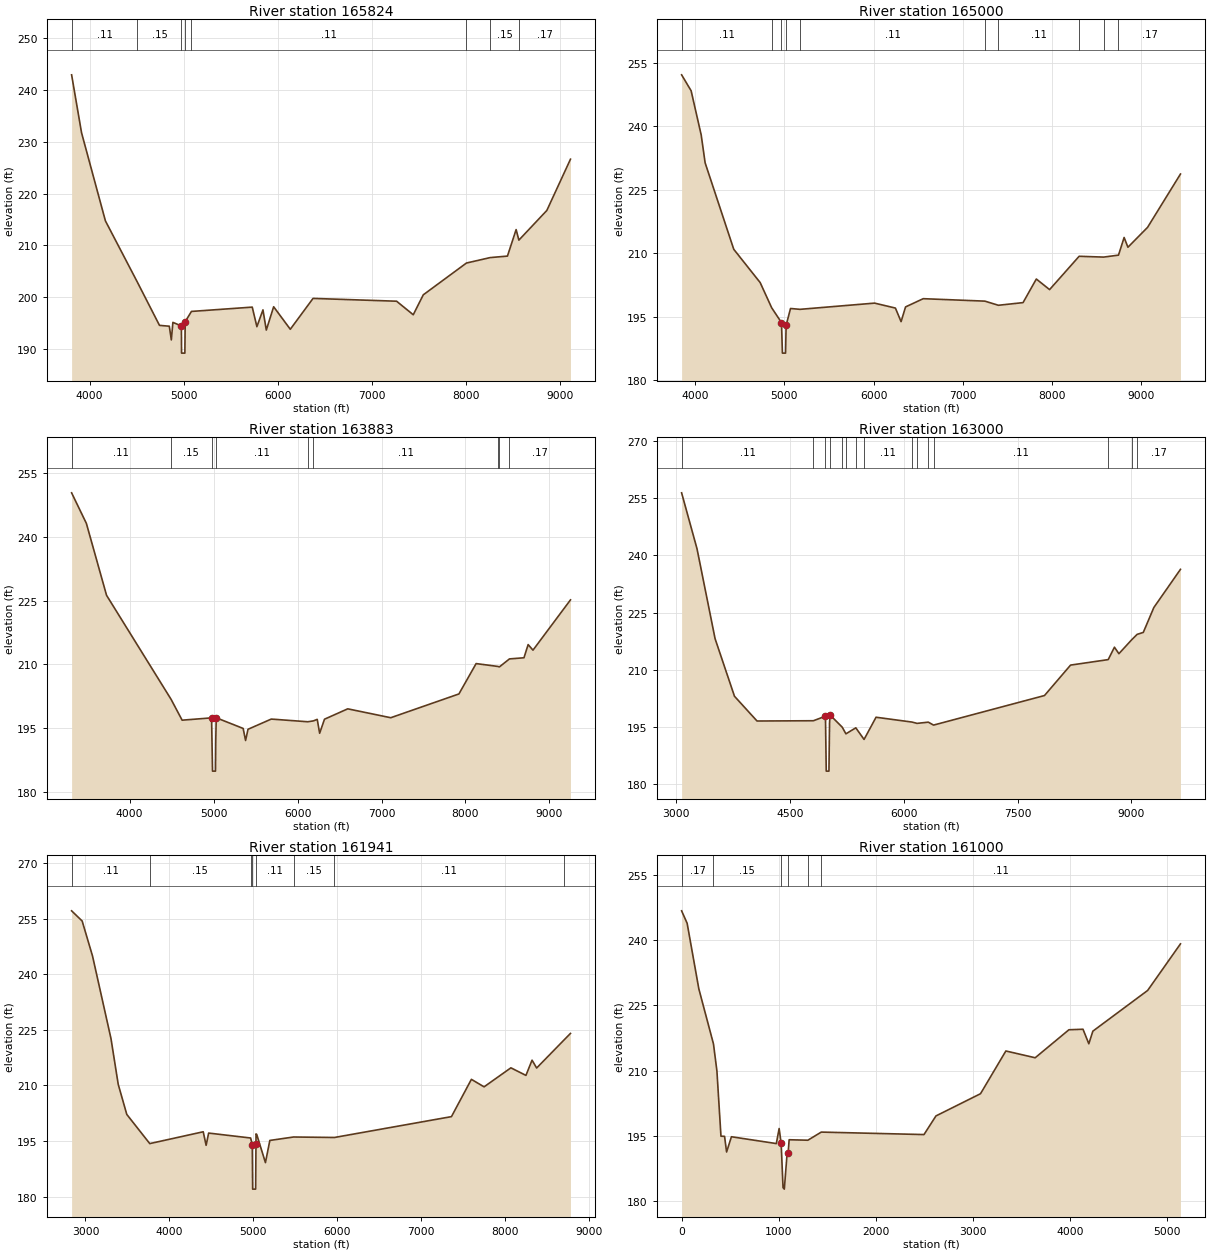
Type RM Length L Ch R = 1 ,165824  ,824,824,824
BEGIN DESCRIPTION:
LAKE CREEK 159.0
END DESCRIPTION:
XS GIS Cut Line= 4
      3741814.16     10121234.76      3741499.49      10120193.1
      3741640.55     10119769.92      3739199.49     10116905.74
#Sta/Elev= 30
  3809.5   242.9  3915.2  231.72  4168.5  214.74  4508.6   202.9  4742.8  194.59
  4846.9  194.43  4868.4  191.79  4885.1  195.17  4975.2  194.48  4977.1  189.24
  5012.3  189.24  5015.7   195.3  5082.1  197.28  5727.7  198.11  5777.1  194.34
  5841.5  197.58    5877  193.69    5955  198.18  6131.8  193.84  6373.4  199.79
  7260.5  199.25  7437.4  196.64  7543.9  200.48  8002.2  206.61  8254.2  207.66
  8437.7  207.95  8529.9  213.06  8559.3  211.03    8856  216.75    9107  226.63
#Mann= 8 ,-1 , 0
  3809.5     .11       0  4508.6     .15       0  4975.2     .06       0
  5015.7     .15       0  5082.1     .11       0  8002.2     .17       0
  8254.2     .15       0  8559.3     .17       0
Bank Sta=4975.2,5015.7
XS Rating Curve= 0 ,0
Exp/Cntr=0.3,0.1

Type RM Length L Ch R = 1 ,165000  ,1117,1117,1117
BEGIN DESCRIPTION:
LAKE CREEK 158.0
END DESCRIPTION:
XS GIS Cut Line= 3
      3742649.66     10121169.65      3742158.66     10120126.97
      3739209.97     10116807.64
#Sta/Elev= 30
  3847.5  252.21  3954.2  248.44    4067     238  4111.2  231.39    4432  210.94
  4728.3  203.06  4857.2   197.1  4967.3  193.59  4977.5  186.37  5012.7  186.37
  5019.2  192.95  5068.5  196.93    5175  196.73    6011   198.2  6244.3  197.03
  6307.9  193.82    6358   197.3  6556.2  199.25  7247.1  198.67  7398.7  197.69
  7675.1  198.32    7824   203.9  7972.8   201.4  8303.9  209.28  8578.2  209.09
  8745.1  209.55  8808.2  213.73  8850.9  211.42  9070.8  216.12  9439.9  228.74
#Mann= 10 ,-1 , 0
  3847.5     .11       0  4857.2     .15       0  4967.3     .06       0
  5019.2     .15       0    5175     .11       0  7247.1     .15       0
  7398.7     .11       0  8303.9     .17       0  8578.2     .15       0
  8745.1     .17       0
Bank Sta=4967.3,5019.2
XS Rating Curve= 0 ,0
Exp/Cntr=0.3,0.1

Type RM Length L Ch R = 1 ,163883  ,883,883,883
BEGIN DESCRIPTION:
LAKE CREEK 157.0
END DESCRIPTION:
XS GIS Cut Line= 3
      3742725.62     10121137.11      3742769.03     10119596.31
      3739329.34     10116851.07
#Sta/Elev= 30
  3308.6  250.35  3484.7  243.15  3724.8  226.25  4493.7  201.78  4625.2  196.88
  4975.9  197.43  4987.1   184.9  5022.3   184.9  5025.5  191.85 5031.26197.4479
  5352.1  194.94  5380.9   192.1  5409.8  194.74  5686.8  197.14  6122.2  196.51
  6189.8  196.72  6234.4  197.07  6263.2  193.81  6320.9  197.11  6597.9  199.55
  7110.2  197.46  7922.1  203.05    8127  210.19  8383.4  209.53  8404.8  209.42
  8524.2  211.29    8697  211.56  8746.7  214.66  8804.3  213.35  9250.9  225.17
#Mann= 9 ,-1 , 0
  3308.6     .11       0  4493.7     .15       0  4975.9     .06       0
 5031.26     .11       0  6122.2     .15       0  6189.8     .11       0
  8383.4     .17       0  8404.8     .11       0  8524.2     .17       0
Bank Sta=4975.9,5031.26
XS Rating Curve= 0 ,0
Exp/Cntr=0.3,0.1

Type RM Length L Ch R = 1 ,163000  ,1059,1059,1059
BEGIN DESCRIPTION:
LAKE CREEK 156.0
END DESCRIPTION:
XS GIS Cut Line= 3
      3745017.81     10119361.06      3743138.08     10118941.89
      3739117.88     10116611.09
#Sta/Elev= 30
  3074.1  256.38  3277.3   241.7  3515.1  218.14  3770.8  203.04  4067.9  196.55
  4810.7  196.62  4969.5  197.82  4979.8  183.41  5015.3  183.41  5023.4  196.08
  5030.3  198.13  5190.5  194.93    5239  193.19  5369.4  194.76  5478.1  191.72
    5636  197.54  6110.8  196.27  6175.6  195.93  6324.3  196.25  6393.7  195.48
  7855.4  203.23    8199  211.21    8695  212.65    8777   215.9  8835.8   214.2
  9003.3  217.83  9076.1  219.27  9157.2  219.78  9296.3  226.31    9647  236.32
#Mann= 15 ,-1 , 0
  3074.1     .11       0  4810.7     .15       0  4969.5     .06       0
  5030.3     .15       0  5190.5     .15       0    5239     .11       0
  5369.4     .15       0  5478.1     .11       0  6110.8     .15       0
  6175.6     .11       0  6324.3     .15       0  6393.7     .11       0
    8695     .17       0  9003.3     .11       0  9076.1     .17       0
Bank Sta=4969.5,5030.3
XS Rating Curve= 0 ,0
Exp/Cntr=0.3,0.1

Type RM Length L Ch R = 1 ,161941  ,941,941,941
BEGIN DESCRIPTION:
LAKE CREEK 155.0
END DESCRIPTION:
XS GIS Cut Line= 3
      3744817.89     10117511.05      3743116.25     10118489.54
       3739546.6     10116720.65
#Sta/Elev= 30
  2834.9  257.14  2960.7  254.39  3084.3  244.94  3304.3  222.66  3390.5  210.32
  3492.6  202.19  3766.5  194.31  4403.8   197.5  4438.4  193.85  4468.5  197.15
  4969.1  195.82  4988.6  194.02  4993.2  182.02  5028.7  182.02  5032.6194.1416
  5033.4  196.92  5041.6  196.78  5145.5  189.18  5197.8  195.16  5480.5  196.09
    5968  195.96  7362.9  201.59  7600.6  211.65    7752  209.63  8071.5  214.76
  8250.8  212.72  8323.7  216.83  8378.5  214.71  8702.8  222.23  8781.7  224.05
#Mann= 8 ,-1 , 0
  2834.9     .11       0  3766.5     .15       0  4969.1     .11       0
  4988.6     .06       0  5032.6     .11       0  5480.5     .15       0
    5968     .11       0  8702.8     .17       0
Bank Sta=4988.6,5032.6
XS Rating Curve= 0 ,0
Exp/Cntr=0.3,0.1

Type RM Length L Ch R = 1 ,161000  ,1000,1000,1000
BEGIN DESCRIPTION:
LAKE CREEK 154.0
END DESCRIPTION:
XS GIS Cut Line= 4
      3743717.85     10116811.07      3743076.69     10117638.54
       3740347.2       10116827.       3739193.4     10116356.86
#Sta/Elev= 30
       0  246.75      57  243.89   177.4  228.81   328.6  216.11   363.9  209.89
   405.6  194.91   442.7  194.87   463.5  191.27   513.3  194.78   975.9  193.21
  1004.9  196.67  1025.7  193.29  1045.2  183.09  1058.3  182.73  1086.3  190.71
  1097.8  191.12  1108.2  194.09  1301.1  193.98  1439.1  195.85  2497.5  195.28
  2620.9  199.57    3080  204.68  3341.1  214.51  3643.3  212.95  3990.9  219.39
    4136  219.51    4196  216.17  4237.6  219.07    4802  228.43  5140.3  239.15
#Mann= 6 ,-1 , 0
       0     .17       0   328.6     .15       0  1025.7     .06       0
  1097.8     .11       0  1301.1     .06       0  1439.1     .11       0
Bank Sta=1025.7,1097.8
XS Rating Curve= 0 ,0
Exp/Cntr=0.3,0.1

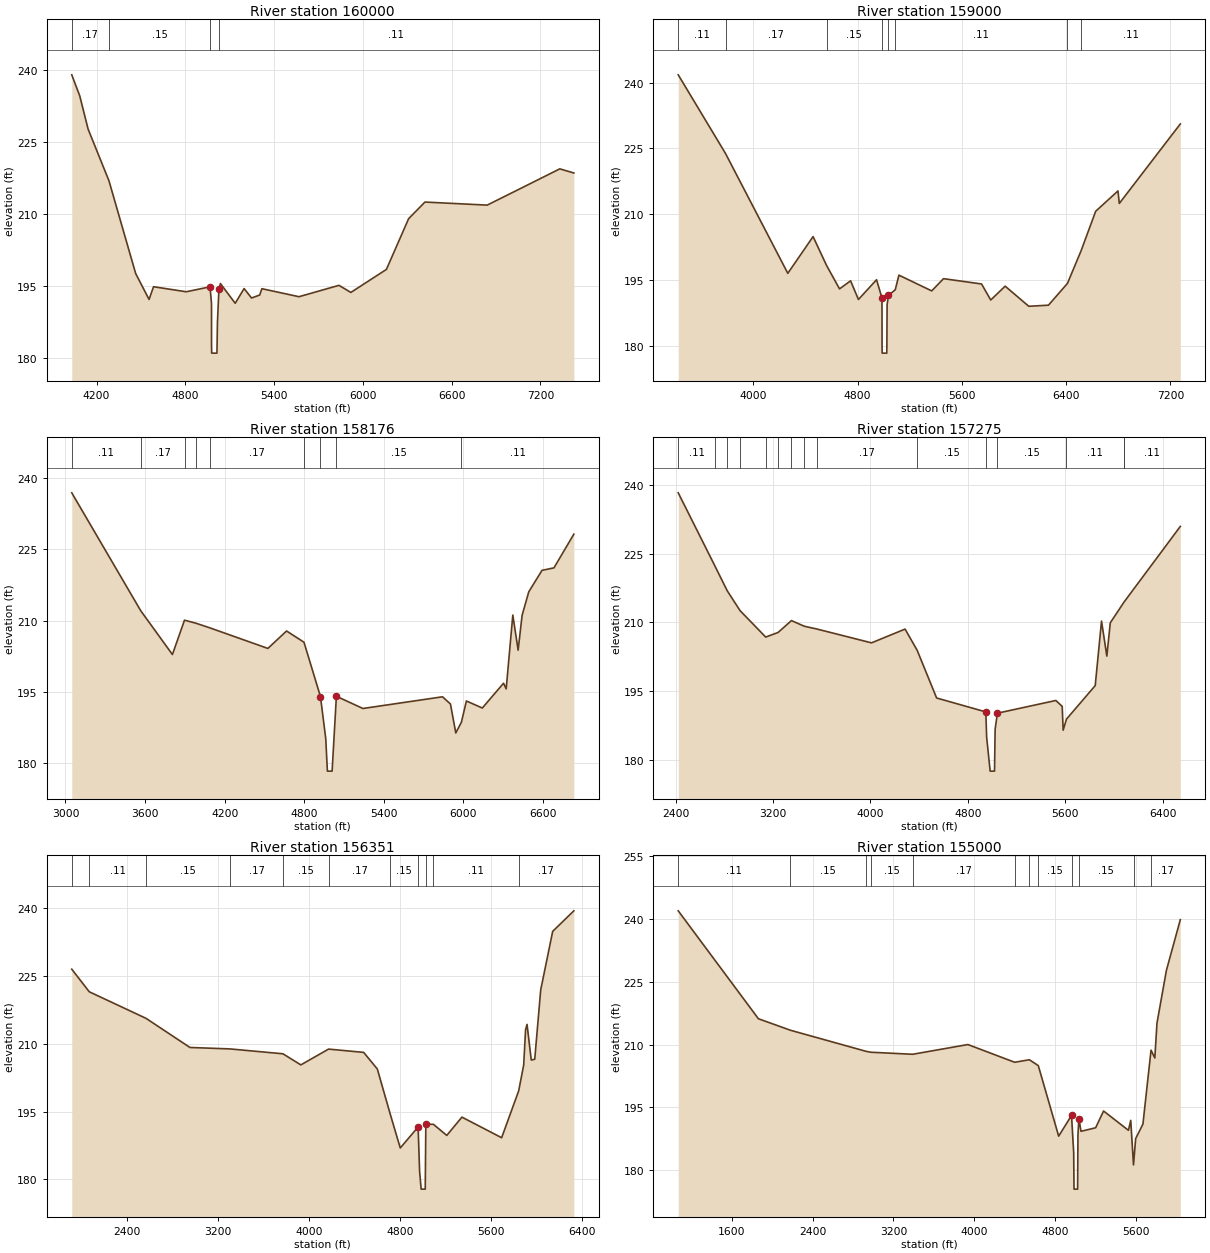
Type RM Length L Ch R = 1 ,160000  ,1000,1000,1000
BEGIN DESCRIPTION:
LAKE CREEK 153.0
END DESCRIPTION:
XS GIS Cut Line= 3
      3743617.85     10116761.07      3742655.05     10116853.25
      3740233.25      10116715.7
#Sta/Elev= 30
  4032.8     239  4086.7  234.62  4143.3  227.68  4283.9  216.94  4464.8  197.57
  4555.2  192.18  4585.3  194.83  4806.3  193.78    4967  194.81  4977.1  191.36
  4977.4  182.69  4978.3  180.99  5013.9  180.99  5017.2  187.39  5027.2  194.33
  5037.3  195.49  5137.4  191.38  5197.5  194.45  5247.6  192.48  5302.8   193.1
  5317.7  194.42  5568.1  192.75  5838.5  195.12  5918.7  193.64  6159.1  198.44
  6309.3  209.02  6419.5  212.48  6840.2  211.84  7330.9   219.4  7425.7  218.54
#Mann= 4 ,-1 , 0
  4032.8     .17       0  4283.9     .15       0    4967     .06       0
  5027.2     .11       0
Bank Sta=4967,5027.2
XS Rating Curve= 0 ,0
Exp/Cntr=0.3,0.1

Type RM Length L Ch R = 1 ,159000  ,824,824,824
BEGIN DESCRIPTION:
LAKE CREEK 152.0
END DESCRIPTION:
XS GIS Cut Line= 3
      3743977.79     10116197.87      3742423.98     10115933.18
      3740162.74     10115677.04
#Sta/Elev= 30
  3423.8  241.79  3786.8  223.83  4264.4   196.5  4458.4  204.88  4561.6  198.31
  4661.3  192.95  4746.1  194.79  4806.3  190.53  4945.3  195.04  4986.9  190.85
  4987.5  179.99  4988.4  178.29    5024  178.29  5026.3  189.34  5036.4  191.46
  5088.8  192.75  5116.9  196.08  5368.5  192.49    5459  195.28  5750.9  194.07
  5821.3  190.41    5932  193.57  6113.2  188.98  6264.2  189.23  6409.9   194.2
  6514.5  201.65  6626.5  210.66  6797.5   215.3  6807.6  212.44  7275.7  230.58
#Mann= 8 ,-1 , 0
  3423.8     .11       0  3786.8     .17       0  4561.6     .15       0
  4986.9     .06       0  5036.4     .15       0  5088.8     .11       0
  6409.9     .15       0  6514.5     .11       0
Bank Sta=4986.9,5036.4
XS Rating Curve= 0 ,0
Exp/Cntr=0.3,0.1

Type RM Length L Ch R = 1 ,158176  ,901,901,901
BEGIN DESCRIPTION:
LAKE CREEK 151.0
END DESCRIPTION:
XS GIS Cut Line= 3
      3744003.87     10115781.22      3742389.25     10115208.29
       3740317.8     10115211.07
#Sta/Elev= 30
  3047.5  236.91  3567.4  212.12  3806.2  202.91  3897.3  210.13    3985  209.48
  4088.3  208.52  4525.8  204.19  4666.7  207.86  4798.1  205.49  4922.2  194.07
  4962.2  185.18  4974.4  178.39    5010  178.39  5042.2  194.13  5242.2  191.56
  5842.2  194.02  5902.2   192.5  5942.2  186.42  5984.6  188.67  6022.2  193.14
  6142.2  191.66  6302.2  196.87  6322.2  195.69  6372.2  211.21  6412.2  203.83
  6442.2  211.15  6492.2  216.08  6592.2  220.61  6682.2  221.13  6832.2  228.22
#Mann= 9 ,-1 , 0
  3047.5     .11       0  3567.4     .17       0  3897.3     .15       0
    3985     .11       0  4088.3     .17       0  4798.1     .15       0
  4922.2     .06       0  5042.2     .15       0  5984.6     .11       0
Bank Sta=4922.2,5042.2
XS Rating Curve= 0 ,0
Exp/Cntr=0.3,0.1

Type RM Length L Ch R = 1 ,157275  ,924,924,924
BEGIN DESCRIPTION:
LAKE CREEK 150.0
END DESCRIPTION:
XS GIS Cut Line= 3
      3744081.92     10115637.96      3741725.19     10114635.37
      3740227.78     10115078.08
#Sta/Elev= 30
  2422.4  238.22    2723  222.32  2824.6  216.89  2930.1  212.56  3140.6   206.8
  3242.2   207.8    3352  210.39  3457.5  209.16    3563  208.54  4009.5  205.54
  4285.1  208.54  4384.3  203.92    4544  193.53    4948   190.5  4954.8  184.98
  4983.8   177.6  5019.4   177.6  5024.5  186.73  5043.3  190.22    5523  192.99
  5575.1   191.7    5583  186.52  5610.4  188.93  5846.3  196.23  5898.1  210.28
  5941.8  202.66  5969.9   209.9  6079.5  214.29  6080.2  214.33    6545   230.9
#Mann= 15 ,-1 , 0
  2422.4     .11       0    2723     .15       0  2824.6     .11       0
  2930.1     .17       0  3140.6     .15       0  3242.2     .17       0
    3352     .15       0  3457.5     .11       0    3563     .17       0
  4384.3     .15       0    4948     .06       0  5043.3     .15       0
  5610.4     .11       0  6079.5     .15       0  6080.2     .11       0
Bank Sta=4948,5043.3
XS Rating Curve= 0 ,0
Exp/Cntr=0.3,0.1

Type RM Length L Ch R = 1 ,156351  ,1351,1351,1351
BEGIN DESCRIPTION:
LAKE CREEK 149.0
END DESCRIPTION:
XS GIS Cut Line= 3
      3744785.05     10115325.46      3742011.65     10113932.25
      3740852.85     10113333.32
#Sta/Elev= 30
  1916.2  226.53  2069.7  221.53  2568.3  215.64  2953.8  209.19  3304.5  208.87
  3770.3  207.79  3927.4  205.33    4171  208.83    4479   208.1  4598.9  204.43
  4712.6   194.4  4800.3  186.93    4957  191.57  4970.3  181.64  4983.9  177.81
  5019.6  177.81  5024.8  192.19  5091.1  192.17  5208.7  189.71  5341.6  193.76
  5690.3   189.2  5839.9  199.57    5884   205.3  5900.5  213.13  5913.4   214.3
  5950.4  206.41    5981  206.58  6033.4  221.95  6138.5  234.91  6324.3  239.46
#Mann= 11 ,-1 , 0
  1916.2     .15       0  2069.7     .11       0  2568.3     .15       0
  3304.5     .17       0  3770.3     .15       0    4171     .17       0
  4712.6     .15       0    4957     .06       0  5024.8     .15       0
  5091.1     .11       0  5839.9     .17       0
Bank Sta=4957,5024.8
XS Rating Curve= 0 ,0
Exp/Cntr=0.3,0.1

Type RM Length L Ch R = 1 ,155000  ,1000,1000,1000
BEGIN DESCRIPTION:
LAKE CREEK 148.0
END DESCRIPTION:
XS GIS Cut Line= 3
      3745110.64     10115559.88      3742384.24     10112730.64
      3741817.83     10111861.04
#Sta/Elev= 30
  1070.9     242  1864.1  216.18  2181.1  213.43  2930.4  208.38  2976.2  208.17
  3390.2  207.68  3936.3  210.01    4399  205.77  4544.7  206.37  4632.9  204.97
  4834.4   188.1  4961.7  193.05  4983.1  184.12  4986.2  175.42  5021.9  175.42
  5025.1   188.3  5034.3  192.29  5055.4  189.25  5200.2   190.1  5278.7  194.11
  5524.6  189.49  5547.4  191.87  5574.8  181.21  5596.2  187.51    5668  190.98
  5748.2  208.67  5785.8  206.79  5806.9  215.12  5900.4  227.77  6037.8  239.88
#Mann= 12 ,-1 , 0
  1070.9     .11       0  2181.1     .15       0  2930.4     .17       0
  2976.2     .15       0  3390.2     .17       0    4399     .11       0
  4544.7     .17       0  4632.9     .15       0  4961.7     .06       0
  5034.3     .15       0  5574.8     .11       0  5748.2     .17       0
Bank Sta=4961.7,5034.3
XS Rating Curve= 0 ,0
Exp/Cntr=0.3,0.1

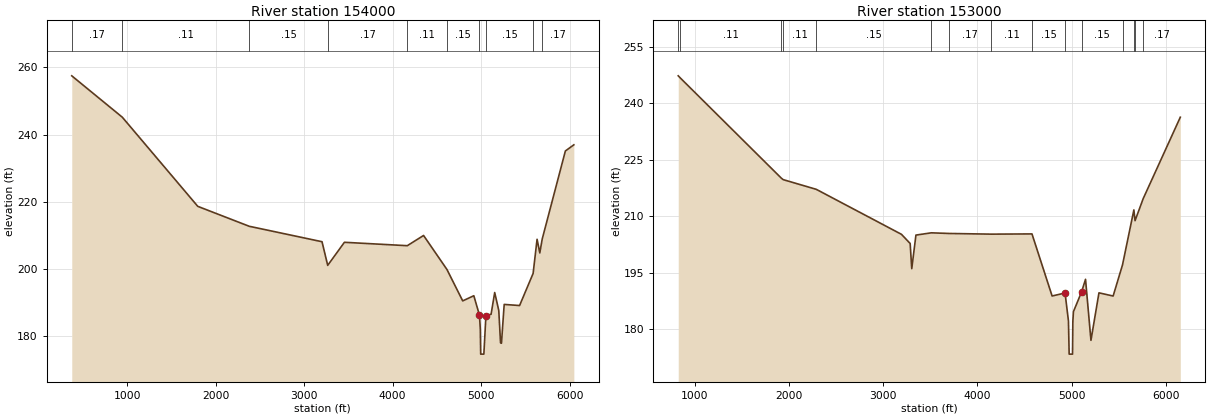
Type RM Length L Ch R = 1 ,154000  ,1000,1000,1000
BEGIN DESCRIPTION:
LAKE CREEK 147.0
END DESCRIPTION:
XS GIS Cut Line= 3
      3745517.86     10116061.09      3743091.07     10112124.03
       3742832.4     10111108.46
#Sta/Elev= 30
   375.1  257.52   946.3   245.2  1798.7  218.68  2379.6  212.75  3202.7  208.15
  3266.9  201.12  3455.8  207.98  4166.1  206.97  4350.1  210.01    4614   199.9
  4792.4  190.54  4917.9  192.08  4981.7  186.28  4991.2   182.1  4995.5   174.7
  5031.2   174.7  5054.7  186.16  5112.9  186.56  5153.8  193.03  5199.8   187.7
  5219.8  178.07  5230.1  177.93    5261  189.49  5434.9  189.16  5587.9  198.72
  5632.5  208.88  5663.5  204.82  5690.4  208.93  5952.4  235.16    6048  236.99
#Mann= 10 ,-1 , 0
   375.1     .17       0   946.3     .11       0  2379.6     .15       0
  3266.9     .17       0  4166.1     .11       0    4614     .15       0
  4981.7     .06       0  5054.7     .15       0  5587.9     .11       0
  5690.4     .17       0
Bank Sta=4981.7,5054.7
XS Rating Curve= 0 ,0
Exp/Cntr=0.3,0.1

Type RM Length L Ch R = 1 ,153000  ,823,823,823
BEGIN DESCRIPTION:
LAKE CREEK 146.0
END DESCRIPTION:
XS GIS Cut Line= 3
      3745317.85     10115611.08      3743900.45     10111684.47
      3743002.06     10110964.16
#Sta/Elev= 30
   825.4  247.26   847.5  246.69  1920.4  220.08  1938.8  219.72  2289.6  217.15
  3193.6  205.21  3285.7  202.78  3302.6  196.11    3347  205.01  3510.5  205.61
  3697.9  205.44  4146.6  205.26    4578  205.32  4791.5  188.85  4928.9  189.65
  4964.9  182.21  4972.4  173.43  5008.1  173.43  5011.6  182.14    5018  184.71
  5104.4  189.95    5146  193.28  5203.6  177.09  5288.5  189.69  5438.9  188.84
  5538.6  197.13  5658.9  211.69  5671.4  208.83  5757.8  214.68  6151.5  236.28
#Mann= 15 ,-1 , 0
   825.4     .17       0   847.5     .11       0  1920.4     .17       0
  1938.8     .11       0  2289.6     .15       0  3510.5     .11       0
  3697.9     .17       0  4146.6     .11       0    4578     .15       0
  4928.9     .06       0  5104.4     .15       0  5538.6     .11       0
  5658.9     .17       0  5671.4     .11       0  5757.8     .17       0
Bank Sta=4928.9,5104.4
XS Rating Curve= 0 ,0
Exp/Cntr=0.3,0.1