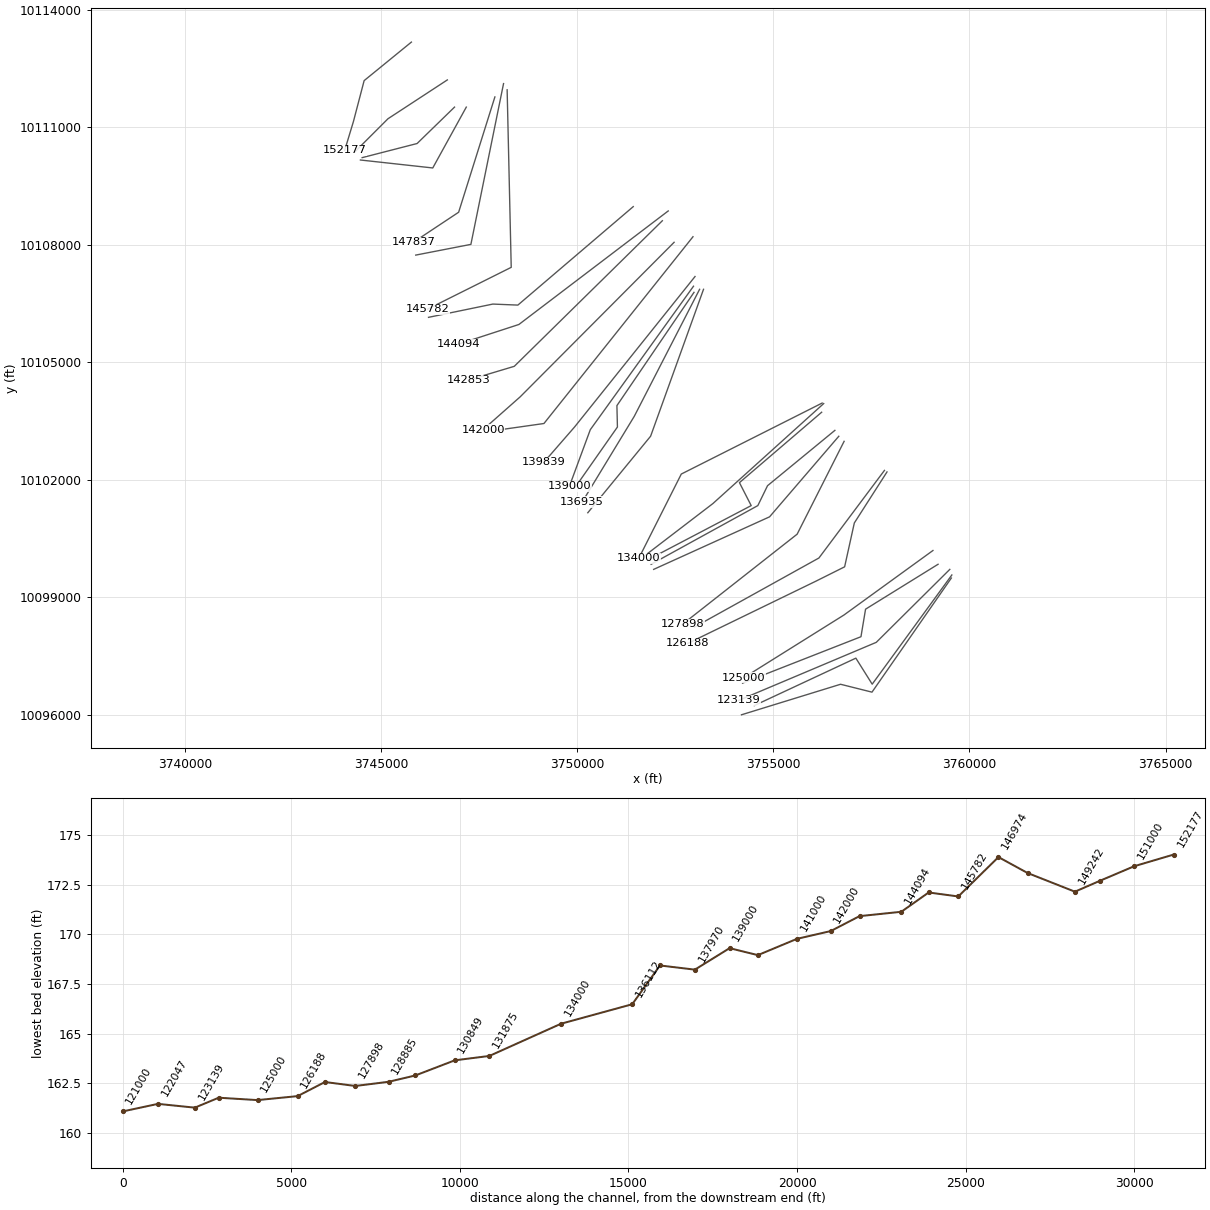
HEC-RAS study LAKE CREEK.prj: LAKE CREEK Base Level Engineering

--- LAKE CREEK.g01 (geometry) --- (continued)

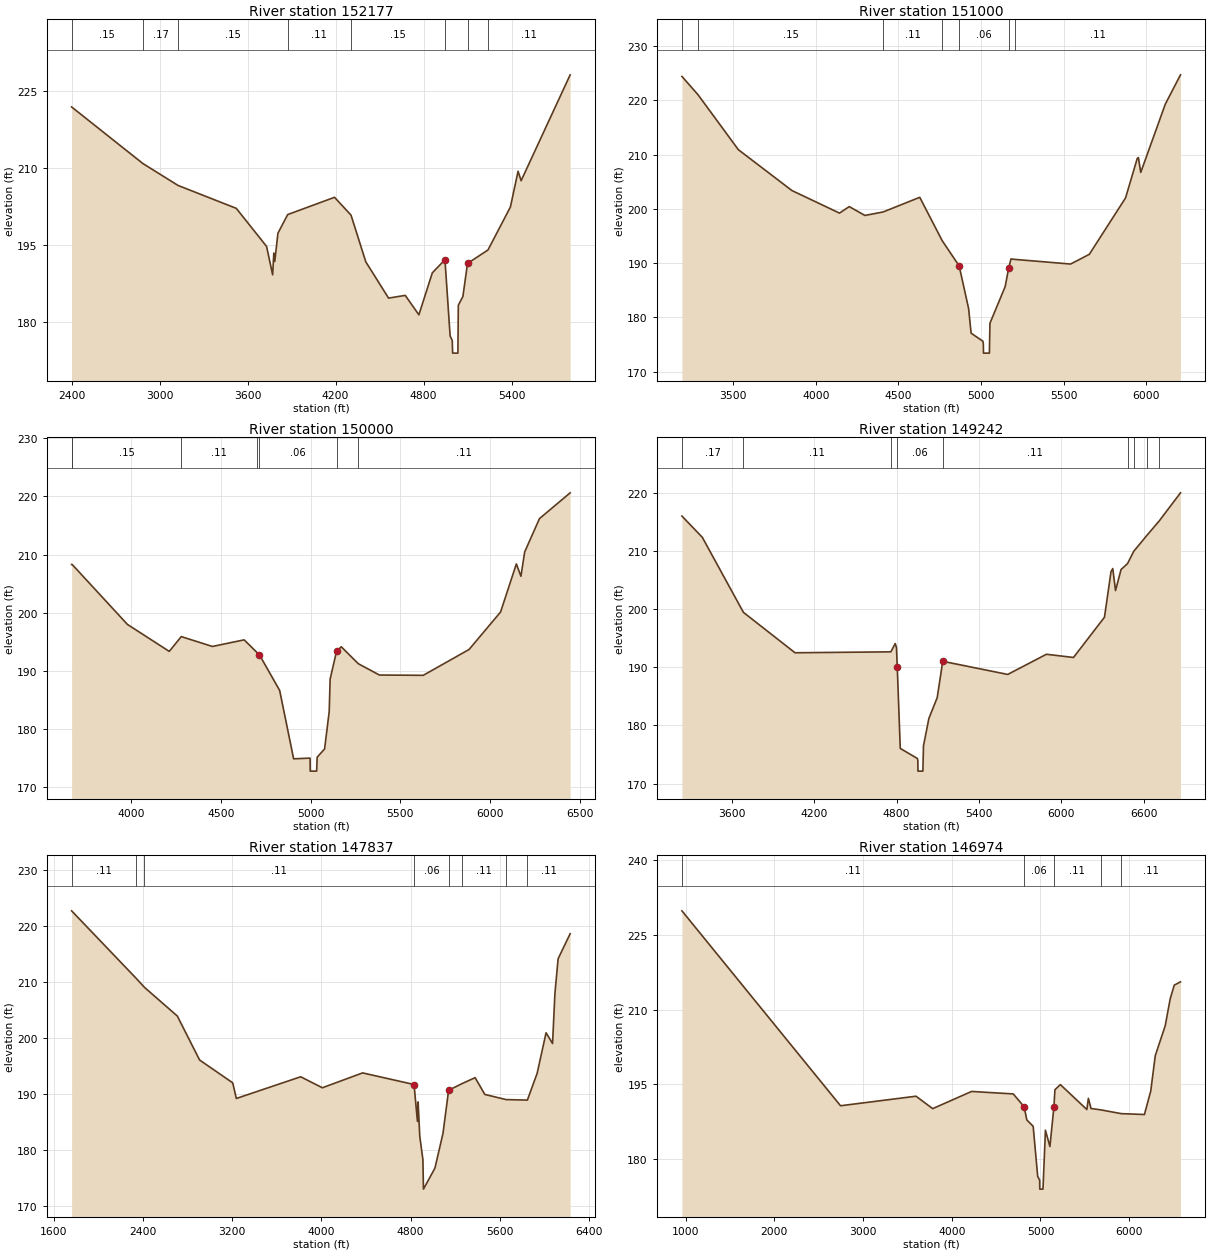
Type RM Length L Ch R = 1 ,152177  ,1177,1177,1177
BEGIN DESCRIPTION:
LAKE CREEK 145.0
END DESCRIPTION:
XS GIS Cut Line= 4
      3745767.92     10113170.56      3744562.52       10112187.
      3744290.29     10111145.79      3744067.86     10110411.09
#Sta/Elev= 30
    2400  221.93  2885.9  210.92  3125.7  206.65    3523  202.19  3729.4  194.79
    3771  189.26  3778.9   193.5  3785.4  191.86  3806.9  197.34  3873.6  200.98
    4193  204.34  4305.4  200.87  4406.3  191.77  4561.4  184.72  4675.1  185.25
  4768.1  181.47  4859.8  189.64  4945.9  192.19  4981.2  177.33  4995.5   176.5
  4998.3  174.01    5034  174.01    5037  183.33  5068.2  185.03  5099.6  191.46
  5239.3  194.09  5392.1  202.45  5444.4  209.41  5465.3  207.57  5799.6  228.18
#Mann= 8 ,-1 , 0
    2400     .15       0  2885.9     .17       0  3125.7     .15       0
  3873.6     .11       0  4305.4     .15       0  4945.9     .06       0
  5099.6     .15       0  5239.3     .11       0
Bank Sta=4945.9,5099.6
XS Rating Curve= 0 ,0
Exp/Cntr=0.3,0.1

Type RM Length L Ch R = 1 ,151000  ,1000,1000,1000
BEGIN DESCRIPTION:
LAKE CREEK 144.0
END DESCRIPTION:
XS GIS Cut Line= 3
      3746684.58     10112205.27      3745170.83     10111214.25
      3744317.87     10110361.09
#Sta/Elev= 30
  3190.7  224.43  3288.4  221.04  3531.8  210.93  3856.1  203.39  4143.8  199.23
  4202.7  200.43  4297.6   198.8  4407.5  199.44  4629.3  202.14    4765  194.15
  4867.5  189.51  4924.8  181.64  4939.9   177.1  5011.4  175.61  5013.9  175.12
  5014.8  173.42  5050.5  173.42  5053.8  178.92  5145.8  185.67    5167  189.06
  5181.1  190.78  5203.9   190.7  5541.8  189.84  5654.9  191.63  5874.1  202.03
  5944.8   209.3  5951.9  209.47    5966  206.73  6114.5  219.31  6206.4  224.72
#Mann= 7 ,-1 , 0
  3190.7     .17       0  3288.4     .15       0  4407.5     .11       0
    4765     .15       0  4867.5     .06       0    5167     .15       0
  5203.9     .11       0
Bank Sta=4867.5,5167
XS Rating Curve= 0 ,0
Exp/Cntr=0.3,0.1

Type RM Length L Ch R = 1 ,150000  ,758,758,758
BEGIN DESCRIPTION:
LAKE CREEK 143.0
END DESCRIPTION:
XS GIS Cut Line= 3
      3746867.86     10111511.08      3745913.19     10110581.91
      3744512.21     10110221.45
#Sta/Elev= 30
  3667.8  208.29    3671  208.29  3978.9  197.97  4212.2  193.32  4279.1  195.87
  4452.7  194.17  4629.6  195.31  4698.5  193.21  4714.4  192.75  4827.5   186.6
  4905.4  174.82    4997  174.94  4997.9   172.7  5033.7   172.7  5036.5   175.1
  5077.8  176.51  5103.6  182.95  5108.8  188.55  5144.4  193.31  5170.7  194.12
  5265.9   191.2  5383.5  189.25  5627.8   189.2  5883.2  193.65  6058.7   200.1
  6146.8  208.39  6172.3  206.26    6193  210.44  6275.6  216.19  6446.6  220.63
#Mann= 7 ,-1 , 0
  3667.8     .17       0    3671     .15       0  4279.1     .11       0
  4698.5     .17       0  4714.4     .06       0  5144.4     .15       0
  5265.9     .11       0
Bank Sta=4714.4,5144.4
XS Rating Curve= 0 ,0
Exp/Cntr=0.3,0.1

Type RM Length L Ch R = 1 ,149242  ,1405,1405,1405
BEGIN DESCRIPTION:
LAKE CREEK 142.0
END DESCRIPTION:
XS GIS Cut Line= 3
      3747167.85     10111511.07      3746312.68     10109958.22
      3744467.86     10110161.07
#Sta/Elev= 30
  3237.6  216.06    3386   212.4  3685.3  199.48  4060.8  192.52  4758.5  192.68
  4790.2  194.11  4799.3   193.4    4805  190.05  4826.8  176.05  4951.8  174.31
  4954.8  173.94  4955.6  172.14  4991.4  172.14  4995.7   176.5  5035.3  181.23
  5095.7  184.79  5135.9  191.05  5608.8  188.79  5890.5  192.26  6087.6  191.71
    6313  198.64  6360.7  206.49  6373.4  207.02  6393.5  203.23  6433.7  206.85
  6481.1  207.88  6525.7  209.98  6625.4  212.83  6711.2  215.21  6866.3  220.06
#Mann= 9 ,-1 , 0
  3237.6     .17       0  3685.3     .11       0  4758.5     .15       0
    4805     .06       0  5135.9     .11       0  6481.1     .17       0
  6525.7     .11       0  6625.4     .17       0  6711.2     .11       0
Bank Sta=4805,5135.9
XS Rating Curve= 0 ,0
Exp/Cntr=0.3,0.1

Type RM Length L Ch R = 1 ,147837  ,863,863,863
BEGIN DESCRIPTION:
LAKE CREEK 141.0
END DESCRIPTION:
XS GIS Cut Line= 3
      3747897.06     10111770.76      3746972.58     10108828.08
      3745817.89     10108061.09
#Sta/Elev= 30
  1759.9  222.72    2337  210.72  2412.9  209.08  2708.2  203.95  2907.8  196.11
  3204.7  192.04  3237.1  189.25  3814.2  193.12  4008.7  191.16  4369.6  193.81
  4830.8  191.74  4861.1  185.16  4867.1  188.64  4882.1   182.5  4910.1  178.36
  4915.1  173.08  5018.1  176.83  5090.2  183.02  5140.7  190.71    5260  191.89
  5378.3  192.96  5465.4  189.97  5656.1  189.05  5846.9  188.96  5934.5  193.73
  6014.6  200.97  6072.8  199.05  6093.8  207.93  6122.6  214.17  6230.6  218.64
#Mann= 8 ,-1 , 0
  1759.9     .11       0    2337     .17       0  2412.9     .11       0
  4830.8     .06       0  5140.7     .15       0    5260     .11       0
  5656.1     .15       0  5846.9     .11       0
Bank Sta=4830.8,5140.7
XS Rating Curve= 0 ,0
Exp/Cntr=0.3,0.1

Type RM Length L Ch R = 1 ,146974  ,1192,1192,1192
BEGIN DESCRIPTION:
LAKE CREEK 140.0
END DESCRIPTION:
XS GIS Cut Line= 3
      3748117.86     10112111.11      3747285.08     10108007.77
      3745878.82     10107734.33
#Sta/Elev= 30
   958.8  229.86  2746.7  190.65  3597.5  192.57  3785.3  190.07  4224.1  193.53
  4693.5  193.03  4815.9  190.46  4846.5   187.8  4917.9  186.52    4969  176.43
  4991.5  175.68  4992.4  173.88  5028.6  173.88  5056.1  185.74  5106.7  182.45
  5151.4  190.35  5163.4  193.88  5224.5   194.9  5523.2  189.89  5540.3  192.14
  5569.8   190.1  5680.8  189.82    5913  189.06  6171.9  188.89  6243.2  193.61
  6294.1  200.72  6406.2  206.73  6462.2  212.14  6508.1  214.91  6578.4  215.58
#Mann= 5 ,-1 , 0
   958.8     .11       0  4815.9     .06       0  5151.4     .11       0
  5680.8     .15       0    5913     .11       0
Bank Sta=4815.9,5151.4
XS Rating Curve= 0 ,0
Exp/Cntr=0.3,0.1

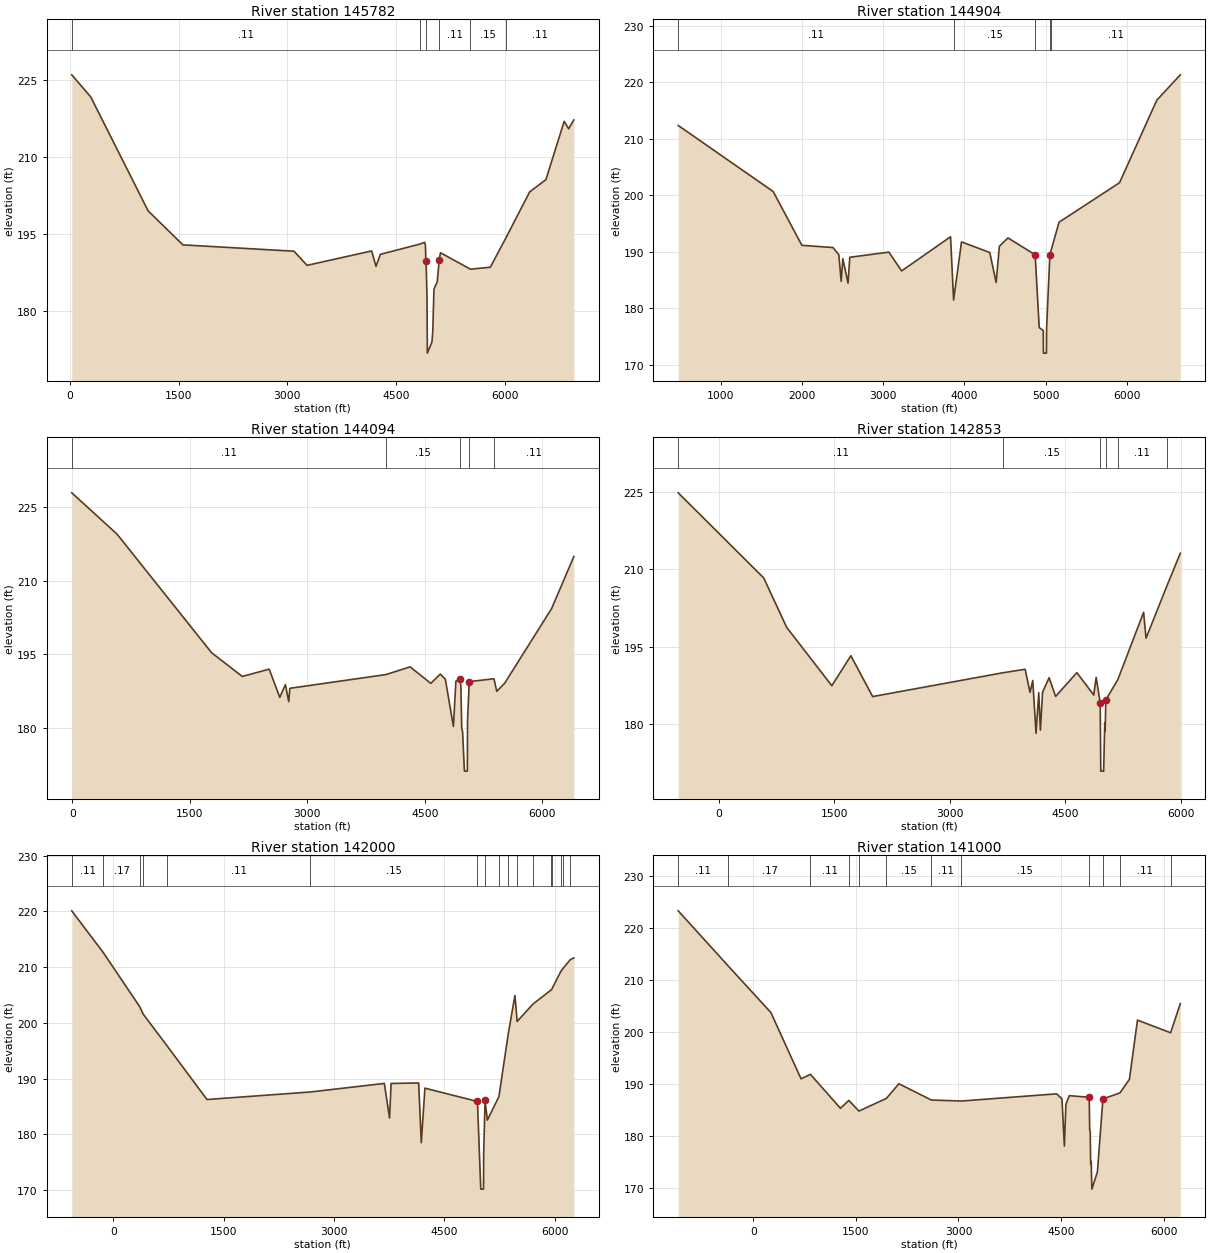
Type RM Length L Ch R = 1 ,145782  ,878,878,878
BEGIN DESCRIPTION:
LAKE CREEK 139.0
END DESCRIPTION:
XS GIS Cut Line= 3
      3748209.56     10111953.04      3748313.73     10107421.83
      3746178.29     10106354.11
#Sta/Elev= 30
    28.7  226.02   290.7  221.71  1080.9  199.57  1561.1  192.95  3091.5  191.72
  3271.5  188.97  4161.8  191.77  4221.8  188.78  4281.8  191.11  4830.8  193.12
  4892.3  193.45  4903.1  192.86    4909  189.81  4914.6  188.56  4925.4  182.18
  4929.7   171.9  4992.5  174.05  5004.1   176.1  5020.8  184.35  5065.6  185.79
  5093.5   190.1  5110.3  191.42  5523.9  188.22  5797.5  188.61  6015.1  194.38
  6340.1  203.26  6563.7  205.63  6815.3  216.97  6876.8  215.53  6948.6  217.25
#Mann= 6 ,-1 , 0
    28.7     .11       0  4830.8     .17       0    4909     .06       0
  5093.5     .11       0  5523.9     .15       0  6015.1     .11       0
Bank Sta=4909,5093.5
XS Rating Curve= 0 ,0
Exp/Cntr=0.3,0.1

Type RM Length L Ch R = 1 ,144904  ,810,810,810
BEGIN DESCRIPTION:
LAKE CREEK 138.0
END DESCRIPTION:
XS GIS Cut Line= 4
      3751425.73     10108971.32        3748483.     10106458.29
      3747844.98     10106484.33      3746205.04     10106145.93
#Sta/Elev= 30
     475  212.38  1643.6   200.7  1998.2  191.17  2381.3  190.78  2452.7   189.5
  2481.3  184.82  2502.1  188.81  2565.8  184.48  2587.8  189.06  3069.7  189.97
  3225.6  186.64  3828.4  192.69    3866   181.5  3963.4  191.78  4311.4   189.9
  4389.9  184.61    4430  191.01  4535.4  192.49  4870.3   189.5  4920.4  176.62
  4970.4  176.09    4972   172.1  5009.2   172.1    5011  176.46  5051.8  189.51
  5063.3   190.1  5164.2  195.26  5909.5  202.25    6369  216.87  6657.8  221.34
#Mann= 5 ,-1 , 0
     475     .11       0    3866     .15       0  4870.3     .06       0
  5051.8     .15       0  5063.3     .11       0
Bank Sta=4870.3,5051.8
XS Rating Curve= 0 ,0
Exp/Cntr=0.3,0.1

Type RM Length L Ch R = 1 ,144094  ,1241,1241,1241
BEGIN DESCRIPTION:
LAKE CREEK 137.0
END DESCRIPTION:
XS GIS Cut Line= 3
      3752317.83     10108861.06      3748509.04      10105963.5
      3746967.85     10105461.07
#Sta/Elev= 30
    -5.6  227.98   572.4  219.54  1778.6  195.32  2170.3  190.47  2513.4  191.96
  2648.5  186.21  2720.9   188.8  2762.9  185.31  2777.4  188.05  4005.2  190.86
  4311.9  192.43  4575.9  189.06  4696.6  190.95    4761  189.93  4864.4  180.26
  4896.3  189.51  4949.6  190.01  4960.1  188.21  4970.7  179.78  4981.2  179.27
  5004.6  171.13  5041.9  171.13  5042.8  173.03  5044.3   181.3  5066.4  189.41
    5382     190  5417.4  187.43  5518.3  189.08  6117.1  204.33  6401.1  214.96
#Mann= 5 ,-1 , 0
    -5.6     .11       0  4005.2     .15       0  4949.6     .06       0
  5066.4     .15       0    5382     .11       0
Bank Sta=4949.6,5066.4
XS Rating Curve= 0 ,0
Exp/Cntr=0.3,0.1

Type RM Length L Ch R = 1 ,142853  ,853,853,853
BEGIN DESCRIPTION:
LAKE CREEK 136.0
END DESCRIPTION:
XS GIS Cut Line= 3
      3752167.86     10108611.08      3748391.86     10104895.79
      3747221.42     10104544.66
#Sta/Elev= 30
  -526.5  224.85   583.7  208.35   880.7   198.8  1467.6  187.46  1715.2  193.28
    1998  185.36  3691.1  189.98  3977.9  190.65  4041.6  186.17  4076.9  188.48
  4119.3  178.24  4154.7  186.11  4175.9  178.85  4204.2  186.21    4289  189.01
  4373.9  185.39  4649.8     190    4869  185.66  4900.3  189.08  4952.5  184.12
    4960  170.91  4997.3  170.91  5011.7  180.24  5016.9  178.62  5025.6  184.71
  5182.4  188.68  5516.3  201.69  5547.6  196.67  5819.3  206.83  5992.8  213.14
#Mann= 6 ,-1 , 0
  -526.5     .11       0  3691.1     .15       0  4952.5     .06       0
  5025.6     .15       0  5182.4     .11       0  5819.3     .17       0
Bank Sta=4952.5,5025.6
XS Rating Curve= 0 ,0
Exp/Cntr=0.3,0.1

Type RM Length L Ch R = 1 ,142000  ,1000,1000,1000
BEGIN DESCRIPTION:
LAKE CREEK 135.0
END DESCRIPTION:
XS GIS Cut Line= 3
      3752467.86     10108061.08      3748542.26     10104117.16
      3747597.62     10103281.23
#Sta/Elev= 30
  -564.6   220.1  -134.6  212.58   357.2  202.94   407.3  201.55   725.7  195.97
  1273.9  186.24  2678.2  187.59  3685.1  189.13  3755.8  182.92  3777.1  189.12
  4151.8  189.21  4187.2   178.5  4236.7  188.28  4950.9  185.89    4996  170.16
  5033.3  170.16  5035.5  176.51 5054.33 186.069  5085.8  182.54  5242.8  186.77
  5370.7  198.11  5460.5   204.9  5491.1  200.25  5702.9  203.34  5956.5  205.94
  5957.7  205.94  6085.1  209.25  6111.6  209.72  6212.5  211.33  6261.4  211.65
#Mann= 17 ,-1 , 0
  -564.6     .11       0  -134.6     .17       0   357.2     .11       0
   407.3     .17       0   725.7     .11       0  2678.2     .15       0
  4950.9     .06       0 5054.33     .15       0  5242.8     .11       0
  5370.7     .15       0  5491.1     .11       0  5702.9     .17       0
  5956.5     .11       0  5957.7     .17       0  6085.1     .11       0
  6111.6     .17       0  6212.5     .11       0
Bank Sta=4950.9,5054.33
XS Rating Curve= 0 ,0
Exp/Cntr=0.3,0.1

Type RM Length L Ch R = 1 ,141000  ,1161,1161,1161
BEGIN DESCRIPTION:
LAKE CREEK 134.0
END DESCRIPTION:
XS GIS Cut Line= 3
      3752949.15     10108203.08      3749148.22     10103436.24
      3747917.83     10103261.07
#Sta/Elev= 30
 -1096.7  223.25  -362.9  212.61     258   203.7   698.3  190.97   836.3  191.82
  1274.8   185.3  1397.4  186.82  1544.7  184.77  1946.7  187.21  2128.9  190.02
    2604  186.89    3042   186.7  4434.3  188.08  4512.8  187.12    4548  178.05
  4570.4  186.06  4620.1  187.73  4911.5  187.42  4917.9  181.16  4925.9  180.95
  4932.3  174.54  4940.4  175.08  4949.6  169.77  5030.7  173.06  5111.5   187.1
  5360.6  188.26  5499.1  190.88  5616.5  202.25  6100.6  199.82  6242.8  205.41
#Mann= 12 ,-1 , 0
 -1096.7     .11       0  -362.9     .17       0   836.3     .11       0
  1397.4     .15       0  1544.7     .11       0  1946.7     .15       0
    2604     .11       0    3042     .15       0  4911.5     .06       0
  5111.5     .15       0  5360.6     .11       0  6100.6     .17       0
Bank Sta=4911.5,5111.5
XS Rating Curve= 0 ,0
Exp/Cntr=0.3,0.1

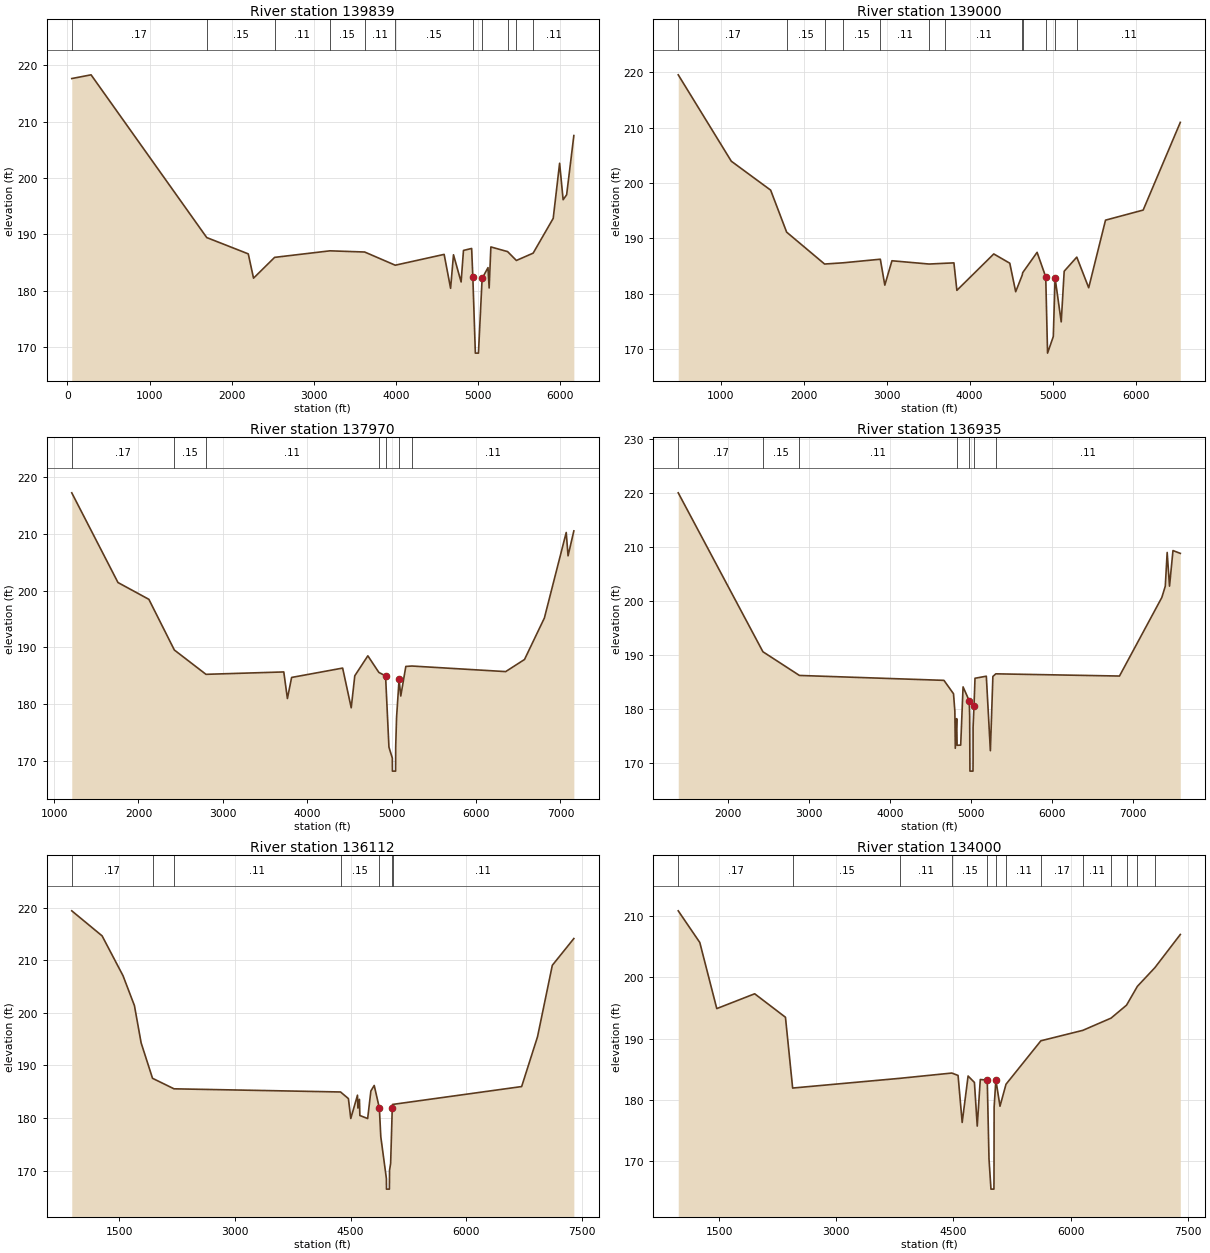
Type RM Length L Ch R = 1 ,139839  ,839,839,839
BEGIN DESCRIPTION:
LAKE CREEK 133.0
END DESCRIPTION:
XS GIS Cut Line= 3
      3753001.25     10107187.47      3749928.31     10103346.31
      3749147.06     10102447.87
#Sta/Elev= 30
    53.1  217.64     288   218.3  1695.7  189.44    2201  186.55    2265  182.24
  2521.6  185.93  3194.4  187.09  3617.4  186.88  3989.4  184.54  4584.5  186.46
    4663  180.44  4698.2  186.39    4791  181.57  4819.8  187.16  4919.1  187.51
 4933.74182.3966  4964.3  168.95    5002  168.95  5046.7  182.19    5118  184.11
  5132.2   180.5  5153.1  187.78  5356.8  186.95  5463.6  185.38  5667.6  186.68
  5911.8  192.85  5989.6  202.62  6032.4  196.15  6075.1  197.03  6162.8  207.53
#Mann= 11 ,-1 , 0
    53.1     .17       0  1695.7     .15       0  2521.6     .11       0
  3194.4     .15       0  3617.4     .11       0  3989.4     .15       0
 4933.74     .06       0  5046.7     .15       0  5356.8     .11       0
  5463.6     .15       0  5667.6     .11       0
Bank Sta=4933.74,5046.7
XS Rating Curve= 0 ,0
Exp/Cntr=0.3,0.1

Type RM Length L Ch R = 1 ,139000  ,1030,1030,1030
BEGIN DESCRIPTION:
LAKE CREEK 132.0
END DESCRIPTION:
XS GIS Cut Line= 3
      3752962.15     10106940.03      3750330.07       10103278.
      3749798.14     10101835.98
#Sta/Elev= 30
   490.2  219.53  1129.3  203.94  1603.1  198.72  1795.6  191.14  2252.8  185.38
  2474.9   185.6  2924.2  186.25  2978.1  181.57    3064  185.97  3511.5  185.38
  3706.3  185.52  3810.4  185.59    3846  180.63  4290.4   187.2  4483.2  185.53
  4554.4  180.38    4633  183.38  4639.1  183.83  4812.2  187.49 4916.22183.0636
  4938.2   169.3  5007.4   172.3  5028.7  182.89  5102.8  174.94  5138.5  184.08
  5290.2  186.63  5433.7   181.1  5636.2   193.3  6089.6  195.12    6537  210.95
#Mann= 12 ,-1 , 0
   490.2     .17       0  1795.6     .15       0  2252.8     .11       0
  2474.9     .15       0  2924.2     .11       0  3511.5     .15       0
  3706.3     .11       0    4633     .15       0  4639.1     .11       0
 4916.22     .06       0  5028.7     .11       0  5290.2     .11       0
Bank Sta=4916.22,5028.7
XS Rating Curve= 0 ,0
Exp/Cntr=0.3,0.1

Type RM Length L Ch R = 1 ,137970  ,1035,1035,1035
BEGIN DESCRIPTION:
LAKE CREEK 131.0
END DESCRIPTION:
XS GIS Cut Line= 4
      3752975.16     10106783.77      3751009.04     10103893.18
      3751022.06     10103346.31       3749929.1     10101784.94
#Sta/Elev= 30
  1209.9  217.21  1757.4  201.42  2123.5  198.46  2425.4  189.54  2799.9  185.26
  3721.9  185.68    3765     181  3814.7  184.71  4419.3  186.36    4521  179.37
  4563.2     185  4717.9  188.52  4848.8  185.59  4927.9  184.99    4968  172.44
    5008  170.51  5009.1  168.22  5046.8  168.22    5048   172.5    5058   177.6
    5088  184.36    5108  181.44    5168  186.65  5240.9  186.72  6350.9  185.74
  6574.1  187.87  6809.5  195.17  7068.4  210.23  7090.2  206.12  7158.7  210.51
#Mann= 7 ,-1 , 0
  1209.9     .17       0  2425.4     .15       0  2799.9     .11       0
  4848.8     .15       0  4927.9     .06       0    5088     .15       0
  5240.9     .11       0
Bank Sta=4927.9,5088
XS Rating Curve= 0 ,0
Exp/Cntr=0.3,0.1

Type RM Length L Ch R = 1 ,136935  ,823,823,823
BEGIN DESCRIPTION:
LAKE CREEK 130.0
END DESCRIPTION:
XS GIS Cut Line= 3
      3753117.86     10106861.09      3751451.75     10103619.75
      3750123.62     10101432.24
#Sta/Elev= 30
  1381.2     220  2427.6  190.55  2878.5  186.16  4664.4  185.25  4782.5  182.77
  4799.1  179.55  4804.7  172.66  4821.3  178.16  4826.9  173.22  4871.3  173.25
  4900.5  184.04  4976.6  181.48  4982.2  178.64  4985.5  168.43  5023.2  168.43
  5024.2  170.43  5024.5  176.63  5035.8  180.55  5048.1  185.64  5187.9  186.02
    5238  172.21    5269  185.97  5305.6  186.46  6833.2  186.05  7356.5  200.61
  7399.2   202.7  7422.4  208.95  7451.5  202.71  7494.2   209.3  7584.8  208.78
#Mann= 7 ,-1 , 0
  1381.2     .17       0  2427.6     .15       0  2878.5     .11       0
  4826.9     .15       0  4976.6     .06       0  5035.8     .15       0
  5305.6     .11       0
Bank Sta=4976.6,5035.8
XS Rating Curve= 0 ,0
Exp/Cntr=0.3,0.1

Type RM Length L Ch R = 1 ,136112  ,2112,2112,2112
BEGIN DESCRIPTION:
LAKE CREEK 129.0
END DESCRIPTION:
XS GIS Cut Line= 3
      3753217.87     10106861.11      3751868.42     10103111.93
      3750266.88     10101158.84
#Sta/Elev= 30
   883.8  219.39  1277.1  214.63  1548.2  207.06  1696.4  201.37  1783.2  194.29
    1931  187.55  2209.9  185.55  4368.9  184.95  4471.1  183.69  4501.8  179.91
  4588.7  184.34    4594  181.89    4614  183.55  4619.4  180.48  4720.6   179.9
  4762.3  185.14  4805.6  186.19  4872.2  181.91    4891  176.44  4963.7  168.48
  4964.6  166.48  5002.4  166.48  5004.4  170.05  5018.7   171.4  5039.5  181.86
  5042.7  182.58  6717.4  185.98  6923.4  195.46    7115  209.03  7394.2  214.12
#Mann= 7 ,-1 , 0
   883.8     .17       0    1931     .15       0  2209.9     .11       0
  4368.9     .15       0  4872.2     .06       0  5039.5     .15       0
  5042.7     .11       0
Bank Sta=4872.2,5039.5
XS Rating Curve= 0 ,0
Exp/Cntr=0.3,0.1

Type RM Length L Ch R = 1 ,134000  ,2125,2125,2125
BEGIN DESCRIPTION:
LAKE CREEK 128.0
END DESCRIPTION:
XS GIS Cut Line= 3
      3756243.38     10103958.27      3752650.92     10102146.42
      3751568.92     10099999.91
#Sta/Elev= 30
   976.5  210.79  1252.5  205.64  1469.9  194.88    1955  197.29  2349.1  193.47
  2441.1  181.95  3820.8  183.54  4478.7  184.39  4558.8     184  4611.4  176.35
  4687.1  183.91  4768.2  182.86  4804.2  175.76  4843.2  183.34  4932.4  183.24
  4954.7  170.43    4980   165.5  5017.8   165.5  5018.8   167.5  5020.4  178.85
  5042.7  183.26  5095.6  178.99  5172.5  182.57  5618.9  189.64  6156.1  191.34
  6517.3  193.33  6715.5  195.44  6854.2   198.5  7078.8  201.55  7403.8  206.94
#Mann= 13 ,-1 , 0
   976.5     .17       0  2441.1     .15       0  3820.8     .11       0
  4478.7     .15       0  4932.4     .06       0  5042.7     .15       0
  5172.5     .11       0  5618.9     .17       0  6156.1     .11       0
  6517.3     .17       0  6715.5     .11       0  6854.2     .17       0
  7078.8     .11       0
Bank Sta=4932.4,5042.7
XS Rating Curve= 0 ,0
Exp/Cntr=0.3,0.1

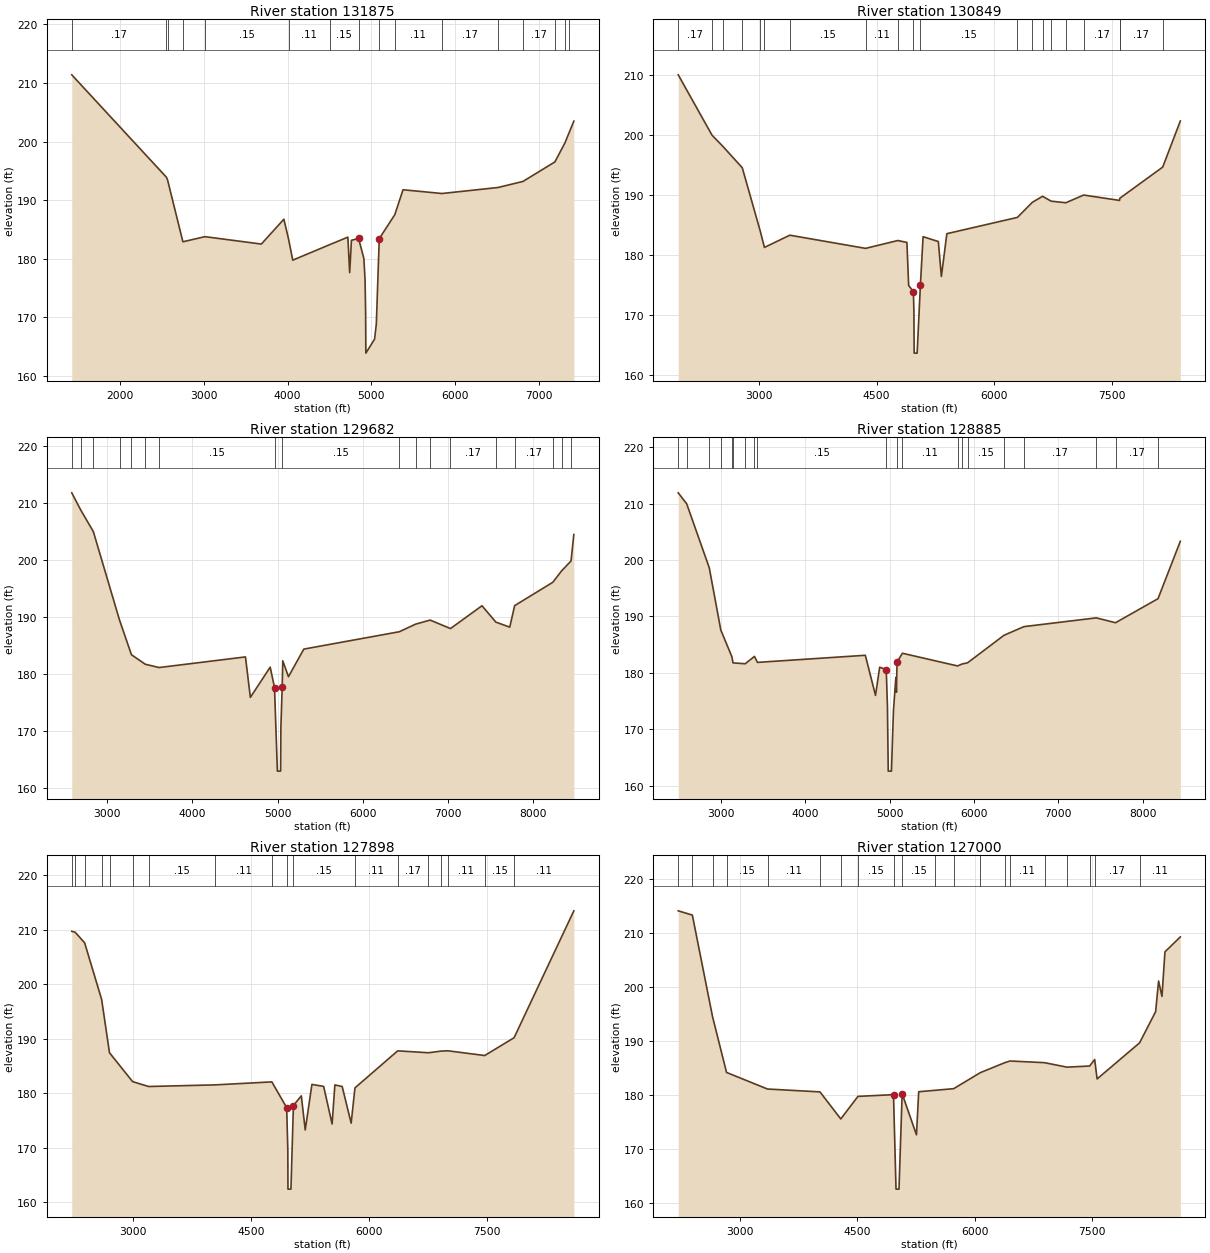
Type RM Length L Ch R = 1 ,131875  ,1026,1026,1026
BEGIN DESCRIPTION:
LAKE CREEK 127.0
END DESCRIPTION:
XS GIS Cut Line= 3
      3756282.47     10103945.25      3753456.96     10101393.18
      3751717.85     10100061.07
#Sta/Elev= 30
    1422  211.39  2553.2   193.9  2565.8  193.48  2749.7  182.89  3012.9  183.76
  3686.9   182.5  3955.9  186.74  4011.4  183.39    4062  179.75  4503.8   182.4
  4720.4  183.68  4742.1  177.63    4763  183.14  4848.2  183.46  4911.7  180.04
  4925.9  176.36  4932.6  170.82  4935.3  163.88  5039.5  166.26  5060.4  168.86
  5095.5  183.42  5281.1  187.51  5379.5  191.77  5844.3  191.13  6512.5  192.15
  6812.4  193.19  7193.6  196.52  7313.8  199.77  7363.8  201.52  7420.1  203.48
#Mann= 16 ,-1 , 0
    1422     .17       0  2553.2     .11       0  2565.8     .17       0
  2749.7     .11       0  3012.9     .15       0  4011.4     .11       0
  4503.8     .15       0  4848.2     .06       0  5095.5     .15       0
  5281.1     .11       0  5844.3     .17       0  6512.5     .11       0
  6812.4     .17       0  7193.6     .11       0  7313.8     .17       0
  7363.8     .11       0
Bank Sta=4848.2,5095.5
XS Rating Curve= 0 ,0
Exp/Cntr=0.3,0.1

Type RM Length L Ch R = 1 ,130849  ,1167,1167,1167
BEGIN DESCRIPTION:
LAKE CREEK 126.0
END DESCRIPTION:
XS GIS Cut Line= 4
      3756230.42     10103723.93      3754134.04     10101927.04
      3754433.52      10101341.1      3751803.29     10099960.88
#Sta/Elev= 30
  1975.4   210.1  2405.9  200.02  2541.8  198.19  2790.4  194.59    3018  184.08
  3072.5   181.3  3395.4  183.34  4359.9  181.14  4769.7  182.45  4885.6  182.13
  4907.8  174.96  4967.8  173.91  4974.5   170.7  4977.8  163.66  5015.7  163.66
  5057.6   175.1  5091.3  183.09  5285.5  182.28  5324.3  176.46  5393.8  183.59
    6292  186.31  6481.3  188.82  6611.7  189.83  6720.9  189.02  6907.1  188.75
  7135.5  190.04  7592.3  189.14  7594.6   189.5  8140.7   194.7  8364.9  202.39
#Mann= 20 ,-1 , 0
  1975.4     .17       0  2405.9     .11       0  2541.8     .17       0
  2790.4     .11       0    3018     .17       0  3072.5     .11       0
  3395.4     .15       0  4359.9     .11       0  4769.7     .15       0
  4967.8     .06       0  5057.6     .15       0    6292     .11       0
  6481.3     .17       0  6611.7     .11       0  6720.9     .17       0
  6907.1     .11       0  7135.5     .17       0  7592.3     .11       0
  7594.6     .17       0  8140.7     .11       0
Bank Sta=4967.8,5057.6
XS Rating Curve= 0 ,0
Exp/Cntr=0.3,0.1

Type RM Length L Ch R = 1 ,129682  ,797,797,797
BEGIN DESCRIPTION:
LAKE CREEK 125.0
END DESCRIPTION:
XS GIS Cut Line= 4
      3756567.88      10103261.1      3754850.19     10101848.91
      3754602.79      10101341.1      3751882.11     10099844.07
#Sta/Elev= 30
  2584.8   211.8  2690.2  208.78  2838.3  204.98  3145.4  189.44  3285.4  183.35
  3447.8  181.68  3610.2   181.1  4623.9  182.97  4681.3  175.86  4914.2  181.17
  4964.8  177.59  4998.5   162.9  5036.4   162.9  5039.7  170.66    5055  177.67
  5061.9  182.28  5128.7  179.49  5308.5  184.34  6429.4  187.39  6622.2  188.73
  6791.6  189.44  7030.7  187.95  7400.4  191.96  7563.4  189.08  7726.2   188.2
    7784  191.98  8231.7  196.08  8335.3  198.09  8445.6  199.83  8478.7  204.47
#Mann= 18 ,-1 , 0
  2584.8     .17       0  2690.2     .11       0  2838.3     .17       0
  3145.4     .11       0  3285.4     .15       0  3447.8     .11       0
  3610.2     .15       0  4964.8     .06       0    5055     .15       0
  6429.4     .11       0  6622.2     .17       0  6791.6     .11       0
  7030.7     .17       0  7563.4     .11       0    7784     .17       0
  8231.7     .11       0  8335.3     .17       0  8445.6     .11       0
Bank Sta=4964.8,5055
XS Rating Curve= 0 ,0
Exp/Cntr=0.3,0.1

Type RM Length L Ch R = 1 ,128885  ,987,987,987
BEGIN DESCRIPTION:
LAKE CREEK 124.0
END DESCRIPTION:
XS GIS Cut Line= 3
      3756667.86     10103111.09      3754902.27     10101054.64
      3751946.52     10099713.48
#Sta/Elev= 30
  2490.3   211.9  2590.5  209.96  2858.6  198.61  2995.2  187.59  3126.7  182.86
  3140.2  181.76  3285.1  181.61  3394.7  182.91  3430.1  181.85  4709.9  183.11
  4830.6     176    4880     181  4957.9  180.58  4972.2  174.07  4981.7  162.58
  5019.6  162.58  5043.5   173.3    5072  179.19  5078.6  176.56  5086.3  181.92
  5149.7  183.47  5804.2  181.22  5857.5  181.56  5923.1  181.78  6355.4  186.66
  6592.2  188.19  7449.5  189.74    7678  188.88    8182  193.14  8446.5  203.31
#Mann= 20 ,-1 , 0
  2490.3     .11       0  2590.5     .17       0  2858.6     .11       0
  2995.2     .11       0  3126.7     .15       0  3140.2     .11       0
  3285.1     .15       0  3394.7     .11       0  3430.1     .15       0
  4957.9     .06       0  5086.3     .15       0  5149.7     .11       0
  5804.2     .15       0  5857.5     .11       0  5923.1     .15       0
  6355.4     .11       0  6592.2     .17       0  7449.5     .11       0
    7678     .17       0    8182     .11       0
Bank Sta=4957.9,5086.3
XS Rating Curve= 0 ,0
Exp/Cntr=0.3,0.1

Type RM Length L Ch R = 1 ,127898  ,898,898,898
BEGIN DESCRIPTION:
LAKE CREEK 123.0
END DESCRIPTION:
XS GIS Cut Line= 3
      3756803.31     10102981.72       3755605.4     10100611.93
      3752675.71     10098307.25
#Sta/Elev= 30
    2222  209.72  2264.6  209.57  2385.7  207.61  2601.7  197.22  2701.7  187.42
  2995.4  182.12  3198.6  181.22  4047.6  181.52  4765.7  182.07  4954.2  177.33
  4968.7   169.6  4970.5  162.37  5008.4  162.37  5039.6  177.73  5140.3   179.5
    5190  173.24    5275   181.6  5424.1  181.24  5531.6  174.34  5566.9  181.51
  5659.9  181.22  5773.8  174.49  5822.2  180.97  6365.7  187.77  6756.6  187.42
  6921.9  187.73  7003.2  187.78  7471.8  186.91  7845.3  190.18  8604.9  213.49
#Mann= 18 ,-1 , 0
    2222     .11       0  2264.6     .17       0  2385.7     .11       0
  2601.7     .17       0  2701.7     .15       0  2995.4     .11       0
  3198.6     .15       0  4047.6     .11       0  4765.7     .15       0
  4954.2     .06       0  5039.6     .15       0  5822.2     .11       0
  6365.7     .17       0  6756.6     .15       0  6921.9     .17       0
  7003.2     .11       0  7471.8     .15       0  7845.3     .11       0
Bank Sta=4954.2,5039.6
XS Rating Curve= 0 ,0
Exp/Cntr=0.3,0.1

Type RM Length L Ch R = 1 ,127000  ,812,812,812
BEGIN DESCRIPTION:
LAKE CREEK 122.0
END DESCRIPTION:
XS GIS Cut Line= 3
      3757831.94     10102239.51      3756161.04     10100004.07
      3752988.23     10098242.15
#Sta/Elev= 30
  2209.1  214.09  2389.6   213.3  2647.4  194.52  2826.9  184.17  3350.6   181.1
  4021.7  180.57  4287.6  175.56  4507.2  179.74  4961.8  180.06    4994  162.57
  5031.9  162.57  5072.3  180.23  5255.3  172.63  5284.1   180.6  5490.7  180.86
  5731.9  181.17  6071.3  184.13  6381.6  185.96  6451.1  186.29    6893  185.98
  7180.4  185.15  7469.8  185.36  7534.2  186.57  7565.4  182.97  8108.4  189.65
  8313.6  195.42  8351.4   201.1  8394.8  198.25  8432.6  206.49  8629.2  209.26
#Mann= 20 ,-1 , 0
  2209.1     .17       0  2389.6     .11       0  2647.4     .17       0
  2826.9     .15       0  3350.6     .11       0  4021.7     .15       0
  4287.6     .11       0  4507.2     .15       0  4961.8     .06       0
  5072.3     .15       0  5490.7     .11       0  5731.9     .15       0
  6071.3     .11       0  6381.6     .17       0  6451.1     .11       0
    6893     .15       0  7180.4     .11       0  7469.8     .11       0
  7534.2     .17       0  8108.4     .11       0
Bank Sta=4961.8,5072.3
XS Rating Curve= 0 ,0
Exp/Cntr=0.3,0.1

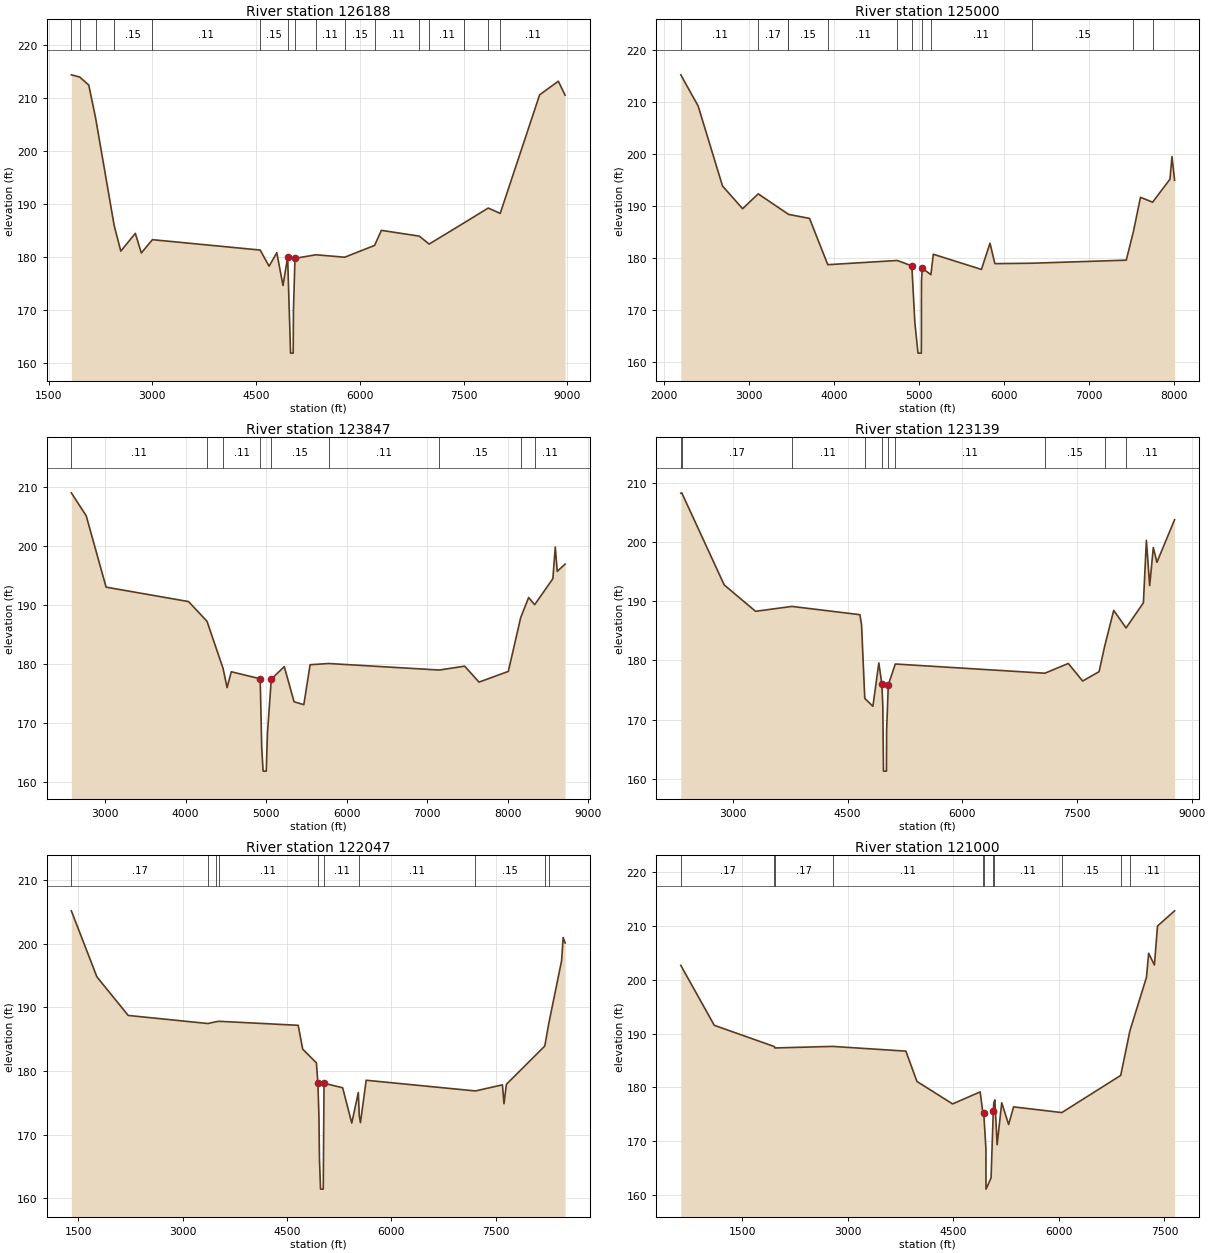
Type RM Length L Ch R = 1 ,126188  ,1188,1188,1188
BEGIN DESCRIPTION:
LAKE CREEK 121.0
END DESCRIPTION:
XS GIS Cut Line= 5
      3757897.07     10102200.49      3757063.73     10100898.39
      3756816.33      10099778.6      3756087.17     10099414.02
      3752819.57     10097825.78
#Sta/Elev= 30
  1828.4  214.38  1948.7  213.97  2080.2  212.45  2178.4  206.29  2447.6  185.95
  2543.6  181.11  2753.8  184.46  2840.4  180.76  3000.6  183.27  4559.2  181.31
    4688  178.27  4799.8   180.8  4889.3  174.62  4956.3  179.98  4998.7  161.86
  5036.9  161.86  5040.2  169.83  5062.6  179.75  5366.2  180.42  5781.9  179.96
  6214.4  182.19  6311.9  185.03  6860.5  183.94  7002.9  182.44  7506.6  186.43
  7857.5  189.24  8030.8  188.23  8600.9  210.61  8871.3  213.17  8969.5  210.54
#Mann= 16 ,-1 , 0
  1828.4     .17       0  1948.7     .11       0  2178.4     .17       0
  2447.6     .15       0  3000.6     .11       0  4559.2     .15       0
  4956.3     .06       0  5062.6     .15       0  5366.2     .11       0
  5781.9     .15       0  6214.4     .11       0  6860.5     .15       0
  7002.9     .11       0  7506.6     .17       0  7857.5     .15       0
  8030.8     .11       0
Bank Sta=4956.3,5062.6
XS Rating Curve= 0 ,0
Exp/Cntr=0.3,0.1

Type RM Length L Ch R = 1 ,125000  ,1153,1153,1153
BEGIN DESCRIPTION:
LAKE CREEK 120.0
END DESCRIPTION:
XS GIS Cut Line= 3
      3759068.93     10100195.26       3756798.2     10098548.17
      3754252.01     10096953.57
#Sta/Elev= 30
  2194.8  215.25  2398.9  209.24  2685.7  193.84  2922.3  189.47  3105.7  192.33
  3459.9  188.41  3461.4  188.38  3709.3   187.6  3924.3  178.69  4741.9   179.5
  4913.1  178.46  4948.7  167.53  4985.7  161.66  5024.5  161.66  5025.5  163.66
  5026.3  175.52  5035.8  178.01  5137.4  176.77  5165.6   180.7    5732  177.78
  5832.6  182.82  5890.4  178.89  6323.5  178.97  7435.7  179.56    7520  185.06
    7603  191.66    7746  190.72  7950.2  195.16  7973.8  199.51  8004.3  194.96
#Mann= 12 ,-1 , 0
  2194.8     .11       0  3105.7     .17       0  3459.9     .11       0
  3461.4     .15       0  3924.3     .11       0  4741.9     .15       0
  4913.1     .06       0  5035.8     .15       0  5137.4     .11       0
  6323.5     .15       0    7520     .17       0    7746     .11       0
Bank Sta=4913.1,5035.8
XS Rating Curve= 0 ,0
Exp/Cntr=0.3,0.1

Type RM Length L Ch R = 1 ,123847  ,708,708,708
BEGIN DESCRIPTION:
LAKE CREEK 119.0
END DESCRIPTION:
XS GIS Cut Line= 4
      3759199.15      10099843.7      3757350.19     10098697.87
        3757233.     10097994.75      3754212.49     10096809.98
#Sta/Elev= 30
  2580.3  209.05  2764.9  205.15  3011.8  193.03  4036.1  190.58  4265.4  187.22
  4464.3  179.24  4514.6  175.96  4566.6  178.66  4925.7  177.46  4944.9  165.66
  4962.1  161.78  5000.9  161.78  5015.9  168.25  5063.6177.4023  5224.8  179.53
  5346.5  173.56  5467.7  173.07  5545.3  179.85  5775.4  180.06  7149.9  178.95
  7465.2  179.61  7643.7   176.9  8007.6  178.72  8160.8  187.85  8259.7  191.27
  8334.4  190.05  8560.7  194.47  8590.5  199.84  8614.9  195.71  8712.9  196.95
#Mann= 9 ,-1 , 0
  2580.3     .11       0  4265.4     .15       0  4464.3     .11       0
  4925.7     .06       0  5063.6     .15       0  5775.4     .11       0
  7149.9     .15       0  8160.8     .17       0  8334.4     .11       0
Bank Sta=4925.7,5063.6
XS Rating Curve= 0 ,0
Exp/Cntr=0.3,0.1

Type RM Length L Ch R = 1 ,123139  ,1092,1092,1092
BEGIN DESCRIPTION:
LAKE CREEK 118.0
END DESCRIPTION:
XS GIS Cut Line= 3
      3759498.63      10099713.5      3757623.63     10097851.52
      3754108.02     10096367.15
#Sta/Elev= 30
  2317.2  208.28  2329.6  208.35  2885.1  192.77  3295.3  188.31  3770.2  189.14
    4660  187.74  4681.2  186.07  4723.7  173.58  4829.7  172.25  4907.5  179.58
  4947.1176.0004  4959.7  172.26  4968.2  161.28  5007.1  161.28  5009.4  168.18
  5031.1  175.86  5122.8   179.4  7079.6  177.84  7385.7  179.49  7573.4  176.52
  7788.2   178.1  7861.5  182.41  7979.9  188.47  8141.4   185.5  8368.1  189.75
  8406.9  200.31  8450.3  192.66  8497.5  199.09  8544.9   196.6  8775.8   203.8
#Mann= 10 ,-1 , 0
  2317.2     .11       0  2329.6     .17       0  3770.2     .11       0
  4723.7     .15       0  4947.1     .06       0  5031.1     .15       0
  5122.8     .11       0  7079.6     .15       0  7861.5     .17       0
  8141.4     .11       0
Bank Sta=4947.1,5031.1
XS Rating Curve= 0 ,0
Exp/Cntr=0.3,0.1

Type RM Length L Ch R = 1 ,122047  ,1047,1047,1047
BEGIN DESCRIPTION:
LAKE CREEK 117.0
END DESCRIPTION:
XS GIS Cut Line= 4
      3759550.72     10099570.28      3757519.46     10096783.81
      3757102.79     10097447.87      3754512.23     10096237.21
#Sta/Elev= 30
  1402.6  205.18  1769.6  194.81  2219.2  188.75  3362.7  187.48  3481.9  187.76
  3521.8  187.83  4660.4   187.2  4725.3  183.46    4922   181.3  4943.3  178.19
  4958.6   172.9  4965.7  166.29  4981.6  161.47  5020.5  161.47  5031.6   178.1
  5299.1  177.39  5429.9  171.84  5524.1  176.65    5538  173.01  5554.7  171.91
  5636.9  178.57  7205.3  176.89    7594  177.85  7616.1  174.88  7650.7  177.93
  8202.3  183.95  8258.6  187.43  8443.9  197.36    8466  200.99  8494.3  200.13
#Mann= 10 ,-1 , 0
  1402.6     .17       0  3362.7     .11       0  3481.9     .17       0
  3521.8     .11       0  4943.3     .06       0  5031.6     .11       0
    5538     .11       0  7205.3     .15       0  8202.3     .17       0
  8258.6     .11       0
Bank Sta=4943.3,5031.6
XS Rating Curve= 0 ,0
Exp/Cntr=0.3,0.1

Type RM Length L Ch R = 1 ,121000  ,1172,1172,1172
BEGIN DESCRIPTION:
LAKE CREEK 116.0
END DESCRIPTION:
XS GIS Cut Line= 4
      3759537.67     10099492.12      3757514.14     10096580.29
      3756712.48     10096781.37       3754186.1     10096002.55
#Sta/Elev= 30
   627.6  202.68  1103.4  191.54  1958.7  187.58  1962.7  187.33  2783.1  187.62
  3825.4  186.74  3983.4   181.1  4489.7  176.93  4881.1  179.16  4923.3  174.97
  4932.3  175.18  4963.5  168.54  4963.7  163.09  4964.7  161.09  5036.2  163.16
  5067.6  175.61  5074.8   177.1  5089.8  177.67  5122.5  169.35  5187.8  177.15
  5285.8   173.1  5356.4  176.38  6041.5  175.32  6878.5  182.23  7009.5  190.54
  7244.2  200.45  7275.6  204.93  7357.1  202.75  7401.2  209.99  7643.7  212.82
#Mann= 11 ,-1 , 0
   627.6     .17       0  1958.7     .15       0  1962.7     .17       0
  2783.1     .11       0  4923.3     .15       0  4932.3     .06       0
  5067.6     .15       0  5074.8     .11       0  6041.5     .15       0
  6878.5     .17       0  7009.5     .11       0
Bank Sta=4932.3,5067.6
XS Rating Curve= 0 ,0
Exp/Cntr=0.3,0.1