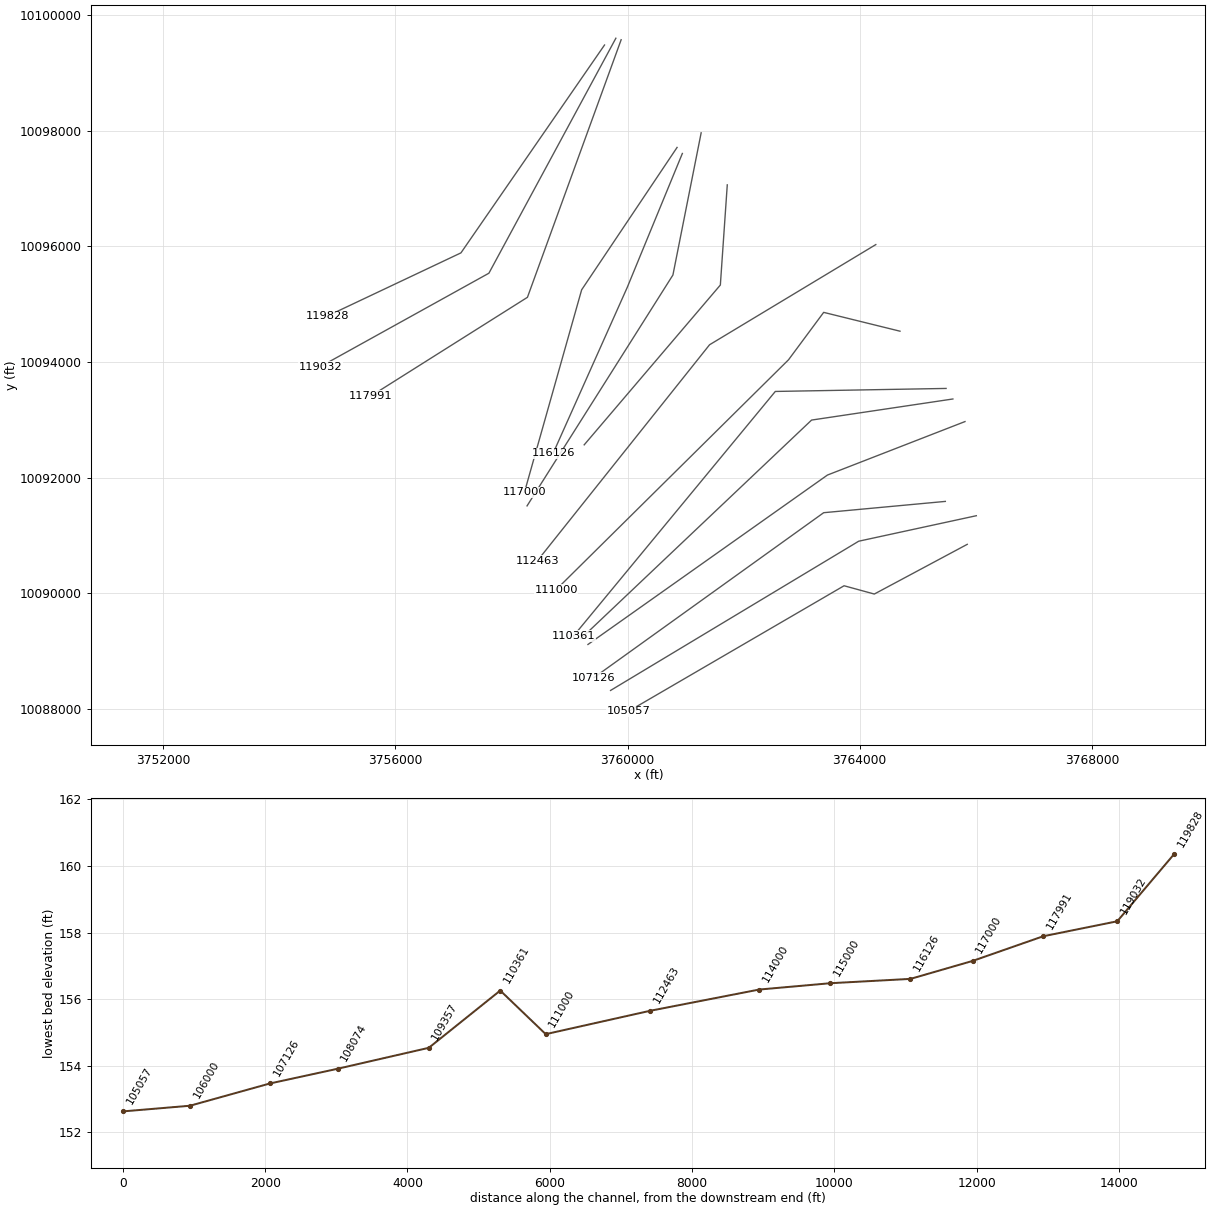
HEC-RAS study LAKE CREEK.prj: LAKE CREEK Base Level Engineering

--- LAKE CREEK.g01 (geometry) --- (continued)

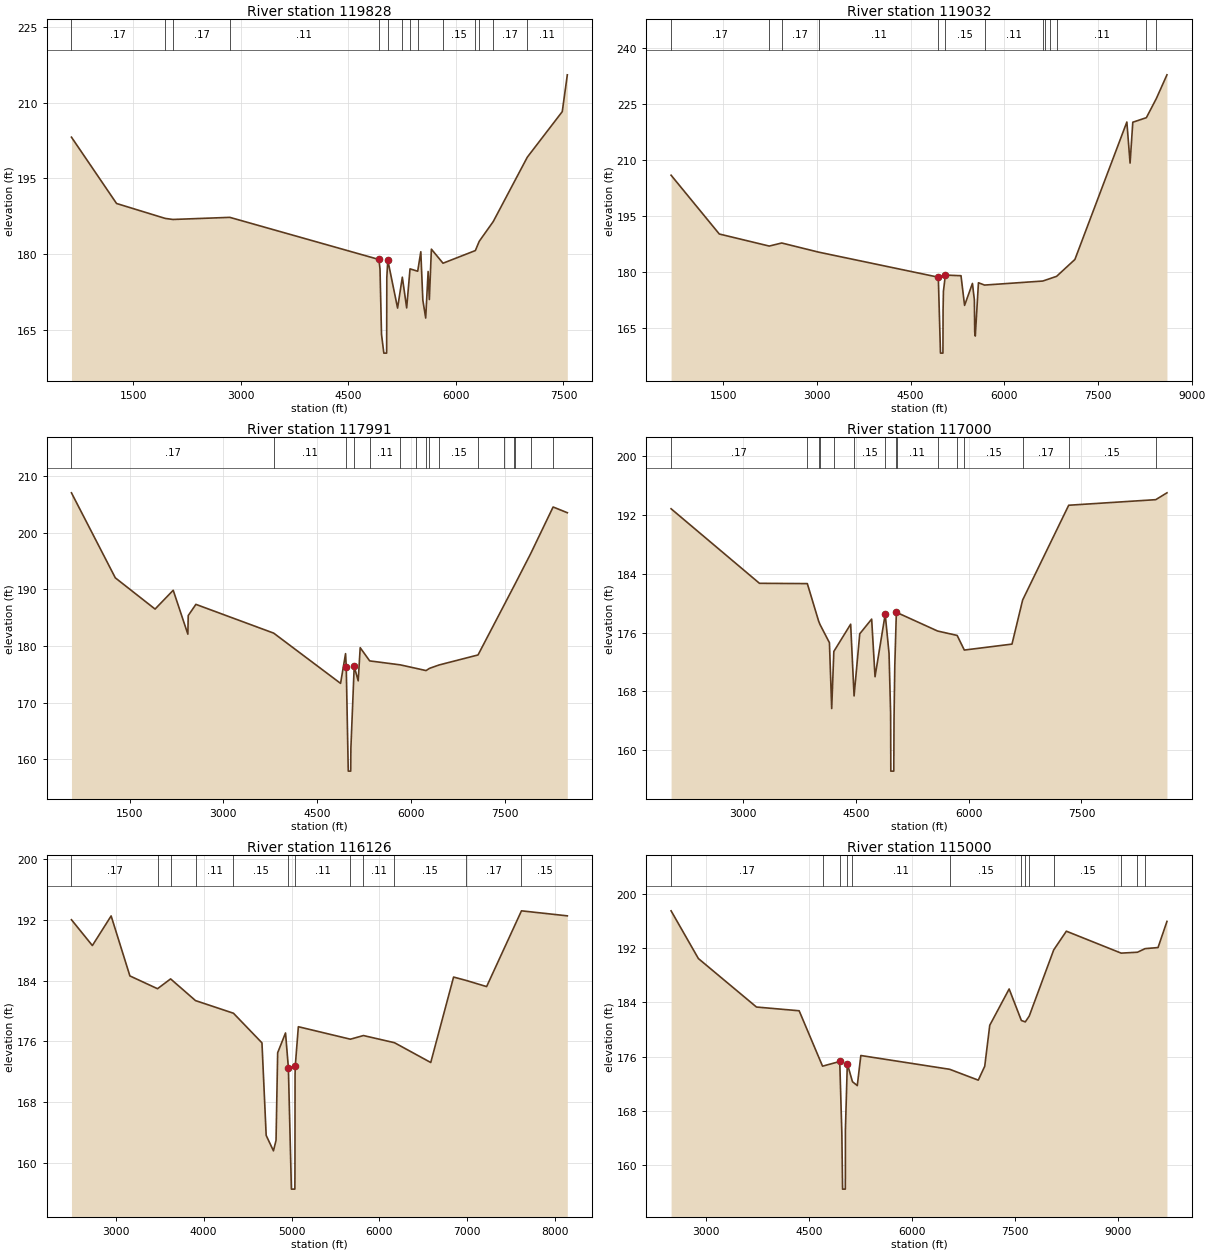
Type RM Length L Ch R = 1 ,119828  ,796,796,796
BEGIN DESCRIPTION:
LAKE CREEK 115.0
END DESCRIPTION:
XS GIS Cut Line= 3
       3759602.8     10099479.14      3757128.83     10095885.37
      3754824.19     10094791.64
#Sta/Elev= 30
   639.9   203.2  1268.7  190.04  1947.3  187.08  2055.1  186.87  2847.9  187.29
  4927.2  178.93  4942.1  177.04  4963.1  164.07  4995.6  160.35  5034.5  160.35
  5037.2  175.37  5050.8   178.8  5187.2  169.29  5253.3  175.42  5313.9  169.32
  5360.6  177.07  5467.8   176.6    5511  180.47  5539.3  170.88  5579.2  167.31
    5613  176.55  5630.2  170.99  5658.5  180.98  5820.7  178.19  6271.6   180.7
  6325.8  182.54  6521.2  186.46  6996.1  199.23  7483.4  208.27  7553.9  215.57
#Mann= 14 ,-1 , 0
   639.9     .17       0  1947.3     .15       0  2055.1     .17       0
  2847.9     .11       0  4927.2     .06       0  5050.8     .15       0
  5253.3     .11       0  5360.6     .15       0  5467.8     .11       0
  5820.7     .15       0  6271.6     .17       0  6325.8     .15       0
  6521.2     .17       0  6996.1     .11       0
Bank Sta=4927.2,5050.8
XS Rating Curve= 0 ,0
Exp/Cntr=0.3,0.1

Type RM Length L Ch R = 1 ,119032  ,1041,1041,1041
BEGIN DESCRIPTION:
LAKE CREEK 114.0
END DESCRIPTION:
XS GIS Cut Line= 3
      3759798.09     10099596.29      3757610.61     10095533.81
      3754706.99     10093919.24
#Sta/Elev= 30
   667.2     206  1438.7  190.25  2238.3  187.02  2437.8  187.84  3029.1  185.39
  4944.1  178.68  4978.8  158.34  5018.1  158.34  5020.4   169.7    5026  174.91
  5057.1  179.24  5307.2  179.08  5364.5  171.13  5490.3  177.01  5521.2  172.59
  5526.9  163.95  5536.1  162.91  5586.4  177.19  5684.7  176.57  6616.4  177.65
  6654.9  177.87  6726.9  178.28  6837.4  178.91  7130.3  183.43  7961.8  220.25
  8013.3  209.25  8056.7  220.19  8274.1  221.41  8433.7  226.54  8603.5  232.89
#Mann= 13 ,-1 , 0
   667.2     .17       0  2238.3     .15       0  2437.8     .17       0
  3029.1     .11       0  4944.1     .06       0  5057.1     .15       0
  5684.7     .11       0  6616.4     .17       0  6654.9     .11       0
  6726.9     .17       0  6837.4     .11       0  8274.1     .17       0
  8433.7     .11       0
Bank Sta=4944.1,5057.1
XS Rating Curve= 0 ,0
Exp/Cntr=0.3,0.1

Type RM Length L Ch R = 1 ,117991  ,991,991,991
BEGIN DESCRIPTION:
LAKE CREEK 113.0
END DESCRIPTION:
XS GIS Cut Line= 3
      3759889.25     10099570.25      3758274.67     10095117.14
      3755579.34      10093411.4
#Sta/Elev= 30
   571.1  207.02  1272.3  192.01  1907.6   186.5  2197.7  189.82  2431.7  182.07
  2437.6  185.35  2560.1  187.33  3803.9  182.25    4873  173.38  4952.7  178.63
 4963.74176.2444  4995.9  157.89  5035.2  157.89  5037.8  161.95    5091  176.39
  5154.8  173.83  5186.7  179.68  5338.4  177.35  5826.8  176.65  6073.5  176.05
  6239.8  175.64  6293.7  176.03  6447.6  176.63  7070.4   178.4  7492.1  187.32
  7643.6  190.53  7664.5  190.97  7909.9  196.24  8270.6  204.52  8497.6  203.51
#Mann= 16 ,-1 , 0
   571.1     .17       0  3803.9     .11       0 4963.74     .06       0
    5091     .15       0  5338.4     .11       0  5826.8     .15       0
  6073.5     .11       0  6239.8     .15       0  6293.7     .11       0
  6447.6     .15       0  7070.4     .11       0  7492.1     .17       0
  7643.6     .15       0  7664.5     .17       0  7909.9     .15       0
  8270.6     .11       0
Bank Sta=4963.74,5091
XS Rating Curve= 0 ,0
Exp/Cntr=0.3,0.1

Type RM Length L Ch R = 1 ,117000  ,874,874,874
BEGIN DESCRIPTION:
LAKE CREEK 112.0
END DESCRIPTION:
XS GIS Cut Line= 3
       3760852.8      10097708.3      3759208.61     10095246.83
       3758222.9     10091745.85
#Sta/Elev= 30
  2039.9  192.84  3215.6   182.7  3852.5  182.66  4001.6   177.6  4020.4  177.11
  4146.6  174.62  4176.7  165.66  4205.1  173.43    4429  177.14  4474.4  167.38
  4549.9  175.83  4708.3  177.83  4753.3  169.99  4888.5  178.49  4939.6  173.17
  4960.6  165.02  4963.2  157.15  5002.6  157.15    5006  164.21  5016.2  171.48
  5037.2  178.86  5049.5   178.7  5585.2  176.21  5845.9  175.61  5941.2  173.62
  6575.4  174.43  6717.2  180.43  7329.9  193.32  8488.1  194.08  8637.1  195.01
#Mann= 15 ,-1 , 0
  2039.9     .17       0  3852.5     .11       0  4001.6     .17       0
  4020.4     .15       0  4205.1     .11       0  4474.4     .15       0
  4888.5     .06       0  5037.2     .15       0  5049.5     .11       0
  5585.2     .15       0  5845.9     .11       0  5941.2     .15       0
  6717.2     .17       0  7329.9     .15       0  8488.1     .17       0
Bank Sta=4888.5,5037.2
XS Rating Curve= 0 ,0
Exp/Cntr=0.3,0.1

Type RM Length L Ch R = 1 ,116126  ,1126,1126,1126
BEGIN DESCRIPTION:
LAKE CREEK 111.0
END DESCRIPTION:
XS GIS Cut Line= 3
      3760943.94     10097604.13      3759993.42     10095286.41
      3758717.37     10092421.82
#Sta/Elev= 30
  2496.2  191.99  2734.1   188.6  2947.6  192.49  3161.1  184.61  3475.3  182.93
  3624.2  184.22  3907.3  181.37  4339.2  179.71  4663.4  175.82  4711.3  163.67
  4794.1  161.64  4823.5  163.02  4842.1  174.52  4931.4  177.12  4963.8  172.58
  4998.3  156.61  5037.7  156.61  5038.7  158.61  5039.9  171.58  5042.2  172.75
  5077.3  177.94  5669.4   176.3  5817.8  176.78    6171  175.84  6583.5  173.24
  6843.3  184.46  6985.9  184.02  7219.2  183.21  7615.6  193.16  8137.2   192.5
#Mann= 12 ,-1 , 0
  2496.2     .17       0  3475.3     .11       0  3624.2     .17       0
  3907.3     .11       0  4339.2     .15       0  4963.8     .06       0
  5042.2     .11       0  5669.4     .15       0  5817.8     .11       0
    6171     .15       0  6985.9     .17       0  7615.6     .15       0
Bank Sta=4963.8,5042.2
XS Rating Curve= 0 ,0
Exp/Cntr=0.3,0.1

Type RM Length L Ch R = 1 ,115000  ,1000,1000,1000
BEGIN DESCRIPTION:
LAKE CREEK 110.0
END DESCRIPTION:
XS GIS Cut Line= 3
      3761267.86      10097961.1      3760781.25     10095502.59
      3758267.87     10091511.09
#Sta/Elev= 30
  2493.8  197.47  2891.4  190.44  3737.5   183.3  4359.3  182.75    4700  174.59
  4950.6  175.28  4981.2  164.72  4991.9  156.48  5031.5  156.48  5032.6  158.48
  5032.9  165.17  5060.9  174.94    5136   172.3    5206  171.73  5257.8  176.16
    6552  174.13  6968.5  172.53  7062.7  174.58  7135.6  180.61  7418.2  185.96
  7596.2  181.32  7653.4  181.11  7710.4  181.96  8067.7  191.72  8251.6  194.47
  9049.6  191.24    9287  191.37  9398.2   191.9  9586.9  192.06  9716.9  195.91
#Mann= 13 ,-1 , 0
  2493.8     .17       0    4700     .15       0  4950.6     .06       0
  5060.9     .15       0    5136     .11       0    6552     .15       0
  7596.2     .17       0  7653.4     .15       0  7710.4     .17       0
  8067.7     .15       0  9049.6     .11       0    9287     .15       0
  9398.2     .17       0
Bank Sta=4950.6,5060.9
XS Rating Curve= 0 ,0
Exp/Cntr=0.3,0.1

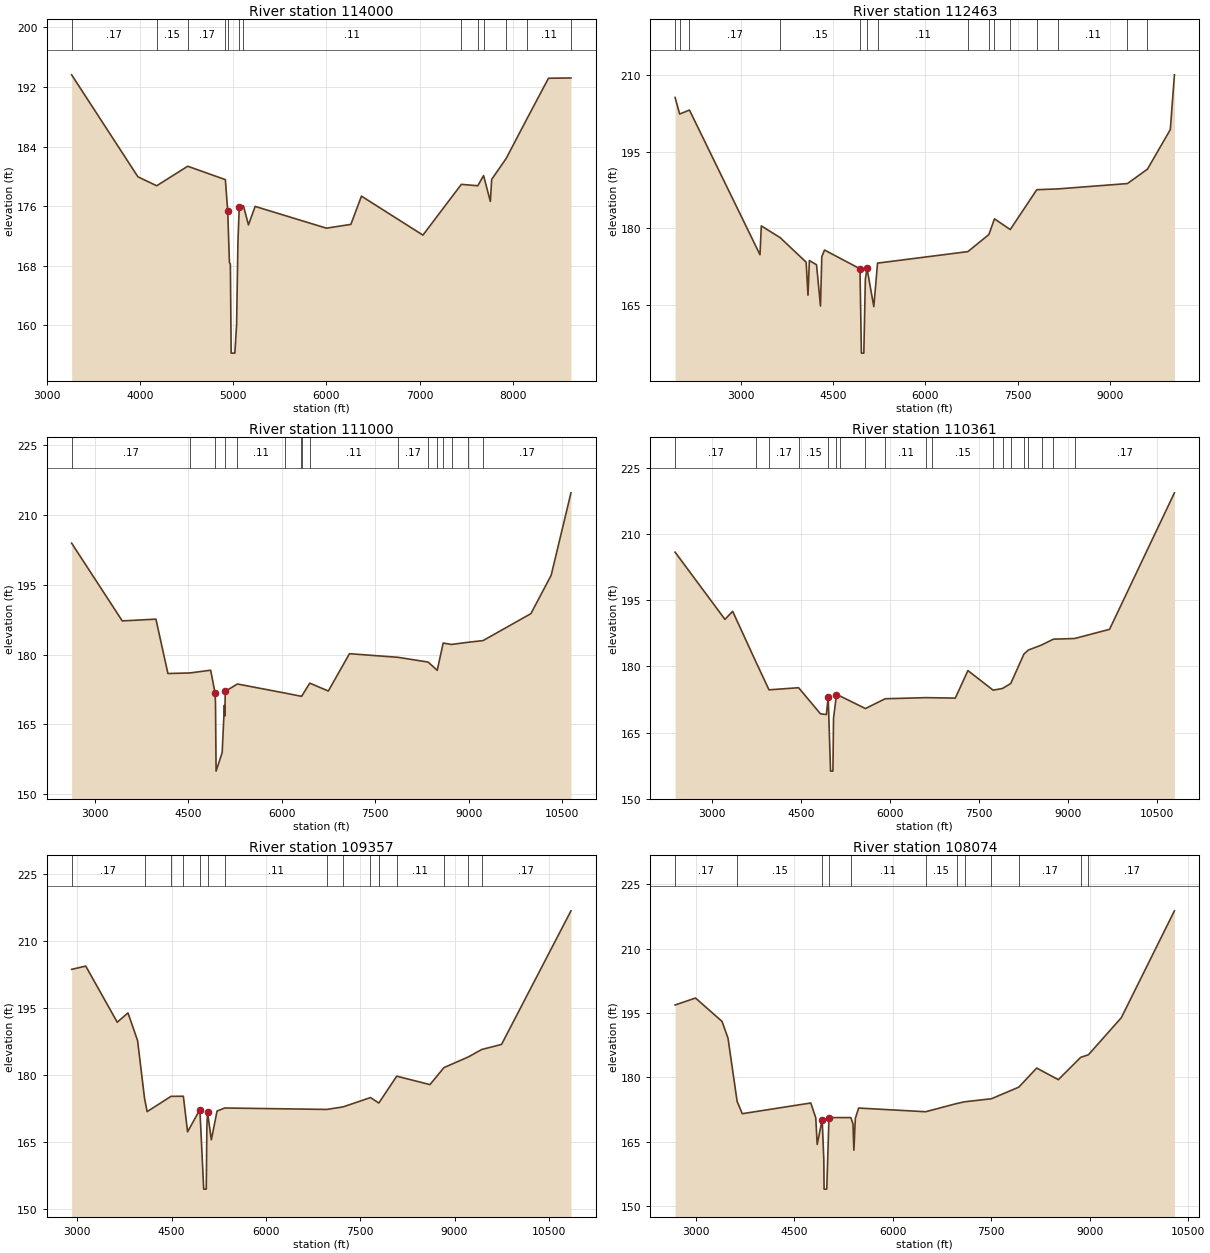
Type RM Length L Ch R = 1 ,114000  ,1537,1537,1537
BEGIN DESCRIPTION:
LAKE CREEK 109.0
END DESCRIPTION:
XS GIS Cut Line= 3
      3761717.85     10097061.07      3761598.49     10095329.38
      3759252.49     10092566.54
#Sta/Elev= 30
  3264.2  193.62  3975.9  179.94  4177.5  178.74  4510.5  181.36  4914.6  179.56
  4939.9  175.31  4958.2  168.44  4968.2  168.24  4976.8  156.29  5016.4  156.29
  5035.1  160.13  5049.4   171.2  5063.4  175.85  5108.9  176.04  5162.5  173.49
  5233.9  175.97  5999.4  173.05  6261.9  173.56  6375.3  177.35  7035.2  172.12
  7447.8  178.93  7624.2  178.74  7686.3  180.11    7759  176.64  7773.3   179.6
  7928.4  182.39  8157.7  187.86  8382.9  193.16  8622.8   193.2  8624.5   193.2
#Mann= 13 ,-1 , 0
  3264.2     .17       0  4177.5     .15       0  4510.5     .17       0
  4914.6     .15       0  4939.9     .06       0  5063.4     .15       0
  5108.9     .11       0  7447.8     .15       0  7624.2     .17       0
  7686.3     .15       0  7928.4     .17       0  8157.7     .11       0
  8622.8     .15       0
Bank Sta=4939.9,5063.4
XS Rating Curve= 0 ,0
Exp/Cntr=0.3,0.1

Type RM Length L Ch R = 1 ,112463  ,1463,1463,1463
BEGIN DESCRIPTION:
LAKE CREEK 107.0
END DESCRIPTION:
XS GIS Cut Line= 3
      3764277.23     10096028.58      3761412.69     10094296.83
      3758443.94     10090559.85
#Sta/Elev= 30
  1929.5  205.59  2003.9  202.35  2162.9  203.13  3310.1  174.87  3331.5   180.5
    3637  178.22    4061  173.41  4090.6  166.96  4113.3  173.74  4229.7  172.91
  4293.8  164.85  4315.1  174.48  4359.3  175.79 4936.31172.1271  4958.8  155.65
  4998.6  155.65  5023.3  170.12  5050.5  172.19    5161  164.74  5221.6  173.23
  6690.9  175.48  7032.4  178.82  7122.9  181.88  7379.9  179.79  7811.1  187.57
  8159.3  187.73    9285  188.77  9610.8  191.59  9982.3  199.31 10049.5  210.01
#Mann= 15 ,-1 , 0
  1929.5     .17       0  2003.9     .15       0  2162.9     .17       0
    3637     .15       0 4936.31     .06       0  5050.5     .15       0
  5221.6     .11       0  6690.9     .15       0  7032.4     .11       0
  7122.9     .17       0  7379.9     .15       0  7811.1     .17       0
  8159.3     .11       0    9285     .15       0  9610.8     .17       0
Bank Sta=4936.31,5050.5
XS Rating Curve= 0 ,0
Exp/Cntr=0.3,0.1

Type RM Length L Ch R = 1 ,111000  ,639,639,639
BEGIN DESCRIPTION:
LAKE CREEK 106.0
END DESCRIPTION:
XS GIS Cut Line= 4
      3764693.97     10094531.19      3763378.83     10094856.72
      3762773.17     10094037.04      3758767.82     10090061.04
#Sta/Elev= 30
    2626  203.95    3439  187.24  3979.5  187.62  4172.1  175.93  4521.2  176.05
  4858.2  176.64  4929.9  171.68  4936.1  169.54  4945.5  154.95  5043.3  158.95
  5078.7  169.12  5085.8  166.81  5092.8  172.09  5287.3  173.68  6047.9  171.74
  6315.7  171.03  6317.8  171.02  6449.6  173.86  6747.5  172.17  7086.9  180.19
  7868.3  179.41  8350.8  178.39    8496  176.62  8591.9  182.48  8725.7  182.18
  8993.5  182.65  9232.7  183.01 10000.2   188.8 10325.5  197.04 10643.7  214.77
#Mann= 16 ,-1 , 0
    2626     .17       0  4521.2     .15       0  4929.9     .06       0
  5092.8     .15       0  5287.3     .11       0  6047.9     .15       0
  6315.7     .11       0  6317.8     .15       0  6449.6     .11       0
  7868.3     .17       0  8350.8     .11       0    8496     .17       0
  8591.9     .11       0  8725.7     .17       0  8993.5     .11       0
  9232.7     .17       0
Bank Sta=4929.9,5092.8
XS Rating Curve= 0 ,0
Exp/Cntr=0.3,0.1

Type RM Length L Ch R = 1 ,110361  ,1004,1004,1004
BEGIN DESCRIPTION:
LAKE CREEK 105.0
END DESCRIPTION:
XS GIS Cut Line= 3
      3765488.21     10093541.62       3762545.5     10093489.54
      3759067.86     10089261.08
#Sta/Elev= 30
  2379.6  205.88  3220.1  190.65  3350.1  192.47  3741.3  181.04  3963.1  174.68
  4461.9  175.16  4830.3  169.25  4930.4  169.08  4960.4  173.16  5000.3  156.26
  5040.4  156.26  5050.4  168.24  5100.4   173.6  5167.3  173.23  5588.2  170.44
    5921  172.66  6608.5  172.91  6706.7  172.89  7103.5  172.81  7315.9  179.04
  7741.9   174.6  7899.3  174.99  8038.6  176.12  8260.7   182.8  8335.4   183.7
  8556.8  184.83  8757.1  186.16  9114.6  186.31  9703.5  188.39 10797.6  219.32
#Mann= 19 ,-1 , 0
  2379.6     .17       0  3741.3     .15       0  3963.1     .17       0
  4461.9     .15       0  4960.4     .06       0  5100.4     .15       0
  5167.3     .11       0  5588.2     .15       0    5921     .11       0
  6608.5     .11       0  6706.7     .15       0  7741.9     .11       0
  7899.3     .11       0  8038.6     .17       0  8260.7     .11       0
  8335.4     .17       0  8556.8     .17       0  8757.1     .11       0
  9114.6     .17       0
Bank Sta=4960.4,5100.4
XS Rating Curve= 0 ,0
Exp/Cntr=0.3,0.1

Type RM Length L Ch R = 1 ,109357  ,1283,1283,1283
BEGIN DESCRIPTION:
LAKE CREEK 104.0
END DESCRIPTION:
XS GIS Cut Line= 3
      3765605.39     10093359.33       3763170.5     10092994.75
      3759199.16     10089218.71
#Sta/Elev= 30
  2909.8  203.65  3134.6  204.38  3635.3  191.84  3805.9  193.92  3958.9  187.73
  4068.9  174.89  4110.6  171.86  4490.3  175.27  4686.5   175.3  4753.9  167.35
  4949.8  172.32  5010.4  154.54  5051.1  154.54  5061.1  168.65  5071.2  171.72
  5131.8  165.56  5222.8  171.99  5345.3  172.67  6968.9  172.35  7228.2  172.92
  7663.1     175  7794.4  173.79  7797.1  173.82  8080.6  179.78  8608.7   177.9
  8832.2   181.7  9219.8  184.08  9429.4  185.73  9747.7  186.88 10851.8  216.73
#Mann= 16 ,-1 , 0
  2909.8     .17       0  4068.9     .15       0  4490.3     .17       0
  4686.5     .15       0  4949.8     .06       0  5071.2     .15       0
  5345.3     .11       0  6968.9     .15       0  7228.2     .11       0
  7663.1     .17       0  7794.4     .15       0  7797.1     .17       0
  8080.6     .11       0  8832.2     .17       0  9219.8     .11       0
  9429.4     .17       0
Bank Sta=4949.8,5071.2
XS Rating Curve= 0 ,0
Exp/Cntr=0.3,0.1

Type RM Length L Ch R = 1 ,108074  ,948,948,948
BEGIN DESCRIPTION:
LAKE CREEK 103.0
END DESCRIPTION:
XS GIS Cut Line= 3
      3765813.76     10092968.72      3763443.94     10092044.22
       3759317.4     10089115.29
#Sta/Elev= 30
  2686.3  196.88  2997.4   198.5  3401.1  193.05  3491.9  189.15  3631.1  174.37
  3709.3  171.51  4752.7  174.01  4828.7  170.54  4850.2  164.35  4926.5  170.14
    4951  160.77  4955.1  153.91  4995.8  153.91  5029.8  170.61  5362.3   170.6
  5395.2  169.17  5409.2     163  5430.9   170.4  5481.3  172.83  6501.6  171.97
  6976.1  173.89  7096.4  174.29  7503.6     175  7920.7  177.71  8192.6  182.16
  8522.3  179.45  8862.8  184.66  8980.5  185.26  9481.8  193.92 10290.4  218.85
#Mann= 12 ,-1 , 0
  2686.3     .17       0  3631.1     .15       0  4926.5     .06       0
  5029.8     .15       0  5362.3     .11       0  6501.6     .15       0
  6976.1     .11       0  7096.4     .17       0  7503.6     .15       0
  7920.7     .17       0  8862.8     .11       0  8980.5     .17       0
Bank Sta=4926.5,5029.8
XS Rating Curve= 0 ,0
Exp/Cntr=0.3,0.1

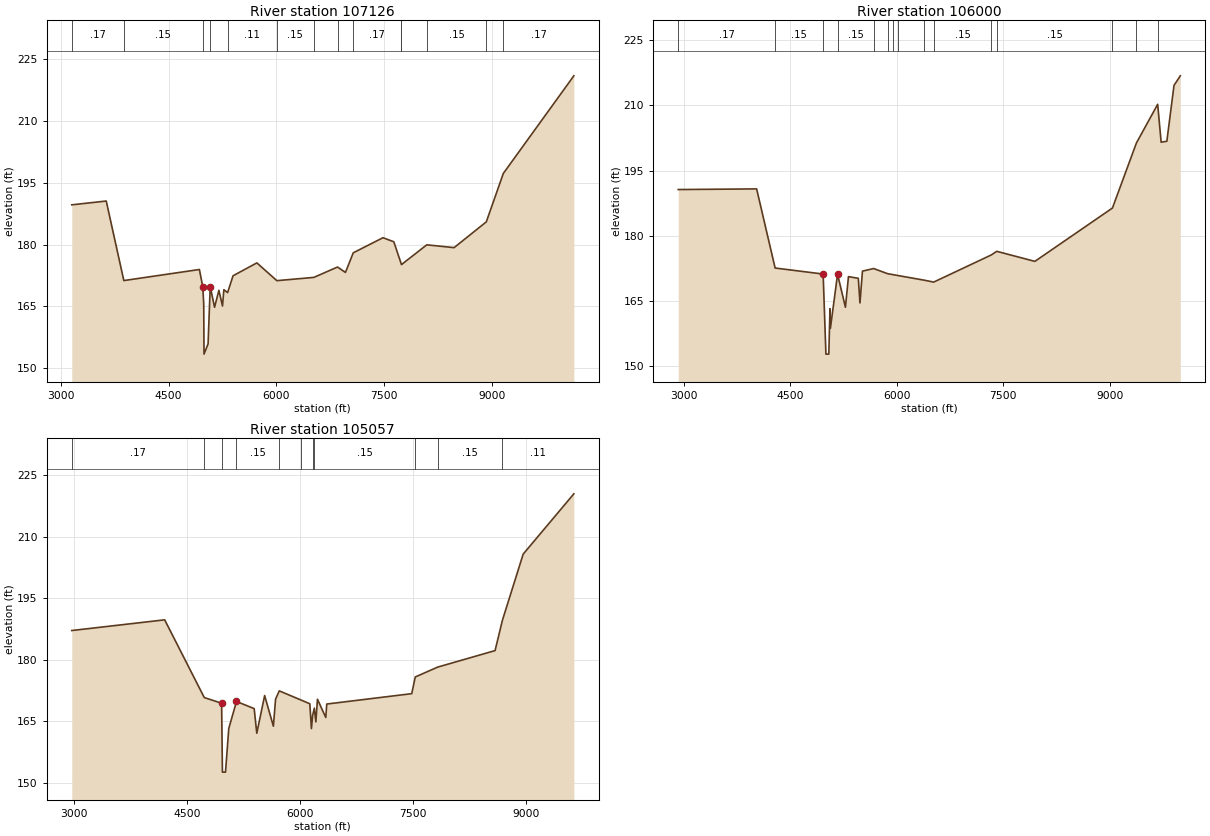
Type RM Length L Ch R = 1 ,107126  ,1126,1126,1126
BEGIN DESCRIPTION:
LAKE CREEK 102.0
END DESCRIPTION:
XS GIS Cut Line= 3
      3765475.17     10091588.49      3763378.83     10091393.18
      3759421.66     10088542.45
#Sta/Elev= 30
    3153   189.6  3632.4  190.52  3877.1  171.27    4928  173.95  4974.9169.7918
  4988.2  165.59  4992.2  153.47  5048.5  155.94  5078.6   169.8  5138.9  164.81
  5199.1  168.91  5249.4  165.12  5268.2  169.06  5320.3  168.36  5395.9  172.43
  5727.2  175.55  6005.2  171.25  6519.9  172.04  6849.3  174.55  6959.3  173.24
  7067.8  177.99  7480.9  181.64  7631.8  180.66    7734  175.37    7738  175.13
    8090  179.92    8470  179.24  8918.1  185.48  9154.8   197.2 10135.5  220.82
#Mann= 14 ,-1 , 0
    3153     .17       0  3877.1     .15       0  4974.9     .06       0
  5078.6     .15       0  5320.3     .11       0  6005.2     .15       0
  6519.9     .11       0  6849.3     .15       0  7067.8     .17       0
    7734     .15       0    7738     .17       0    8090     .15       0
  8918.1     .11       0  9154.8     .17       0
Bank Sta=4974.9,5078.6
XS Rating Curve= 0 ,0
Exp/Cntr=0.3,0.1

Type RM Length L Ch R = 1 ,106000  ,943,943,943
BEGIN DESCRIPTION:
LAKE CREEK 101.0
END DESCRIPTION:
XS GIS Cut Line= 3
      3766009.01     10091341.09       3763982.3     10090900.28
      3759706.96     10088320.27
#Sta/Elev= 30
  2925.9  190.63  4029.5  190.78  4289.8  172.59 4965.78171.2079  5004.8   152.8
  5045.5   152.8    5062  163.23  5067.8  158.73  5168.8  171.17  5279.4  163.57
  5322.1  170.61  5460.7  170.23  5484.1  164.56  5519.1  171.88  5676.6  172.47
  5873.2  171.29    5956  171.05  6013.6  170.88  6387.5   169.8  6522.1  169.36
  7330.7  175.58  7409.9  176.43  7946.3  174.12  9038.1  186.38  9375.9  201.34
  9674.9  210.22  9723.8  201.51  9803.9  201.73  9904.9  214.57  9993.5  216.77
#Mann= 15 ,-1 , 0
  2925.9     .17       0  4289.8     .15       0 4965.78     .06       0
  5168.8     .15       0  5676.6     .11       0  5873.2     .15       0
    5956     .11       0  6013.6     .15       0  6387.5     .11       0
  6522.1     .15       0  7330.7     .17       0  7409.9     .15       0
  9038.1     .11       0  9375.9     .17       0  9674.9     .11       0
Bank Sta=4965.78,5168.8
XS Rating Curve= 0 ,0
Exp/Cntr=0.3,0.1

Type RM Length L Ch R = 1 ,105057  ,1346,1346,1346
BEGIN DESCRIPTION:
LAKE CREEK 100.0
END DESCRIPTION:
XS GIS Cut Line= 4
      3765852.78      10090846.3      3764251.23     10089986.93
       3763730.4     10090130.16      3760017.83     10087961.06
#Sta/Elev= 30
  2974.6  187.15  4206.6  189.76  4731.6  170.81  4961.6  169.42  4972.3  152.63
  5013.1  152.63  5056.5  163.27  5158.6  169.85  5393.2  168.12  5427.9  162.11
  5532.1   171.3    5648  163.83  5677.2  170.43  5726.1  172.44  6008.9  170.25
    6131   169.3  6152.5  163.25    6168  166.42  6190.9  168.23  6211.2  164.88
  6232.6   170.4  6342.9  165.95  6355.8  169.23  7482.5  171.76  7529.6  175.83
  7825.9  178.23  8587.6  182.26  8685.2  189.66  8960.3  205.78  9632.1  220.48
#Mann= 11 ,-1 , 0
  2974.6     .17       0  4731.6     .15       0  4961.6     .06       0
  5158.6     .15       0  5726.1     .11       0  6008.9     .15       0
    6168     .11       0  6190.9     .15       0  7529.6     .17       0
  7825.9     .15       0  8685.2     .11       0
Bank Sta=4961.6,5158.6
XS Rating Curve= 0 ,0
Exp/Cntr=0.3,0.1