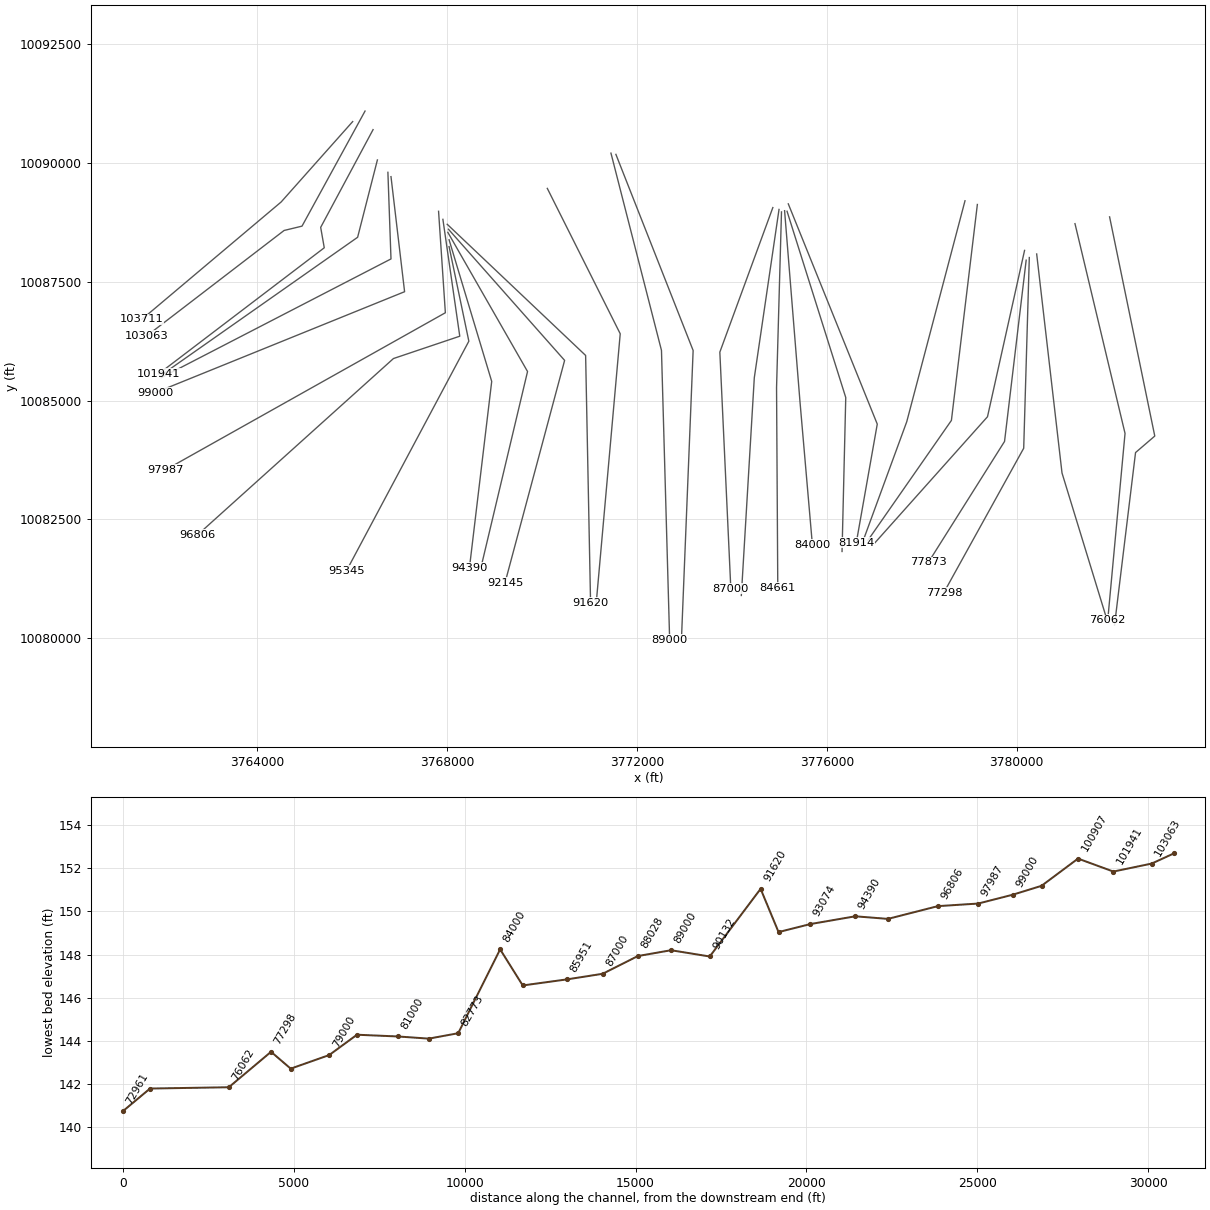
HEC-RAS study LAKE CREEK.prj: LAKE CREEK Base Level Engineering

--- LAKE CREEK.g01 (geometry) --- (continued)

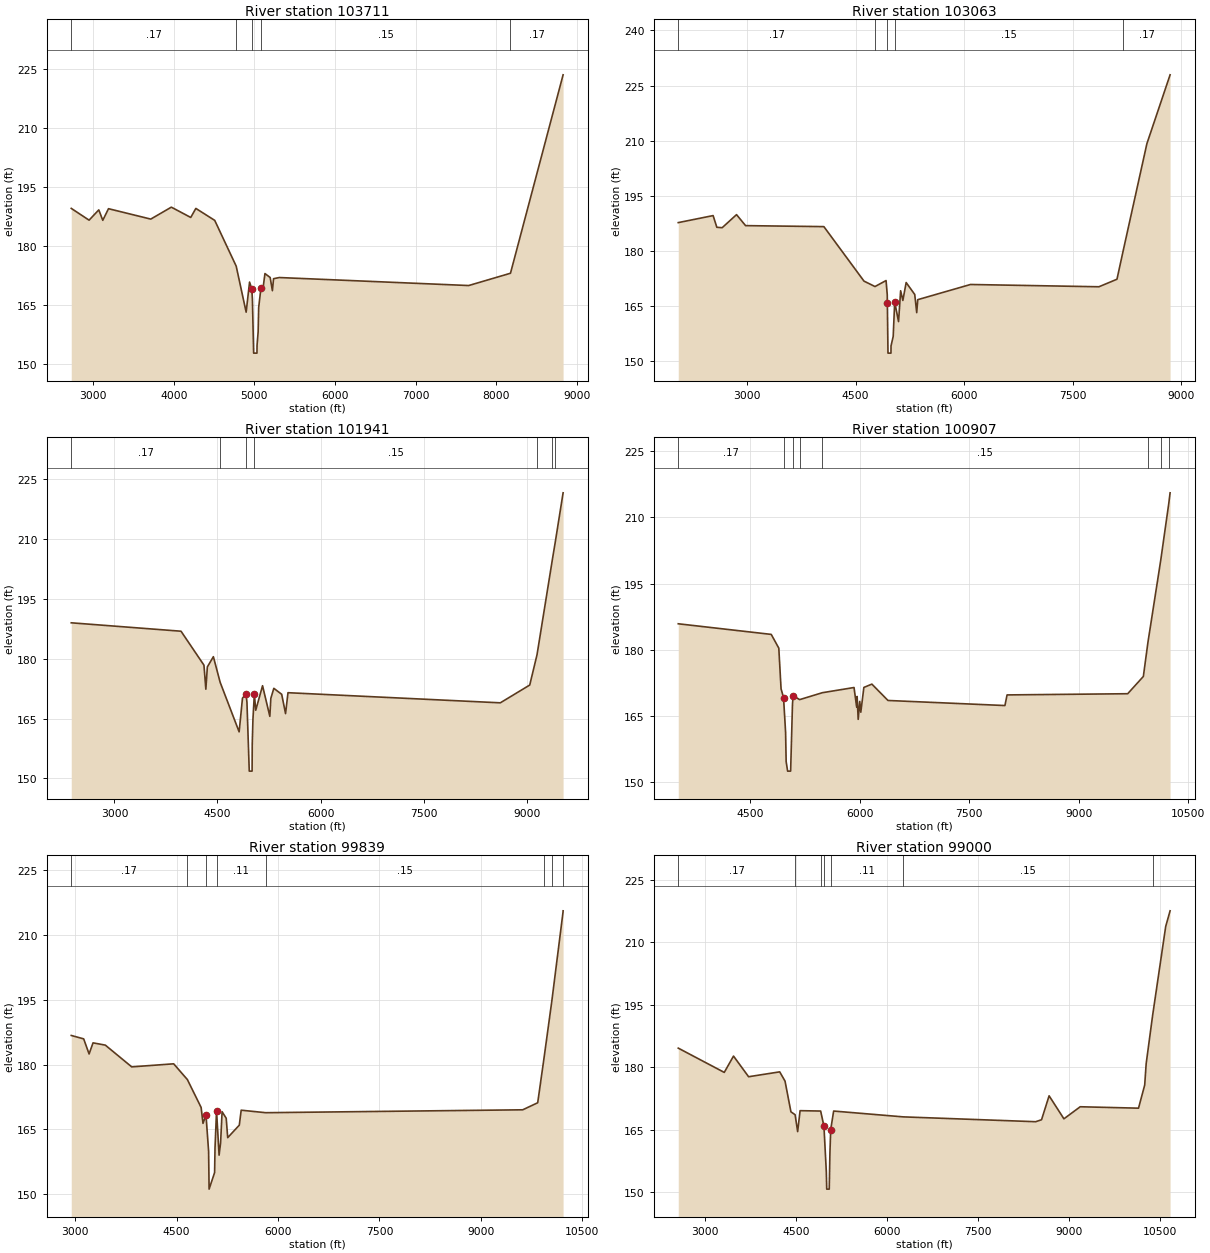
Type RM Length L Ch R = 1 ,103711  ,648,648,648
BEGIN DESCRIPTION:
LAKE CREEK 99.0
END DESCRIPTION:
XS GIS Cut Line= 3
      3766009.04     10090872.35       3764501.3     10089180.05
      3761567.86     10086711.08
#Sta/Elev= 30
  2729.2  189.54  2950.4  186.54  3070.8  189.16  3120.2   186.5  3191.2  189.46
  3715.5  186.81  3970.5  189.85  4211.3  187.23  4274.8  189.53  4508.9  186.48
  4775.2  174.82  4898.6  163.11  4940.8  170.77  4968.8  169.03  4976.3  166.28
  4991.5  152.68  5032.7  152.68  5033.7  154.68  5047.2  158.07  5053.8  164.26
  5082.4  169.33  5104.4  168.64  5131.8  172.94  5196.3  171.94  5224.1  168.58
  5238.4  171.63  5309.9  171.93  7658.8  169.89  8177.2  173.02  8829.9  223.55
#Mann= 5 ,-1 , 0
  2729.2     .17       0  4775.2     .15       0  4968.8     .06       0
  5082.4     .15       0  8177.2     .17       0
Bank Sta=4968.8,5082.4
XS Rating Curve= 0 ,0
Exp/Cntr=0.3,0.1

Type RM Length L Ch R = 1 ,103063  ,1122,1122,1122
BEGIN DESCRIPTION:
LAKE CREEK 98.0
END DESCRIPTION:
XS GIS Cut Line= 4
      3766269.47     10091093.72      3764941.33     10088671.83
      3764563.73     10088580.68      3761667.83     10086361.05
#Sta/Elev= 30
  2049.5  187.71  2531.5  189.62    2583  186.44    2657  186.33  2855.1  189.88
  2980.2  186.89  4062.6  186.62  4617.1   171.8  4769.3  170.32  4922.3  171.95
  4938.7  168.12 4940.26165.7619  4948.9  152.21  4990.1  152.21  4991.1  154.21
    5021  156.75  5041.6  166.11    5095  160.78  5123.8  169.18  5154.7  166.54
  5200.1  171.41  5318.7  168.17  5346.1  163.23  5360.3  166.75  6089.3  170.88
  7865.2  170.26  8114.5  172.31  8200.1  180.04  8527.9  209.17  8848.8  227.91
#Mann= 5 ,-1 , 0
  2049.5     .17       0  4769.3     .15       0 4940.26     .06       0
  5041.6     .15       0  8200.1     .17       0
Bank Sta=4940.26,5041.6
XS Rating Curve= 0 ,0
Exp/Cntr=0.3,0.1

Type RM Length L Ch R = 1 ,101941  ,1034,1034,1034
BEGIN DESCRIPTION:
LAKE CREEK 97.0
END DESCRIPTION:
XS GIS Cut Line= 4
      3766438.72     10090703.05      3765334.57     10088646.24
      3765410.08      10088216.1      3761917.82     10085561.05
#Sta/Elev= 30
  2371.7  189.04  3969.2  186.93  4302.9  178.42  4330.5  172.39  4352.4  177.97
  4440.1  180.54  4538.5  174.13  4814.9  161.69  4863.7  170.14  4914.4  171.23
  4928.6  169.13  4962.3  151.84  5003.5  151.84  5005.8   158.7    5016  164.89
  5036.3  171.15  5056.6  167.11  5155.7  173.26  5261.8  165.58  5276.3  170.09
    5320  172.61  5434.3  171.11  5490.5  166.26  5525.9  171.51  8615.9  168.97
  9044.2  173.43  9150.5  181.05    9375  205.04  9414.9  209.19  9529.8  221.64
#Mann= 7 ,-1 , 0
  2371.7     .17       0  4538.5     .15       0  4914.4     .06       0
  5036.3     .15       0  9150.5     .11       0    9375     .17       0
  9414.9     .11       0
Bank Sta=4914.4,5036.3
XS Rating Curve= 0 ,0
Exp/Cntr=0.3,0.1

Type RM Length L Ch R = 1 ,100907  ,1068,1068,1068
BEGIN DESCRIPTION:
LAKE CREEK 96.0
END DESCRIPTION:
XS GIS Cut Line= 3
      3766529.87     10090065.03      3766113.21     10088437.45
      3761974.33     10085535.03
#Sta/Elev= 30
  3516.7  185.87  4790.1  183.46  4893.7  180.34  4924.6  171.11  4958.5  169.13
  4986.6  161.27  4994.2  154.63  5014.4  152.44  5055.6  152.44  5080.9  167.59
  5089.8  169.58  5178.6  168.66  5489.9  170.23  5923.9  171.41    5960  166.94
  5966.1  169.38  5980.9  164.18  6001.8  168.26  6016.6  165.81  6058.5  171.43
  6168.2  172.18  6388.8  168.47    7990  167.32  8019.7  169.73  9671.4     170
  9885.8  173.92  9948.3  181.64 10123.4  200.24   10234  213.18 10251.9  215.58
#Mann= 8 ,-1 , 0
  3516.7     .17       0  4958.5     .06       0  5089.8     .15       0
  5178.6     .11       0  5489.9     .15       0  9948.3     .11       0
 10123.4     .17       0   10234     .11       0
Bank Sta=4958.5,5089.8
XS Rating Curve= 0 ,0
Exp/Cntr=0.3,0.1

Type RM Length L Ch R = 1 ,99839   ,839,839,839
BEGIN DESCRIPTION:
LAKE CREEK 95.0
END DESCRIPTION:
XS GIS Cut Line= 3
      3766751.23     10089804.69      3766816.33     10087981.72
      3761972.75     10085481.81
#Sta/Elev= 30
  2941.6  186.73  3125.3  185.94  3205.4  182.45  3263.8  185.02  3445.5  184.49
  3835.8  179.46  4456.2  180.17    4659  176.53  4862.5  170.07  4890.2  166.39
  4934.6  168.31  4973.2  159.93  4980.4  151.18  5061.9  155.01  5067.9   160.7
  5090.4  169.32  5128.3  159.04  5150.5  161.88  5172.6  169.09  5233.5  167.57
  5255.6  163.09  5427.2  165.98    5455  169.44  5818.7  168.86  9619.1  169.53
  9840.7  171.16  9930.7   181.1 10048.9   194.6   10215  215.22 10216.4  215.56
#Mann= 8 ,-1 , 0
  2941.6     .17       0    4659     .11       0  4934.6     .06       0
  5090.4     .11       0  5818.7     .15       0  9930.7     .11       0
 10048.9     .17       0   10215     .11       0
Bank Sta=4934.6,5090.4
XS Rating Curve= 0 ,0
Exp/Cntr=0.3,0.1

Type RM Length L Ch R = 1 ,99000   ,1013,1013,1013
BEGIN DESCRIPTION:
LAKE CREEK 94.0
END DESCRIPTION:
XS GIS Cut Line= 3
      3766816.33      10089713.5      3767102.94      10087291.8
      3761855.36     10085169.21
#Sta/Elev= 30
  2561.4  184.63  3319.1   178.8  3471.4  182.72  3719.9  177.76  4231.9  178.93
  4319.8  176.71  4416.7  169.34    4486  168.63  4527.5  164.58  4567.7  169.61
  4906.4  169.52  4960.5  165.89  4999.6  154.95  5006.5  150.77  5047.7  150.77
  5059.4  159.66  5072.1  165.07  5120.3  169.52  6266.3  168.12  8446.6  166.96
  8543.6  167.43  8668.3  173.18  8912.3  167.65  9180.5  170.55 10140.6  170.21
 10242.4  175.76 10266.6  180.89 10373.1  192.51 10588.4  213.85 10660.6   217.6
#Mann= 7 ,-1 , 0
  2561.4     .17       0    4486     .15       0  4906.4     .11       0
  4960.5     .06       0  5072.1     .11       0  6266.3     .15       0
 10373.1     .17       0
Bank Sta=4960.5,5072.1
XS Rating Curve= 0 ,0
Exp/Cntr=0.3,0.1

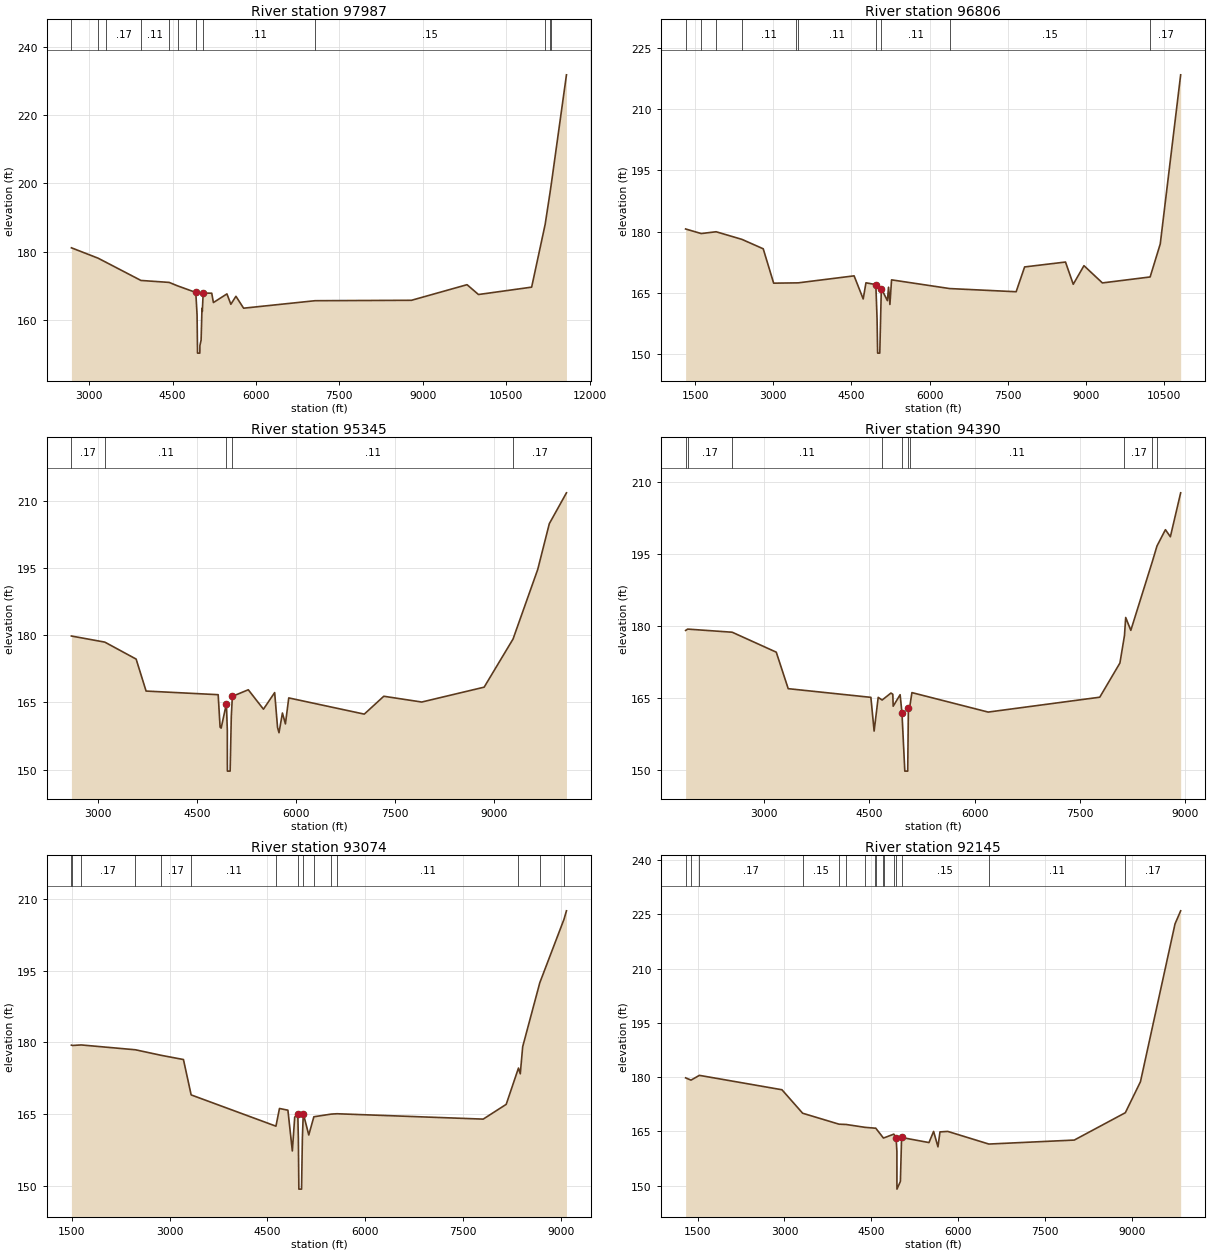
Type RM Length L Ch R = 1 ,97987   ,1181,1181,1181
BEGIN DESCRIPTION:
LAKE CREEK 93.0
END DESCRIPTION:
XS GIS Cut Line= 3
      3767818.94     10088984.28      3767962.17     10086848.91
      3762063.77     10083541.64
#Sta/Elev= 30
  2682.2  181.18  3162.5  178.14  3311.8  176.88  3932.3  171.63  4441.1  171.05
  4590.5  170.05    4919  168.12    4942  161.48  4950.3  150.36  4991.6  150.36
  4992.7  152.55  5014.3  154.17  5030.3  163.45    5036  162.59    5052  167.95
  5205.7  167.89  5235.7  165.16  5478.8  167.69  5549.6  164.66  5640.8  166.99
  5778.9  163.51  7064.7   165.7  8797.4  165.82    9797  170.39 10002.4  167.51
 10958.7  169.67 11201.7  188.05 11287.4  197.13 11312.5  199.91 11584.7   231.8
#Mann= 12 ,-1 , 0
  2682.2     .17       0  3162.5     .15       0  3311.8     .17       0
  3932.3     .11       0  4441.1     .15       0  4590.5     .11       0
    4919     .06       0    5052     .11       0  7064.7     .15       0
 11201.7     .17       0 11287.4     .15       0 11312.5     .17       0
Bank Sta=4919,5052
XS Rating Curve= 0 ,0
Exp/Cntr=0.3,0.1

Type RM Length L Ch R = 1 ,96806   ,1461,1461,1461
BEGIN DESCRIPTION:
LAKE CREEK 92.0
END DESCRIPTION:
XS GIS Cut Line= 4
      3767910.09     10088815.04      3768265.65     10086355.24
      3766868.42     10085885.37      3762740.82     10082174.43
#Sta/Elev= 30
  1313.5  180.62  1612.9   179.5  1899.6  179.94  2396.4  178.07  2804.3  175.77
  3004.9  167.36  3443.2  167.43    3479  167.44  4550.1  169.15    4725   163.5
  4777.7  167.45  4967.6  167.01  4991.2  158.67  5002.1  150.24  5043.4  150.24
  5073.1  166.05  5189.2  163.08  5211.8  166.37    5238  162.15  5269.6  168.17
    6385  166.04  7662.9  165.26  7825.8  171.33  8611.4  172.53  8760.1  167.09
  8965.7  171.64    9320  167.42 10237.2  168.88 10431.5  176.96 10823.5  218.34
#Mann= 10 ,-1 , 0
  1313.5     .17       0  1612.9     .15       0  1899.6     .17       0
  2396.4     .11       0  3443.2     .15       0    3479     .11       0
  4967.6     .06       0  5073.1     .11       0    6385     .15       0
 10237.2     .17       0
Bank Sta=4967.6,5073.1
XS Rating Curve= 0 ,0
Exp/Cntr=0.3,0.1

Type RM Length L Ch R = 1 ,95345   ,955,955,955
BEGIN DESCRIPTION:
LAKE CREEK 90.0
END DESCRIPTION:
XS GIS Cut Line= 3
      3768040.29     10088242.14      3768456.96     10086249.95
      3765878.85     10081419.25
#Sta/Elev= 30
  2594.1  179.82  3100.7  178.46    3576  174.67  3727.1  167.53  4820.8  166.72
  4849.8  159.48  4866.1  159.26  4945.5  164.73  4959.6  158.73  4959.9  151.65
  4960.9  149.65  5002.2  149.65  5019.8  161.83  5036.1  166.35  5277.6  167.82
  5507.7  163.48  5677.7  167.19  5721.6   159.4  5743.6  158.23  5795.6  162.63
    5841   160.2  5891.6     166  7037.5  162.38  7333.5  166.37  7909.3  165.08
  8856.1   168.4  9294.5  179.15  9669.1  194.69  9844.8  204.91   10105   211.8
#Mann= 5 ,-1 , 0
  2594.1     .17       0  3100.7     .11       0  4945.5     .06       0
  5036.1     .11       0  9294.5     .17       0
Bank Sta=4945.5,5036.1
XS Rating Curve= 0 ,0
Exp/Cntr=0.3,0.1

Type RM Length L Ch R = 1 ,94390   ,1316,1316,1316
BEGIN DESCRIPTION:
LAKE CREEK 89.0
END DESCRIPTION:
XS GIS Cut Line= 3
      3768040.29     10088385.39      3768938.73      10085403.6
      3768470.09     10081485.23
#Sta/Elev= 30
  1878.7   179.1  1907.8  179.38  2542.6  178.73  3171.6  174.57  3341.8  166.96
  4521.1  165.15  4567.3  158.12  4625.3  165.15  4681.4  164.59  4807.5  166.05
  4833.8  165.79    4839   163.3    4938   165.7  4964.2  161.95    5005  149.77
  5046.3  149.77  5055.9  162.92  5075.8  163.24  5106.2  166.14  6193.9  162.08
  7785.2  165.18    8073  172.31  8137.8  178.03  8155.4   181.8  8228.3  179.12
  8536.3  193.51  8600.9  196.69  8721.8  200.11  8792.3  198.63  8939.2  207.79
#Mann= 10 ,-1 , 0
  1878.7     .15       0  1907.8     .17       0  2542.6     .11       0
  4681.4     .15       0  4964.2     .06       0  5055.9     .15       0
  5075.8     .11       0  8137.8     .17       0  8536.3     .11       0
  8600.9     .17       0
Bank Sta=4964.2,5055.9
XS Rating Curve= 0 ,0
Exp/Cntr=0.3,0.1

Type RM Length L Ch R = 1 ,93074   ,929,929,929
BEGIN DESCRIPTION:
LAKE CREEK 88.0
END DESCRIPTION:
XS GIS Cut Line= 3
      3768014.26      10088541.6      3769693.94     10085611.93
      3768717.86     10081511.11
#Sta/Elev= 30
  1494.2  179.44  1509.9  179.37  1644.4  179.48  2476.1  178.47  2872.5  177.31
  3212.3  176.44  3330.6  169.06    4631  162.54  4685.1  166.23  4814.6  165.87
  4882.4  157.37  4918.7  164.42    4966  165.14  4974.9  159.98  4982.4  149.41
  5023.7  149.41  5036.6  160.13  5050.3  165.17  5134.6   160.7  5212.5   164.5
    5481  165.06  5567.8  165.13  7809.7  164.01  8162.4  167.09  8350.7  174.66
  8378.3  173.46  8415.3  179.12  8677.8  192.46  9047.8  205.65  9086.6  207.45
#Mann= 15 ,-1 , 0
  1494.2     .17       0  1509.9     .15       0  1644.4     .17       0
  2476.1     .11       0  2872.5     .17       0  3330.6     .11       0
    4631     .15       0    4966     .06       0  5050.3     .15       0
  5212.5     .11       0    5481     .15       0  5567.8     .11       0
  8350.7     .17       0  8677.8     .11       0  9047.8     .17       0
Bank Sta=4966,5050.3
XS Rating Curve= 0 ,0
Exp/Cntr=0.3,0.1

Type RM Length L Ch R = 1 ,92145   ,525,525,525
BEGIN DESCRIPTION:
LAKE CREEK 87.0
END DESCRIPTION:
XS GIS Cut Line= 3
      3768027.28     10088606.71      3770475.19     10085846.31
      3769217.84     10081161.04
#Sta/Elev= 30
  1294.4   179.8  1387.5  179.17  1531.9  180.49  2956.6  176.51  3313.3  170.02
  3941.8  166.99  4064.5  166.91  4389.6  166.12  4563.5  165.89  4572.9  165.92
  4706.9  163.17  4725.2  163.26    4886  164.24  4925.4  163.25  4939.6   159.4
  4939.7  151.04  4940.7  149.04  4999.6  151.17  5020.3  163.32  5492.9  161.91
  5572.9  164.99  5647.8  160.73  5682.6  164.86  5817.6  164.99    6526   161.5
  7999.7   162.6  8880.3  170.16  9141.2  178.72  9737.5  222.35  9834.9  225.97
#Mann= 16 ,-1 , 0
  1294.4     .17       0  1387.5     .15       0  1531.9     .17       0
  3313.3     .15       0  3941.8     .17       0  4064.5     .15       0
  4389.6     .17       0  4563.5     .15       0  4572.9     .11       0
  4706.9     .15       0  4725.2     .11       0    4886     .15       0
  4925.4     .06       0  5020.3     .15       0    6526     .11       0
  8880.3     .17       0
Bank Sta=4925.4,5020.3
XS Rating Curve= 0 ,0
Exp/Cntr=0.3,0.1

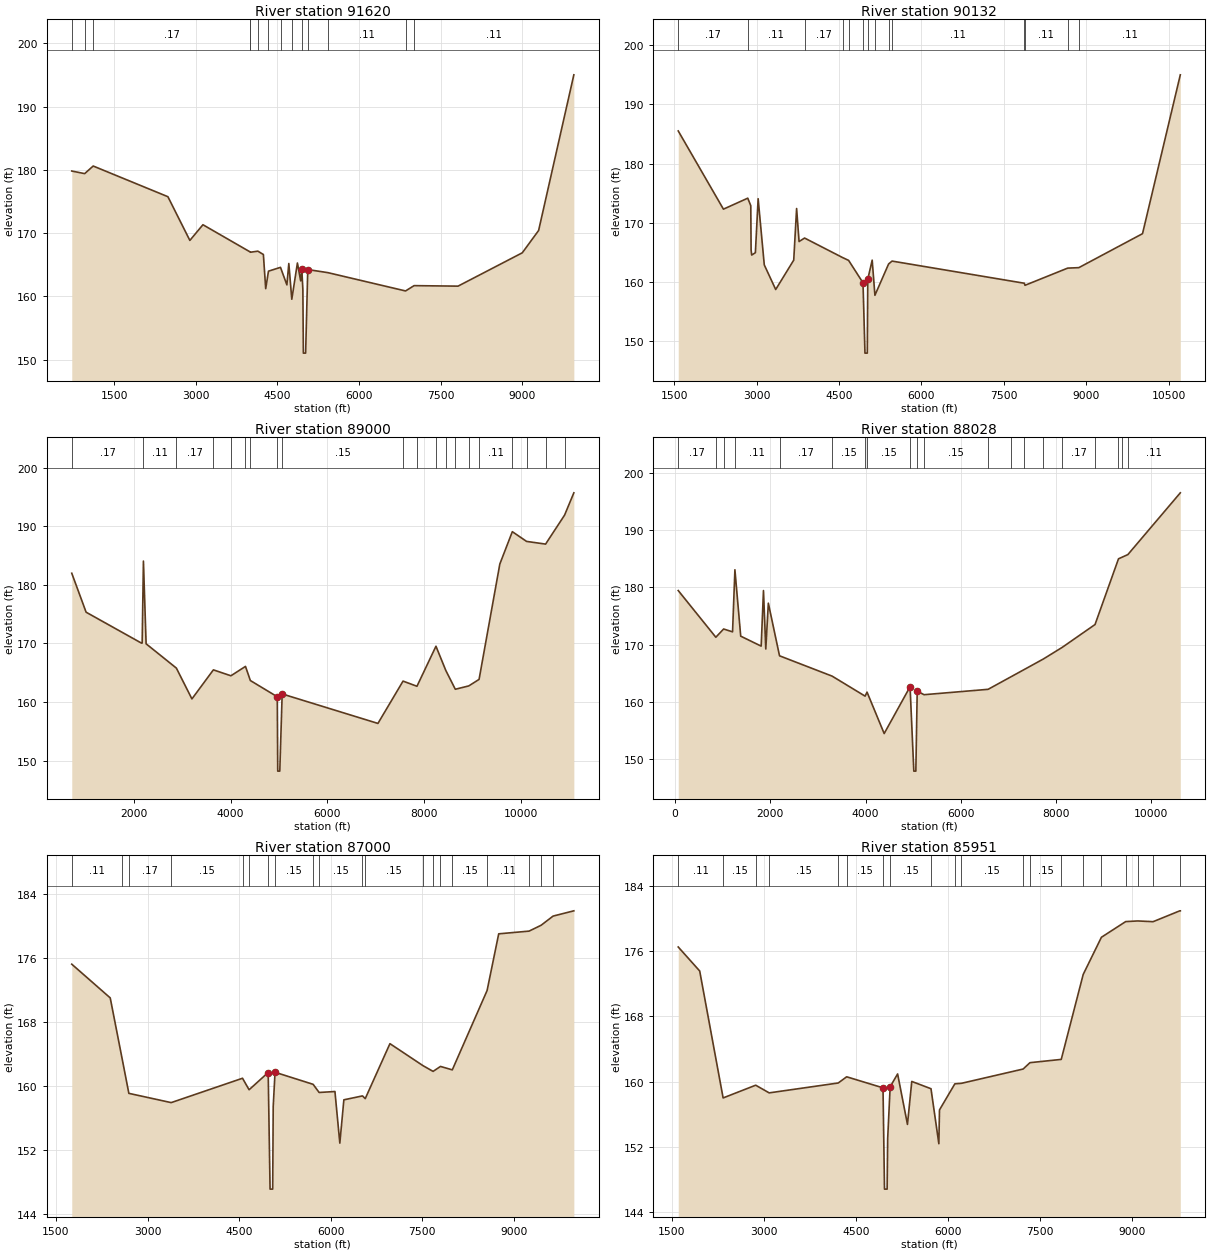
Type RM Length L Ch R = 1 ,91620   ,1488,1488,1488
BEGIN DESCRIPTION:
LAKE CREEK 86.0
END DESCRIPTION:
XS GIS Cut Line= 3
       3768001.2     10088710.92       3770917.9     10085950.47
      3771022.02     10080744.08
#Sta/Elev= 30
   721.2  179.83   957.8  179.42  1115.1  180.62  2487.2  175.77  2890.5  168.86
  3130.8  171.34  3999.5  167.03    4002  166.99  4139.4  167.16  4241.3  166.63
  4283.7  161.23  4334.8     164  4555.7   164.6  4672.9  161.83  4708.5  165.21
  4763.2  159.56  4866.5  165.29  4926.5  162.46  4946.5   164.4  4966.5  161.09
  4975.8  151.04  5017.2  151.04  5056.5  164.25  5423.1  163.77  6852.8  160.87
  7009.8  161.71  7817.1  161.63  8997.3   166.9  9297.4  170.43  9944.5  195.04
#Mann= 14 ,-1 , 0
   721.2     .17       0   957.8     .15       0  1115.1     .17       0
  3999.5     .11       0    4002     .17       0  4139.4     .11       0
  4334.8     .15       0  4555.7     .11       0  4763.2     .15       0
  4946.5     .06       0  5056.5     .15       0  5423.1     .11       0
  6852.8     .15       0  7009.8     .11       0
Bank Sta=4946.5,5056.5
XS Rating Curve= 0 ,0
Exp/Cntr=0.3,0.1

Type RM Length L Ch R = 1 ,90132   ,1132,1132,1132
BEGIN DESCRIPTION:
LAKE CREEK 85.0
END DESCRIPTION:
XS GIS Cut Line= 3
      3770110.59     10089466.12      3771647.06      10086406.2
      3771139.25     10080716.13
#Sta/Elev= 30
  1573.6  185.52  2396.1  172.28  2838.8  174.14  2893.7  172.87  2899.7  165.36
  2910.5  164.51  2977.5  164.91  3027.7  174.05  3139.4  162.85  3347.2  158.68
  3675.4  163.65  3727.7  172.39  3772.5   166.8    3873  167.39    4566  164.08
    4674  163.61  4936.2  159.81  4971.8  147.91  5014.1  147.91  5022.8  160.41
  5103.2  163.65  5152.8   157.7  5401.9     163  5464.5  163.49  7871.7  159.74
  7883.8  159.39  8660.7   162.3  8863.8  162.38 10022.6  168.13 10710.3  195.02
#Mann= 14 ,-1 , 0
  1573.6     .17       0  2838.8     .11       0    3873     .17       0
    4566     .11       0    4674     .15       0  4936.2     .06       0
  5022.8     .15       0  5152.8     .11       0  5401.9     .15       0
  5464.5     .11       0  7871.7     .15       0  7883.8     .11       0
  8660.7     .15       0  8863.8     .11       0
Bank Sta=4936.2,5022.8
XS Rating Curve= 0 ,0
Exp/Cntr=0.3,0.1

Type RM Length L Ch R = 1 ,89000   ,972,972,972
BEGIN DESCRIPTION:
LAKE CREEK 84.0
END DESCRIPTION:
XS GIS Cut Line= 3
      3771451.76     10090208.27      3772516.31     10086056.48
      3772688.73     10079960.91
#Sta/Elev= 30
   713.9  181.97  1010.4  175.32  2156.3  170.04  2169.8  170.06  2195.9  184.04
  2251.3  169.93  2877.4  165.78    3199  160.52  3642.6  165.48  4005.3  164.47
  4306.9  166.07  4407.4  163.66  4964.3  160.89  4973.9   148.2  5016.2   148.2
  5065.4  161.37  7046.2  156.34  7565.4  163.56  7853.3  162.68  8246.4  169.51
  8449.9  165.38  8646.4  162.17  8924.5  162.74  9137.8  163.85  9567.2  183.54
  9825.7  189.06 10120.5   187.4 10513.6  186.94 10906.7  191.89   11098  195.69
#Mann= 20 ,-1 , 0
   713.9     .17       0  2195.9     .11       0  2877.4     .17       0
  3642.6     .11       0  4005.3     .15       0  4306.9     .17       0
  4407.4     .15       0  4964.3     .06       0  5065.4     .15       0
  7565.4     .11       0  7853.3     .15       0  8246.4     .11       0
  8449.9     .15       0  8646.4     .11       0  8924.5     .15       0
  9137.8     .11       0  9825.7     .11       0 10120.5     .17       0
 10513.6     .11       0 10906.7     .11       0
Bank Sta=4964.3,5065.4
XS Rating Curve= 0 ,0
Exp/Cntr=0.3,0.1

Type RM Length L Ch R = 1 ,88028   ,1028,1028,1028
BEGIN DESCRIPTION:
LAKE CREEK 83.0
END DESCRIPTION:
XS GIS Cut Line= 3
      3771555.92     10090182.23      3773183.52     10086054.64
      3772936.12     10079947.85
#Sta/Elev= 30
    64.5  179.45   854.5   171.3  1018.4  172.74  1205.8  172.24  1255.3  183.08
  1377.2  171.49  1807.1  169.75  1855.4  179.45  1903.9  169.25  1957.6  177.25
  2192.8  168.06  3298.1  164.51  3990.6  161.02  4031.5  161.72  4391.4  154.49
  4935.3  162.66  5014.3  147.93  5056.6  147.93  5085.4   161.9  5228.9  161.27
  6575.2  162.21  7047.1  164.36  7328.2  165.64  7737.2  167.51  8131.5  169.53
  8821.5  173.52  9314.4  184.99  9380.9  185.24  9511.5  185.73 10613.2  196.51
#Mann= 20 ,-1 , 0
    64.5     .17       0   854.5     .11       0  1018.4     .17       0
  1255.3     .11       0  2192.8     .17       0  3298.1     .15       0
  3990.6     .11       0  4031.5     .15       0  4935.3     .06       0
  5085.4     .15       0  5228.9     .15       0  6575.2     .17       0
  7047.1     .11       0  7328.2     .15       0  7737.2     .11       0
  8131.5     .17       0  8821.5     .11       0  9314.4     .15       0
  9380.9     .17       0  9511.5     .11       0
Bank Sta=4935.3,5085.4
XS Rating Curve= 0 ,0
Exp/Cntr=0.3,0.1

Type RM Length L Ch R = 1 ,87000   ,1049,1049,1049
BEGIN DESCRIPTION:
LAKE CREEK 82.0
END DESCRIPTION:
XS GIS Cut Line= 3
      3774863.22     10089062.48       3773746.3     10086020.01
      3773977.79     10081041.59
#Sta/Elev= 30
    1759  175.27    2389  171.05  2583.1  163.47  2694.2   159.1  3387.7  157.94
  4556.2  160.99  4663.9  159.55  4976.6  161.71  5007.5  147.11  5050.4  147.11
    5059  157.46    5089  161.74  5712.8  160.23  5811.1  159.21  6070.1  159.33
  6150.2  152.87  6216.4  158.29  6521.4  158.78  6566.6  158.44  6971.1  165.32
  7514.2  162.56  7678.2  161.85  7799.1  162.47  7992.7  162.04  8562.6  171.97
    8753  179.07  9250.5  179.41  9447.1  180.14  9643.6  181.29  9983.8  181.95
#Mann= 20 ,-1 , 0
    1759     .11       0  2583.1     .15       0  2694.2     .17       0
  3387.7     .15       0  4556.2     .11       0  4663.9     .15       0
  4976.6     .06       0    5089     .15       0  5712.8     .11       0
  5811.1     .15       0  6521.4     .11       0  6566.6     .15       0
  7514.2     .11       0  7678.2     .17       0  7799.1     .17       0
  7992.7     .15       0  8562.6     .11       0  9250.5     .17       0
  9447.1     .15       0  9643.6     .11       0
Bank Sta=4976.6,5089
XS Rating Curve= 0 ,0
Exp/Cntr=0.3,0.1

Type RM Length L Ch R = 1 ,85951   ,1290,1290,1290
BEGIN DESCRIPTION:
LAKE CREEK 81.0
END DESCRIPTION:
XS GIS Cut Line= 3
      3774993.42     10089023.38      3774472.58     10085481.72
      3774199.15     10080898.43
#Sta/Elev= 30
  1607.8  176.51  1957.1  173.57  2338.3  158.02  2868.2  159.58    3088  158.64
  4211.5  159.85  4349.3  160.61  4940.5159.2555  4964.6  146.85  5007.5  146.85
  5016.4  153.04  5056.8  159.39  5178.1  160.96  5338.5  154.78  5408.6  160.04
  5721.3  159.15  5849.4  152.41  5859.6  156.55  6109.9  159.75  6216.4  159.81
  7220.8  161.56    7332  162.34  7841.2  162.74  8198.7  173.15    8495   177.7
  8889.9  179.62  9087.4   179.7  9336.3  179.61  9770.7  180.94    9779  180.94
#Mann= 20 ,-1 , 0
  1607.8     .11       0  2338.3     .15       0  2868.2     .17       0
    3088     .15       0  4211.5     .11       0  4349.3     .15       0
  4940.5     .06       0  5056.8     .15       0  5721.3     .15       0
  6109.9     .11       0  6216.4     .15       0  7220.8     .11       0
    7332     .15       0  7841.2     .17       0  8198.7     .11       0
    8495     .17       0  8889.9     .11       0  9087.4     .15       0
  9336.3     .11       0  9770.7     .15       0
Bank Sta=4940.5,5056.8
XS Rating Curve= 0 ,0
Exp/Cntr=0.3,0.1

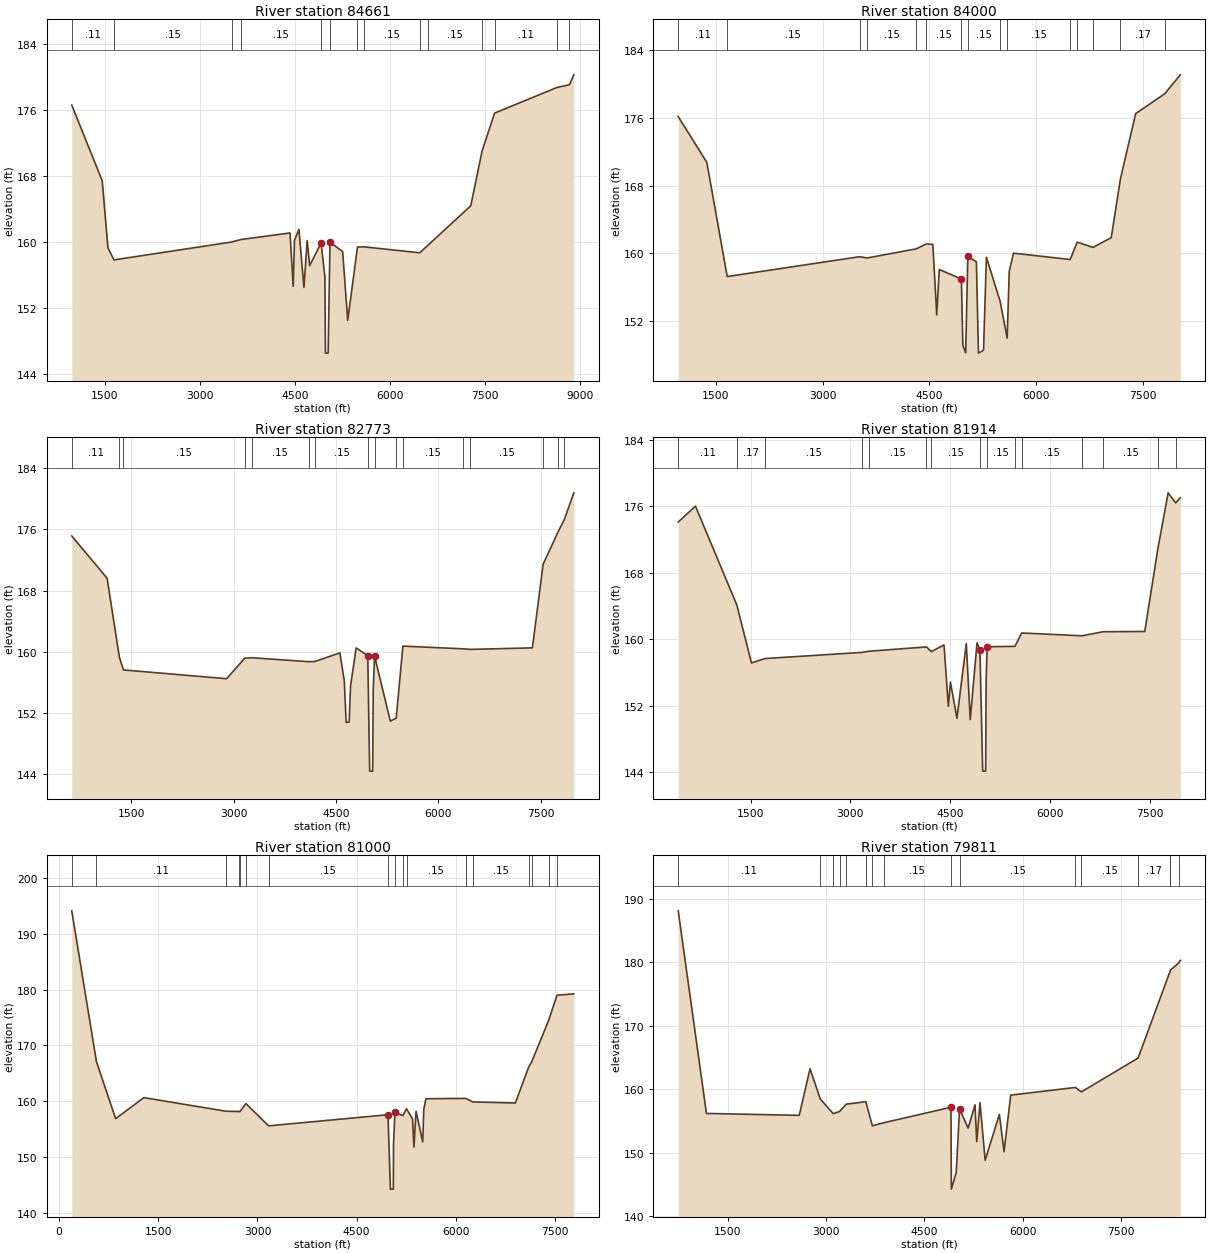
Type RM Length L Ch R = 1 ,84661   ,661,661,661
BEGIN DESCRIPTION:
LAKE CREEK 80.0
END DESCRIPTION:
XS GIS Cut Line= 3
       3775045.5     10088971.35      3774941.33     10085273.39
      3774967.37      10081055.4
#Sta/Elev= 30
   978.6  176.57  1459.1  167.42  1549.1  159.31  1644.2  157.85  3498.1  160.01
  3652.6  160.32  4420.2  161.11  4470.3  154.66  4490.3  160.21  4560.3  161.55
  4640.3  154.52  4690.3  160.19  4730.3  157.15  4910.4   159.9  4970.4  155.78
  4978.9  146.57  5021.8  146.57  5050.4  159.99  5250.4  158.86  5330.4  150.53
  5483.7   159.4    5582  159.43  6466.8  158.71    6592   159.6  7270.4  164.39
    7450  171.05  7646.6  175.61  8629.8  178.71  8826.5  179.04  8896.1  180.24
#Mann= 14 ,-1 , 0
   978.6     .11       0  1644.2     .15       0  3498.1     .11       0
  3652.6     .15       0  4910.4     .06       0  5050.4     .15       0
  5483.7     .11       0    5582     .15       0  6466.8     .11       0
    6592     .15       0    7450     .17       0  7646.6     .11       0
  8629.8     .15       0  8826.5     .11       0
Bank Sta=4910.4,5050.4
XS Rating Curve= 0 ,0
Exp/Cntr=0.3,0.1

Type RM Length L Ch R = 1 ,84000   ,1227,1227,1227
BEGIN DESCRIPTION:
LAKE CREEK 79.0
END DESCRIPTION:
XS GIS Cut Line= 3
      3775110.61     10088997.35      3775434.84     10084980.51
      3775696.55     10081966.05
#Sta/Elev= 30
   970.1  176.16  1371.8  170.76  1658.3  157.28  3517.7  159.62  3625.3  159.47
  4316.3  160.55  4457.5  161.13    4548  161.07  4602.8  152.76  4638.3  158.11
  4949.3  156.99  4969.3  149.19  5009.5  148.28  5039.6  159.66    5160  159.02
  5189.2  148.24  5260.4  148.59  5300.6  159.55  5494.2  154.35  5592.5  150.01
  5621.8  157.91    5682  160.04    6478  159.29  6576.3  161.34  6799.3  160.72
  7055.1  161.87    7184   168.8  7398.4  176.51  7806.3  178.85  8025.8  181.09
#Mann= 15 ,-1 , 0
   970.1     .11       0  1658.3     .15       0  3517.7     .11       0
  3625.3     .15       0  4316.3     .11       0  4457.5     .15       0
  4949.3     .06       0  5039.6     .15       0  5494.2     .11       0
  5592.5     .15       0    6478     .11       0  6576.3     .17       0
  6799.3     .15       0    7184     .17       0  7806.3     .11       0
Bank Sta=4949.3,5039.6
XS Rating Curve= 0 ,0
Exp/Cntr=0.3,0.1

Type RM Length L Ch R = 1 ,82773   ,859,859,859
BEGIN DESCRIPTION:
LAKE CREEK 78.0
END DESCRIPTION:
XS GIS Cut Line= 3
      3775162.69     10088984.32      3776399.67     10085065.06
      3776321.58     10081824.43
#Sta/Elev= 30
   631.9  175.15  1149.1  169.62  1329.2  159.26  1389.3  157.61  2900.3  156.46
  3163.1  159.14    3265  159.21  4099.1  158.69  4193.7  158.72  4557.7  159.84
  4622.4  156.17  4649.5  150.73  4693.5  150.79  4714.1  155.54  4795.7  160.49
  4965.8   159.5  4993.7  144.36  5037.8  144.36  5045.8  155.07  5065.8  159.43
  5295.9  150.91  5382.3   151.3  5480.7  160.73  6366.8  160.37  6465.3   160.3
  7376.5   160.5  7533.6  171.45  7745.3  175.55  7843.7   177.3  7983.3   180.8
#Mann= 16 ,-1 , 0
   631.9     .11       0  1329.2     .17       0  1389.3     .15       0
  3163.1     .11       0    3265     .15       0  4099.1     .11       0
  4193.7     .15       0  4965.8     .06       0  5065.8     .15       0
  5382.3     .11       0  5480.7     .15       0  6366.8     .11       0
  6465.3     .15       0  7533.6     .17       0  7745.3     .11       0
  7843.7     .17       0
Bank Sta=4965.8,5065.8
XS Rating Curve= 0 ,0
Exp/Cntr=0.3,0.1

Type RM Length L Ch R = 1 ,81914   ,914,914,914
BEGIN DESCRIPTION:
LAKE CREEK 77.0
END DESCRIPTION:
XS GIS Cut Line= 3
      3775188.72      10089140.6      3777063.73     10084505.16
      3776621.11     10082005.64
#Sta/Elev= 30
   414.7  174.11   673.1  176.03  1294.5  164.12  1514.1  157.14  1719.6  157.67
  3174.7  158.41  3279.1  158.55  4142.1  159.07    4215  158.51  4405.4  159.31
  4470.1  151.92  4501.5  154.83  4599.6  150.48  4739.8  159.48  4799.2  150.32
  4901.1  159.57  4944.8  158.68  4986.3  144.11  5030.4  144.11  5037.9  154.95
  5052.6  159.09  5470.5  159.14  5571.1  160.75  6476.1  160.41    6795   160.9
  7419.8  160.93  7618.1  170.97  7770.8  177.63  7883.8  176.42  7953.4  177.04
#Mann= 15 ,-1 , 0
   414.7     .11       0  1294.5     .17       0  1719.6     .15       0
  3174.7     .11       0  3279.1     .15       0  4142.1     .11       0
    4215     .15       0  4944.8     .06       0  5052.6     .15       0
  5470.5     .11       0  5571.1     .15       0  6476.1     .11       0
    6795     .15       0  7618.1     .17       0  7883.8     .11       0
Bank Sta=4944.8,5052.6
XS Rating Curve= 0 ,0
Exp/Cntr=0.3,0.1

Type RM Length L Ch R = 1 ,81000   ,1189,1189,1189
BEGIN DESCRIPTION:
LAKE CREEK 76.0
END DESCRIPTION:
XS GIS Cut Line= 3
      3778912.68     10089205.64      3777685.15     10084555.95
      3776725.18     10081940.03
#Sta/Elev= 30
     191  194.18   563.9  167.12   854.4  156.86  1281.7  160.64    2527  158.19
  2721.6  158.15  2735.2  158.12  2824.4  159.58  3169.1  155.57  4974.5  157.57
  5011.7  144.21  5055.8  144.21  5058.5  152.38  5079.8  157.97  5201.1  157.42
  5255.1  158.65  5346.1   156.8  5367.4  151.77  5399.3  158.19  5500.3   152.7
  5516.5  158.53  5548.5  160.44  6150.3   160.5  6256.5  159.87  6901.3  159.67
  7106.5  166.22  7148.2  167.03  7407.4  174.57  7531.5  179.03  7786.5  179.27
#Mann= 17 ,-1 , 0
     191     .17       0   563.9     .11       0    2527     .15       0
  2721.6     .11       0  2735.2     .15       0  2824.4     .11       0
  3169.1     .15       0  4974.5     .06       0  5079.8     .15       0
  5201.1     .11       0  5255.1     .15       0  6150.3     .11       0
  6256.5     .15       0  7106.5     .17       0  7148.2     .11       0
  7407.4     .17       0  7531.5     .11       0
Bank Sta=4974.5,5079.8
XS Rating Curve= 0 ,0
Exp/Cntr=0.3,0.1

Type RM Length L Ch R = 1 ,79811   ,811,811,811
BEGIN DESCRIPTION:
LAKE CREEK 75.0
END DESCRIPTION:
XS GIS Cut Line= 3
      3779173.11     10089127.59      3778626.23     10084583.29
      3776867.88     10082061.11
#Sta/Elev= 30
   748.6  188.08  1178.2   156.2  2592.7   155.9    2757  163.23    2914  158.48
  3110.3  156.16  3209.8  156.52  3309.3  157.66  3607.8  158.05  3707.3  154.25
  3879.6  154.73  4904.9  157.17  4910.7  144.29  4985.5  146.93  5035.8  156.92
  5166.8  153.89  5271.4  157.56  5297.7  151.77  5347.9  157.89  5425.9  148.83
  5642.8  156.05  5714.3  150.17  5815.6  159.08  6801.5  160.29  6892.3  159.59
  7756.8  164.91  8241.9  178.49  8249.5  178.75  8372.7  179.84  8400.3  180.28
#Mann= 16 ,-1 , 0
   748.6     .11       0    2914     .15       0  3110.3     .11       0
  3209.8     .15       0  3309.3     .11       0  3607.8     .15       0
  3707.3     .11       0  3879.6     .15       0  4904.9     .06       0
  5035.8     .15       0  6801.5     .11       0  6892.3     .15       0
  7756.8     .17       0  8241.9     .11       0  8249.5     .17       0
  8372.7     .11       0
Bank Sta=4904.9,5035.8
XS Rating Curve= 0 ,0
Exp/Cntr=0.3,0.1

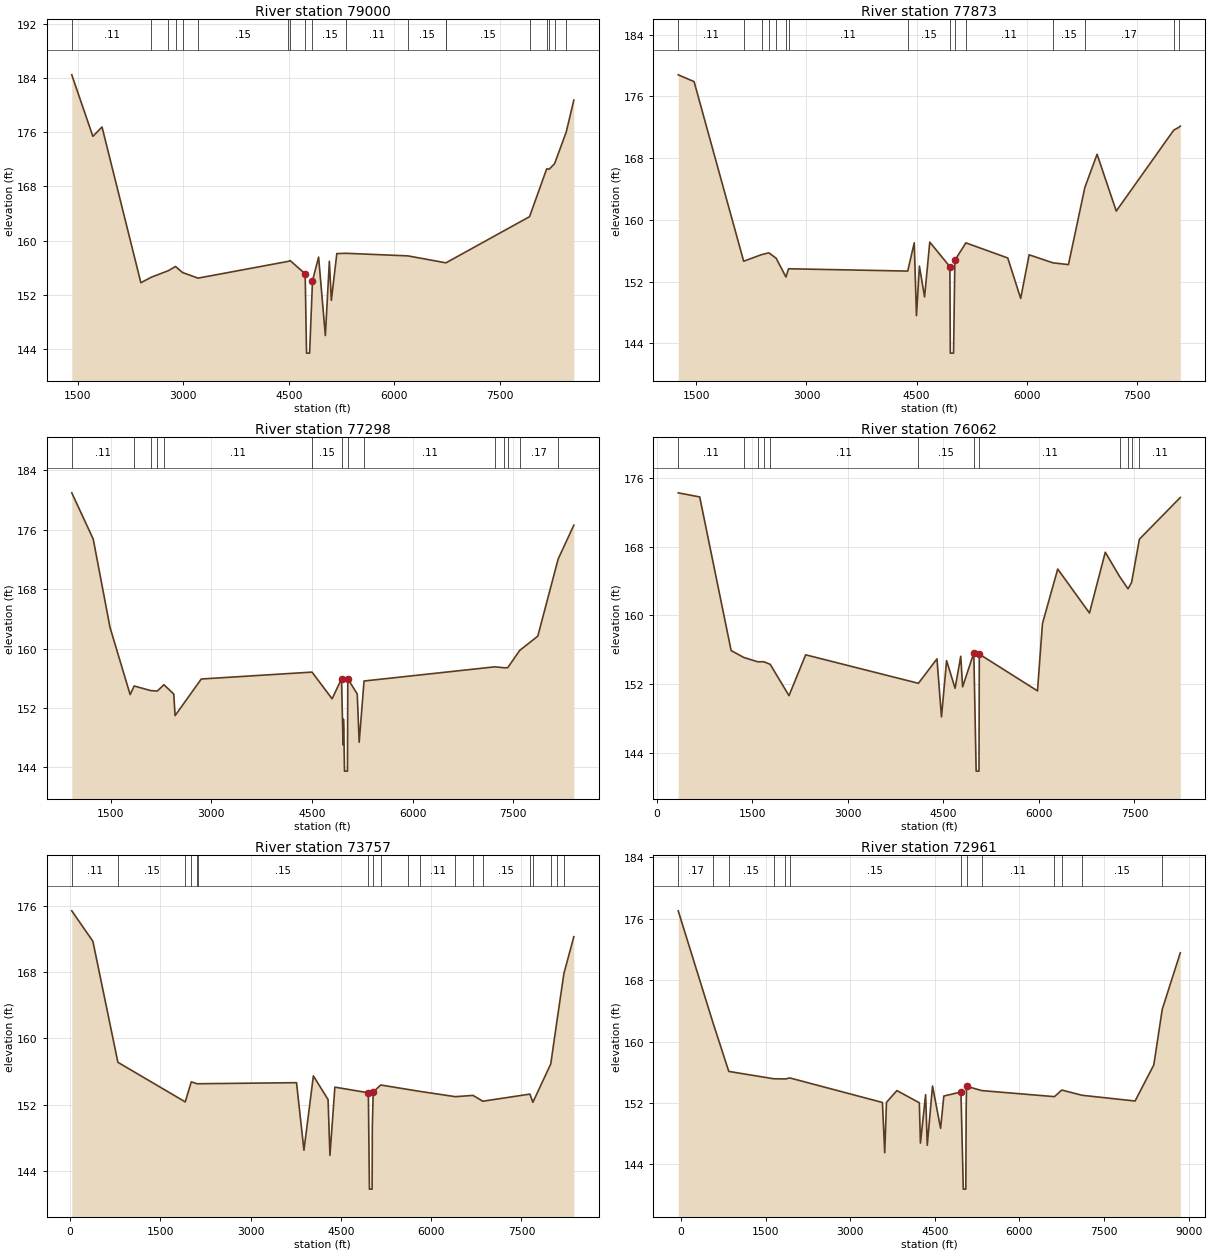
Type RM Length L Ch R = 1 ,79000   ,1127,1127,1127
BEGIN DESCRIPTION:
LAKE CREEK 74.0
END DESCRIPTION:
XS GIS Cut Line= 3
      3780167.86      10088161.1      3779386.49     10084660.13
      3777017.84     10082011.06
#Sta/Elev= 30
  1412.9   184.5  1713.3   175.4  1843.3  176.79  2395.7  153.76  2544.9  154.58
  2786.6  155.54  2888.2  156.16  2989.8  155.26  3209.3  154.44  4487.2  156.91
  4519.4  157.03  4732.6  155.07  4751.6  143.35  4795.7  143.35  4836.6  154.05
  4923.5  157.55  5019.7  145.95  5076.5  156.94  5104.9  151.16  5182.7  158.07
  5317.3  158.11  6193.6  157.73  6734.4   156.7  6736.3  156.71  7923.9  163.53
  8167.1  170.59  8203.4  170.55    8280  171.37  8445.4  176.04  8553.6  180.77
#Mann= 19 ,-1 , 0
  1412.9     .11       0  2544.9     .15       0  2786.6     .11       0
  2888.2     .17       0  2989.8     .11       0  3209.3     .15       0
  4487.2     .11       0  4519.4     .15       0  4732.6     .06       0
  4836.6     .15       0  5317.3     .11       0  6193.6     .15       0
  6734.4     .11       0  6736.3     .15       0  7923.9     .11       0
  8167.1     .15       0  8203.4     .11       0    8280     .17       0
  8445.4     .11       0
Bank Sta=4732.6,4836.6
XS Rating Curve= 0 ,0
Exp/Cntr=0.3,0.1

Type RM Length L Ch R = 1 ,77873   ,575,575,575
BEGIN DESCRIPTION:
LAKE CREEK 73.0
END DESCRIPTION:
XS GIS Cut Line= 3
      3780201.75     10087955.66      3779746.02     10084140.58
      3778144.45      10081601.5
#Sta/Elev= 30
  1251.9  178.81    1468  177.93  2143.9  154.64  2387.5  155.49    2487  155.73
  2586.5  155.03  2720.4  152.59  2755.1  153.66  4380.2  153.36  4469.2  157.03
  4499.4  147.58  4539.7  154.01  4610.1  150.01  4680.7  157.12  4954.9  153.93
  4960.8  142.72  5004.9  142.72  5023.1  154.76  5173.3  157.02  5743.8  155.06
    5920  149.82  6035.4  155.47  6359.7  154.43  6571.4   154.2  6794.7   164.2
  6961.6  168.51  7222.9  161.14  8005.8  171.63  8074.9     172  8096.1  172.16
#Mann= 15 ,-1 , 0
  1251.9     .11       0  2143.9     .15       0  2387.5     .11       0
    2487     .17       0  2586.5     .11       0  2720.4     .15       0
  2755.1     .11       0  4380.2     .15       0  4954.9     .06       0
  5023.1     .15       0  5173.3     .11       0  6359.7     .15       0
  6794.7     .17       0  8005.8     .11       0  8074.9     .15       0
Bank Sta=4954.9,5023.1
XS Rating Curve= 0 ,0
Exp/Cntr=0.3,0.1

Type RM Length L Ch R = 1 ,77298   ,1236,1236,1236
BEGIN DESCRIPTION:
LAKE CREEK 72.0
END DESCRIPTION:
XS GIS Cut Line= 3
      3780267.85     10088011.11      3780149.67     10083997.35
      3778467.83     10080961.03
#Sta/Elev= 30
   918.3  180.96  1238.5  174.73  1488.6  162.85  1788.7   153.8  1848.6  154.96
  2095.5  154.34    2194  154.28  2292.5  155.13    2439  153.87    2459  150.97
  2849.2   155.9  4500.6  156.83    4800  153.24    4941  155.92  4963.3  147.05
    4969   150.5  4975.3  149.09  4984.8   143.5  5028.9   143.5  5034.3  155.92
  5175.1  153.89  5203.9  147.39  5276.5  155.63  7228.5  157.54  7366.9  157.41
  7418.9  157.42  7596.6  159.74  7867.5  161.67  8170.9  172.05  8404.8  176.61
#Mann= 14 ,-1 , 0
   918.3     .11       0  1848.6     .15       0  2095.5     .11       0
    2194     .15       0  2292.5     .11       0  4500.6     .15       0
    4941     .06       0  5034.3     .15       0  5276.5     .11       0
  7228.5     .15       0  7366.9     .11       0  7418.9     .15       0
  7596.6     .17       0  8170.9     .11       0
Bank Sta=4941,5034.3
XS Rating Curve= 0 ,0
Exp/Cntr=0.3,0.1

Type RM Length L Ch R = 1 ,76062   ,2305,2305,2305
BEGIN DESCRIPTION:
LAKE CREEK 71.0
END DESCRIPTION:
XS GIS Cut Line= 3
       3780423.1     10088085.91      3780956.96     10083476.52
      3781907.49     10080377.52
#Sta/Elev= 30
   338.1  174.28   675.2   173.8  1168.5  155.91  1367.6   155.1  1585.1   154.6
  1683.6   154.6  1782.2   154.3  2076.9  150.65  2338.1  155.41  4108.4  152.09
  4399.9  154.94  4470.4  148.18  4550.9  154.73  4684.3  151.51  4773.1  155.24
  4802.6  151.68  4978.3  155.64  5014.9  141.86  5059.2  141.86  5064.5  155.49
  5977.7  151.21  6055.8  159.05  6295.5   165.4  6793.6  160.28  7041.9  167.36
  7272.9  164.46  7399.3   163.1  7454.8  163.84  7577.9  168.88  8219.8  173.74
#Mann= 12 ,-1 , 0
   338.1     .11       0  1367.6     .15       0  1585.1     .11       0
  1683.6     .15       0  1782.2     .11       0  4108.4     .15       0
  4978.3     .06       0  5064.5     .11       0  7272.9     .15       0
  7399.3     .11       0  7454.8     .15       0  7577.9     .11       0
Bank Sta=4978.3,5064.5
XS Rating Curve= 0 ,0
Exp/Cntr=0.3,0.1

Type RM Length L Ch R = 1 ,73757   ,796,796,796
BEGIN DESCRIPTION:
LAKE CREEK 70.0
END DESCRIPTION:
XS GIS Cut Line= 3
       3781230.4     10088723.88      3782285.08     10084309.85
      3781933.52     10080520.81
#Sta/Elev= 30
    26.6  175.42   377.6  171.74   793.3  157.12  1912.5  152.34  2012.7  154.76
  2112.9  154.52  2121.5  154.53  3761.7  154.66    3885   146.5  4041.7  155.48
    4286  152.62  4316.9  145.88  4399.1  154.12  4955.3  153.44  4973.2   141.8
  5017.8   141.8  5021.3  149.25  5035.7  153.54  5161.6  154.38  5615.1  153.84
  5818.5   153.6  6401.1  152.97    6695  153.12  6857.5  152.42  7640.3  153.28
  7689.6  152.29    7987  156.93  8097.4  162.52  8205.6  167.87  8370.2  172.29
#Mann= 19 ,-1 , 0
    26.6     .11       0   793.3     .15       0  1912.5     .11       0
  2012.7     .17       0  2112.9     .11       0  2121.5     .15       0
  4955.3     .06       0  5035.7     .15       0  5161.6     .11       0
  5615.1     .15       0  5818.5     .11       0  6401.1     .15       0
    6695     .11       0  6857.5     .15       0  7640.3     .11       0
  7689.6     .17       0    7987     .15       0  8097.4     .17       0
  8205.6     .11       0
Bank Sta=4955.3,5035.7
XS Rating Curve= 0 ,0
Exp/Cntr=0.3,0.1

Type RM Length L Ch R = 1 ,72961   ,1430,1430,1430
BEGIN DESCRIPTION:
LAKE CREEK 69.0
END DESCRIPTION:
XS GIS Cut Line= 4
      3781959.57     10088867.12      3782911.77     10084253.63
      3782506.44      10083906.2       3782063.9     10080274.75
#Sta/Elev= 30
   -50.8  177.04   562.5  162.52   845.4   156.1  1642.4  155.14    1851  155.12
  1927.2  155.25    3570  152.05  3610.8   145.5  3641.5  152.06  3827.3   153.6
  4224.3  152.01  4243.9  146.75  4335.8  153.07  4364.9  146.47  4458.3   154.2
  4601.3  148.68  4658.7  152.89  4962.5  153.41  5003.8  140.75  5048.4  140.75
  5054.7  151.12  5061.2  154.17  5330.4   153.6  6620.6  152.81  6750.5  153.67
  7108.4  152.99  8049.9  152.24  8382.3  156.95  8531.6  164.19  8852.1  171.57
#Mann= 13 ,-1 , 0
   -50.8     .17       0   562.5     .11       0   845.4     .15       0
  1642.4     .17       0    1851     .11       0  1927.2     .15       0
  4962.5     .06       0  5061.2     .15       0  5330.4     .11       0
  6620.6     .15       0  6750.5     .11       0  7108.4     .15       0
  8531.6     .17       0
Bank Sta=4962.5,5061.2
XS Rating Curve= 0 ,0
Exp/Cntr=0.3,0.1