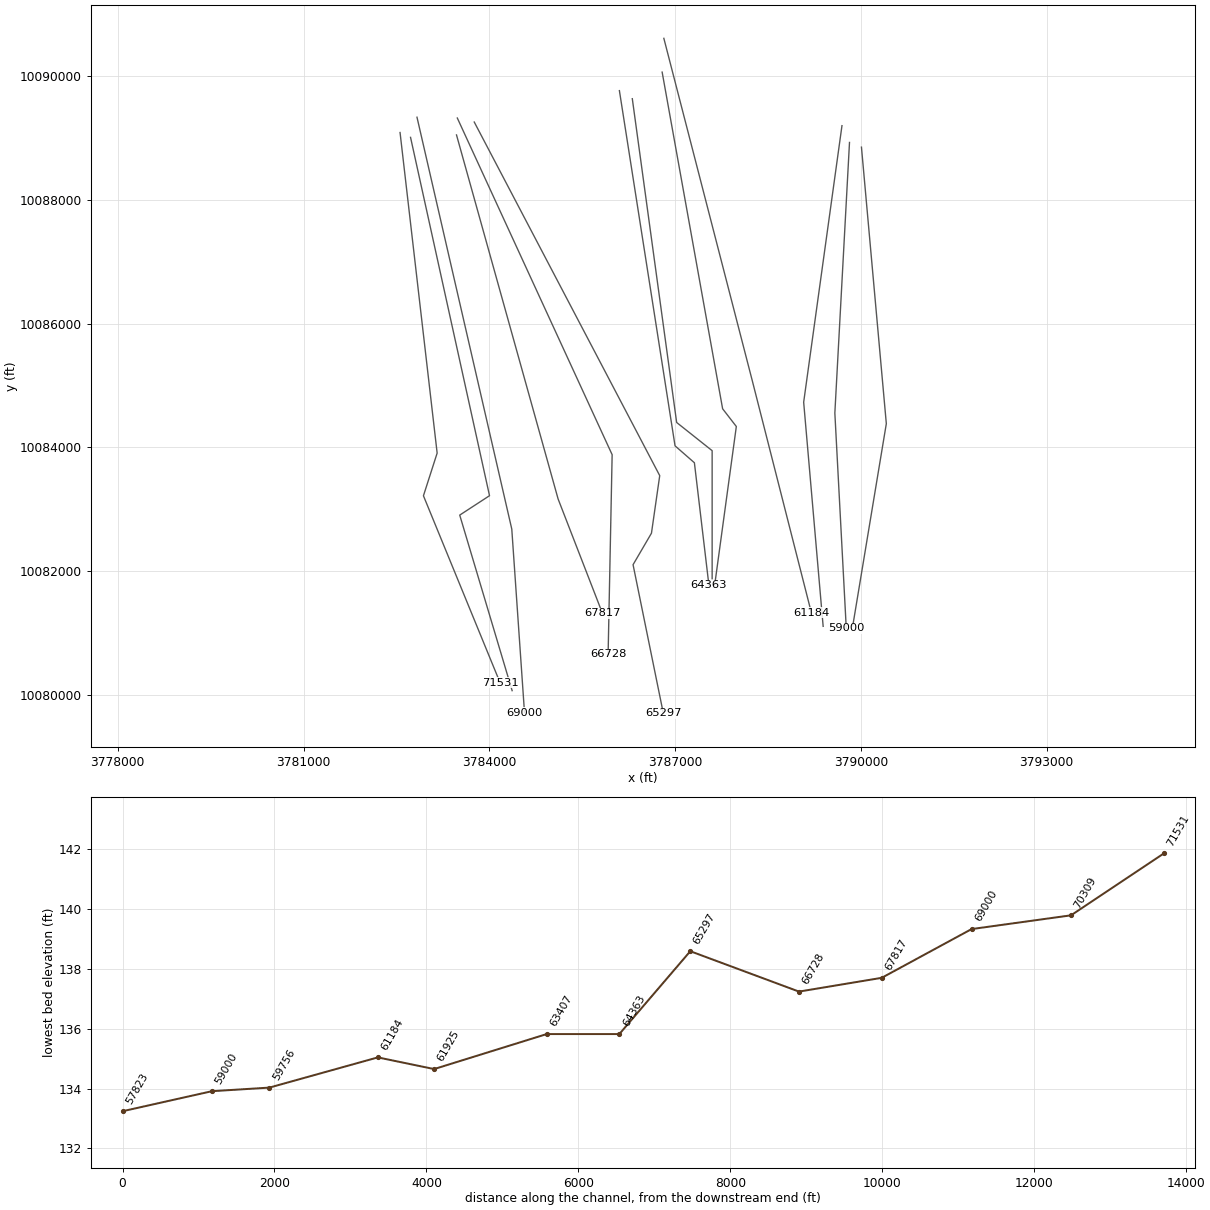
HEC-RAS study LAKE CREEK.prj: LAKE CREEK Base Level Engineering

--- LAKE CREEK.g01 (geometry) --- (continued)

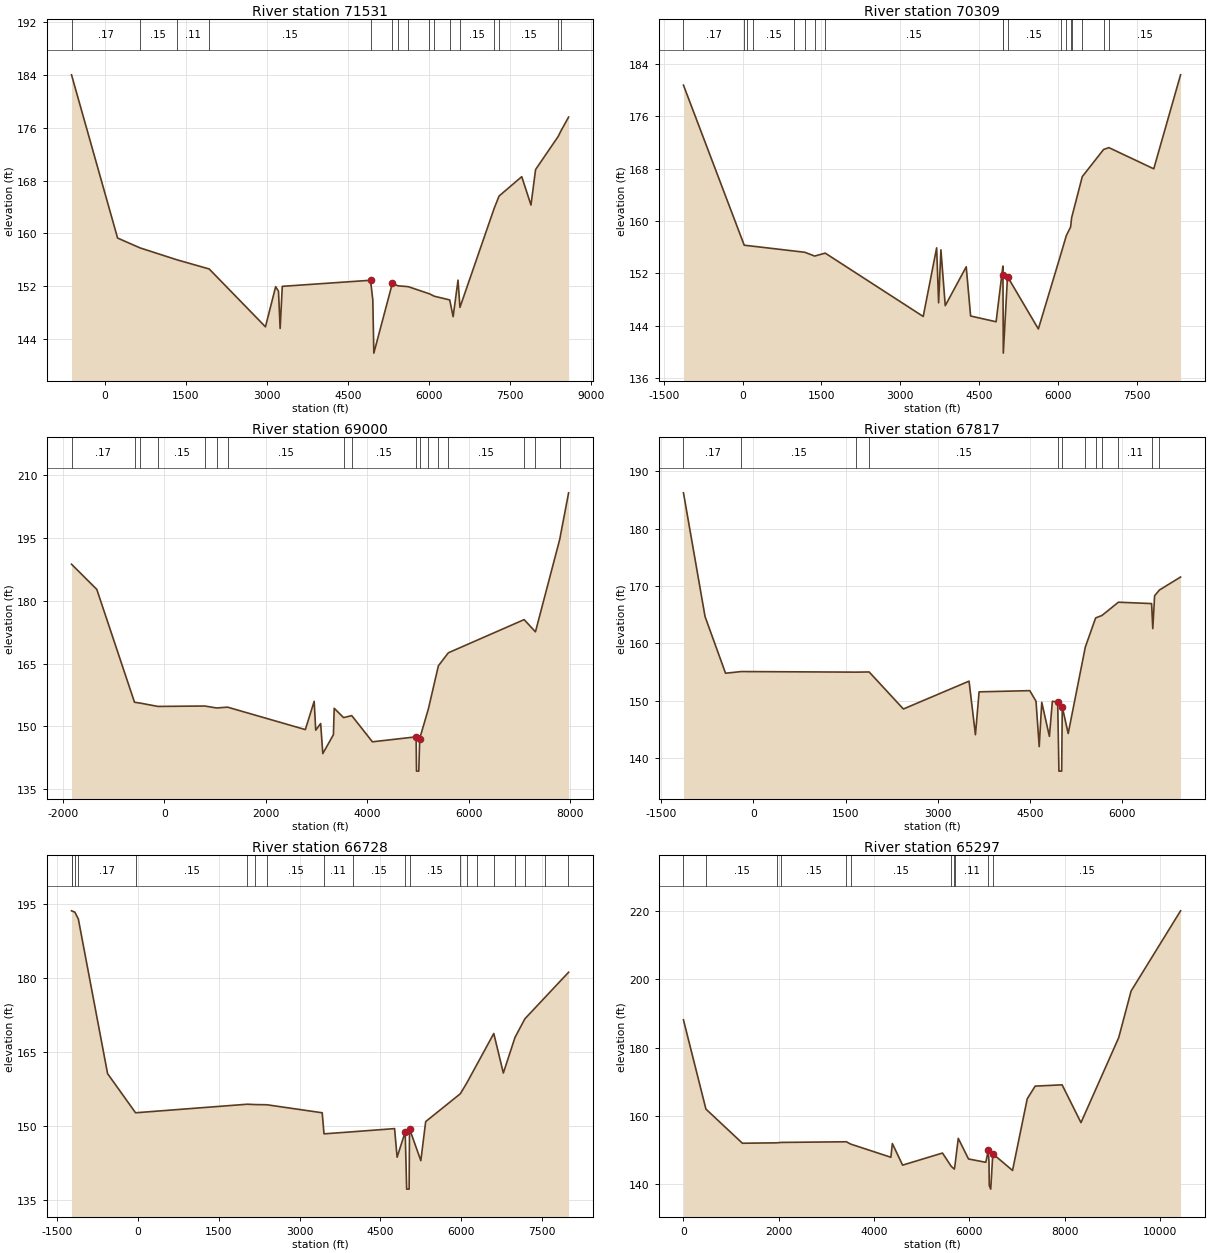
Type RM Length L Ch R = 1 ,71531   ,1222,1222,1222
BEGIN DESCRIPTION:
LAKE CREEK 67.0
END DESCRIPTION:
XS GIS Cut Line= 4
      3782558.52      10089088.5      3783157.48      10083906.2
      3782936.13      10083216.1       3784172.8     10080196.02
#Sta/Elev= 30
  -614.9  184.03   238.2   159.3   652.6  157.81    1334  156.01  1934.7  154.61
  2976.3  145.85  3165.3  151.93  3217.9  151.24  3248.1   145.6  3288.3  151.98
  4922.3   152.9  4964.3  149.94  4983.2  141.86  5326.6  152.44  5428.4  152.06
  5621.4  151.93  6011.8  150.85  6103.9  150.48  6388.5  149.92  6451.6  147.38
  6542.3  152.92    6578  148.79  7213.1  163.83    7302  165.66  7722.5   168.6
  7893.1   164.3  7978.7  169.68  8396.2  174.68  8449.2  175.55  8590.1  177.63
#Mann= 16 ,-1 , 0
  -614.9     .17       0   652.6     .15       0    1334     .11       0
  1934.7     .15       0  4922.3     .06       0  5326.6     .15       0
  5428.4     .11       0  5621.4     .15       0  6011.8     .11       0
  6103.9     .15       0  6388.5     .11       0    6578     .15       0
  7213.1     .17       0    7302     .15       0  8396.2     .11       0
  8449.2     .15       0
Bank Sta=4922.3,5326.6
XS Rating Curve= 0 ,0
Exp/Cntr=0.3,0.1

Type RM Length L Ch R = 1 ,70309   ,1309,1309,1309
BEGIN DESCRIPTION:
LAKE CREEK 66.0
END DESCRIPTION:
XS GIS Cut Line= 4
       3782727.8     10089010.35      3784003.06     10083217.29
      3783522.06      10082903.6      3784368.26     10080065.58
#Sta/Elev= 30
 -1128.6  180.79    28.7   156.3    84.8  156.25   203.9  156.14   971.1  155.42
  1183.1  155.22  1369.4  154.64  1571.9  155.09  3437.5   145.4  3693.4   155.9
  3730.8  147.49  3774.6   155.6  3857.3  147.05  4256.6     153  4340.4  145.47
  4825.5  144.59  4955.2  153.11 4956.02 151.765  4963.2  139.79  5042.8   151.5
  5630.5  143.49  6061.5     155    6163  157.77  6244.3  159.08  6264.4  160.51
  6467.3   166.8  6873.2  170.95  6974.6  171.23  7828.5  167.99  8338.9  182.37
#Mann= 18 ,-1 , 0
 -1128.6     .17       0    28.7     .15       0    84.8     .17       0
   203.9     .15       0   971.1     .11       0  1183.1     .17       0
  1369.4     .11       0  1571.9     .15       0  4955.2     .12       0
 4956.02     .06       0  5042.8     .15       0  6061.5     .11       0
    6163     .17       0  6244.3     .15       0  6264.4     .17       0
  6467.3     .11       0  6873.2     .17       0  6974.6     .15       0
Bank Sta=4956.02,5042.8
XS Rating Curve= 0 ,0
Exp/Cntr=0.3,0.1

Type RM Length L Ch R = 1 ,69000   ,1183,1183,1183
BEGIN DESCRIPTION:
LAKE CREEK 65.0
END DESCRIPTION:
XS GIS Cut Line= 3
      3782831.95     10089335.93      3784362.54     10082677.69
      3784567.85     10079711.08
#Sta/Elev= 30
 -1831.9  188.74 -1333.1  182.73  -589.4  155.78  -474.5  155.57  -125.5  154.78
   796.2  154.88  1030.1  154.41  1245.6  154.61  2780.2  149.25  2954.6     156
  2985.4  149.11  3082.5   150.7  3125.3  143.52  3334.3  148.03  3349.8  154.34
  3534.9  152.11    3696  152.59  4103.7  146.33  4965.7  147.52  4973.3  139.33
  5018.1  139.33  5036.7  147.11  5208.2  154.22  5404.8  164.48  5601.4  167.59
  7096.4  175.51  7319.7   172.6  7800.7  194.78  7811.3  195.52  7973.7  205.79
#Mann= 18 ,-1 , 0
 -1831.9     .17       0  -589.4     .15       0  -474.5     .17       0
  -125.5     .15       0   796.2     .17       0  1030.1     .11       0
  1245.6     .15       0  3534.9     .11       0    3696     .15       0
  4965.7     .06       0  5036.7     .15       0  5208.2     .17       0
  5404.8     .11       0  5601.4     .15       0  7096.4     .11       0
  7319.7     .15       0  7800.7     .17       0  7811.3     .15       0
Bank Sta=4965.7,5036.7
XS Rating Curve= 0 ,0
Exp/Cntr=0.3,0.1

Type RM Length L Ch R = 1 ,67817   ,1089,1089,1089
BEGIN DESCRIPTION:
LAKE CREEK 64.0
END DESCRIPTION:
XS GIS Cut Line= 3
      3783469.98     10089049.43      3785110.61     10083164.02
      3785826.57     10081315.53
#Sta/Elev= 30
 -1139.1  186.25  -787.8  164.67  -454.3  154.78  -198.1  155.07  1670.6  154.97
  1883.7     155  2440.7  148.54    3510   153.4  3613.8  144.05  3673.3  151.53
  4498.2  151.74    4600  149.89  4651.9  141.98  4693.5   149.7    4818  143.77
  4866.1  149.89    4953  149.75  4972.9   137.7  5017.8   137.7  5027.2   148.9
    5124  144.27  5402.1  159.33  5570.3  164.42  5674.3  164.86  5941.3  167.17
  6481.5  166.93  6500.9  162.57  6530.8   168.3  6609.5   169.3    6953  171.56
#Mann= 12 ,-1 , 0
 -1139.1     .17       0  -198.1     .15       0  1670.6     .11       0
  1883.7     .15       0    4953     .06       0  5027.2     .15       0
  5402.1     .17       0  5570.3     .11       0  5674.3    .125       0
  5941.3     .11       0  6481.5     .17       0  6609.5     .11       0
Bank Sta=4953,5027.2
XS Rating Curve= 0 ,0
Exp/Cntr=0.3,0.1

Type RM Length L Ch R = 1 ,66728   ,1431,1431,1431
BEGIN DESCRIPTION:
LAKE CREEK 63.0
END DESCRIPTION:
XS GIS Cut Line= 3
        3783483.     10089322.87        3785983.     10083880.16
       3785917.9     10080651.03
#Sta/Elev= 30
 -1229.2  193.52 -1225.4   193.5 -1167.7  193.26 -1102.5  191.86  -560.1  160.59
   -41.5  152.68  2030.5  154.41  2177.4  154.34  2395.6   154.3  3420.2  152.68
  3453.5  148.42  3985.2  148.84  4762.3  149.48  4809.3  143.69  4959.3  148.82
  4986.6  137.24  5032.2  137.24  5039.4  149.46  5249.4     143  5339.4   150.9
  5982.9  156.54    6110  158.87  6294.8  162.56  6602.2  168.71  6779.7  160.72
  6995.9  167.93  7178.8  171.68  7560.3  176.11  7980.3  180.99    7990   181.1
#Mann= 20 ,-1 , 0
 -1229.2     .11       0 -1225.4     .17       0 -1167.7     .11       0
 -1102.5     .17       0   -41.5     .15       0  2030.5     .17       0
  2177.4     .11       0  2395.6     .15       0  3453.5     .11       0
  3985.2     .15       0  4959.3     .06       0  5039.4     .15       0
  5982.9     .11       0    6110     .17       0  6294.8     .11       0
  6602.2     .17       0  6995.9    .125       0  7178.8     .11       0
  7560.3     .17       0  7980.3     .11       0
Bank Sta=4959.3,5039.4
XS Rating Curve= 0 ,0
Exp/Cntr=0.3,0.1

Type RM Length L Ch R = 1 ,65297   ,934,934,934
BEGIN DESCRIPTION:
LAKE CREEK 62.0
END DESCRIPTION:
XS GIS Cut Line= 5
      3783756.44     10089257.77      3786751.23     10083541.62
      3786617.85     10082611.07      3786320.76      10082101.9
      3786809.68     10079698.23
#Sta/Elev= 30
       0  188.16   471.2  162.04  1237.3  152.03  1960.6  152.15  2050.9  152.27
  3420.5  152.46  3508.7  151.79    4354  147.92  4385.1  151.95  4600.1  145.62
  5437.7  149.16  5620.1  145.29  5686.3  144.46  5697.1  145.28  5768.9  153.46
  5983.9  147.42  6347.7  146.45  6397.5  149.93  6413.9  146.64  6419.9  139.62
  6450.6  138.59  6494.1  148.94  6908.3  144.06  7216.7  165.04  7383.1  168.76
  7948.9  169.14  8345.1  158.07  9136.7  182.94  9397.4  196.62 10435.6   220.1
#Mann= 11 ,-1 , 0
       0     .17       0   471.2     .15       0  1960.6     .11       0
  2050.9     .15       0  3420.5     .11       0  3508.7     .15       0
  5620.1     .11       0  5686.3     .15       0  5697.1     .11       0
  6397.5     .06       0  6494.1     .15       0
Bank Sta=6397.5,6494.1
XS Rating Curve= 0 ,0
Exp/Cntr=0.3,0.1

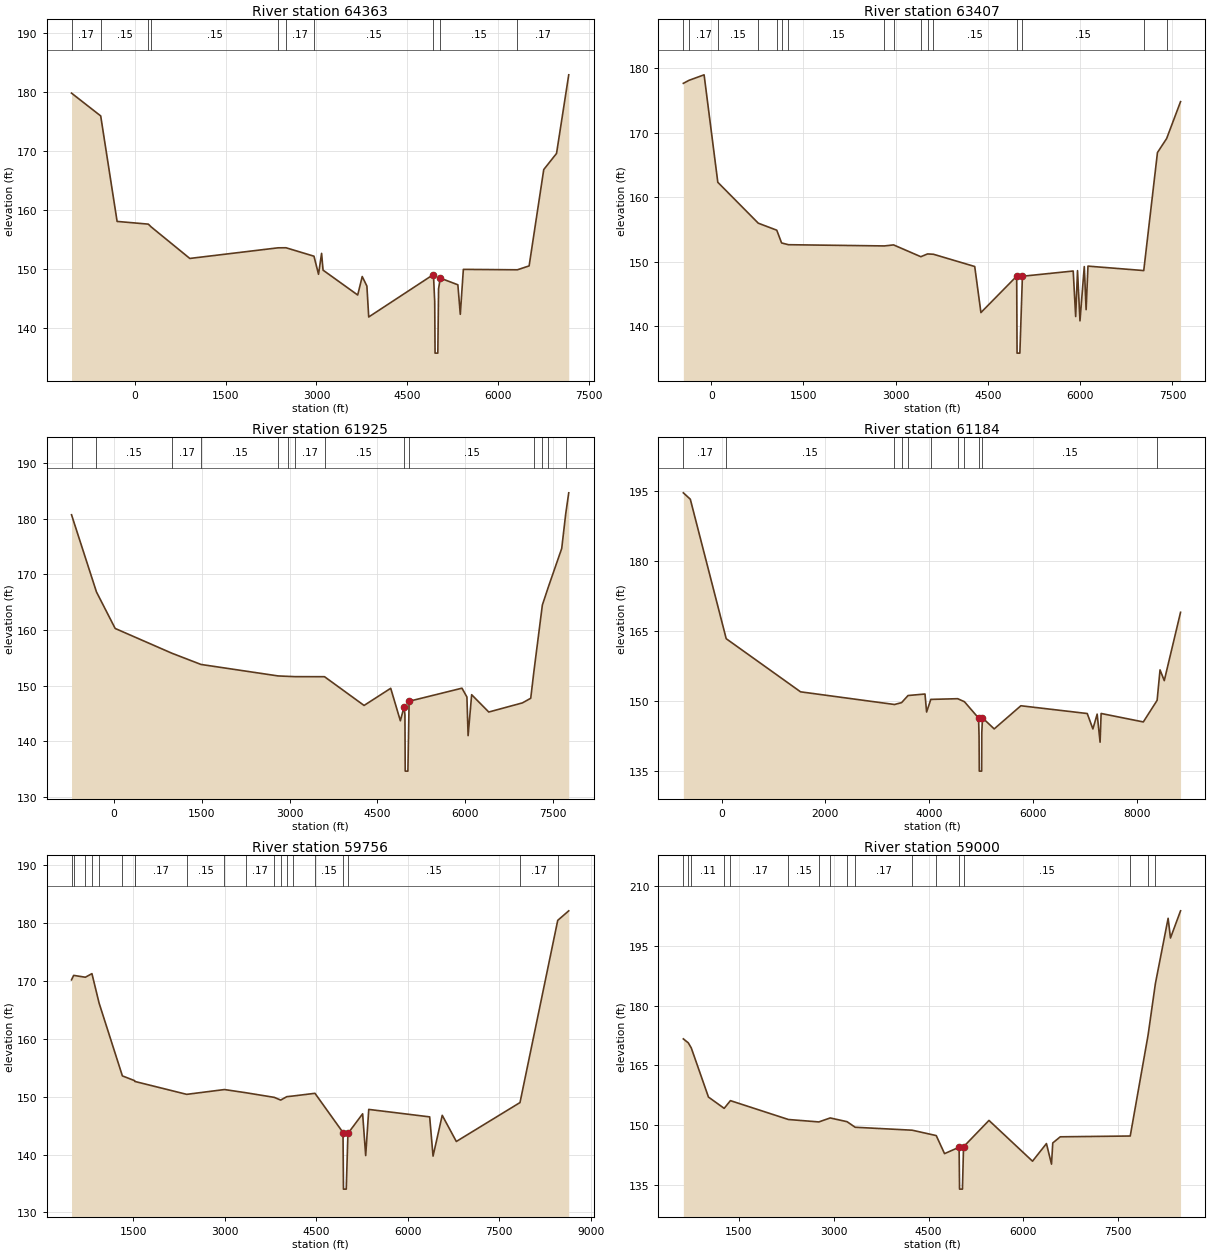
Type RM Length L Ch R = 1 ,64363   ,956,956,956
BEGIN DESCRIPTION:
LAKE CREEK 61.0
END DESCRIPTION:
XS GIS Cut Line= 4
      3786100.18     10089765.62      3786998.63     10084023.39
      3787311.13     10083749.95       3787545.5     10081770.82
#Sta/Elev= 30
 -1049.9  179.84  -567.6  175.98  -296.3  158.12   220.2  157.66   264.3  157.21
   905.6  151.85  2365.1  153.65  2496.1  153.66  2958.7  152.23  3033.7  149.17
  3084.3  152.71  3108.6  149.87  3681.5  145.66    3756  148.79  3833.3  147.18
  3863.7  141.94  4933.8  149.13  4954.7  144.52  4960.4  135.82    5006  135.82
  5018.3  146.71  5046.8  148.52  5337.4  147.39  5377.7  142.39  5428.1     150
  6321.6  149.93  6515.6  150.59  6757.3   166.9  6968.7  169.63  7170.4  182.94
#Mann= 10 ,-1 , 0
 -1049.9     .17       0  -567.6     .15       0   220.2     .11       0
   264.3     .15       0  2365.1     .11       0  2496.1     .17       0
  2958.7     .15       0  4933.8     .06       0  5046.8     .15       0
  6321.6     .17       0
Bank Sta=4933.8,5046.8
XS Rating Curve= 0 ,0
Exp/Cntr=0.3,0.1

Type RM Length L Ch R = 1 ,63407   ,1482,1482,1482
BEGIN DESCRIPTION:
LAKE CREEK 60.0
END DESCRIPTION:
XS GIS Cut Line= 4
      3786308.52     10089635.35      3787024.67       10084401.
      3787597.58     10083945.27      3787597.58     10081875.55
#Sta/Elev= 30
  -453.6  177.65  -360.9  178.12  -116.2  178.97   106.8  162.31   764.4  155.97
  1065.3  154.88  1144.1   152.9  1255.1  152.63  2815.5  152.44  2964.4   152.6
  3407.9  150.77  3517.7   151.2  3613.1  151.15  4284.4  149.25  4385.3  142.11
  4966.8  147.75  4972.8  135.82  5018.5  135.82  5059.8  147.74  5885.8  148.55
  5925.8  141.49  5955.8  148.61  5995.8  140.82  6065.8  149.24  6095.8  142.56
  6125.8  149.31  7032.9  148.62  7255.8  166.92  7404.9  169.09  7631.3  174.81
#Mann= 16 ,-1 , 0
  -453.6     .15       0  -360.9     .17       0   106.8     .15       0
   764.4     .11       0  1065.3     .15       0  1144.1     .11       0
  1255.1     .15       0  2815.5     .11       0  2964.4     .17       0
  3407.9     .15       0  3517.7     .17       0  3613.1     .15       0
  4966.8     .06       0  5059.8     .15       0  7032.9     .11       0
  7404.9     .17       0
Bank Sta=4966.8,5059.8
XS Rating Curve= 0 ,0
Exp/Cntr=0.3,0.1

Type RM Length L Ch R = 1 ,61925   ,741,741,741
BEGIN DESCRIPTION:
LAKE CREEK 59.0
END DESCRIPTION:
XS GIS Cut Line= 4
      3786790.28      10090065.1      3787766.86     10084622.35
      3787988.21     10084335.89      3787636.64     10081757.74
#Sta/Elev= 30
  -725.4  180.67  -299.5  166.82    20.3  160.26   990.4  155.81  1486.5   153.8
  2802.5  151.74  2974.9  151.66  3088.8  151.61  3596.5   151.6  4272.1  146.44
  4727.2  149.52  4891.9  143.69  4956.2  146.19  4970.2  144.74    4975  134.65
  5020.7  134.65  5041.4  147.19  5944.6  149.54    6029  147.96  6049.2  141.02
  6109.8  148.37  6402.4  145.26  6977.4   146.9    7119  147.73    7174   152.6
  7317.8  164.47  7417.5  167.63  7648.6  174.63  7716.8  180.84  7768.3  184.61
#Mann= 14 ,-1 , 0
  -725.4     .17       0  -299.5     .15       0   990.4     .17       0
  1486.5     .15       0  2802.5     .17       0  2974.9     .11       0
  3088.8     .17       0  3596.5     .15       0  4956.2     .06       0
  5041.4     .15       0    7174     .11       0  7317.8     .17       0
  7417.5     .11       0  7716.8     .17       0
Bank Sta=4956.2,5041.4
XS Rating Curve= 0 ,0
Exp/Cntr=0.3,0.1

Type RM Length L Ch R = 1 ,61184   ,1428,1428,1428
BEGIN DESCRIPTION:
LAKE CREEK 58.0
END DESCRIPTION:
XS GIS Cut Line= 3
      3786817.85     10090611.09      3788248.63     10085065.06
      3789199.15     10081328.06
#Sta/Elev= 30
  -735.9  194.56  -601.6  193.19    90.4  163.36  1523.3     152  3333.9  149.29
  3470.9  149.69  3595.5  151.21  3921.8  151.53  3952.8  147.68  4033.9  150.38
  4552.1  150.53  4681.6  149.89  4954.5  146.39  4964.1  142.47  4968.3  135.04
    5014  135.04  5016.5  143.19  5029.7146.4388  5255.6  144.07  5769.7  149.02
  7049.2  147.36  7158.2  144.06  7240.1  147.23  7296.8  141.23  7316.7  147.37
    8130  145.56    8396  150.18  8452.2  156.69    8534   154.4  8847.7  169.01
#Mann= 11 ,-1 , 0
  -735.9     .17       0    90.4     .15       0  3333.9     .17       0
  3470.9     .11       0  3595.5     .17       0  4033.9     .15       0
  4552.1     .11       0  4681.6     .15       0  4954.5     .06       0
  5029.7     .15       0    8396     .17       0
Bank Sta=4954.5,5029.7
XS Rating Curve= 0 ,0
Exp/Cntr=0.3,0.1

Type RM Length L Ch R = 1 ,59756   ,756,756,756
BEGIN DESCRIPTION:
LAKE CREEK 57.0
END DESCRIPTION:
XS GIS Cut Line= 3
      3789693.93     10089199.14      3789075.45     10084728.69
      3789390.05     10081105.35
#Sta/Elev= 30
   491.4  170.18   526.6  170.95   718.4  170.63     826  171.25   943.2  166.17
    1325  153.59  1524.6  152.77  1529.1  152.63    2379   150.4  2998.8  151.23
  3349.1  150.68  3814.9  149.88  3919.9  149.41  4019.7     150  4119.5  150.11
  4481.7  150.58  4941.5  143.81  4948.8  134.03  4994.6  134.03  5022.1  143.64
    5263  147.04  5313.2  139.82  5363.4   147.8  6361.9  146.51  6417.3  139.73
  6567.9  146.78  6798.8  142.26  7842.5  148.98    8461  180.45  8641.4   182.1
#Mann= 20 ,-1 , 0
   491.4    .125       0   526.6     .11       0   718.4     .17       0
     826     .11       0   943.2     .17       0    1325     .15       0
  1524.6     .15       0  1529.1     .17       0    2379     .15       0
  2998.8     .11       0  3349.1     .17       0  3814.9     .15       0
  3919.9     .17       0  4019.7     .11       0  4119.5     .17       0
  4481.7     .15       0  4941.5     .06       0  5022.1     .15       0
  7842.5     .17       0    8461     .11       0
Bank Sta=4941.5,5022.1
XS Rating Curve= 0 ,0
Exp/Cntr=0.3,0.1

Type RM Length L Ch R = 1 ,59000   ,1177,1177,1177
BEGIN DESCRIPTION:
LAKE CREEK 56.0
END DESCRIPTION:
XS GIS Cut Line= 3
      3789815.47     10088927.93      3789578.91     10084553.72
      3789763.38       10081072.
#Sta/Elev= 30
   619.4  171.67   697.7  170.68   745.4  169.38  1016.8  157.05  1265.5  154.21
  1364.2  156.15  2281.9  151.41  2763.2   150.8  2943.2   151.8  3209.9  150.86
  3337.9  149.46  4240.7  148.72  4620.8  147.37  4752.3  142.83  4982.6  144.44
  4989.8  133.91  5035.6  133.91  5052.7  144.55  5455.4  151.18  6144.2  140.93
  6364.6  145.36  6444.7  140.19  6464.7  145.52  6583.2  147.06  7690.5  147.26
    7973  172.65  8088.1  185.54  8289.9  201.98  8327.3  197.03  8486.6  203.86
#Mann= 17 ,-1 , 0
   619.4     .11       0   697.7     .17       0   745.4     .11       0
  1265.5     .15       0  1364.2     .17       0  2281.9     .15       0
  2763.2     .11       0  2943.2    .125       0  3209.9     .11       0
  3337.9     .17       0  4240.7     .11       0  4620.8     .15       0
  4982.6     .06       0  5052.7     .15       0  7690.5     .11       0
    7973     .17       0  8088.1     .11       0
Bank Sta=4982.6,5052.7
XS Rating Curve= 0 ,0
Exp/Cntr=0.3,0.1

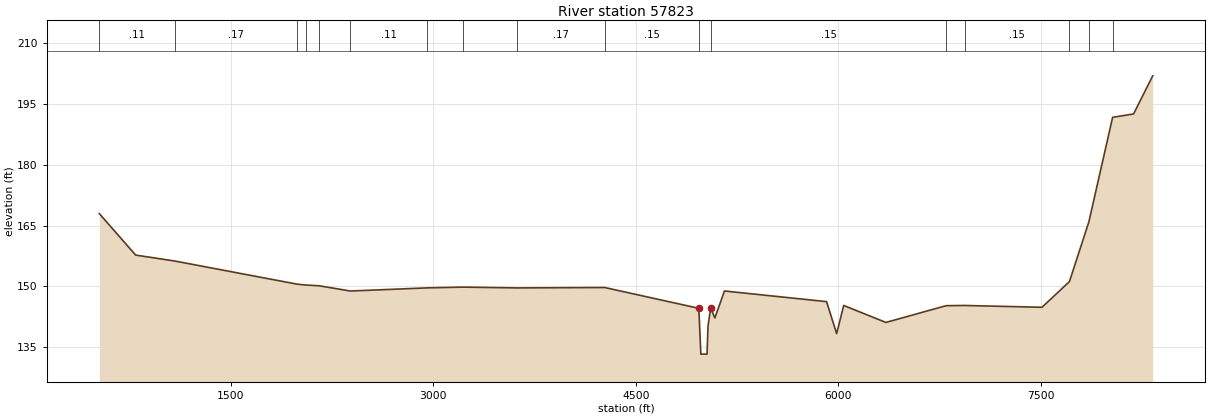
Type RM Length L Ch R = 1 ,57823   ,821,821,821
BEGIN DESCRIPTION:
LAKE CREEK 55.0
END DESCRIPTION:
XS GIS Cut Line= 3
      3790008.61     10088851.99      3790410.08     10084381.46
      3789867.84     10081111.03
#Sta/Elev= 30
   526.7  167.96   795.7  157.71  1087.5  156.23  1990.1  150.54  2055.1  150.31
  2154.1  150.13  2386.4  148.83    2957  149.61  3220.7   149.8  3620.1   149.6
  4269.9   149.7  4967.8144.5593  4982.7  133.24  5028.5  133.24  5035.9   140.2
  5055.3  144.63  5086.6  142.18  5157.5  148.84    5914  146.21  5988.7   138.3
    6041  145.26  6353.6  141.07    6800  145.21  6938.1  145.26  7509.6  144.81
    7713  151.15  7857.1  165.91  8033.1  191.75  8188.3  192.58  8330.3     202
#Mann= 17 ,-1 , 0
   526.7     .11       0  1087.5     .17       0  1990.1     .15       0
  2055.1     .17       0  2154.1     .15       0  2386.4     .11       0
    2957     .17       0  3220.7     .15       0  3620.1     .17       0
  4269.9     .15       0  4967.8     .06       0  5055.3     .15       0
    6800     .11       0  6938.1     .15       0    7713     .11       0
  7857.1     .17       0  8033.1     .11       0
Bank Sta=4967.8,5055.3
XS Rating Curve= 0 ,0
Exp/Cntr=0.3,0.1