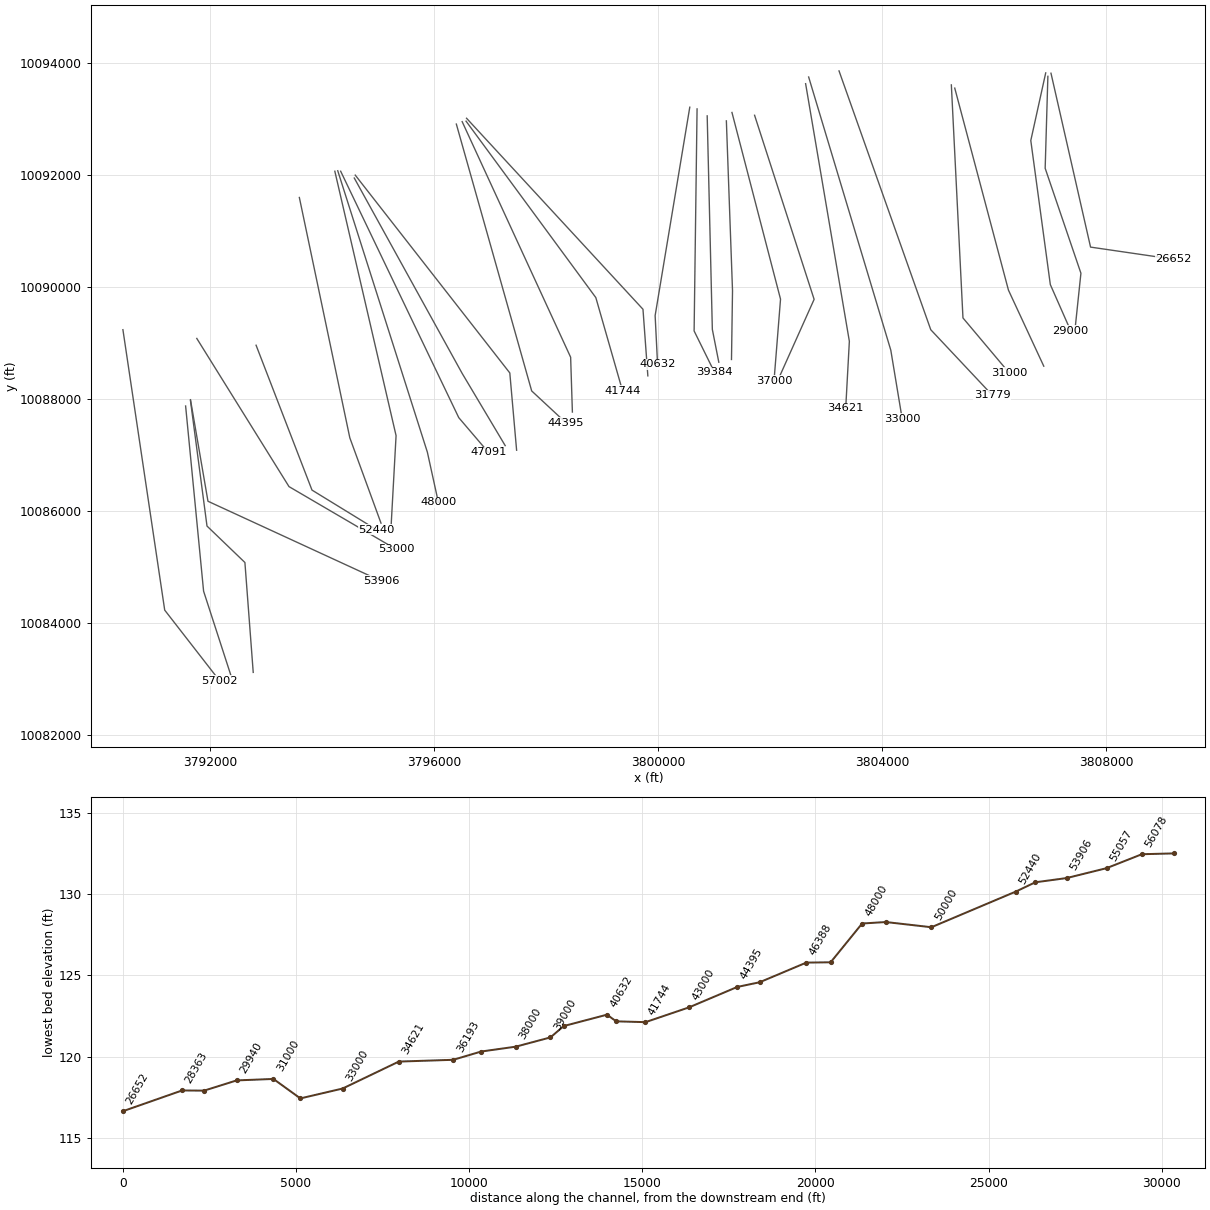
HEC-RAS study LAKE CREEK.prj: LAKE CREEK Base Level Engineering

--- LAKE CREEK.g01 (geometry) --- (continued)

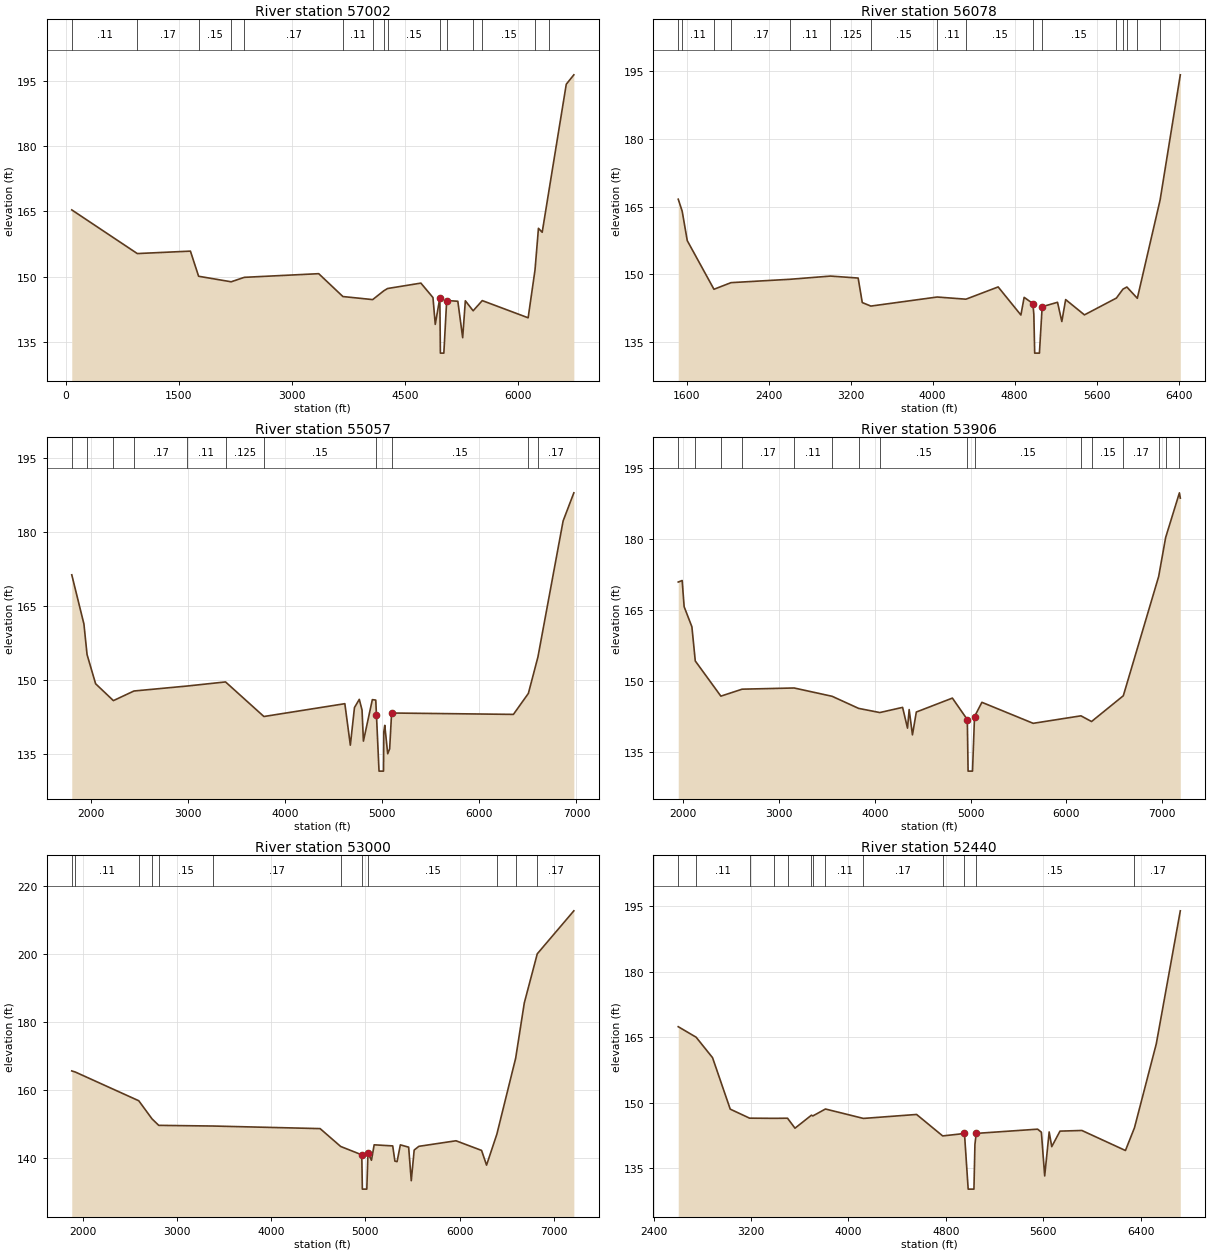
Type RM Length L Ch R = 1 ,57002   ,924,924,924
BEGIN DESCRIPTION:
LAKE CREEK 54.0
END DESCRIPTION:
XS GIS Cut Line= 3
      3790440.46     10089231.76      3791186.99     10084223.04
      3792167.87     10082961.05
#Sta/Elev= 30
    81.4  165.35   951.1  155.34    1656   155.9  1764.5  150.14  2196.3  148.87
  2370.6  149.89  3358.3  150.73  3679.1  145.49  4074.6  144.79  4222.8  146.82
  4272.3  147.33    4714  148.57  4874.5  145.26  4904.8  139.11  4965.5  145.17
  4972.9  132.52  5018.7  132.52  5056.4  144.58  5204.4  144.41  5268.7  136.05
    5304  144.52  5407.6  142.23  5528.6  144.56  6137.4  140.62  6228.5  151.57
  6274.1  161.13  6323.9  160.22  6420.1  170.47  6643.3  194.15  6743.8  196.31
#Mann= 15 ,-1 , 0
    81.4     .11       0   951.1     .17       0  1764.5     .15       0
  2196.3     .11       0  2370.6     .17       0  3679.1     .11       0
  4074.6     .15       0  4222.8     .11       0  4272.3     .15       0
  4965.5     .06       0  5056.4     .15       0  5407.6     .11       0
  5528.6     .15       0  6228.5     .17       0  6420.1     .11       0
Bank Sta=4965.5,5056.4
XS Rating Curve= 0 ,0
Exp/Cntr=0.3,0.1

Type RM Length L Ch R = 1 ,56078   ,1021,1021,1021
BEGIN DESCRIPTION:
LAKE CREEK 53.0
END DESCRIPTION:
XS GIS Cut Line= 3
      3791560.26     10087868.88      3791881.44     10084561.59
      3792367.84      10083061.1
#Sta/Elev= 30
  1517.3  166.63  1555.7  163.98  1605.5  157.43    1866  146.64  2032.4  148.11
  2609.6  148.86  3003.3  149.57  3273.3  149.13  3313.5  143.69  3397.1  142.91
  4044.4  144.92  4325.2  144.44  4639.7  147.16  4861.7  140.93  4893.3  144.85
  4978.5  143.47  4987.9  141.08  4996.3  132.47  5042.4  132.47  5069.2  142.77
  5219.1  143.75  5261.1  139.48  5298.4  144.35  5481.9  140.96  5793.8  144.69
  5857.8  146.67  5895.9  147.14    5998  144.64  6220.6  166.49  6417.5  194.23
#Mann= 16 ,-1 , 0
  1517.3     .17       0  1555.7     .11       0    1866     .15       0
  2032.4     .17       0  2609.6     .11       0  3003.3    .125       0
  3397.1     .15       0  4044.4     .11       0  4325.2     .15       0
  4978.5     .06       0  5069.2     .15       0  5793.8     .11       0
  5857.8     .15       0  5895.9     .11       0    5998     .17       0
  6220.6     .11       0
Bank Sta=4978.5,5069.2
XS Rating Curve= 0 ,0
Exp/Cntr=0.3,0.1

Type RM Length L Ch R = 1 ,55057   ,1151,1151,1151
BEGIN DESCRIPTION:
LAKE CREEK 52.0
END DESCRIPTION:
XS GIS Cut Line= 4
      3791647.06     10087964.39       3791942.2     10085724.78
      3792619.29     10085073.74      3792767.85     10083111.03
#Sta/Elev= 30
  1806.2   171.4  1931.3  161.43  1963.6  155.23  2051.6  149.32  2234.6   145.9
  2445.8  147.85  2993.8  148.86  3388.6  149.69  3783.3  142.68  4616.3  145.28
  4672.9  136.87  4715.3  144.49    4765  146.16  4793.3  143.99  4807.4  137.69
  4899.3   146.1  4934.5  146.01  4941.7  142.95  4968.1  131.61  5014.2  131.61
  5017.2  139.57  5027.2  140.89  5057.3  135.13  5077.4  136.13  5097.4  143.39
    6351  143.11    6505  147.37  6603.4  154.76  6862.4  182.32  6972.8  188.02
#Mann= 11 ,-1 , 0
  1806.2     .17       0  1963.6     .11       0  2234.6     .15       0
  2445.8     .17       0  2993.8     .11       0  3388.6    .125       0
  3783.3     .15       0  4941.7     .06       0  5097.4     .15       0
    6505     .11       0  6603.4     .17       0
Bank Sta=4941.7,5097.4
XS Rating Curve= 0 ,0
Exp/Cntr=0.3,0.1

Type RM Length L Ch R = 1 ,53906   ,906,906,906
BEGIN DESCRIPTION:
LAKE CREEK 51.0
END DESCRIPTION:
XS GIS Cut Line= 3
      3791647.07      10087981.7      3791959.56     10086167.49
      3795049.89     10084743.86
#Sta/Elev= 30
  1946.1  170.87  1987.3  171.19  2007.6  165.68  2088.8  161.43  2124.1  154.23
  2391.4  146.81  2613.6  148.28  3156.5  148.53    3553  146.78    3830  144.23
  4051.1  143.35  4289.2  144.44  4340.6  140.06  4357.7  143.98  4392.1  138.65
  4432.5  143.46  4809.1   146.4  4965.1  141.87  4973.2     131  5019.3     131
  5040.3  142.49  5117.4  145.51    5653  141.08  6151.9  142.66  6262.5  141.46
  6594.2  146.89  6963.2  172.02  7036.5  180.27  7180.2  189.68  7189.5  188.56
#Mann= 16 ,-1 , 0
  1946.1     .17       0  2124.1     .11       0  2391.4     .15       0
  2613.6     .17       0  3156.5     .11       0    3553    .125       0
    3830     .11       0  4051.1     .15       0  4965.1     .06       0
  5040.3     .15       0  6151.9     .11       0  6262.5     .15       0
  6594.2     .17       0  6963.2     .11       0  7036.5     .17       0
  7180.2     .11       0
Bank Sta=4965.1,5040.3
XS Rating Curve= 0 ,0
Exp/Cntr=0.3,0.1

Type RM Length L Ch R = 1 ,53000   ,560,560,560
BEGIN DESCRIPTION:
LAKE CREEK 50.0
END DESCRIPTION:
XS GIS Cut Line= 3
       3791759.9     10089075.49      3793406.89     10086429.03
      3795317.89     10085311.05
#Sta/Elev= 30
  1882.9  165.53  1920.8   165.2  2594.3  156.75    2735  151.42  2806.1  149.51
  3386.2  149.31  4519.9  148.55  4737.9   143.3  4962.3  140.83  4968.4  130.74
  5015.7  130.74  5027.9  141.36  5065.1  139.24  5093.8  143.78  5290.8  143.46
  5313.9  138.98  5336.9  138.83  5371.9  143.77    5460  143.09  5487.7  133.21
  5518.7  142.25  5568.8  143.34  5962.7  144.97  6234.3  142.13  6287.1   137.8
  6396.5   146.9  6596.3  169.29    6688  185.55  6825.7     200    7214  212.65
#Mann= 12 ,-1 , 0
  1882.9     .17       0  1920.8     .11       0  2594.3     .17       0
    2735     .11       0  2806.1     .15       0  3386.2     .17       0
  4737.9     .15       0  4962.3     .06       0  5027.9     .15       0
  6396.5     .17       0  6596.3     .11       0  6825.7     .17       0
Bank Sta=4962.3,5027.9
XS Rating Curve= 0 ,0
Exp/Cntr=0.3,0.1

Type RM Length L Ch R = 1 ,52440   ,2440,2440,2440
BEGIN DESCRIPTION:
LAKE CREEK 49.0
END DESCRIPTION:
XS GIS Cut Line= 3
      3792818.93     10088953.96       3793817.2     10086367.14
      3794967.88     10085661.05
#Sta/Elev= 30
  2602.1  167.39  2749.1  164.98  2883.9  160.29  3029.1   148.5  3187.9  146.43
  3391.5  146.39  3499.5  146.42  3560.9  144.13  3695.7  147.11  3707.2  146.94
  3811.1  148.53  4122.7  146.37  4559.3  147.28  4773.5  142.36  4952.6  142.92
    4983  130.17  5030.3  130.17  5038.4  140.43  5049.1  142.94  5553.2  143.91
  5584.1  143.21  5611.2  133.19    5648  143.27  5669.3  139.91  5736.8  143.46
  5916.7  143.61  6274.4  139.02  6348.7  144.25  6527.7  163.47  6724.9  193.94
#Mann= 13 ,-1 , 0
  2602.1     .17       0  2749.1     .11       0  3187.9     .17       0
  3391.5     .15       0  3499.5     .11       0  3695.7     .17       0
  3707.2     .15       0  3811.1     .11       0  4122.7     .17       0
  4773.5     .15       0  4952.6     .06       0  5049.1     .15       0
  6348.7     .17       0
Bank Sta=4952.6,5049.1
XS Rating Curve= 0 ,0
Exp/Cntr=0.3,0.1

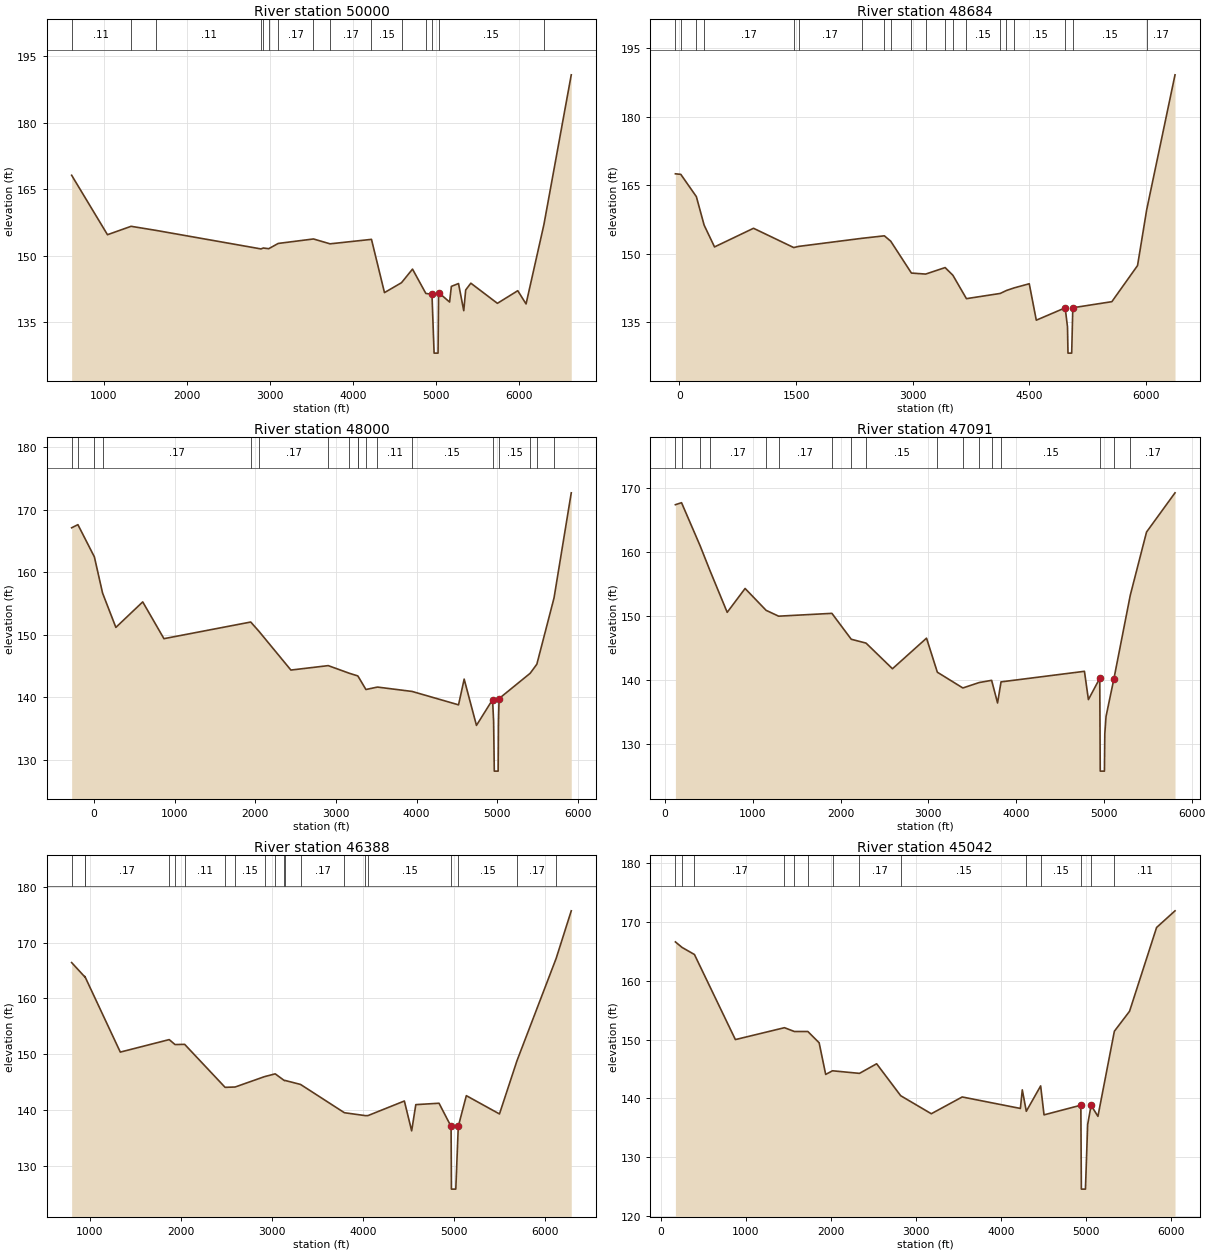
Type RM Length L Ch R = 1 ,50000   ,1316,1316,1316
BEGIN DESCRIPTION:
LAKE CREEK 48.0
END DESCRIPTION:
XS GIS Cut Line= 3
      3793591.52      10091592.8      3794492.58     10087301.69
      3795049.86     10085776.82
#Sta/Elev= 30
   615.3  168.15  1046.2  154.72  1330.3  156.62  1629.4   155.7  2892.2  151.51
  2920.4  151.72  2984.7  151.56  3099.7  152.75  3523.3  153.76  3722.6  152.66
    4221  153.67  4377.3  141.64  4582.1  143.88  4714.5  146.95  4874.8  141.45
  4948.5  141.27    4974  127.97  5021.6  127.97  5028.1141.6578  5160.4  139.51
  5181.7  143.05  5267.6  143.69  5330.7  137.56  5353.9  142.24  5415.9  143.77
  5735.3  139.22  5980.2  142.07    6080  139.08  6294.7  157.02  6623.5  190.84
#Mann= 15 ,-1 , 0
   615.3     .11       0  1330.3     .17       0  1629.4     .11       0
  2892.2     .15       0  2920.4     .17       0  2984.7     .11       0
  3099.7     .17       0  3523.3     .11       0  3722.6     .17       0
    4221     .15       0  4582.1     .17       0  4874.8     .15       0
  4948.5     .06       0  5028.1     .15       0  6294.7     .17       0
Bank Sta=4948.5,5028.1
XS Rating Curve= 0 ,0
Exp/Cntr=0.3,0.1

Type RM Length L Ch R = 1 ,48684   ,684,684,684
BEGIN DESCRIPTION:
LAKE CREEK 47.0
END DESCRIPTION:
XS GIS Cut Line= 3
      3794225.19     10092061.59      3795318.94     10087339.36
      3795232.13     10085759.48
#Sta/Elev= 30
   -52.3  167.53    17.2  167.41   217.2  162.54   317.3   156.3   451.2  151.53
   952.8  155.61  1470.5  151.39  1532.2  151.64  2345.9  153.41  2636.6  153.96
  2718.5  152.79    2985  145.81    3168  145.59  3418.8  147.01  3518.9  145.32
  3692.9  140.21  4127.9  141.35  4208.3     142  4307.4  142.57  4501.3  143.47
  4591.9   135.5  4963.5   138.2  4993.5  134.03  4999.8  128.29  5047.4  128.29
  5061.8 138.217  5564.4  139.55  5894.9  147.45    6012  159.61  6377.2  189.19
#Mann= 20 ,-1 , 0
   -52.3     .11       0    17.2     .17       0   217.2     .11       0
   317.3     .17       0  1470.5     .11       0  1532.2     .17       0
  2345.9     .11       0  2636.6     .17       0  2718.5     .11       0
    2985     .17       0    3168     .11       0  3418.8     .15       0
  3518.9     .17       0  3692.9     .15       0  4127.9     .17       0
  4208.3     .11       0  4307.4     .15       0  4963.5     .06       0
  5061.8     .15       0    6012     .17       0
Bank Sta=4963.5,5061.8
XS Rating Curve= 0 ,0
Exp/Cntr=0.3,0.1

Type RM Length L Ch R = 1 ,48000   ,909,909,909
BEGIN DESCRIPTION:
LAKE CREEK 46.0
END DESCRIPTION:
XS GIS Cut Line= 3
      3794277.29     10092070.22      3795877.87     10087044.02
      3796074.15     10086150.11
#Sta/Elev= 30
  -274.9  167.11  -197.3  167.61     6.6  162.46   108.6  156.66     273  151.18
   605.8  155.26   868.7  149.38  1943.8  152.04  2045.7  150.56  2441.5  144.36
  2904.1  145.07  3167.3  143.84  3269.2  143.43  3273.7  143.37  3371.2  141.25
  3513.9  141.64  3943.7  140.94  4518.6   138.8  4588.3  142.91  4740.7  135.51
  4940.1  139.63  4953.2  136.19  4961.6   128.2  5009.3   128.2  5013.3  135.98
  5020.8   139.8  5405.7  143.84    5489   145.3  5701.7  155.89  5915.2   172.7
#Mann= 18 ,-1 , 0
  -274.9     .11       0  -197.3     .17       0     6.6     .11       0
   108.6     .17       0  1943.8     .11       0  2045.7     .17       0
  2904.1     .15       0  3167.3     .11       0  3269.2     .15       0
  3273.7     .11       0  3371.2     .15       0  3513.9     .11       0
  3943.7     .15       0  4940.1     .06       0  5020.8     .15       0
  5405.7     .17       0    5489     .15       0  5701.7     .17       0
Bank Sta=4940.1,5020.8
XS Rating Curve= 0 ,0
Exp/Cntr=0.3,0.1

Type RM Length L Ch R = 1 ,47091   ,703,703,703
BEGIN DESCRIPTION:
LAKE CREEK 45.0
END DESCRIPTION:
XS GIS Cut Line= 3
      3794329.35      10092061.6      3796438.73     10087660.54
       3796966.3     10087042.17
#Sta/Elev= 30
   117.2  167.37   187.2  167.68   401.3  160.88   508.4  157.18   707.4  150.58
   911.3   154.3  1150.9  150.89  1293.5  149.98  1900.4  150.42    2121  146.38
  2289.5  145.78  2590.7  141.78  2978.8  146.55  3102.1  141.24  3392.7  138.78
  3579.3  139.63  3720.7  139.97  3788.3  136.44  3827.8  139.73  4778.3  141.38
  4823.6  136.97  4952.7  140.28  4958.3  125.81  5006.1  125.81  5010.3  131.61
  5024.6  134.35 5114.56140.2453  5300.7  153.25  5485.8   163.1  5810.5  169.22
#Mann= 17 ,-1 , 0
   117.2     .11       0   187.2     .17       0   401.3     .11       0
   508.4     .17       0  1150.9     .11       0  1293.5     .17       0
  1900.4     .11       0    2121     .17       0  2289.5     .15       0
  3102.1     .17       0  3392.7     .15       0  3579.3     .17       0
  3720.7     .11       0  3827.8     .15       0  4952.7     .06       0
 5114.56     .15       0  5300.7     .17       0
Bank Sta=4952.7,5114.56
XS Rating Curve= 0 ,0
Exp/Cntr=0.3,0.1

Type RM Length L Ch R = 1 ,46388   ,1346,1346,1346
BEGIN DESCRIPTION:
LAKE CREEK 44.0
END DESCRIPTION:
XS GIS Cut Line= 3
      3794572.42     10091940.04      3796499.49     10088450.47
      3797267.86     10087161.06
#Sta/Elev= 30
   801.1  166.41   945.9  163.84   946.6  163.92  1335.5  150.36  1872.7   152.6
  1936.6  151.71  2042.3  151.75  2486.6  144.04  2596.6   144.1  2919.5  145.96
  3036.6  146.46  3138.7  145.24  3146.6  145.27  3315.2  144.56  3796.6  139.49
  4025.1  138.97  4054.8  138.97  4455.4  141.59  4535.4  136.24  4581.1  140.94
  4836.1  141.19  4968.5  137.02  4972.4  125.79  5020.2  125.79  5047.6137.0261
  5135.9  142.55  5499.9  139.27  5692.2  148.81  6122.3  167.15  6288.4  175.69
#Mann= 20 ,-1 , 0
   801.1     .17       0   945.9     .11       0   946.6     .17       0
  1872.7     .11       0  1936.6     .17       0  2042.3     .11       0
  2486.6     .17       0  2596.6     .15       0  2919.5     .11       0
  3036.6     .17       0  3138.7     .11       0  3146.6     .15       0
  3315.2     .17       0  3796.6     .15       0  4025.1     .17       0
  4054.8     .15       0  4968.5     .06       0  5047.6     .15       0
  5692.2     .17       0  6122.3     .11       0
Bank Sta=4968.5,5047.6
XS Rating Curve= 0 ,0
Exp/Cntr=0.3,0.1

Type RM Length L Ch R = 1 ,45042   ,647,647,647
BEGIN DESCRIPTION:
LAKE CREEK 43.0
END DESCRIPTION:
XS GIS Cut Line= 3
      3794589.76     10091992.16      3797350.19     10088459.15
      3797471.72     10087078.93
#Sta/Elev= 30
   172.8  166.59     251  165.65   396.4  164.45   877.4  149.99  1453.8  152.01
  1571.3  151.36  1729.2  151.36  1861.3  149.45  1938.2  144.07  2018.6  144.69
    2335  144.25  2536.9  145.88  2819.6  140.45    3179  137.39  3541.7  140.24
  4225.4  138.29  4247.8  141.45  4294.9  137.81  4463.4  142.12  4503.1   137.2
  4935.5  138.84  4941.7  124.58  4989.5  124.58  5015.8  135.56    5056  138.82
  5136.3  136.95  5329.4  151.41  5507.7   154.8  5825.4  169.04  6041.9  171.87
#Mann= 14 ,-1 , 0
   172.8     .17       0     251     .11       0   396.4     .17       0
  1453.8     .11       0  1571.3     .17       0  1729.2     .11       0
  2018.6     .15       0    2335     .17       0  2819.6     .15       0
  4294.9     .11       0  4463.4     .15       0  4935.5     .06       0
    5056     .15       0  5329.4     .11       0
Bank Sta=4935.5,5056
XS Rating Curve= 0 ,0
Exp/Cntr=0.3,0.1

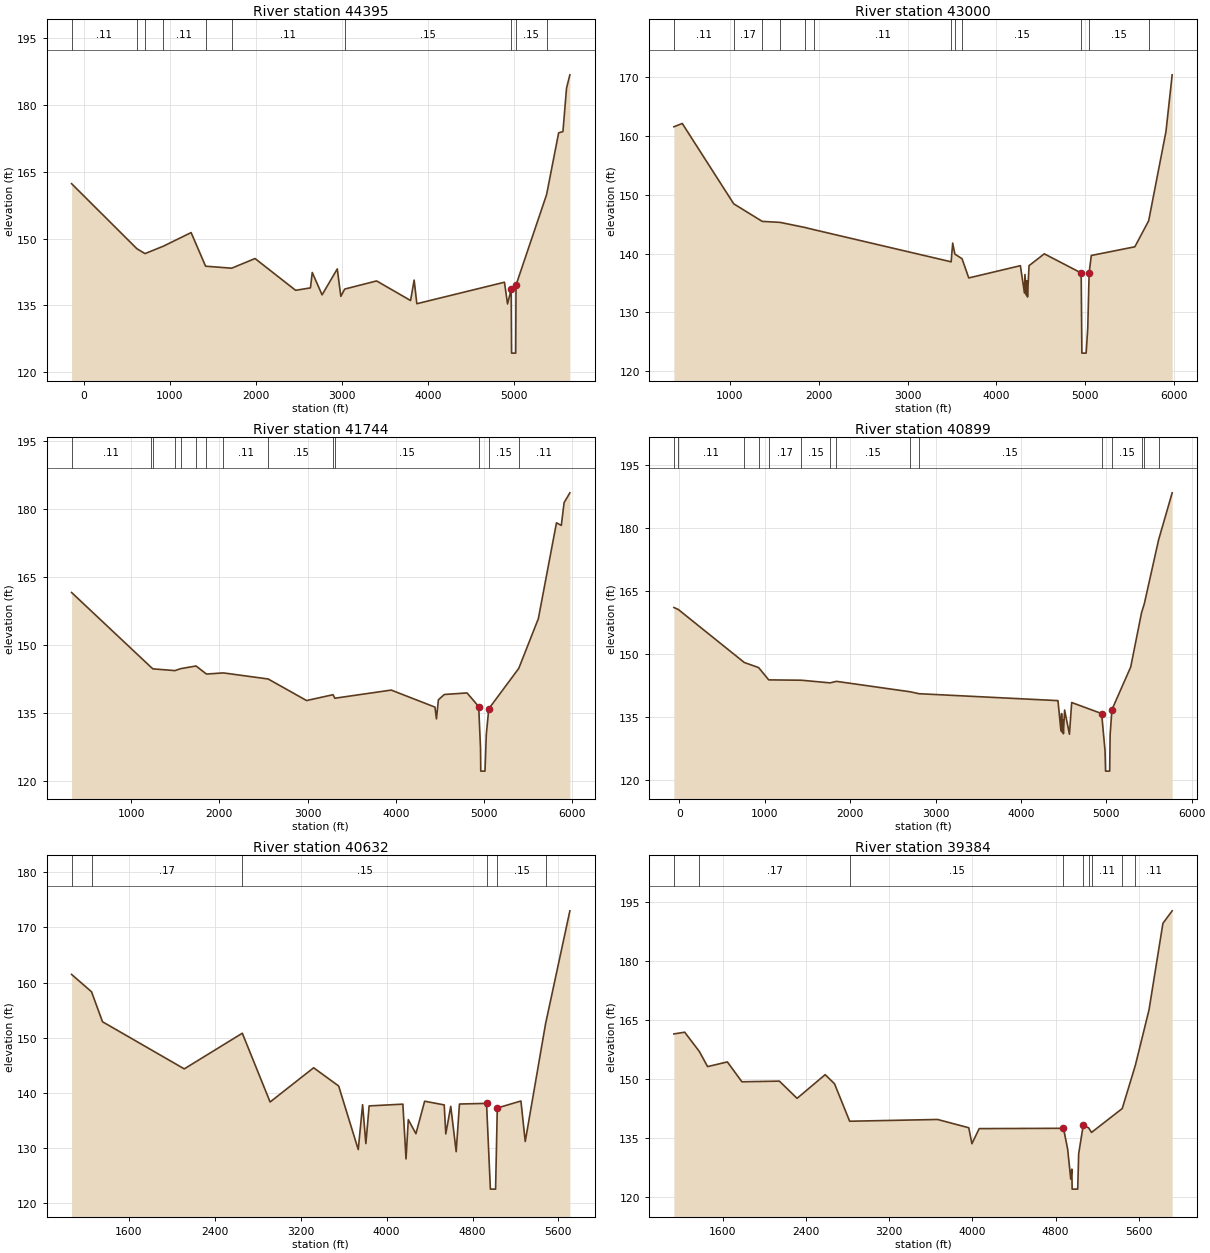
Type RM Length L Ch R = 1 ,44395   ,1395,1395,1395
BEGIN DESCRIPTION:
LAKE CREEK 42.0
END DESCRIPTION:
XS GIS Cut Line= 3
      3796395.32     10092903.63      3797740.81     10088137.97
       3798356.6     10087565.56
#Sta/Elev= 30
  -140.8  162.36   618.7  147.74   712.9  146.65   923.6  148.29  1248.9  151.37
    1417  143.82  1720.2  143.37    1992  145.54    2464   138.4  2636.2  138.95
    2657  142.41  2771.3  137.38    2948  143.21  2989.5  137.05  3034.3  138.68
  3405.2  140.51    3800  136.11  3841.6   140.7  3872.8  135.39  4891.6  140.22
  4927.3  135.34  4969.8   138.6  4974.3  124.29  5022.1  124.29    5026  139.59
  5381.4  159.91  5521.4  173.78  5571.3  174.06  5613.3  183.84  5651.9  186.81
#Mann= 10 ,-1 , 0
  -140.8     .11       0   618.7     .17       0   712.9     .15       0
   923.6     .11       0    1417     .17       0  1720.2     .11       0
  3034.3     .15       0  4969.8     .06       0    5026     .15       0
  5381.4     .11       0
Bank Sta=4969.8,5026
XS Rating Curve= 0 ,0
Exp/Cntr=0.3,0.1

Type RM Length L Ch R = 1 ,43000   ,1256,1256,1256
BEGIN DESCRIPTION:
LAKE CREEK 41.0
END DESCRIPTION:
XS GIS Cut Line= 3
       3796499.5     10092946.99      3798436.65     10088739.84
      3798467.85     10087761.04
#Sta/Elev= 30
   368.3   161.6   462.9  162.16  1042.4  148.47  1363.1  145.48  1563.9  145.31
  1843.9  144.44  1943.9  144.07  3490.3  138.59  3507.7  141.78    3532  139.91
  3613.4  139.11  3688.6  135.84  4270.1  137.93    4316  133.27  4321.5  136.43
  4338.1  132.89  4344.5  135.36    4350  132.59  4367.4  137.93  4539.2  139.95
  4954.6  136.69  4962.6  123.03  5010.5  123.03  5028.8   127.3  5044.1136.6977
  5068.8  139.67  5559.1  141.15  5714.6  145.58  5909.2  160.77  5979.3  170.45
#Mann= 12 ,-1 , 0
   368.3     .11       0  1042.4     .17       0  1363.1     .15       0
  1563.9     .11       0  1843.9     .15       0  1943.9     .11       0
  3490.3     .15       0    3532     .11       0  3613.4     .15       0
  4954.6     .06       0  5044.1     .15       0  5714.6     .11       0
Bank Sta=4954.6,5044.1
XS Rating Curve= 0 ,0
Exp/Cntr=0.3,0.1

Type RM Length L Ch R = 1 ,41744   ,845,845,845
BEGIN DESCRIPTION:
LAKE CREEK 40.0
END DESCRIPTION:
XS GIS Cut Line= 3
      3796568.94     10092955.68      3798886.65     10089804.64
      3799364.07       10088138.
#Sta/Elev= 30
   326.2  161.55  1221.2  145.15  1247.9  144.69  1498.2  144.31  1560.6  144.73
  1735.7  145.33  1854.4  143.55  2046.4   143.8  2553.3  142.46  2988.6   137.7
  3288.8  138.99  3308.9  138.21  3947.5  140.01  4443.2  136.25    4460  133.66
  4482.1  137.87  4549.6  139.04  4806.8  139.38  4938.5  136.37  4959.3  127.16
    4962  122.12  5009.9  122.12  5024.9  130.28  5052.9  135.88  5392.6   144.8
  5614.6  155.79  5819.7  176.93  5874.7  176.36  5905.9  181.38  5971.5  183.55
#Mann= 14 ,-1 , 0
   326.2     .11       0  1221.2     .17       0  1247.9     .15       0
  1498.2     .11       0  1560.6     .17       0  1735.7     .11       0
  1854.4     .15       0  2046.4     .11       0  2553.3     .15       0
  3288.8     .11       0  3308.9     .15       0  4938.5     .06       0
  5052.9     .15       0  5392.6     .11       0
Bank Sta=4938.5,5052.9
XS Rating Curve= 0 ,0
Exp/Cntr=0.3,0.1

Type RM Length L Ch R = 1 ,40899   ,267,267,267
BEGIN DESCRIPTION:
Mapping XS 7725b6d0
END DESCRIPTION:
XS GIS Cut Line= 3
      3796577.62     10093007.76      3799728.66     10089596.31
      3799815.46     10088407.11
#Sta/Elev= 30
   -64.6  161.14   -13.1  160.67   759.7  148.05   927.8  146.83  1046.5   143.9
  1428.3  143.82  1764.1  143.19  1839.7  143.55  2701.9  141.07  2805.3  140.61
  4434.1  138.96  4469.3  131.75  4476.6  135.87  4483.5  131.45  4490.8  134.39
  4497.6  131.07  4511.8  136.72  4568.5  130.96  4594.7  138.51  4945.6  135.88
  4985.7  126.95  4991.7  122.17  5039.9  122.17    5045  130.82    5066   136.8
  5286.5  146.99    5413  159.91  5445.2  162.01  5612.5  177.23  5771.8  188.45
#Mann= 15 ,-1 , 0
   -64.6     .17       0   -13.1     .11       0   759.7     .17       0
   927.8     .15       0  1046.5     .17       0  1428.3     .15       0
  1764.1     .11       0  1839.7     .15       0  2701.9     .11       0
  2805.3     .15       0  4945.6     .06       0    5066     .15       0
    5413     .11       0  5445.2     .17       0  5612.5     .11       0
Bank Sta=4945.6,5066
XS Rating Curve= 0 ,0
Exp/Cntr=0.3,0.1

Type RM Length L Ch R = 1 ,40632   ,1248,1248,1248
BEGIN DESCRIPTION:
LAKE CREEK 39.0
END DESCRIPTION:
XS GIS Cut Line= 3
      3800564.42     10093205.31      3799945.67     10089483.46
      3799989.06     10088615.78
#Sta/Elev= 30
  1065.3  161.49  1251.2  158.34  1353.4  152.91  2115.1  144.37  2655.7  150.83
  2914.6  138.37  3320.1  144.57  3553.2  141.27  3735.7  129.75  3776.2  137.88
  3806.7  130.83  3837.1  137.66  4151.3  137.98  4180.7  128.05    4202  135.17
    4273  132.62  4354.1  138.51  4536.5  137.84  4551.2  132.59  4597.4  137.58
    4648  129.37  4678.5     138  4930.7  138.12  4966.7  122.58    5015  122.58
  5030.9  137.28  5251.1  138.55  5291.2  131.21  5480.7  152.56    5707  173.01
#Mann= 6 ,-1 , 0
  1065.3    .125       0  1251.2     .17       0  2655.7     .15       0
  4930.7     .06       0  5030.9     .15       0  5480.7     .17       0
Bank Sta=4930.7,5030.9
XS Rating Curve= 0 ,0
Exp/Cntr=0.3,0.1

Type RM Length L Ch R = 1 ,39384   ,384,384,384
BEGIN DESCRIPTION:
LAKE CREEK 38.0
END DESCRIPTION:
XS GIS Cut Line= 3
      3800694.63     10093174.89      3800641.86     10089209.15
      3801005.57     10088471.32
#Sta/Elev= 30
  1131.6  161.45  1235.4  161.89  1376.9  156.96  1455.5  153.12  1645.5  154.32
  1785.5  149.25  2145.5  149.42  2315.5  145.03  2585.6  151.07  2675.6  148.74
  2820.7  139.19  3665.6  139.64  3965.7  137.53  3995.7  133.46  4065.7  137.31
  4875.8  137.39  4915.8  132.08  4945.8  124.42  4955.8  126.99  4959.1  121.88
  5012.4  121.88  5021.8  130.92  5065.8   138.2  5117.6  137.49  5145.4  136.34
  5440.4  142.43  5566.6  153.47  5697.6  167.57  5831.4  189.66  5920.3  192.84
#Mann= 9 ,-1 , 0
  1131.6     .11       0  1376.9     .17       0  2820.7     .15       0
  4875.8     .06       0  5065.8     .15       0  5117.6     .17       0
  5145.4     .11       0  5440.4     .17       0  5566.6     .11       0
Bank Sta=4875.8,5065.8
XS Rating Curve= 0 ,0
Exp/Cntr=0.3,0.1

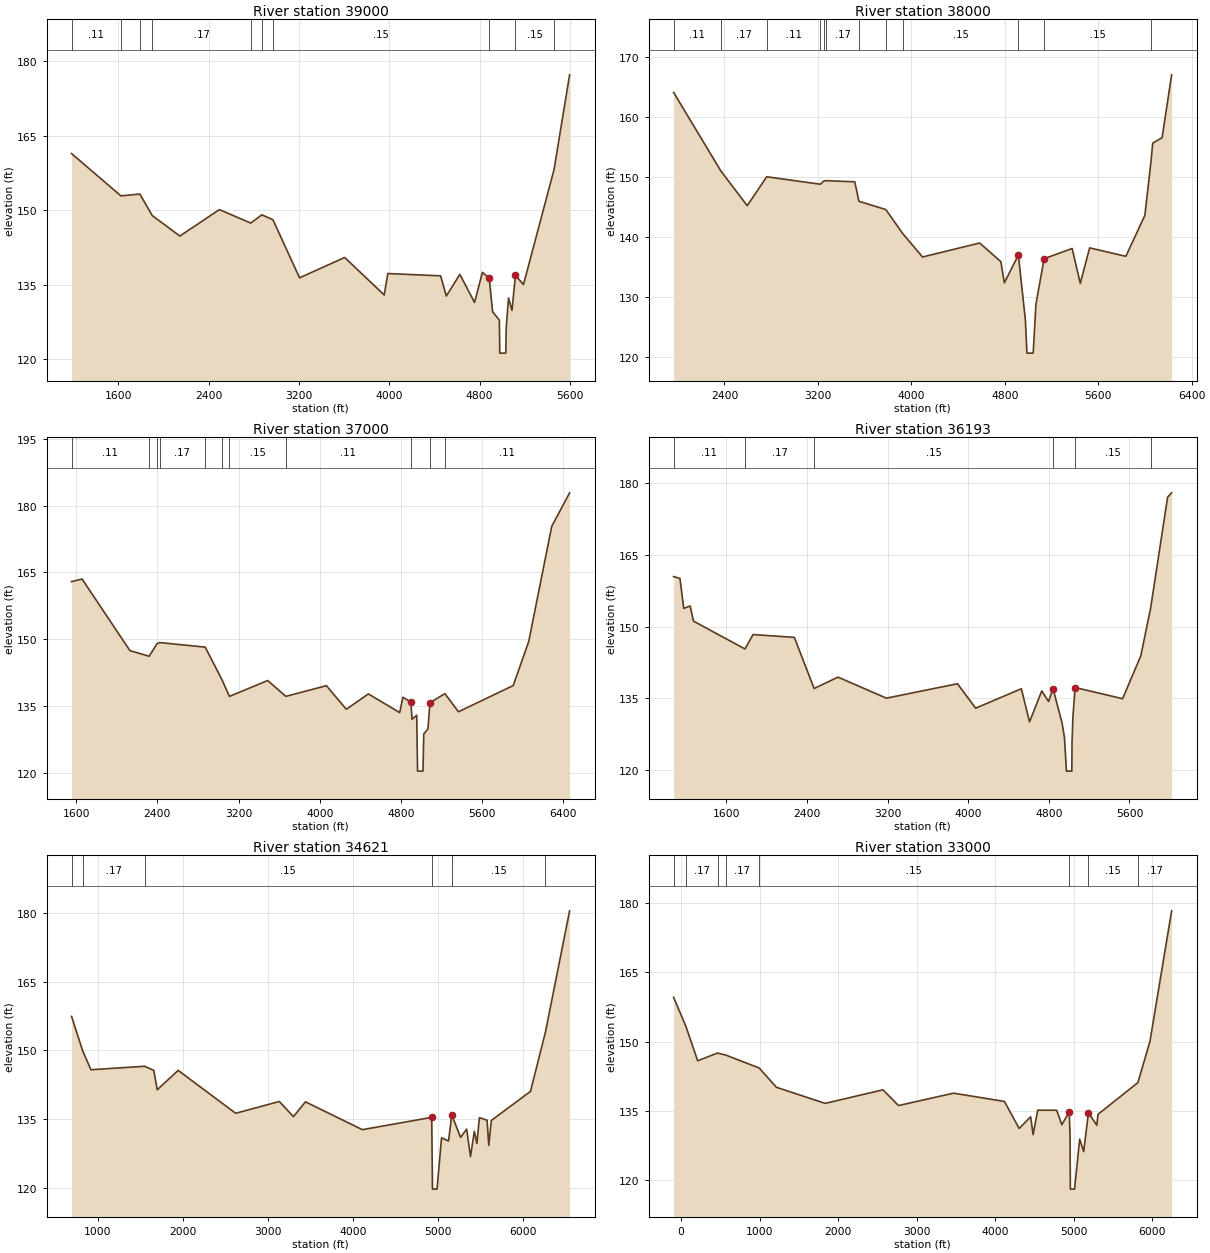
Type RM Length L Ch R = 1 ,39000   ,1000,1000,1000
BEGIN DESCRIPTION:
LAKE CREEK 37.0
END DESCRIPTION:
XS GIS Cut Line= 3
      3800875.36     10093050.25      3800967.33     10089236.96
      3801082.83     10088650.12
#Sta/Elev= 30
  1185.6  161.43  1623.3  152.89  1790.5  153.27  1900.2  148.93  2145.1  144.79
  2495.2  150.13  2773.2  147.41  2871.5  149.07  2969.7  148.09  3205.4  136.37
  3605.5  140.47  3955.6  132.91  3987.6  137.23  4455.7  136.77  4505.7  132.69
  4625.8  137.06  4755.8   131.4  4825.8  137.48  4885.9  136.28  4915.9  129.53
  4975.9  127.82  4979.4  121.18  5032.7  121.18  5036.6  126.31    5057  132.31
  5087.5  129.79  5118.1  136.85  5189.5  135.01  5460.1  158.19  5598.1  177.31
#Mann= 10 ,-1 , 0
  1185.6     .11       0  1623.3     .17       0  1790.5     .11       0
  1900.2     .17       0  2773.2     .11       0  2871.5     .17       0
  2969.7     .15       0  4885.9     .06       0  5118.1     .15       0
  5460.1     .11       0
Bank Sta=4885.9,5118.1
XS Rating Curve= 0 ,0
Exp/Cntr=0.3,0.1

Type RM Length L Ch R = 1 ,38000   ,1000,1000,1000
BEGIN DESCRIPTION:
LAKE CREEK 36.0
END DESCRIPTION:
XS GIS Cut Line= 3
      3801217.85     10092961.04      3801327.75     10089927.63
      3801309.39     10088699.16
#Sta/Elev= 30
  1964.6  164.11  2368.9  151.01    2595  145.21  2761.9  150.03  3220.6  148.79
  3253.2  149.36    3271  149.38  3515.6  149.19  3551.5  145.94  3781.8  144.56
  3926.5  140.55    4096  136.65  4584.9  138.98  4766.4  135.87  4796.4  132.34
  4916.5  136.98  4976.5  126.11  4989.9  120.61  5043.3  120.61  5066.6  128.74
  5136.6  136.36  5376.6  138.07  5446.6  132.25  5526.6  138.17  5836.6  136.76
  5999.3  143.58  6051.1  152.47  6066.7  155.65  6146.7  156.54  6228.6  167.04
#Mann= 12 ,-1 , 0
  1964.6     .11       0  2368.9     .17       0  2761.9     .11       0
  3220.6     .17       0  3253.2     .11       0    3271     .17       0
  3551.5     .11       0  3781.8     .17       0  3926.5     .15       0
  4916.5     .06       0  5136.6     .15       0  6051.1     .11       0
Bank Sta=4916.5,5136.6
XS Rating Curve= 0 ,0
Exp/Cntr=0.3,0.1

Type RM Length L Ch R = 1 ,37000   ,807,807,807
BEGIN DESCRIPTION:
LAKE CREEK 35.0
END DESCRIPTION:
XS GIS Cut Line= 3
      3801317.84      10093111.1      3802185.15     10089776.85
      3802068.94     10088319.38
#Sta/Elev= 30
  1554.8  162.94  1658.7  163.52  2129.6  147.42  2319.5  146.15  2395.9  148.93
  2421.5  149.23  2871.6   148.2  3037.3  140.84  3110.3  137.12  3487.1  140.69
  3666.3  137.13  4065.7  139.53    4262  134.22  4479.3  137.68    4788  133.48
    4820  136.93  4897.9135.8255  4909.6  131.97  4955.3  132.89    4964  120.31
  5017.4  120.31  5024.9  128.64    5066   129.8  5086.1   135.7  5233.2  137.74
  5366.9  133.66  5906.6  139.56  6059.1  149.45  6285.9  175.36  6462.1  182.91
#Mann= 11 ,-1 , 0
  1554.8     .11       0  2319.5     .17       0  2395.9     .11       0
  2421.5     .17       0  2871.6     .11       0  3037.3     .17       0
  3110.3     .15       0  3666.3     .11       0  4897.9     .06       0
  5086.1     .15       0  5233.2     .11       0
Bank Sta=4897.9,5086.1
XS Rating Curve= 0 ,0
Exp/Cntr=0.3,0.1

Type RM Length L Ch R = 1 ,36193   ,1572,1572,1572
BEGIN DESCRIPTION:
Mapping XS 1c26f40f
END DESCRIPTION:
XS GIS Cut Line= 3
      3801721.71     10093061.17      3802785.08     10089773.39
      3802177.44     10088417.05
#Sta/Elev= 30
  1076.9  160.47  1140.1  160.08  1177.5  153.83  1241.5  154.32  1273.5  151.17
    1785  145.34  1865.5  148.35  2275.1  147.76  2471.1  137.07  2708.3  139.45
  3188.5  135.05  3893.7  138.07  4073.9  132.96  4527.3  137.02  4608.7   130.1
  4730.1  136.56  4797.9  134.35  4841.7  137.04    4932  129.81  4955.2  126.79
  4974.9   119.8  5028.3   119.8  5030.2  125.75    5039   131.2  5060.9  137.28
  5532.1  134.94  5712.4  143.89  5809.9  153.83  5978.4  177.06  6018.6  177.98
#Mann= 6 ,-1 , 0
  1076.9     .11       0    1785     .17       0  2471.1     .15       0
  4841.7     .06       0  5060.9     .15       0  5809.9     .11       0
Bank Sta=4841.7,5060.9
XS Rating Curve= 0 ,0
Exp/Cntr=0.3,0.1

Type RM Length L Ch R = 1 ,34621   ,1621,1621,1621
BEGIN DESCRIPTION:
Mapping XS bbfa1315
END DESCRIPTION:
XS GIS Cut Line= 3
      3802633.17     10093625.43      3803414.42     10089024.69
      3803349.32     10087831.07
#Sta/Elev= 30
     691  157.45   821.7  149.92   918.6  145.79  1551.1  146.55    1659  145.64
  1699.5  141.41  1945.8  145.65  2622.6  136.27  3136.5  138.85  3302.2  135.54
  3444.2  138.77  4113.7  132.69  4930.1  135.38    4939  119.69  4992.4  119.69
  5045.7   130.9    5128  130.21  5166.2  135.89    5270  130.99    5341  132.82
  5386.4   126.8  5431.3  132.33  5461.4  129.66  5491.4  135.31  5581.6  134.75
  5601.6  129.25  5631.6   134.7  6092.3  141.05  6268.4     154    6553  180.53
#Mann= 6 ,-1 , 0
     691     .11       0   821.7     .17       0  1551.1     .15       0
  4930.1     .06       0  5166.2     .15       0  6268.4     .11       0
Bank Sta=4930.1,5166.2
XS Rating Curve= 0 ,0
Exp/Cntr=0.3,0.1

Type RM Length L Ch R = 1 ,33000   ,1221,1221,1221
BEGIN DESCRIPTION:
LAKE CREEK 32.0
END DESCRIPTION:
XS GIS Cut Line= 3
      3802687.43     10093744.73       3804154.5     10088866.04
      3804358.42     10087635.92
#Sta/Elev= 30
   -94.5  159.62    58.9  153.46   212.1  145.86     465  147.53   566.5  147.11
   995.5  144.29  1214.6  140.11  1835.1  136.62  2572.1  139.56  2768.6  136.15
  3470.9  138.83  4117.6  137.04  4305.5  131.18  4451.7  133.71  4483.1  129.84
  4541.7  135.14  4783.3  135.13  4848.5     132  4942.5  134.74    4953  129.91
  4957.5  118.03    5011  118.03    5076  128.88  5126.7  126.16  5187.5  134.58
  5294.8  131.86  5309.1  134.24    5817  141.12  5970.7  150.04  6246.9  178.36
#Mann= 8 ,-1 , 0
   -94.5     .11       0    58.9     .17       0     465     .15       0
   566.5     .17       0   995.5     .15       0  4942.5     .06       0
  5187.5     .15       0    5817     .17       0
Bank Sta=4942.5,5187.5
XS Rating Curve= 0 ,0
Exp/Cntr=0.3,0.1

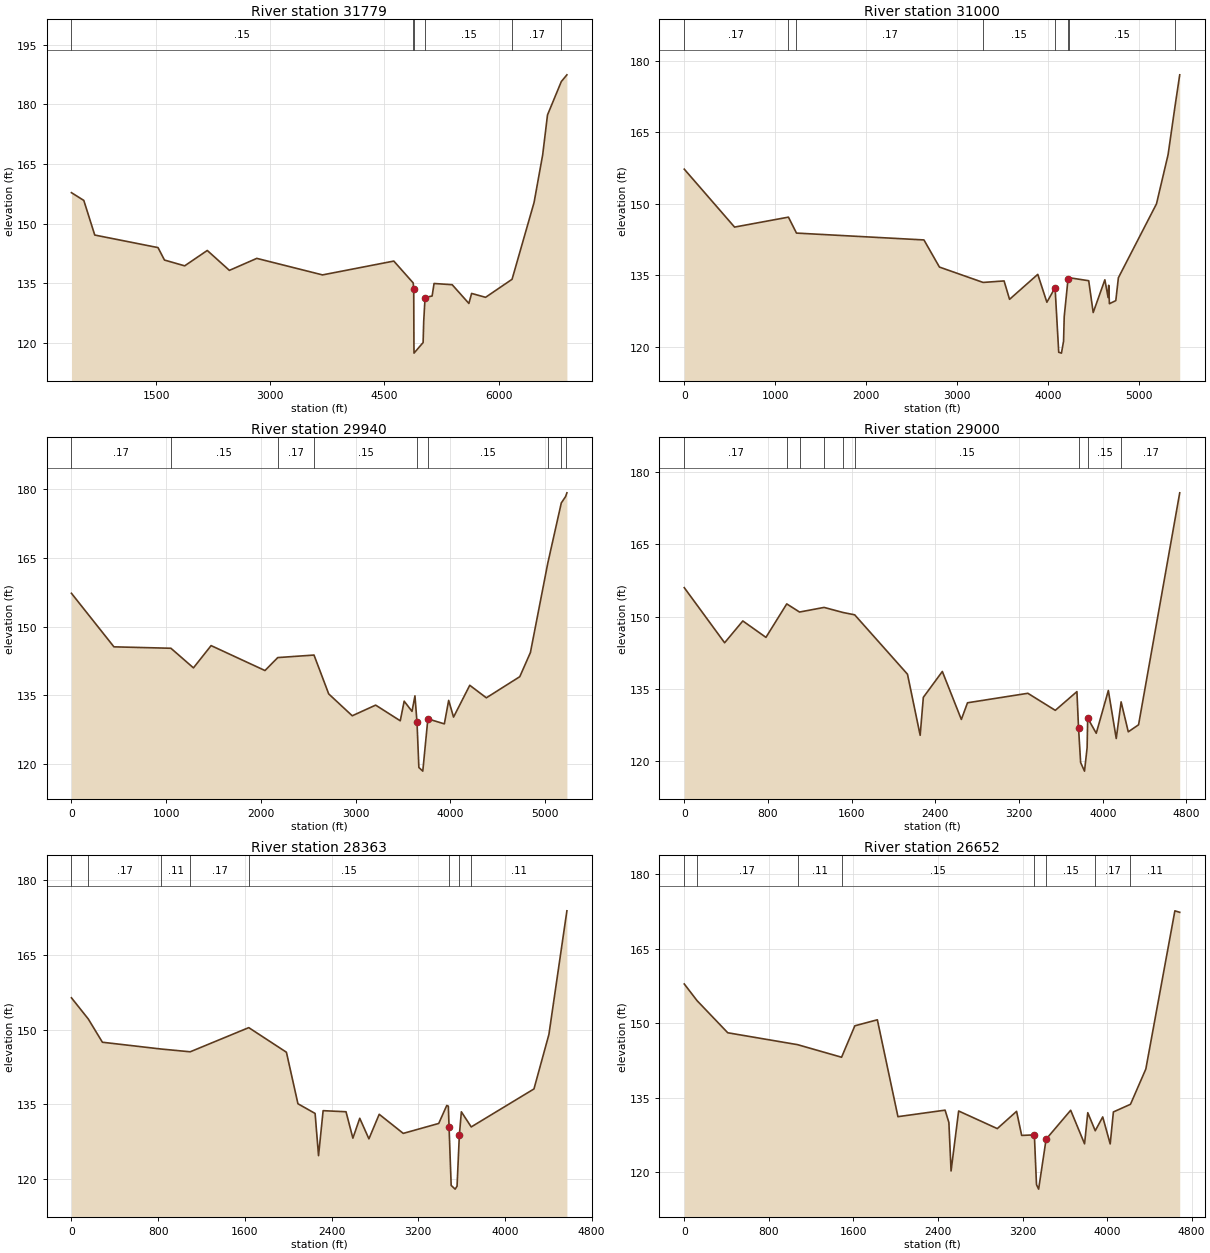
Type RM Length L Ch R = 1 ,31779   ,779,779,779
BEGIN DESCRIPTION:
LAKE CREEK 31.0
END DESCRIPTION:
XS GIS Cut Line= 3
      3803229.97     10093853.24      3804868.42     10089230.86
      3805967.83     10088061.09
#Sta/Elev= 30
   388.6  157.79   551.1  155.84   694.9  147.13  1526.1  143.97    1611  140.84
  1876.3  139.38  2173.3  143.25  2463.8  138.24  2823.8  141.26  3687.5   137.1
  4624.1  140.58  4878.8  135.08  4885.5  133.57  4888.4  119.42  4889.6  117.42
  5009.1  120.08  5016.7  125.34  5034.6  131.41  5127.3  131.79  5152.9  134.94
  5391.1  134.63  5610.4  129.92  5646.1  132.44  5829.7  131.46  6177.8     136
  6466.6  155.31  6579.9  167.31  6643.4  177.35  6824.5  185.74  6898.1  187.44
#Mann= 6 ,-1 , 0
   388.6     .15       0  4878.8     .12       0  4885.5     .06       0
  5034.6     .15       0  6177.8     .17       0  6824.5     .11       0
Bank Sta=4885.5,5034.6
XS Rating Curve= 0 ,0
Exp/Cntr=0.3,0.1

Type RM Length L Ch R = 1 ,31000   ,1060,1060,1060
BEGIN DESCRIPTION:
LAKE CREEK 30.0
END DESCRIPTION:
XS GIS Cut Line= 3
      3805235.98     10093603.42      3805443.44     10089441.33
      3806267.85     10088461.07
#Sta/Elev= 30
       0  157.27     553   145.1  1145.5  147.19  1233.9  143.84  2635.6   142.4
  2805.8   136.7  3286.4  133.47  3516.7  133.79  3576.8  129.92  3887.2  135.17
  3987.3  129.31  4077.4  132.36  4117.5   118.8  4147.5  118.62  4170.7  121.13
    4178  126.29  4219.9  134.18  4227.4  134.48  4447.3  133.83  4496.7  127.15
  4624.9  134.03  4660.5   130.3  4667.1  132.87  4674.8     129  4745.1  129.65
  4773.7  134.46  5192.5  149.98    5320  160.31    5398  170.71  5448.1  177.09
#Mann= 8 ,-1 , 0
       0     .17       0  1145.5     .15       0  1233.9     .17       0
  3286.4     .15       0  4077.4     .06       0  4219.9     .12       0
  4227.4     .15       0    5398     .11       0
Bank Sta=4077.4,4219.9
XS Rating Curve= 0 ,0
Exp/Cntr=0.3,0.1

Type RM Length L Ch R = 1 ,29940   ,940,940,940
BEGIN DESCRIPTION:
LAKE CREEK 29.0
END DESCRIPTION:
XS GIS Cut Line= 3
      3805296.64     10093546.07      3806255.68     10089938.22
      3806886.65     10088579.81
#Sta/Elev= 30
       0  157.25   448.7  145.59  1050.3  145.28  1288.2  141.01  1474.5  145.86
  2043.4  140.43  2178.1  143.25    2561   143.8  2716.2  135.34  2964.5  130.58
  3211.9   132.9  3471.5  129.49  3512.9  133.76  3595.7  131.54  3626.7  134.92
  3648.4  129.15  3668.1  119.32  3709.5  118.53  3763.1  129.91    3937  128.82
  3982.8  133.93  4034.1  130.29  4205.4  137.22  4380.5  134.49  4733.4  139.09
  4845.6  144.34  5028.8  163.78  5171.7  176.91  5217.5  178.32  5230.9  179.12
#Mann= 9 ,-1 , 0
       0     .17       0  1050.3     .15       0  2178.1     .17       0
    2561     .15       0  3648.4     .06       0  3763.1     .15       0
  5028.8     .11       0  5171.7     .17       0  5217.5     .11       0
Bank Sta=3648.4,3763.1
XS Rating Curve= 0 ,0
Exp/Cntr=0.3,0.1

Type RM Length L Ch R = 1 ,29000   ,637,637,637
BEGIN DESCRIPTION:
LAKE CREEK 28.0
END DESCRIPTION:
XS GIS Cut Line= 4
      3806921.11     10093817.74      3806654.78     10092609.82
      3807003.67     10090036.85      3807367.85     10089211.07
#Sta/Elev= 30
       0  155.99   385.7  144.55   559.8  149.08   780.7  145.67   979.6  152.62
    1102  150.93  1336.6  151.89  1516.7  150.84  1629.2  150.35  2133.8  138.02
  2254.9  125.34  2285.2  133.22  2466.8  138.59  2648.5  128.63  2707.5  132.09
  3284.2  134.06  3546.6  130.52  3753.2  134.41  3768.6  126.95  3788.8  119.68
  3825.8   117.9  3850.7  122.76  3856.2   128.9  3938.1  125.76  4053.7  134.64
  4129.1  124.67  4175.7  132.28  4244.2  126.06  4342.5  127.52    4736  175.68
#Mann= 9 ,-1 , 0
       0     .17       0   979.6     .11       0    1102     .17       0
  1336.6     .15       0  1516.7     .17       0  1629.2     .15       0
  3768.6     .06       0  3856.2     .15       0  4175.7     .17       0
Bank Sta=3768.6,3856.2
XS Rating Curve= 0 ,0
Exp/Cntr=0.3,0.1

Type RM Length L Ch R = 1 ,28363   ,1711,1711,1711
BEGIN DESCRIPTION:
Mapping XS 9fe7c5bf
END DESCRIPTION:
XS GIS Cut Line= 4
      3806959.92     10093756.76      3806911.47     10092114.26
      3807549.97       10090240.      3807450.88     10089295.96
#Sta/Elev= 30
       0  156.39   155.8  152.12   285.8  147.45     826  146.09  1096.2  145.53
  1636.4  150.39    1984  145.44  2090.3  135.08  2248.7  133.13  2280.4  124.64
  2322.7  133.69    2534  133.47  2597.4  128.16  2660.8  132.16  2745.3  128.02
  2840.3  132.96  3062.2  129.12  3389.7  131.12  3463.6  134.73  3478.3  134.59
  3484.8  130.45  3504.4  118.66    3541  117.91  3558.7   118.5  3579.9  128.75
  3598.4  133.46  3689.5  130.42  4268.5  138.06  4406.4  149.02  4572.4  173.88
#Mann= 8 ,-1 , 0
       0     .15       0   155.8     .17       0     826     .11       0
  1096.2     .17       0  1636.4     .15       0  3484.8     .06       0
  3579.9     .17       0  3689.5     .11       0
Bank Sta=3484.8,3579.9
XS Rating Curve= 0 ,0
Exp/Cntr=0.3,0.1

Type RM Length L Ch R = 1 ,26652   ,665,665,665
BEGIN DESCRIPTION:
Mapping XS c4a785c0
END DESCRIPTION:
XS GIS Cut Line= 3
      3807015.36      10093812.2      3807722.15     10090706.55
       3809208.7     10090489.54
#Sta/Elev= 30
       0  157.88   121.5  154.52   411.4  148.07  1071.6  145.68  1488.2  143.15
  1613.7  149.47  1826.7  150.68  2021.6   131.2  2467.4  132.51  2503.5  130.03
  2524.1  120.28  2595.8  132.34  2961.4   128.8  3143.8  132.27  3192.1  127.43
  3312.1  127.54  3332.3  117.54  3352.5  116.63  3423.3  126.67  3655.7  132.49
  3787.1  125.74  3817.4     132  3888.1  128.37  3958.9  131.15  4029.6  125.72
  4059.9  132.15  4221.6  133.69  4366.7  140.78  4641.6  172.59  4687.4  172.29
#Mann= 8 ,-1 , 0
       0     .15       0   121.5     .17       0  1071.6     .11       0
  1488.2     .15       0  3312.1     .06       0  3423.3     .15       0
  3888.1     .17       0  4221.6     .11       0
Bank Sta=3312.1,3423.3
XS Rating Curve= 0 ,0
Exp/Cntr=0.3,0.1