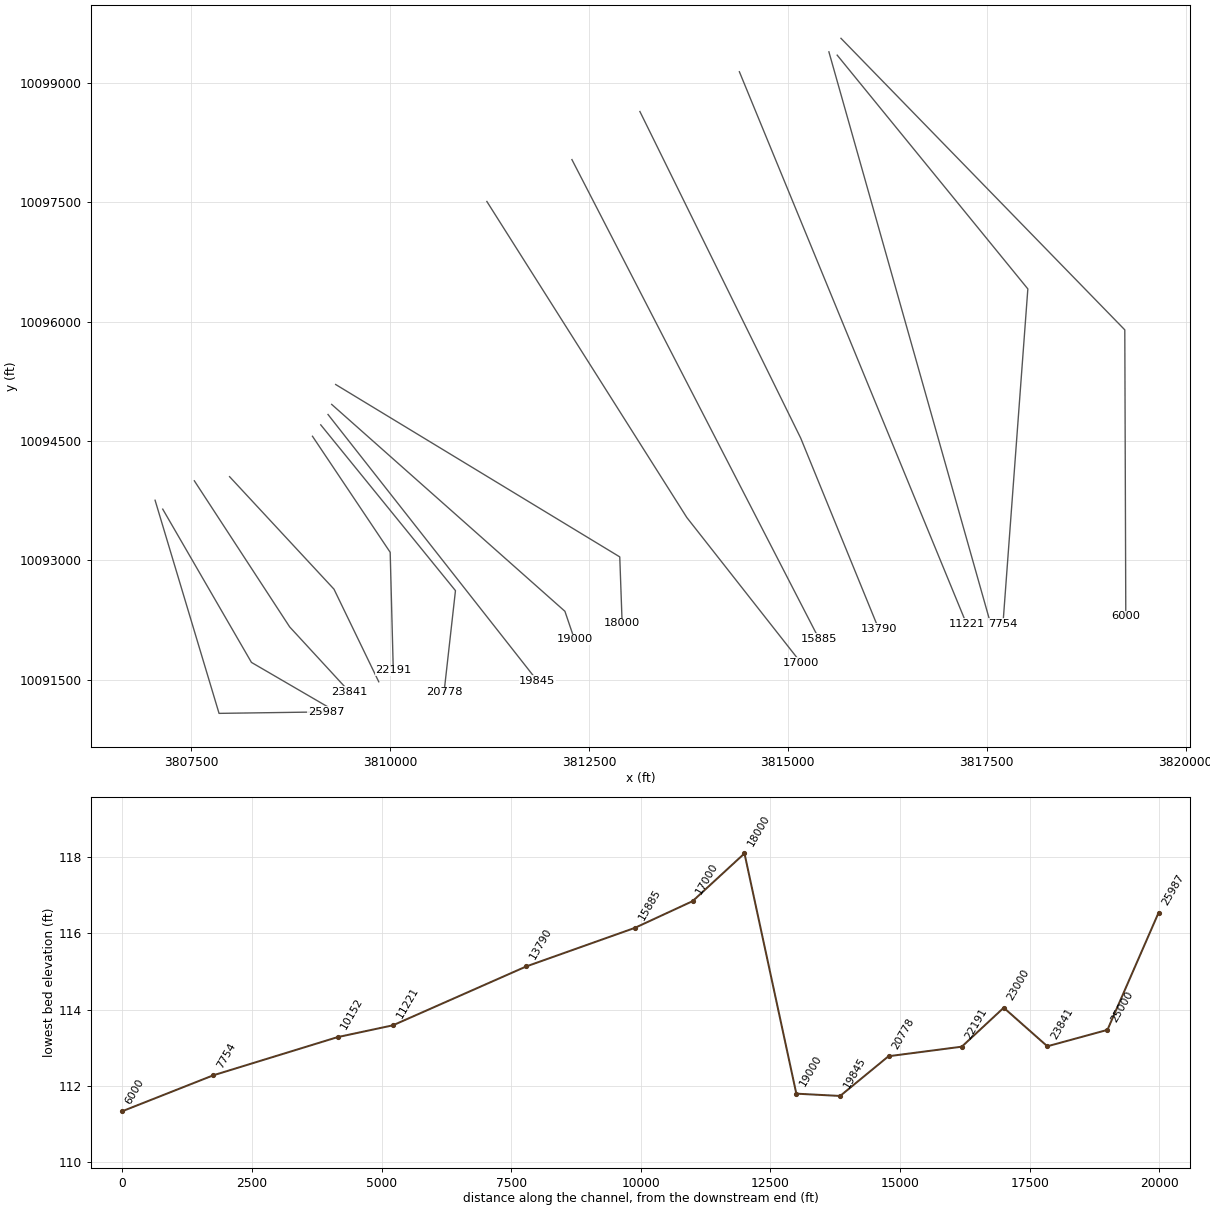
HEC-RAS study LAKE CREEK.prj: LAKE CREEK Base Level Engineering

--- LAKE CREEK.g01 (geometry) --- (continued)

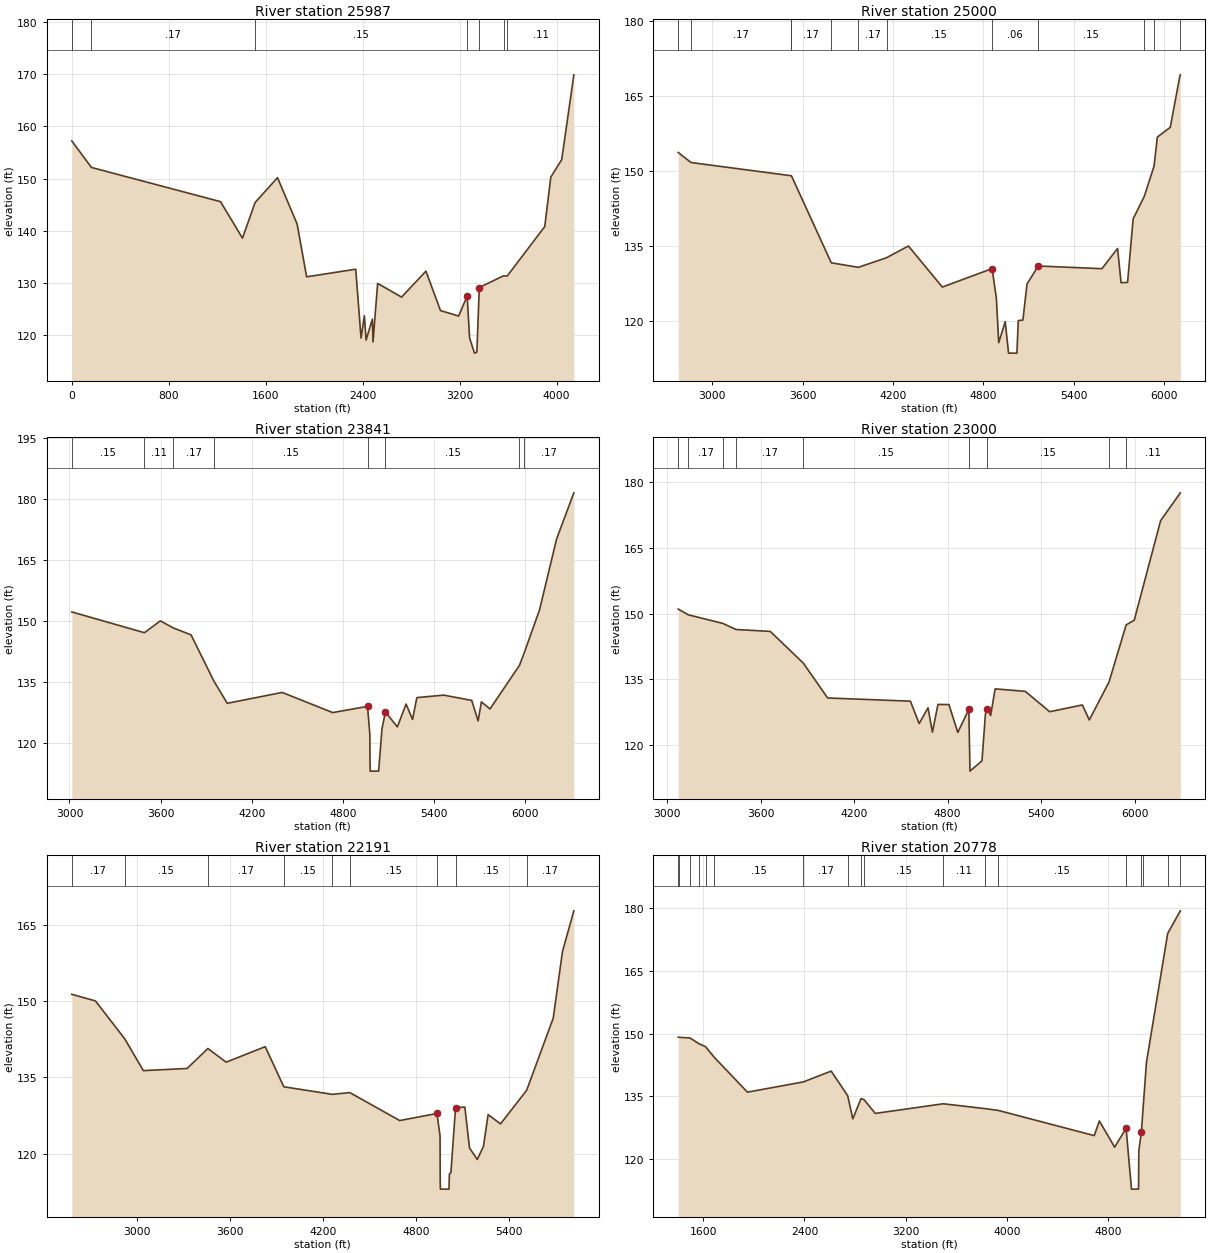
Type RM Length L Ch R = 1 ,25987   ,987,987,987
BEGIN DESCRIPTION:
Mapping XS 131c5304
END DESCRIPTION:
XS GIS Cut Line= 3
      3807048.62     10093756.76      3807852.47     10091078.36
      3809197.84     10091097.18
#Sta/Elev= 30
       0  157.22   162.5  152.14  1227.3  145.58  1408.2  138.58  1512.6  145.42
  1697.3  150.18  1858.8  141.32  1937.5  131.17  2342.5  132.63  2386.4  119.43
  2413.8   123.7  2428.2  119.05  2479.9  123.06  2485.1  118.67  2523.4  129.91
  2720.5  127.28  2921.8  132.26  3041.8   124.7  3191.8  123.65  3261.8  127.51
  3281.9  119.48  3321.9  116.54  3341.9  116.72  3361.9  129.12  3561.9  131.37
  3591.9  131.31  3901.9  140.81  3951.9  150.29  4041.9  153.64  4141.9   169.9
#Mann= 7 ,-1 , 0
       0     .15       0   162.5     .17       0  1512.6     .15       0
  3261.8     .06       0  3361.9     .11       0  3561.9     .17       0
  3591.9     .11       0
Bank Sta=3261.8,3361.9
XS Rating Curve= 0 ,0
Exp/Cntr=0.3,0.1

Type RM Length L Ch R = 1 ,25000   ,1159,1159,1159
BEGIN DESCRIPTION:
LAKE CREEK 25.0
END DESCRIPTION:
XS GIS Cut Line= 3
      3807144.78     10093644.86      3808259.62     10091718.85
      3809217.81      10091161.1
#Sta/Elev= 30
  2774.6  153.65    2859  151.64    3525  148.99  3526.1     149  3790.7  131.56
  3970.6  130.65  4157.6  132.57  4303.1  134.92  4528.4   126.7  4858.8  130.39
  4887.2   124.5  4902.9  115.56    4946  119.77  4968.1  113.47  5023.6  113.47
  5032.7  119.98  5063.4  120.09  5090.7   127.3  5165.1  130.92  5588.1  130.38
  5692.2  134.43  5715.3  127.56  5758.4  127.64  5795.6  140.36  5869.2  144.84
  5934.6  150.94  5956.1  156.73  6042.1  158.69  6103.4   168.6  6108.7   169.2
#Mann= 12 ,-1 , 0
  2774.6     .11       0    2859     .17       0    3525     .15       0
  3526.1     .17       0  3790.7     .15       0  3970.6     .17       0
  4157.6     .15       0  4858.8     .06       0  5165.1     .15       0
  5869.2     .11       0  5934.6     .17       0  6103.4     .11       0
Bank Sta=4858.8,5165.1
XS Rating Curve= 0 ,0
Exp/Cntr=0.3,0.1

Type RM Length L Ch R = 1 ,23841   ,841,841,841
BEGIN DESCRIPTION:
Mapping XS 0a8a7780
END DESCRIPTION:
XS GIS Cut Line= 3
      3807542.04      10094000.8      3808739.95     10092164.88
      3809493.34     10091346.54
#Sta/Elev= 30
  3015.2  152.17  3493.4  147.06  3598.1  149.97  3683.2  148.24  3800.3  146.53
  3950.8  135.16  4038.6  129.71    4400  132.38  4732.6  127.43  4961.8  128.95
  4976.9  122.09  4978.2  115.04  4979.4  113.04    5035  113.04  5056.7  123.41
  5079.6  127.57    5158  123.91  5215.5  129.53    5258  125.74  5286.4  131.11
  5463.3  131.72  5647.5  130.42  5689.6  125.39  5711.2  130.07  5767.9  128.32
  5961.6  139.02  5993.4  142.14  6093.4  152.61  6206.2  170.09  6319.7  181.44
#Mann= 8 ,-1 , 0
  3015.2     .15       0  3493.4     .11       0  3683.2     .17       0
  3950.8     .15       0  4961.8     .06       0  5079.6     .15       0
  5961.6     .11       0  5993.4     .17       0
Bank Sta=4961.8,5079.6
XS Rating Curve= 0 ,0
Exp/Cntr=0.3,0.1

Type RM Length L Ch R = 1 ,23000   ,809,809,809
BEGIN DESCRIPTION:
LAKE CREEK 23.0
END DESCRIPTION:
XS GIS Cut Line= 3
      3807984.72     10094052.92      3809296.74     10092639.24
      3809859.43     10091475.42
#Sta/Elev= 30
  3071.3  151.04  3135.7  149.73  3356.6  147.78  3442.3  146.38  3661.9  145.94
  3874.5  138.69  4029.9  130.75  4560.9  130.02  4617.2  124.91  4673.9  128.51
  4702.2  122.94  4737.9  129.28  4808.2  129.24  4864.9  122.88  4935.8  128.13
  4943.2  114.05  5020.2  116.41  5042.5  127.17  5053.5  128.34  5075.7  126.74
  5104.7  132.83  5297.9  132.26  5454.7  127.61  5664.4  129.16  5708.8  125.73
  5835.3  134.39  5945.3  147.43    5997   148.5  6166.3  171.22  6292.7  177.58
#Mann= 9 ,-1 , 0
  3071.3     .15       0  3135.7     .17       0  3356.6     .11       0
  3442.3     .17       0  3874.5     .15       0  4935.8     .06       0
  5053.5     .15       0  5835.3     .17       0  5945.3     .11       0
Bank Sta=4935.8,5053.5
XS Rating Curve= 0 ,0
Exp/Cntr=0.3,0.1

Type RM Length L Ch R = 1 ,22191   ,1413,1413,1413
BEGIN DESCRIPTION:
Mapping XS ff59cede
END DESCRIPTION:
XS GIS Cut Line= 3
      3809026.41     10094560.71      3810002.97     10093102.38
      3810042.03       10091618.
#Sta/Elev= 30
  2580.1  151.35  2732.8  150.05  2921.7  142.61    3042  136.34  3324.2  136.76
  3458.6  140.69  3576.4     138  3828.5  141.05  3948.4  133.16  4261.7  131.67
  4374.3  132.02  4696.6  126.52  4936.7  127.91  4956.7   123.5  4957.7  115.03
  4958.8  113.03  5014.6  113.03  5016.7  115.98  5026.7  116.26  5056.8  129.08
  5116.8  129.16  5146.8  121.13  5196.8  118.86  5236.8  121.43  5266.8  127.69
  5346.9  125.86  5515.7  132.48    5687  146.65    5747  159.79  5820.1  167.77
#Mann= 9 ,-1 , 0
  2580.1     .17       0  2921.7     .15       0  3458.6     .17       0
  3948.4     .15       0  4261.7     .11       0  4374.3     .15       0
  4936.7     .06       0  5056.8     .15       0  5515.7     .17       0
Bank Sta=4936.7,5056.8
XS Rating Curve= 0 ,0
Exp/Cntr=0.3,0.1

Type RM Length L Ch R = 1 ,20778   ,933,933,933
BEGIN DESCRIPTION:
Mapping XS 2a26095a
END DESCRIPTION:
XS GIS Cut Line= 3
      3809130.56     10094703.96      3810823.28     10092620.61
      3810680.14     10091345.35
#Sta/Elev= 30
  1402.5  149.15  1405.6  149.12  1495.5  148.96  1569.8  147.52  1618.4  146.88
  1687.6  144.31  1949.6  135.99  2391.4  138.44  2611.1  141.03  2741.7  135.13
  2782.1   129.6  2847.1  134.46  2870.8   134.2  2959.5   130.9  3496.6  133.21
  3830.2  132.04  3931.2  131.62  4690.1  125.59  4730.4  129.09  4851.1  122.83
  4941.7  127.33  4984.2  112.78    5040  112.78  5042.3  121.96  5062.5  126.41
  5071.8   130.4  5102.7  143.16  5270.6  173.98  5369.9  179.39  5370.1  179.39
#Mann= 18 ,-1 , 0
  1402.5     .17       0  1405.6     .11       0  1495.5     .17       0
  1569.8     .11       0  1618.4     .17       0  1687.6     .15       0
  2391.4     .17       0  2741.7     .15       0  2847.1     .17       0
  2870.8     .15       0  3496.6     .11       0  3830.2     .17       0
  3931.2     .15       0  4941.7     .06       0  5062.5     .15       0
  5071.8     .17       0  5270.6     .11       0  5369.9     .17       0
Bank Sta=4941.7,5062.5
XS Rating Curve= 0 ,0
Exp/Cntr=0.3,0.1

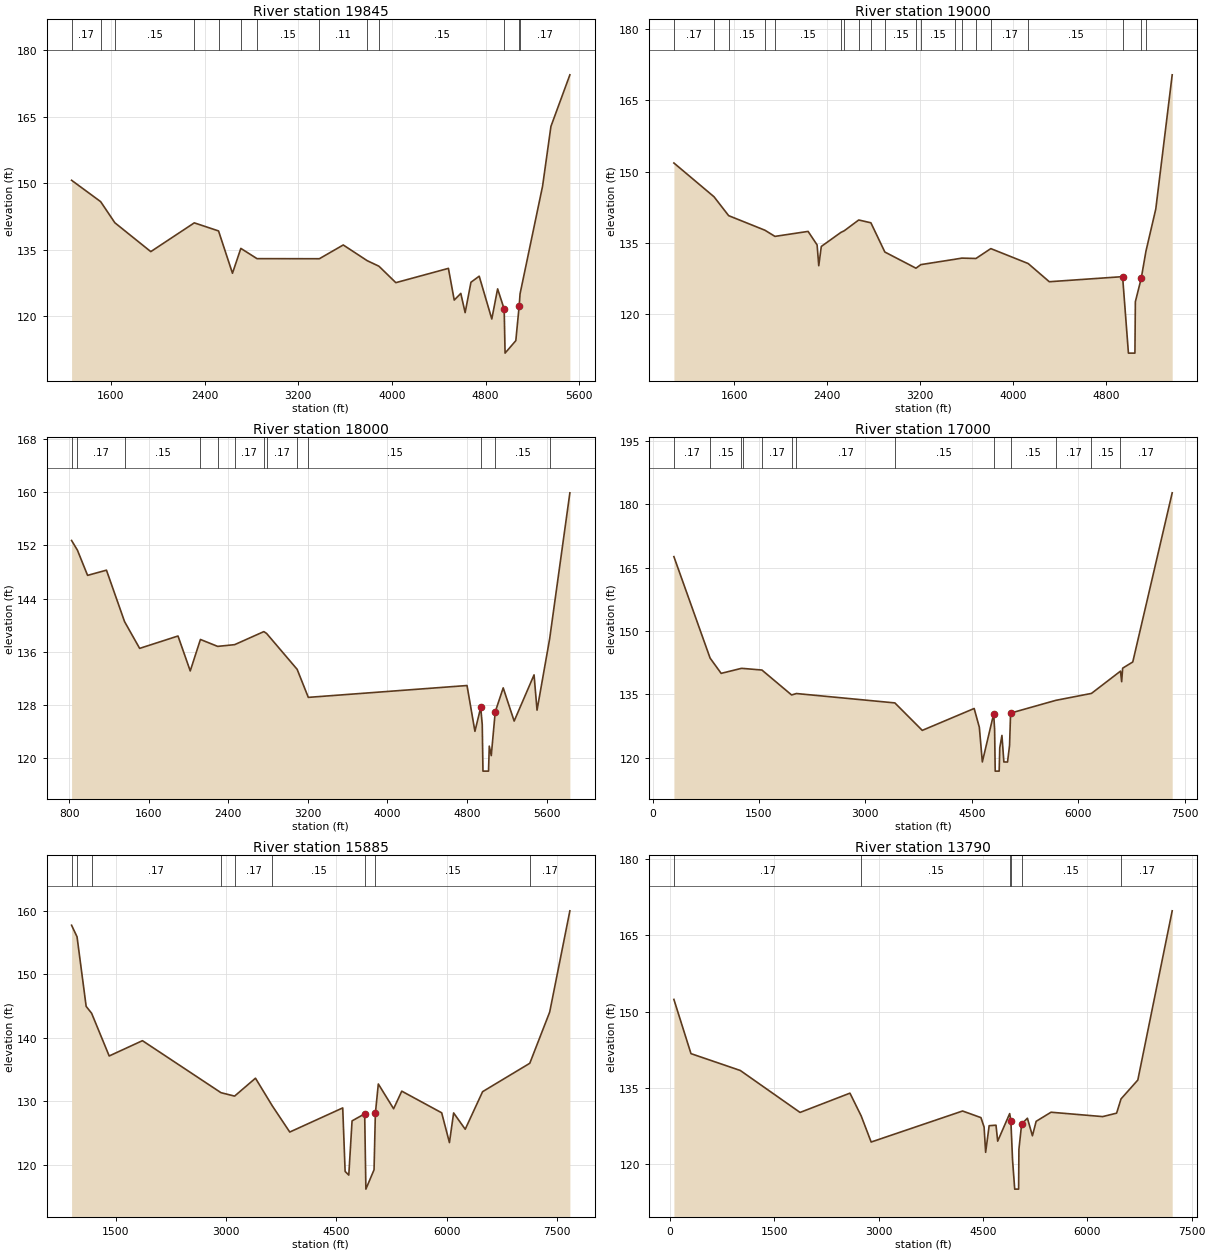
Type RM Length L Ch R = 1 ,19845   ,845,845,845
BEGIN DESCRIPTION:
Mapping XS 65186c67
END DESCRIPTION:
XS GIS Cut Line= 2
      3809221.74     10094834.13      3811851.95     10091487.77
#Sta/Elev= 30
    1264  150.67  1512.3  145.86  1633.7   141.1  1940.6   134.6  2312.2  141.08
  2519.3  139.26  2638.3  129.73  2709.7  135.33  2847.9  133.02  3380.5     133
  3584.5   136.1  3788.6  132.57  3889.5  131.31  4033.7  127.61  4482.8  130.83
  4532.5  123.69  4588.6  125.19  4625.6  120.86  4675.3   127.7  4745.8  129.07
  4853.3  119.43    4903  126.21  4959.1  121.66  4966.7  111.74  5058.5  114.55
  5087.4  122.43  5094.6  125.08  5287.2  149.37  5358.5  162.81  5520.3  174.42
#Mann= 13 ,-1 , 0
    1264     .17       0  1512.3     .11       0  1633.7     .15       0
  2312.2     .17       0  2519.3     .15       0  2709.7     .17       0
  2847.9     .15       0  3380.5     .11       0  3788.6     .17       0
  3889.5     .15       0  4959.1     .06       0  5087.4     .15       0
  5094.6     .17       0
Bank Sta=4959.1,5087.4
XS Rating Curve= 0 ,0
Exp/Cntr=0.3,0.1

Type RM Length L Ch R = 1 ,19000   ,1000,1000,1000
BEGIN DESCRIPTION:
LAKE CREEK 19.0
END DESCRIPTION:
XS GIS Cut Line= 3
      3809267.84     10094961.08      3812198.64     10092361.31
      3812317.86     10092011.04
#Sta/Elev= 30
  1082.3   151.8  1427.4   144.7  1553.6  140.72  1865.3  137.66  1951.8  136.36
  2236.9  137.41  2314.6  134.56  2328.8  130.19  2350.6  134.24  2519.4   137.2
    2548  137.54  2672.7  139.81  2777.4  139.22  2897.5  133.07  3165.1  129.67
  3207.3  130.42  3498.8  131.54  3560.3  131.79  3681.2  131.71  3809.3  133.79
  4130.6  130.65  4312.6  126.82  4943.2  127.89  4993.4   111.8  5049.3   111.8
  5053.1  122.63  5103.4  127.52    5144  133.23  5228.8  142.12    5370  170.35
#Mann= 20 ,-1 , 0
  1082.3     .17       0  1427.4     .11       0  1553.6     .15       0
  1865.3     .17       0  1951.8     .15       0  2519.4     .11       0
    2548     .17       0  2672.7     .11       0  2777.4     .17       0
  2897.5     .15       0  3165.1     .11       0  3207.3     .15       0
  3498.8     .11       0  3560.3     .17       0  3681.2     .11       0
  3809.3     .17       0  4130.6     .15       0  4943.2     .06       0
  5103.4     .15       0    5144     .17       0
Bank Sta=4943.2,5103.4
XS Rating Curve= 0 ,0
Exp/Cntr=0.3,0.1

Type RM Length L Ch R = 1 ,18000   ,1000,1000,1000
BEGIN DESCRIPTION:
LAKE CREEK 18.0
END DESCRIPTION:
XS GIS Cut Line= 3
      3809317.85     10095211.07      3812887.89     10093044.75
      3812917.85     10092211.09
#Sta/Elev= 30
   824.1  152.74     883  151.28     985   147.5  1174.9  148.28  1357.1  140.54
  1508.4  136.53  1894.2  138.39  2017.2  133.14  2119.6  137.87    2293  136.83
  2463.4  137.09  2757.3  139.05  2785.1  138.77  3092.2  133.38  3204.2  129.17
    4800  130.95  4879.5  124.07  4937.6  127.65  4953.1  125.09  4960.3  118.09
  5016.2  118.09  5023.7  121.85  5043.7  120.42  5083.7     127  5163.8   130.6
  5273.9  125.61    5474  132.55    5504  127.25  5630.9  137.98  5834.2   159.9
#Mann= 13 ,-1 , 0
   824.1     .11       0     883     .17       0  1357.1     .15       0
  2119.6     .17       0    2293     .15       0  2463.4     .17       0
  2757.3     .11       0  2785.1     .17       0  3092.2     .11       0
  3204.2     .15       0  4937.6     .06       0  5083.7     .15       0
  5630.9     .17       0
Bank Sta=4937.6,5083.7
XS Rating Curve= 0 ,0
Exp/Cntr=0.3,0.1

Type RM Length L Ch R = 1 ,17000   ,1115,1115,1115
BEGIN DESCRIPTION:
LAKE CREEK 17.0
END DESCRIPTION:
XS GIS Cut Line= 3
      3811217.86     10097511.06      3813730.76     10093539.36
      3815167.86     10091711.06
#Sta/Elev= 30
   300.1  167.59   810.4  143.59   966.4  139.97  1250.2  141.15  1273.1  141.14
  1541.2  140.76  1959.6  134.86  2027.5   135.2  3415.5  132.98  3801.9  126.48
  4533.4  131.66  4606.4  127.22  4648.7  119.01  4808.6  130.38  4821.6   126.8
  4830.1  116.84  4886.1  116.84  4894.5  122.36  4925.1  125.29  4952.2  119.01
  5003.8  118.99  5032.7  122.96  5047.1  130.57  5685.2  133.59  6187.4  135.23
  6596.5   140.5  6613.2     138  6626.9   141.2  6769.7  142.67  7325.5  182.69
#Mann= 13 ,-1 , 0
   300.1     .17       0   810.4     .15       0  1250.2     .17       0
  1273.1     .11       0  1541.2     .17       0  1959.6     .15       0
  2027.5     .17       0  3415.5     .15       0  4808.6     .06       0
  5047.1     .15       0  5685.2     .17       0  6187.4     .15       0
  6596.5     .17       0
Bank Sta=4808.6,5047.1
XS Rating Curve= 0 ,0
Exp/Cntr=0.3,0.1

Type RM Length L Ch R = 1 ,15885   ,2095,2095,2095
BEGIN DESCRIPTION:
Mapping XS da951fdf
END DESCRIPTION:
XS GIS Cut Line= 2
      3812286.84     10098037.24      3815390.99     10092016.45
#Sta/Elev= 30
     902   157.7   976.3  155.88  1100.2  144.92  1174.3  143.84  1413.3  137.11
  1865.3  139.52  2932.9  131.33  3118.1  130.79  3401.9  133.61  3630.4  129.26
  3867.9  125.13    4588  128.93  4620.5  118.93  4670.4  118.35  4714.8  126.89
  4886.4     128  4902.8  116.14  5013.8  119.19 5031.57128.0531  5071.8   132.7
  5279.7   128.8  5390.5  131.57  5933.3  128.16  6038.5  123.47  6095.6  128.14
  6253.1  125.57  6489.4  131.49  7130.8  135.96  7401.3  144.02  7675.9  159.97
#Mann= 9 ,-1 , 0
     902     .17       0   976.3     .11       0  1174.3     .17       0
  2932.9     .15       0  3118.1     .17       0  3630.4     .15       0
  4886.4     .06       0 5031.57     .15       0  7130.8     .17       0
Bank Sta=4886.4,5031.57
XS Rating Curve= 0 ,0
Exp/Cntr=0.3,0.1

Type RM Length L Ch R = 1 ,13790   ,2569,2569,2569
BEGIN DESCRIPTION:
Mapping XS 46221def
END DESCRIPTION:
XS GIS Cut Line= 3
      3813140.98     10098641.46      3815161.82     10094537.28
      3816140.98     10092141.47
#Sta/Elev= 30
    57.5  152.43   303.2  141.77  1011.7  138.46    1871  130.21  2588.2     134
  2749.7  129.52  2893.1  124.39  4207.2  130.49  4471.2  129.19  4516.2  127.35
  4538.6  122.36  4589.1   127.6  4687.7   127.7  4711.7  124.56  4884.3  129.98
  4901.4   128.6  4925.5  120.88  4956.6  115.13  5012.6  115.13    5017  122.96
  5056.4  127.94  5139.2  129.07  5211.3  125.62  5264.7  128.46  5478.5  130.25
  6221.2  129.39  6421.4  130.07    6485  132.87  6726.2  136.58  7220.4  169.85
#Mann= 6 ,-1 , 0
    57.5     .17       0  2749.7     .15       0  4884.3     .17       0
  4901.4     .06       0  5056.4     .15       0    6485     .17       0
Bank Sta=4901.4,5056.4
XS Rating Curve= 0 ,0
Exp/Cntr=0.3,0.1

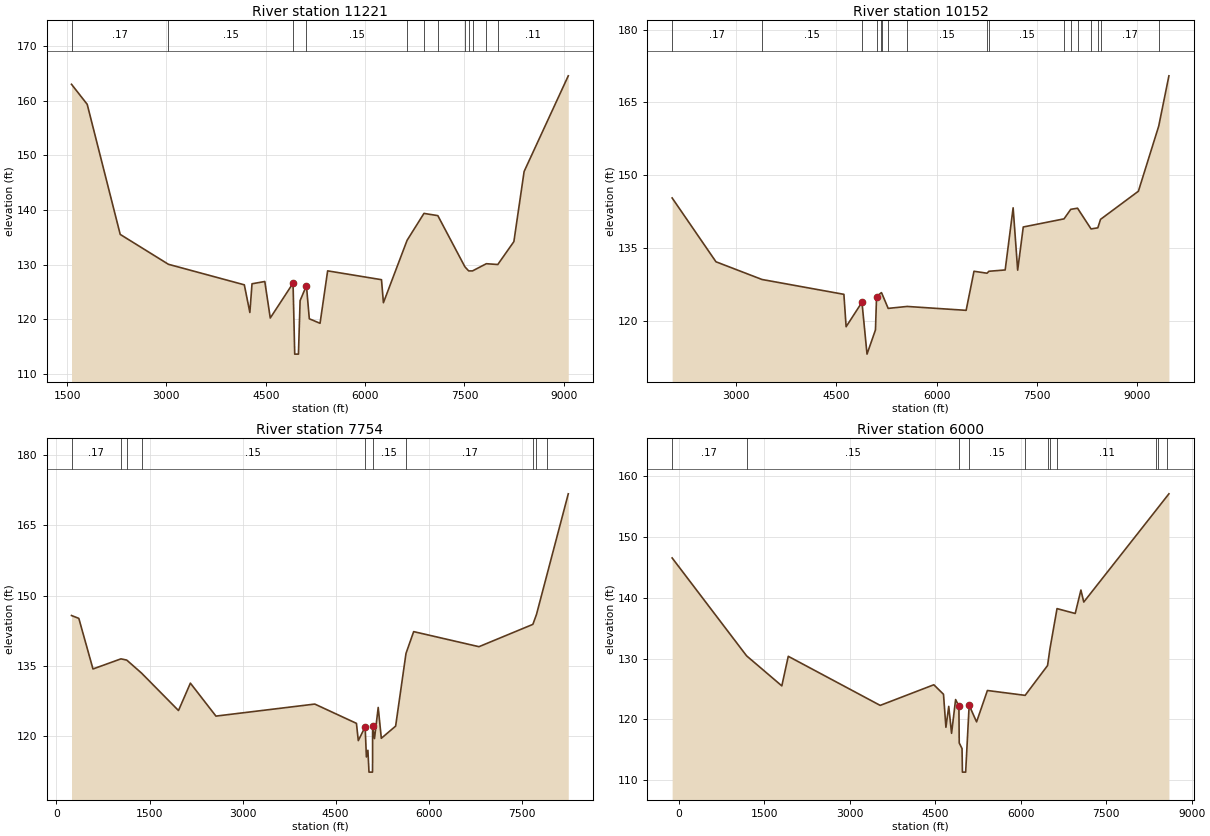
Type RM Length L Ch R = 1 ,11221   ,1069,1069,1069
BEGIN DESCRIPTION:
Mapping XS 83af29d7
END DESCRIPTION:
XS GIS Cut Line= 2
        3814391.     10099141.41      3817244.72       10092205.
#Sta/Elev= 30
  1567.6  163.04  1804.7  159.37  2303.1  135.53  3031.3  130.05  4176.9  126.29
  4260.5  121.22  4292.9  126.48    4486   126.9  4568.7  120.21  4912.5  126.59
  4937.8  113.59    4994  113.59  5019.2   123.4  5114.7  126.14    5158  120.07
  5320.2  119.24  5434.9  128.85  6247.8  127.23  6277.1  123.01  6634.1  134.44
  6889.2  139.38  7098.6  138.97  7506.9   129.6  7564.1  128.84    7622  128.84
  7831.4  130.16  8003.7  130.01  8246.8  134.21  8401.3  147.06  9068.1  164.59
#Mann= 12 ,-1 , 0
  1567.6     .17       0  3031.3     .15       0  4912.5     .06       0
  5114.7     .15       0  6634.1     .17       0  6889.2     .11       0
  7098.6     .17       0  7506.9     .15       0  7564.1     .17       0
    7622     .15       0  7831.4     .17       0  8003.7     .11       0
Bank Sta=4912.5,5114.7
XS Rating Curve= 0 ,0
Exp/Cntr=0.3,0.1

Type RM Length L Ch R = 1 ,10152   ,2398,2398,2398
BEGIN DESCRIPTION:
Mapping XS 7f85a3a4
END DESCRIPTION:
XS GIS Cut Line= 2
      3815515.99     10099391.44      3817536.75     10092245.88
#Sta/Elev= 30
  2043.9  145.38    2699  132.26  3387.3  128.62  4611.2  125.57  4644.5  118.91
  4881.3  123.94    4957  113.28  5083.2  118.26  5099.6  125.11  5171.9  125.92
  5178.3  125.77    5273  122.68    5557  123.08  6438.5  122.28    6556  130.31
  6751.3  129.91    6779  130.31  7022.1  130.58    7141  143.35  7208.9  130.54
  7292.4  139.41  7901.5  141.08  8002.6  143.04  8103.7  143.27  8305.9  139.01
    8407  139.24  8447.6  140.98  9013.3  146.76  9316.9  160.13  9469.7  170.48
#Mann= 17 ,-1 , 0
  2043.9     .17       0  3387.3     .15       0  4881.3     .06       0
  5099.6     .15       0  5171.9     .11       0  5178.3     .15       0
    5273     .11       0    5557     .15       0  6751.3     .11       0
    6779     .15       0  7901.5     .11       0  8002.6    .125       0
  8103.7     .11       0  8305.9     .17       0    8407     .11       0
  8447.6     .17       0  9316.9     .11       0
Bank Sta=4881.3,5099.6
XS Rating Curve= 0 ,0
Exp/Cntr=0.3,0.1

Type RM Length L Ch R = 1 ,7754    ,1754,1754,1754
BEGIN DESCRIPTION:
Mapping XS 2122830f
END DESCRIPTION:
XS GIS Cut Line= 3
      3815620.15     10099349.79      3818015.99     10096412.28
      3817703.57     10092205.01
#Sta/Elev= 30
   242.1  145.74   360.1  145.13   588.4  134.32  1039.2  136.48  1132.6  136.22
  1371.2  133.44  1967.1  125.44  2158.8  131.29  2570.9  124.25  4164.3  126.82
  4836.2   122.7  4866.2  119.01  4976.5  121.96  4996.6  115.52    5021  116.95
  5038.5  112.28  5095.1  112.28  5096.2  114.28  5096.9  122.07    5127  119.44
  5187.1   126.1  5237.3  119.51  5467.9  122.11  5635.1  137.64  5758.7   142.3
  6811.6  139.08  7680.8  143.85  7738.8  145.96  7907.1  154.42  8251.6  171.74
#Mann= 10 ,-1 , 0
   242.1     .17       0  1039.2     .11       0  1132.6     .17       0
  1371.2     .15       0  4976.5     .06       0  5096.9     .15       0
  5635.1     .17       0  7680.8     .11       0  7738.8     .17       0
  7907.1     .11       0
Bank Sta=4976.5,5096.9
XS Rating Curve= 0 ,0
Exp/Cntr=0.3,0.1

Type RM Length L Ch R = 1 ,6000    ,2134,2134,2134
BEGIN DESCRIPTION:
LAKE CREEK 6.0
END DESCRIPTION:
XS GIS Cut Line= 3
      3815667.83      10099561.1      3819234.36     10095897.68
      3819246.89     10092297.71
#Sta/Elev= 30
  -112.8  146.55  1192.5  130.46  1810.8  125.52    1924  130.38  3536.2  122.31
  4476.8   125.7  4646.4  124.14  4688.8  118.71  4738.4  122.15  4787.9  117.72
  4858.6  123.27 4916.45122.2042  4922.3  116.14  4971.8  115.21  4978.3  111.34
    5035  111.34  5096.6  122.33  5226.6   119.6  5416.6  124.76  6078.1  123.96
  6471.4  128.86  6513.1   131.6  6637.5  138.22  6956.6  137.42  7056.6  141.27
  7106.6   139.3  8372.8  154.38  8405.3  154.77  8557.8  156.59    8600  157.09
#Mann= 11 ,-1 , 0
  -112.8     .17       0  1192.5     .15       0 4916.45     .06       0
  5096.6     .15       0  6078.1     .17       0  6471.4     .11       0
  6513.1     .17       0  6637.5     .11       0  8372.8     .17       0
  8405.3     .11       0  8557.8     .17       0
Bank Sta=4916.45,5096.6
XS Rating Curve= 0 ,0
Exp/Cntr=0.3,0.1