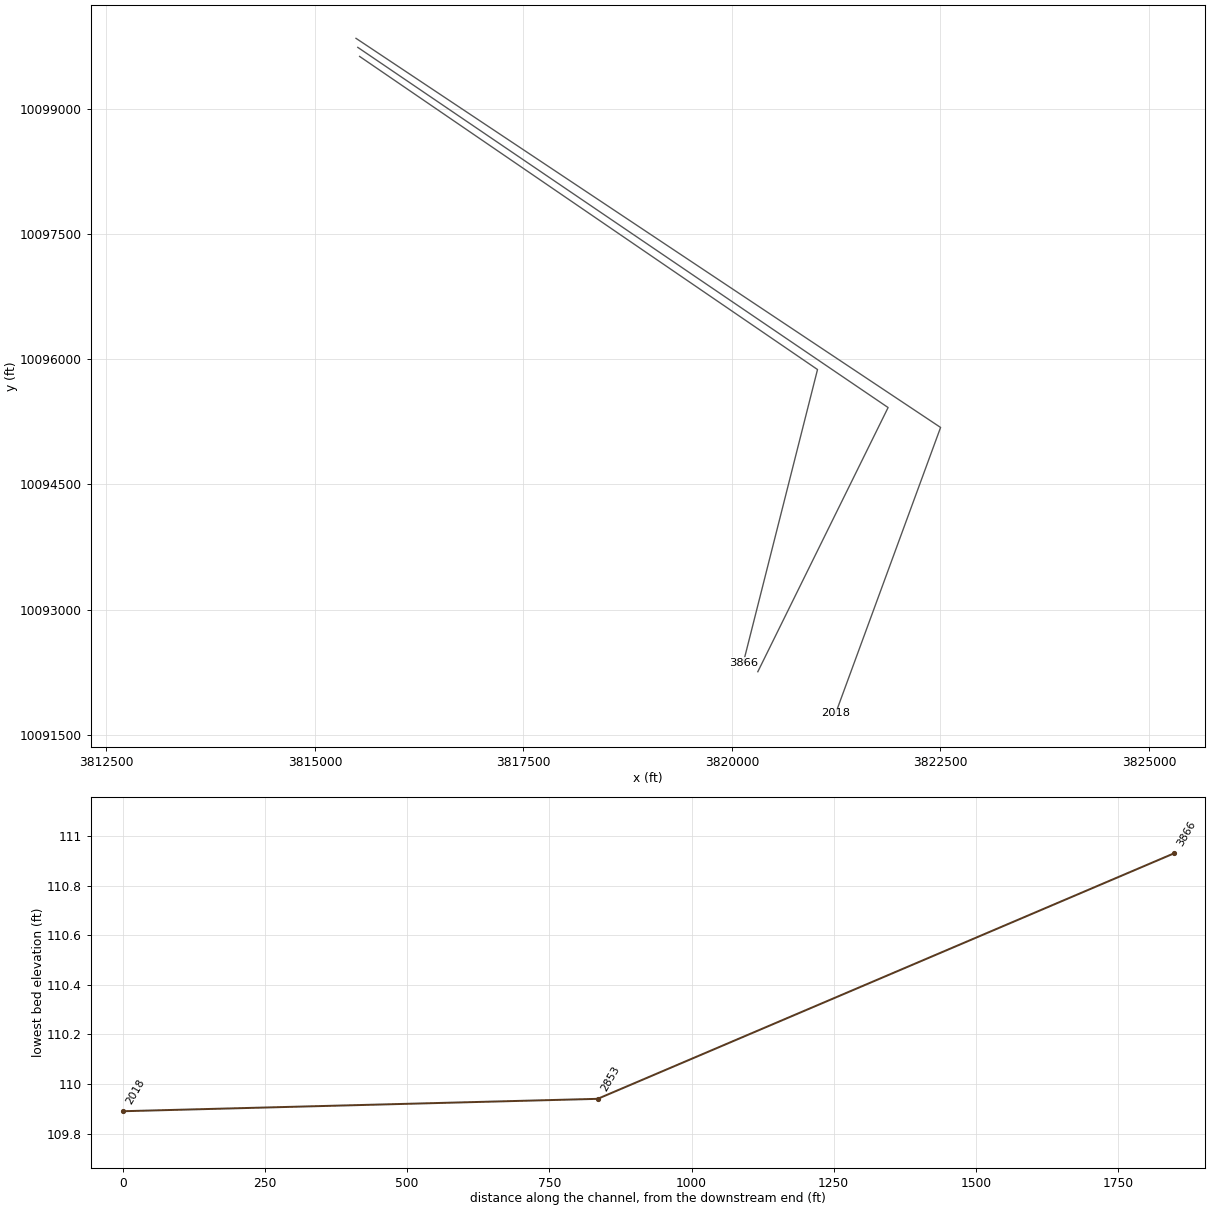
HEC-RAS study LAKE CREEK.prj: LAKE CREEK Base Level Engineering

--- LAKE CREEK.g01 (geometry) --- (continued)

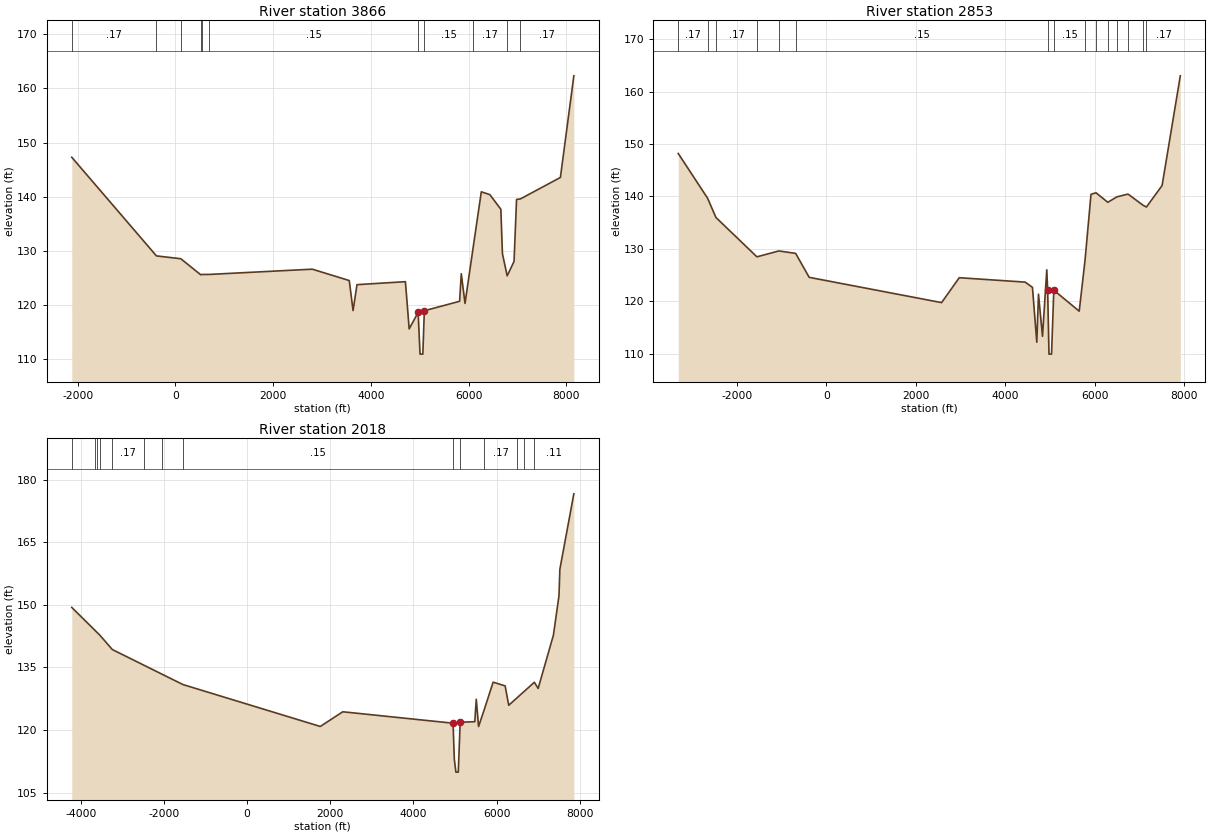
Type RM Length L Ch R = 1 ,3866    ,1013,1013,1013
BEGIN DESCRIPTION:
Mapping XS d02fc1d5
END DESCRIPTION:
XS GIS Cut Line= 3
      3815535.96     10099632.76       3821026.4     10095878.43
      3820137.06     10092364.44
#Sta/Elev= 30
 -2121.2  147.29    -388  129.07   110.1  128.55   518.1  125.59   543.2  125.64
   693.6  125.65  2801.8  126.62  3558.3  124.52  3636.1  118.98  3716.7  123.76
  4707.8  124.31  4784.6  115.59 4967.88118.6353  5007.3  110.93  5064.3  110.93
  5094.7  118.94  5816.8  120.69  5850.9  125.78  5927.7   120.3  6098.2  130.88
    6261  140.91  6435.7  140.39  6660.8  137.69  6693.6  129.45  6790.9  125.39
  6930.9  128.05  6982.4   139.5  7060.4  139.59  7879.9  143.56  8154.9  162.33
#Mann= 11 ,-1 , 0
 -2121.2     .17       0    -388     .15       0   110.1     .17       0
   518.1     .15       0   543.2     .17       0   693.6     .15       0
 4967.88     .06       0  5094.7     .15       0  6098.2     .17       0
  6790.9     .11       0  7060.4     .17       0
Bank Sta=4967.88,5094.7
XS Rating Curve= 0 ,0
Exp/Cntr=0.3,0.1

Type RM Length L Ch R = 1 ,2853    ,835,835,835
BEGIN DESCRIPTION:
Mapping XS f558cf8a
END DESCRIPTION:
XS GIS Cut Line= 3
      3815514.22     10099741.29      3821872.76      10095422.7
      3820310.69     10092255.16
#Sta/Elev= 30
 -3306.5   148.2 -2650.2  139.66   -2464  135.99 -1548.3  128.49 -1058.6  129.61
    -683  129.15  -380.5  124.58  2577.6  119.76  2972.8  124.51  4445.3  123.67
  4608.1  122.67  4705.1  112.21  4742.8  121.37  4832.6  113.35  4928.1  126.02
 4947.73122.1603  4977.6  109.94  5034.6  109.94  5085.2  122.13  5652.8  118.13
  5783.2  127.86    5916  140.41  6028.8   140.7  6291.8  138.89    6494  139.92
  6744.1  140.45  7081.9  138.31  7154.9  137.99  7504.6  142.08  7911.7     163
#Mann= 15 ,-1 , 0
 -3306.5     .17       0 -2650.2     .11       0   -2464     .17       0
 -1548.3     .15       0 -1058.6     .17       0    -683     .15       0
 4947.73     .06       0  5085.2     .15       0  5783.2     .17       0
  6028.8     .11       0  6291.8     .17       0    6494     .11       0
  6744.1     .17       0  7081.9     .11       0  7154.9     .17       0
Bank Sta=4947.73,5085.2
XS Rating Curve= 0 ,0
Exp/Cntr=0.3,0.1

Type RM Length L Ch R = 1 ,2018    ,0,0,0
BEGIN DESCRIPTION:
Mapping XS 20168e34
END DESCRIPTION:
XS GIS Cut Line= 3
      3815492.53     10099849.79       3822502.1     10095183.98
      3821243.58     10091755.61
#Sta/Elev= 30
   -4216  149.38 -3664.2  143.95 -3609.8  143.41 -3542.6  142.75 -3240.3  139.28
 -2488.1  135.56 -2051.8   133.4 -1540.6  130.88  1759.5  120.84  2300.5  124.36
  4952.3  121.62  4982.8  112.97  5020.6  109.89  5077.6  109.89  5123.6  121.86
  5474.5  121.98  5510.3  127.37  5565.9  120.82  5685.3  124.36  5915.8  131.46
  6204.7  130.57  6290.9  125.92  6500.5   127.8    6664  129.26  6906.8  131.44
  6998.5  129.96  7365.7  142.75  7499.2   152.2  7520.5  158.54  7856.5  176.62
#Mann= 14 ,-1 , 0
   -4216     .17       0 -3664.2     .11       0 -3609.8     .17       0
 -3542.6     .11       0 -3240.3     .17       0 -2488.1     .15       0
 -2051.8     .17       0 -1540.6     .15       0  4952.3     .06       0
  5123.6     .15       0  5685.3     .17       0  6500.5     .11       0
    6664     .17       0  6906.8     .11       0
Bank Sta=4952.3,5123.6
XS Rating Curve= 0 ,0
Exp/Cntr=0.3,0.1

Chan Stop Cuts=-1
Use User Specified Reach Order=0
Composite Channel Slope=5