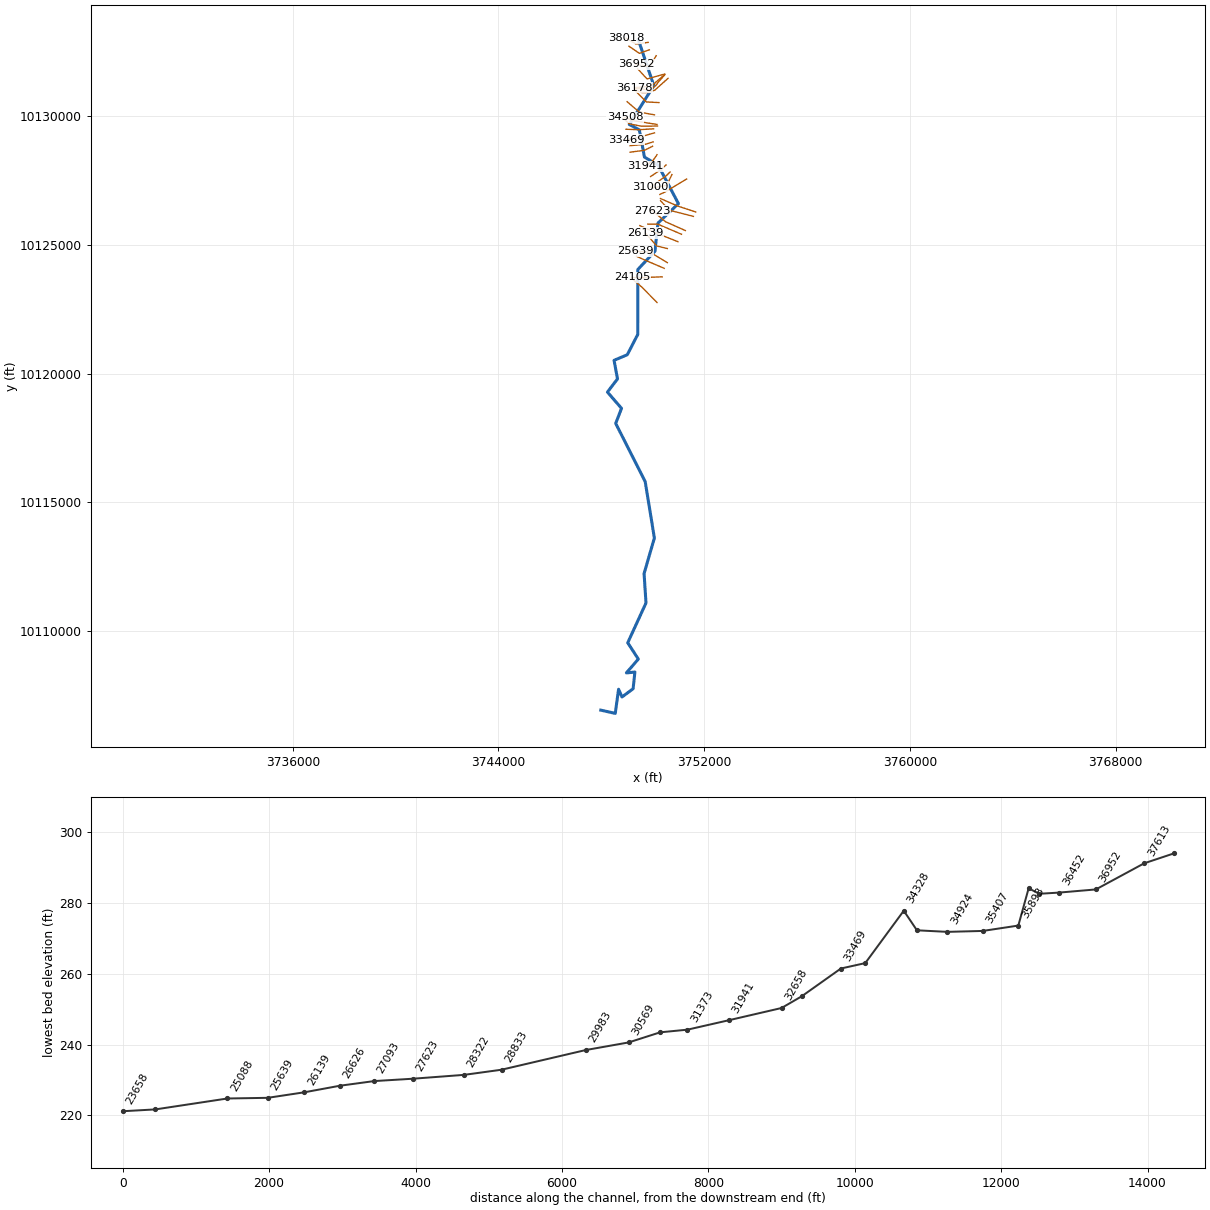
--- LANDRUM CREEK.prj (project) ---

Proj Title=LANDRUM CREEK Base Level Engineering
Current Plan=p01
Default Exp/Contr=0.3,0.1
English Units
Geom File=g01
Flow File=f01
Plan File=p01
Y Axis Title=Elevation
X Axis Title(PF)=Main Channel Distance
X Axis Title(XS)=Station
BEGIN DESCRIPTION:
LANDRUM CREEK
END DESCRIPTION:
DSS Export Rating Curves= 0
DSS Export Rating Curve Sorted= 0
DSS Export Volume Flow Curves= 0
DXF OffsetX= 0
DXF OffsetY= 0
DXF ScaleX= 1
DXF ScaleY= 10

--- LANDRUM CREEK.p01 (plan) ---

Plan Title=Multiple Run
Short Identifier=Multiple
Geom File=g01
Flow File=f01
Subcritical Flow
K Sum by GR= 0
Std Step Tol= 0.01
Critical Tol= 0.01
Num of Std Step Trials= 20
Max Error Tol= 0.3
Flow Tol Ratio= 0.001
Split Flow NTrial= 30
Split Flow Tol= 0.02
Split Flow Ratio= 0.02
Log Output Level= 0
Friction Slope Method= 1
Unsteady Friction Slope Method= 2
Unsteady Bridges Friction Slope Method= 1
Parabolic Critical Depth
Global Vel Dist=  1 , 1 , 1
Global Log Level= 0
CheckData=True
Encroach Param= -1, 0, 0, 0
BEGIN DESCRIPTION:
Multiple Run
END DESCRIPTION:

--- LANDRUM CREEK.f01 (steady flow) ---

Flow Title=Multiple
Program Version=4.10
Number of Profiles= 7
Profile Names=10-year,25-year,50-year,1pct_min,100-year,1pct_plu,500-year
River Rch & RM=LANDRUM CREEK,Reach-1         ,38018
     493     660     884     391    1180    3564    2174
River Rch & RM=LANDRUM CREEK,Reach-1         ,33802
     595     801    1078     477    1440    4349    2663
River Rch & RM=LANDRUM CREEK,Reach-1         ,28833
    1502    2112    2927    1329    4014   12122    7814
River Rch & RM=LANDRUM CREEK,Reach-1         ,20669
    2099    2989    4176    1909    5766   17413   11388
River Rch & RM=LANDRUM CREEK,Reach-1         ,12323
    2486    3549    4963    2271    6858   20711   13554
River Rch & RM=LANDRUM CREEK,Reach-1         ,10365
    2486    3549    4963    2271    6858   20711   13554
River Rch & RM=LANDRUM CREEK,Reach-1         ,4171
    2973    4264    5981    2742    8282   25011   16448
Boundary for River Rch & Prof#=LANDRUM CREEK,Reach-1         , 1
Up Type= 0
Dn Type= 3
Dn Slope=0.002
Boundary for River Rch & Prof#=LANDRUM CREEK,Reach-1         , 2
Up Type= 0
Dn Type= 3
Dn Slope=0.002
Boundary for River Rch & Prof#=LANDRUM CREEK,Reach-1         , 3
Up Type= 0
Dn Type= 3
Dn Slope=0.002
Boundary for River Rch & Prof#=LANDRUM CREEK,Reach-1         , 4
Up Type= 0
Dn Type= 3
Dn Slope=0.002
Boundary for River Rch & Prof#=LANDRUM CREEK,Reach-1         , 5
Up Type= 0
Dn Type= 3
Dn Slope=0.002
Boundary for River Rch & Prof#=LANDRUM CREEK,Reach-1         , 6
Up Type= 0
Dn Type= 3
Dn Slope=0.002
Boundary for River Rch & Prof#=LANDRUM CREEK,Reach-1         , 7
Up Type= 0
Dn Type= 3
Dn Slope=0.002
DSS Import GetInterval= 0
DSS Import GetPeak= 0
DSS Import FillOption= 0

--- LANDRUM CREEK.g01 (geometry) ---

Geom Title=Existing Conditions
Program Version=4.10

River Reach=LANDRUM CREEK   ,Reach-1
Reach XY= 30
      3749439.03     10132986.21      3750042.33     10131195.85
      3749088.23     10129686.84      3749478.23     10129476.84
      3749678.23     10128416.84      3750208.23     10128106.84
      3750998.59     10126609.21      3750202.24     10125850.04
      3750086.36     10124757.39      3749419.91     10124045.14
      3749417.49     10121519.99      3749010.05     10120730.54
      3748495.81     10120512.43      3748629.13     10119789.51
      3748237.38     10119277.49      3748786.31     10118646.04
      3748559.13     10118060.04      3749706.63     10115795.23
      3750063.89     10113601.23      3749662.84     10112219.28
       3749737.5     10111075.19      3749027.43     10109526.57
      3749438.89     10108892.89      3748975.51     10108355.32
      3749305.91     10108386.99       3749236.3     10107738.28
      3748802.91     10107418.05      3748671.71     10107719.15
      3748541.52     10106780.86      3747978.23     10106906.84

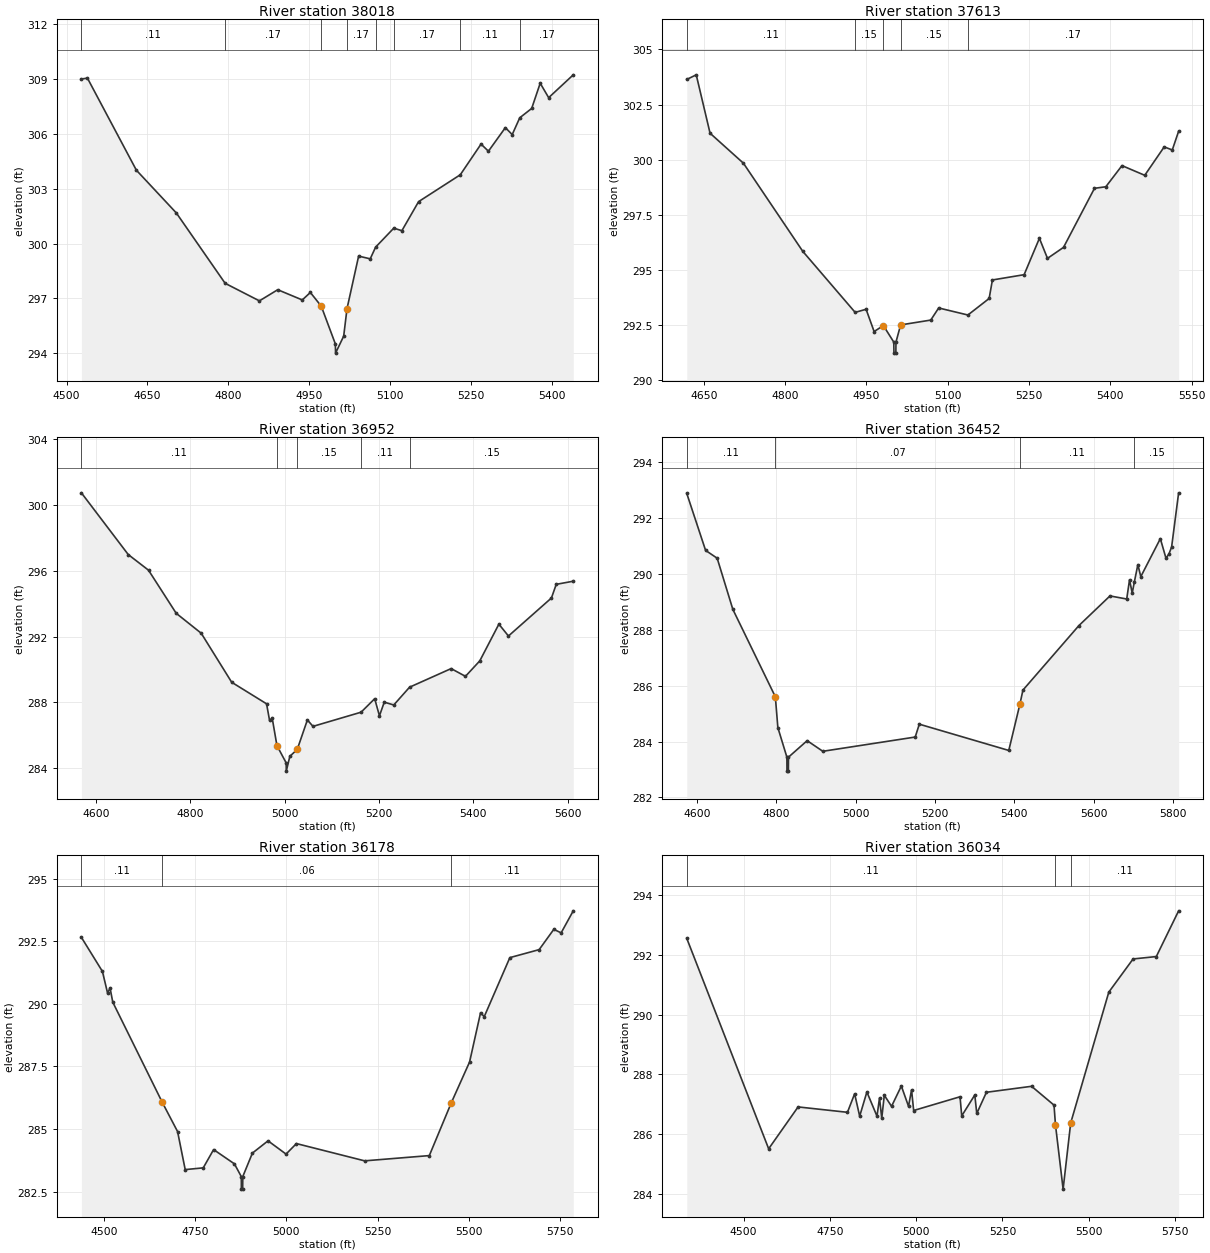
Type RM Length L Ch R = 1 ,38018   ,405,405,405
BEGIN DESCRIPTION:
LANDRUM CREEK 65.0
END DESCRIPTION:
XS GIS Cut Line= 3
        3749819.     10132878.35       3749346.8     10132817.59
      3748970.06     10133037.07
#Sta/Elev= 30
  4527.5  309.01  4538.7  309.06  4629.5  304.02  4703.6  301.68  4794.1  297.83
  4857.6  296.87  4891.6  297.48  4937.1  296.92  4952.1  297.33  4972.3  296.58
  4998.5  294.51  4998.8  294.01  5013.9  294.94  5020.1  296.45  5041.6  299.32
  5063.1  299.17  5073.1  299.81  5106.8  300.85  5121.8  300.71  5152.8   302.3
  5230.1  303.77  5268.6  305.45  5282.3  305.06  5313.7  306.35  5326.4  305.97
  5340.4  306.89  5362.5   307.4  5378.3  308.78    5394  307.99  5439.6  309.24
#Mann= 8 ,-1 , 0
  4527.5     .11       0  4794.1     .17       0  4972.3     .09       0
  5020.1     .17       0  5073.1     .15       0  5106.8     .17       0
  5230.1     .11       0  5340.4     .17       0
Bank Sta=4972.3,5020.1
XS Rating Curve= 0 ,0
Exp/Cntr=0.3,0.1

Type RM Length L Ch R = 1 ,37613   ,661,661,661
BEGIN DESCRIPTION:
Mapping XS 3b483a20
END DESCRIPTION:
XS GIS Cut Line= 3
      3749869.41     10132591.91      3749480.48     10132453.01
       3749072.7     10132732.38
#Sta/Elev= 30
  4618.7  303.64  4636.2  303.85  4661.7   301.2  4723.2  299.84  4832.7  295.84
  4929.3  293.07  4949.5  293.21  4964.3   292.2  4981.4  292.47  5000.6  291.72
  5000.9  291.22  5004.4  291.22  5004.6  291.72  5013.2   292.5  5068.8  292.72
  5083.4  293.27  5137.3  292.95  5176.5   293.7  5182.5  294.54    5241  294.78
  5269.2  296.43  5284.1  295.52  5313.7  296.02  5370.8   298.7  5391.7  298.77
  5421.5  299.73  5463.5  299.29  5499.4  300.58  5514.3  300.44    5526  301.29
#Mann= 5 ,-1 , 0
  4618.7     .11       0  4929.3     .15       0  4981.4     .09       0
  5013.2     .15       0  5137.3     .17       0
Bank Sta=4981.4,5013.2
XS Rating Curve= 0 ,0
Exp/Cntr=0.3,0.1

Type RM Length L Ch R = 1 ,36952   ,500,500,500
BEGIN DESCRIPTION:
Mapping XS 90754568
END DESCRIPTION:
XS GIS Cut Line= 3
      3750133.28     10132361.02      3749886.73     10131935.65
      3749342.21     10132025.82
#Sta/Elev= 30
  4568.6  300.74    4668  296.99    4711  296.04  4769.8  293.42  4822.8  292.21
  4887.5  289.23  4961.5  287.92  4967.8  286.92  4973.6  287.03  4983.5  285.38
  5003.1  284.33  5003.3  283.83  5010.9  284.73  5026.6  285.15  5048.1  286.94
    5060  286.55    5162  287.41  5190.9  288.23    5201  287.19  5211.2  288.02
  5231.4  287.85  5264.9  288.93  5353.1  290.06  5383.5  289.59  5413.9  290.53
  5454.4  292.76  5474.7  292.04  5565.9  294.35  5576.1  295.18  5612.2  295.37
#Mann= 5 ,-1 , 0
  4568.6     .11       0  4983.5     .09       0  5026.6     .15       0
    5162     .11       0  5264.9     .15       0
Bank Sta=4983.5,5026.6
XS Rating Curve= 0 ,0
Exp/Cntr=0.3,0.1

Type RM Length L Ch R = 1 ,36452   ,274,274,274
BEGIN DESCRIPTION:
Mapping XS 38d6506c
END DESCRIPTION:
XS GIS Cut Line= 3
      3750463.16     10131647.46      3749777.36     10131458.21
      3749419.29     10131847.42
#Sta/Elev= 30
  4574.2  292.88  4621.7  290.84  4650.9  290.56  4690.4  288.73  4797.6   285.6
  4803.9   284.5  4826.7  283.44  4826.9  282.94  4830.4  282.94  4830.7  283.44
  4877.8  284.03  4917.3  283.65  5150.3  284.16  5160.6  284.62  5386.2  283.68
  5414.5  285.35  5421.9  285.84  5563.1  288.15  5641.4  289.21  5683.6   289.1
  5690.7  289.79  5697.5  289.31  5702.7   289.7  5711.7  290.33  5719.1   289.9
  5768.4  291.26  5782.6  290.56    5790  290.71  5796.8  290.96  5814.5   292.9
#Mann= 4 ,-1 , 0
  4574.2     .11       0  4797.6     .07       0  5414.5     .11       0
  5702.7     .15       0
Bank Sta=4797.6,5414.5
XS Rating Curve= 0 ,0
Exp/Cntr=0.3,0.1

Type RM Length L Ch R = 1 ,36178   ,144,144,144
BEGIN DESCRIPTION:
Mapping XS 2895d314
END DESCRIPTION:
XS GIS Cut Line= 3
      3750466.63     10131633.59      3749938.82     10131171.76
      3749294.72     10131121.41
#Sta/Elev= 30
  4438.8  292.66  4496.4   291.3  4510.6  290.43  4517.3  290.64  4524.8  290.07
  4659.6  286.09  4702.3   284.9  4723.2  283.38  4772.6  283.45    4801  284.18
    4858  283.61  4876.9   283.1  4877.1   282.6  4880.6   282.6  4880.9   283.1
  4907.3  284.04  4950.1  284.53  4999.4     284  5027.9  284.42  5214.7  283.73
  5391.9  283.94  5452.1  286.05  5502.2  287.68  5532.3  289.65  5542.3  289.49
  5612.5  291.85  5692.8  292.17  5732.9  292.98    5753  292.84  5786.2  293.72
#Mann= 3 , 0 , 0
  4438.8     .11       0  4659.6     .06       0  5452.1     .11       0
Bank Sta=4659.6,5452.1
XS Rating Curve= 0 ,0
Exp/Cntr=0.3,0.1

Type RM Length L Ch R = 1 ,36034   ,141,141,141
BEGIN DESCRIPTION:
Mapping XS b98e2b37
END DESCRIPTION:
XS GIS Cut Line= 6
      3750468.35     10131616.23      3750225.28     10131345.37
      3750112.43     10131192.59      3749983.96      10131091.9
      3749867.64     10131031.13      3749296.46     10131102.31
#Sta/Elev= 30
    4335  292.55  4572.4  285.51  4657.7  286.91  4800.8  286.73  4821.6  287.35
  4836.2   286.6  4857.1  287.41  4886.4   286.6  4893.7  287.21  4900.2  286.53
  4907.6   287.3  4928.6  286.93    4957  287.61  4977.8  286.93  4986.6  287.48
  4992.7  286.79  5127.1  287.25    5132  286.61  5169.9  287.31  5175.6  286.69
  5203.6   287.4  5334.5   287.6  5399.5  286.97 5403.73  286.31  5425.9  284.16
  5447.8  286.37  5558.3  290.75  5628.7  291.86    5696  291.94  5760.7  293.47
#Mann= 3 , 0 , 0
    4335     .11       0 5403.73     .06       0  5447.8     .11       0
Bank Sta=5403.73,5447.8
XS Rating Curve= 0 ,0
Exp/Cntr=0.3,0.1

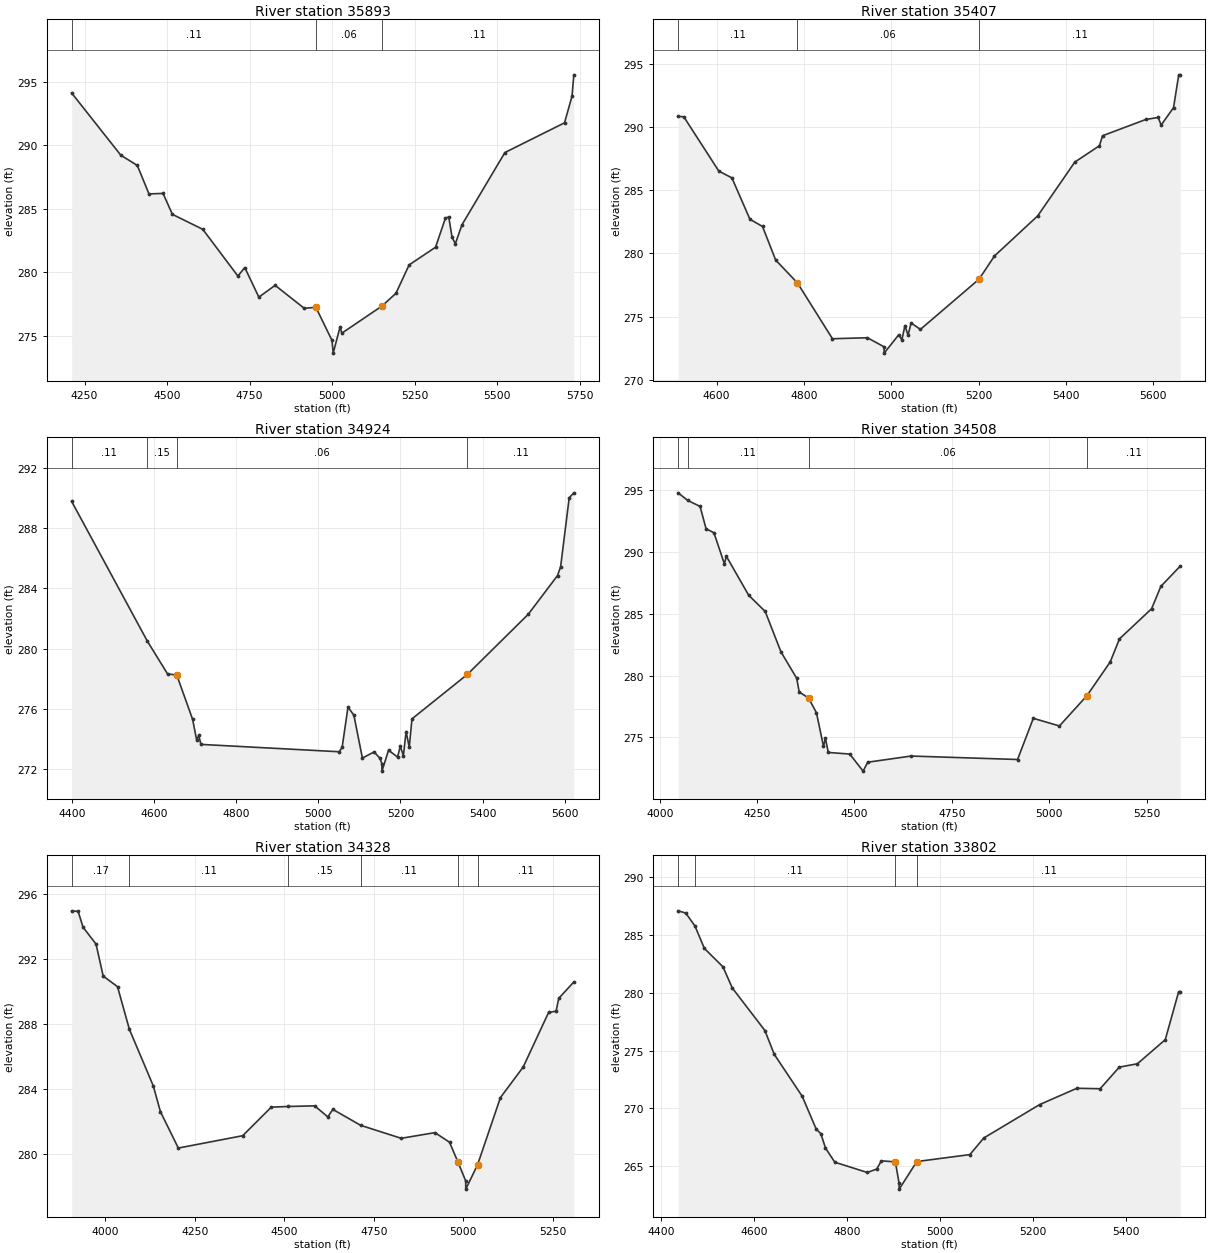
Type RM Length L Ch R = 1 ,35893   ,486,486,486
BEGIN DESCRIPTION:
Mapping XS 7f96e4a9
END DESCRIPTION:
XS GIS Cut Line= 5
       3750596.8     10131482.52      3750081.18     10131022.45
       3749846.8     10130930.44      3749565.55      10130928.7
      3749302.87     10131066.05
#Sta/Elev= 30
    4211  294.11  4359.8  289.21  4409.9   288.4  4445.1  286.16  4487.7   286.2
  4516.1  284.55  4608.1  283.37  4714.3  279.69  4735.2  280.36  4777.8  278.03
  4827.1  278.96  4915.2  277.15  4950.4  277.23  4999.3  274.62  5002.9  273.62
  5023.7  275.69    5029  275.19  5150.6  277.33  5192.8  278.33  5232.8  280.57
  5312.8  281.96  5342.8  284.26  5352.8  284.34  5362.8  282.74  5372.8  282.24
  5392.8  283.73  5522.8  289.42  5703.3  291.76  5725.9  293.85  5731.5  295.54
#Mann= 3 , 0 , 0
    4211     .11       0  4950.4     .06       0  5150.6     .11       0
Bank Sta=4950.4,5150.6
XS Rating Curve= 0 ,0
Exp/Cntr=0.3,0.1

Type RM Length L Ch R = 1 ,35407   ,483,483,483
BEGIN DESCRIPTION:
Mapping XS 24622606
END DESCRIPTION:
XS GIS Cut Line= 3
      3750240.94     10130538.07      3749753.05     10130562.38
      3749287.76     10131032.88
#Sta/Elev= 30
  4511.7  290.87  4524.8  290.83  4604.9  286.53  4634.9  285.99  4676.2  282.71
    4705  282.14  4735.1  279.48  4785.1  277.66  4865.2  273.24  4945.3  273.32
  4983.4   272.6  4983.6   272.1  5017.1  273.56  5024.2  273.15  5031.2  274.28
  5038.3  273.53  5045.4  274.49  5066.6  273.98  5200.9  277.96  5236.3   279.8
  5335.3  282.98  5420.2  287.24  5476.7  288.54  5483.8  289.33  5582.8  290.62
  5611.1  290.78  5618.1  290.18  5646.4  291.56  5658.3  294.16  5661.9  294.16
#Mann= 3 , 0 , 0
  4511.7     .11       0  4785.1     .06       0  5200.9     .11       0
Bank Sta=4785.1,5200.9
XS Rating Curve= 0 ,0
Exp/Cntr=0.3,0.1

Type RM Length L Ch R = 1 ,34924   ,416,416,416
BEGIN DESCRIPTION:
LANDRUM CREEK 64.0
END DESCRIPTION:
XS GIS Cut Line= 3
      3750067.88     10130061.07      3749476.35     10130167.94
      3749003.36     10130572.65
#Sta/Elev= 30
  4398.9   289.8    4583  280.51  4632.6  278.31    4655  278.24  4693.6  275.29
  4703.5  273.91  4708.6  274.22  4713.9  273.62  5050.7  273.13    5058  273.43
  5072.2   276.1  5086.5  275.57  5107.3  272.71  5135.9  273.12  5150.2  272.69
  5154.7  272.34    5155  271.84    5171  273.23    5193  272.78  5199.6  273.49
  5207.2  272.87  5213.8  274.47  5221.5  273.43  5228.1  275.32  5363.1  278.28
  5511.3  282.28  5582.7  284.86  5590.3  285.45  5611.2  290.04  5622.5  290.37
#Mann= 4 ,-1 , 0
  4398.9     .11       0    4583     .15       0    4655     .06       0
  5363.1     .11       0
Bank Sta=4655,5363.1
XS Rating Curve= 0 ,0
Exp/Cntr=0.3,0.1

Type RM Length L Ch R = 1 ,34508   ,180,180,180
BEGIN DESCRIPTION:
LANDRUM CREEK 63.0
END DESCRIPTION:
XS GIS Cut Line= 3
       3750168.7     10129687.26      3749227.62     10129836.23
      3748916.53     10129965.04
#Sta/Elev= 30
  4047.2  294.78  4071.6  294.17  4103.6  293.68  4118.9  291.88  4139.2  291.55
    4166  289.04  4171.1  289.65  4228.4   286.5  4270.8  285.19  4311.3  281.92
  4351.8  279.78  4358.1  278.68  4382.2  278.19  4402.4     277  4420.5  274.28
  4425.5  274.94  4432.8  273.79  4487.9  273.66  4522.2  272.28    4534     273
  4645.4   273.5  4918.8  273.22  4959.3  276.55  5026.3  275.93  5097.2  278.39
  5156.6   281.1  5180.4  282.97    5263  285.41  5286.8  287.22  5336.7  288.86
#Mann= 4 ,-1 , 0
  4047.2     .17       0  4071.6     .11       0  4382.2     .06       0
  5097.2     .11       0
Bank Sta=4382.2,5097.2
XS Rating Curve= 0 ,0
Exp/Cntr=0.3,0.1

Type RM Length L Ch R = 1 ,34328   ,526,526,526
BEGIN DESCRIPTION:
LANDRUM CREEK 62.0
END DESCRIPTION:
XS GIS Cut Line= 4
        3750186.      10129626.5      3749563.22     10129617.82
      3749090.13     10129711.13      3748867.86     10129911.06
#Sta/Elev= 30
  3905.5  294.95  3923.7  294.91  3937.4  293.94  3973.7   292.9  3993.7  290.93
  4033.7  290.28  4066.8  287.66  4133.7  284.17  4153.7  282.58  4203.7  280.34
  4383.7   281.1  4463.7  282.86  4511.3   282.9  4584.8  282.94  4621.6  282.26
  4635.7  282.72  4713.5  281.74  4826.8  280.94  4921.1  281.29  4961.9   280.7
  4985.9  279.46  5007.2  278.31  5007.4  277.81  5040.5  279.32  5104.3  283.45
  5167.9  285.33  5238.9  288.69  5259.8  288.77  5267.3  289.56  5309.5  290.57
#Mann= 6 ,-1 , 0
  3905.5     .17       0  4066.8     .11       0  4511.3     .15       0
  4713.5     .11       0  4985.9     .06       0  5040.5     .11       0
Bank Sta=4985.9,5040.5
XS Rating Curve= 0 ,0
Exp/Cntr=0.3,0.1

Type RM Length L Ch R = 1 ,33802   ,333,333,333
BEGIN DESCRIPTION:
LANDRUM CREEK 61.0
END DESCRIPTION:
XS GIS Cut Line= 3
      3750034.13     10129517.99       3749469.9     10129483.27
      3748955.59     10129500.63
#Sta/Elev= 30
  4436.5   287.1  4452.8  286.91  4472.7  285.79  4492.9  283.85    4533  282.25
    4553  280.42  4623.1  276.74  4643.2  274.68  4703.3  271.05  4733.3  268.22
  4743.4  267.81  4753.4  266.57  4773.4  265.34  4843.5  264.45  4863.6  264.75
  4873.6  265.46  4903.7  265.37  4911.7  263.51  4911.9  263.01 4949.83265.3975
  5063.9     266  5093.9  267.44    5214  270.33    5294  271.74    5344   271.7
  5385.2  273.57  5424.1  273.86  5484.1  275.95  5512.8  280.09  5516.4  280.09
#Mann= 4 ,-1 , 0
  4436.5     .17       0  4472.7     .11       0  4903.7     .06       0
 4949.83     .11       0
Bank Sta=4903.7,4949.83
XS Rating Curve= 0 ,0
Exp/Cntr=0.3,0.1

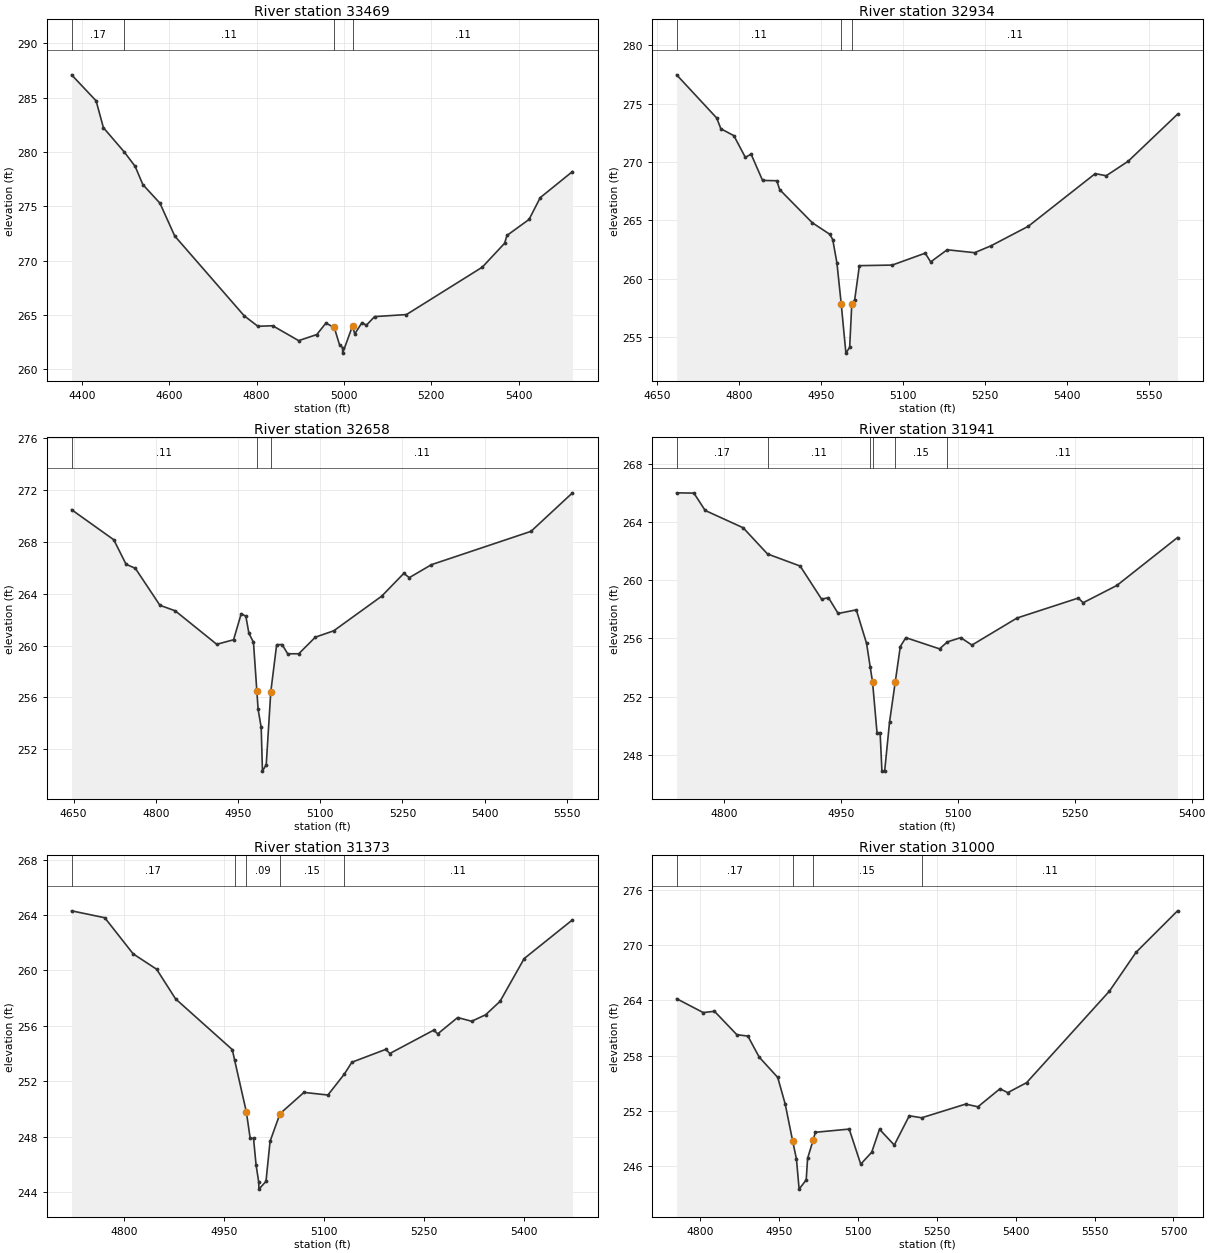
Type RM Length L Ch R = 1 ,33469   ,535,535,535
BEGIN DESCRIPTION:
LANDRUM CREEK 60.0
END DESCRIPTION:
XS GIS Cut Line= 3
      3750067.89     10129361.08      3749465.56      10129190.3
      3748955.57     10129086.13
#Sta/Elev= 30
  4376.7  287.09  4432.8   284.7  4449.5  282.23  4497.5  279.98  4522.3  278.66
  4539.8  276.99  4578.9  275.28  4612.8  272.26  4771.7  264.92  4803.2  263.95
  4837.1     264  4896.5  262.63    4938  263.19  4958.8  264.24    4978  263.84
    4990  262.25    4997  261.98  4997.2  261.48  5019.8  263.99  5024.9  263.25
  5041.3  264.28  5051.5  264.05  5070.3  264.84  5143.3  265.03  5316.8  269.39
  5367.9  271.59  5373.3  272.31  5423.8  273.78  5449.5  275.79  5523.3  278.19
#Mann= 4 ,-1 , 0
  4376.7     .17       0  4497.5     .11       0    4978     .07       0
  5019.8     .11       0
Bank Sta=4978,5019.8
XS Rating Curve= 0 ,0
Exp/Cntr=0.3,0.1

Type RM Length L Ch R = 1 ,32934   ,276,276,276
BEGIN DESCRIPTION:
LANDRUM CREEK 59.0
END DESCRIPTION:
XS GIS Cut Line= 3
      3750017.86     10129011.07      3749718.23     10128916.84
      3749117.82     10128861.07
#Sta/Elev= 30
  4685.9  277.46  4759.3  273.76  4766.9  272.84  4790.7  272.25  4811.7  270.39
  4822.2  270.67  4843.2  268.42  4869.3  268.39  4874.6  267.63  4934.1   264.8
  4966.5   263.8  4971.7  263.35  4979.4  261.34 4987.27257.8247  4995.8  253.63
  5002.7  254.13  5006.6257.8538  5011.9   258.2  5020.5  261.12  5080.7  261.17
    5141  262.19    5151  261.44  5181.2  262.48  5231.4  262.23  5261.5  262.82
  5329.7  264.49  5452.3     269  5472.4  268.82  5512.6  270.06    5603  274.09
#Mann= 3 ,-1 , 0
  4685.9     .11       0 4987.27     .07       0  5006.6     .11       0
Bank Sta=4987.27,5006.6
XS Rating Curve= 0 ,0
Exp/Cntr=0.3,0.1

Type RM Length L Ch R = 1 ,32658   ,717,717,717
BEGIN DESCRIPTION:
LANDRUM CREEK 58.0
END DESCRIPTION:
XS GIS Cut Line= 3
      3749995.06     10128838.73      3749680.41     10128682.49
      3749122.77     10128608.71
#Sta/Elev= 30
  4646.5  270.48  4723.5  268.16  4745.9  266.27  4762.8  265.96  4807.6  263.11
  4835.6  262.68  4911.3   260.1    4942  260.45    4956  262.46  4964.4  262.26
    4970  260.95  4978.3  260.26 4984.45256.5119  4986.8  255.08  4992.4  253.69
  4994.7  250.32  5001.6  250.82 5009.93256.4452  5020.6  260.07  5030.6  260.08
  5040.7  259.37  5060.9  259.37  5091.2  260.65  5124.7  261.14  5212.2  263.81
  5252.6  265.57  5262.6  265.24    5303  266.24  5484.6  268.81  5560.3  271.78
#Mann= 3 ,-1 , 0
  4646.5     .11       0 4984.45     .07       0 5009.93     .11       0
Bank Sta=4984.45,5009.93
XS Rating Curve= 0 ,0
Exp/Cntr=0.3,0.1

Type RM Length L Ch R = 1 ,31941   ,568,568,568
BEGIN DESCRIPTION:
LANDRUM CREEK 57.0
END DESCRIPTION:
XS GIS Cut Line= 3
      3750167.85     10128511.07      3750018.23     10128296.84
      3749717.82     10128061.05
#Sta/Elev= 30
  4738.7     266  4760.9  265.98  4775.3  264.79  4824.1   263.6  4855.4   261.8
  4897.3  260.97  4924.9  258.69  4933.6   258.8  4946.1  257.71  4969.4  257.96
  4982.6  255.65  4987.3  254.02  4990.3  252.98    4996  249.52    5000  249.52
  5002.3  246.88  5005.8  246.88  5012.1  250.26 5019.47253.0265  5025.9  255.44
    5033  256.05  5076.3  255.28  5086.4  255.76  5103.5  256.05  5117.9  255.54
  5175.8   257.4  5254.4  258.77  5260.7  258.45  5304.1  259.64  5381.9  262.93
#Mann= 6 ,-1 , 0
  4738.7     .17       0  4855.4     .11       0  4987.3     .15       0
  4990.3     .09       0 5019.47     .15       0  5086.4     .11       0
Bank Sta=4990.3,5019.47
XS Rating Curve= 0 ,0
Exp/Cntr=0.3,0.1

Type RM Length L Ch R = 1 ,31373   ,373,373,373
BEGIN DESCRIPTION:
LANDRUM CREEK 56.0
END DESCRIPTION:
XS GIS Cut Line= 3
      3750517.89      10128111.1      3750314.09     10127929.45
      3749917.83     10127661.06
#Sta/Elev= 30
  4720.9  264.31  4770.7  263.81  4813.3   261.2  4848.5  260.09  4876.9  257.95
  4962.1  254.28  4965.4  253.55  4983.1  249.79  4988.9  247.87  4993.9  247.87
  4997.7  245.96  5001.7   244.7    5002   244.2  5012.6  244.76  5018.7  247.65
  5033.6  249.65  5069.6  251.19  5105.5     251  5130.1  252.51  5141.5  253.37
  5192.4   254.3  5198.4     254  5264.3  255.69  5270.3  255.42  5300.2   256.6
  5321.2  256.33  5342.2   256.8  5363.8  257.77    5400  260.86  5472.5  263.66
#Mann= 5 ,-1 , 0
  4720.9     .17       0  4965.4     .15       0  4983.1     .09       0
  5033.6     .15       0  5130.1     .11       0
Bank Sta=4983.1,5033.6
XS Rating Curve= 0 ,0
Exp/Cntr=0.3,0.1

Type RM Length L Ch R = 1 ,31000   ,431,431,431
BEGIN DESCRIPTION:
LANDRUM CREEK 55.0
END DESCRIPTION:
XS GIS Cut Line= 3
      3750674.37     10127836.17      3750496.38     10127669.03
      3749917.82     10127261.05
#Sta/Elev= 30
  4755.6  264.19  4806.1  262.68  4827.5  262.82    4870  260.27    4891  260.12
  4912.5  257.83  4947.7  255.62  4961.9  252.73    4976  248.72  4983.3  246.74
  4988.4  243.45  5001.9  244.46  5004.5   246.8 5014.94 248.763  5019.3  249.64
  5083.6  249.99  5105.5  246.17  5126.4  247.47  5141.2  249.97  5169.3  248.25
  5197.8  251.44  5221.3  251.22  5304.9  252.71  5328.3  252.42  5370.2  254.38
    5385  253.96  5420.7  255.04  5578.3  265.02  5628.9  269.25  5707.7  273.76
#Mann= 4 ,-1 , 0
  4755.6     .17       0    4976     .09       0 5014.94     .15       0
  5221.3     .11       0
Bank Sta=4976,5014.94
XS Rating Curve= 0 ,0
Exp/Cntr=0.3,0.1

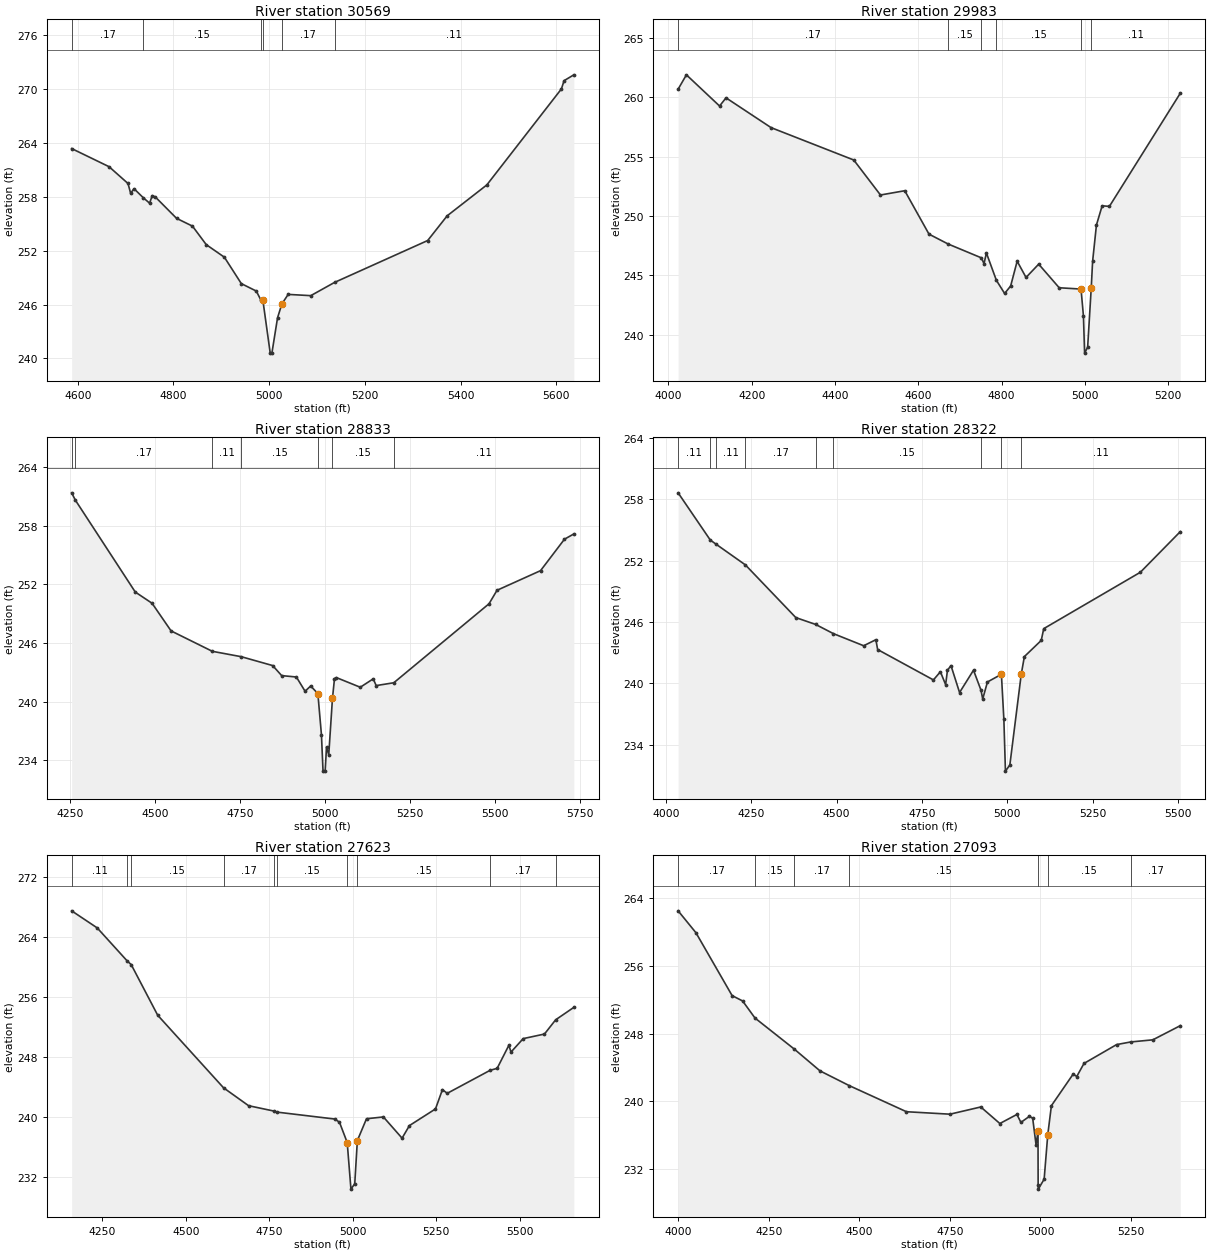
Type RM Length L Ch R = 1 ,30569   ,586,586,586
BEGIN DESCRIPTION:
LANDRUM CREEK 54.0
END DESCRIPTION:
XS GIS Cut Line= 3
      3750745.93     10127738.45      3750544.12     10127321.81
      3749967.81     10127211.06
#Sta/Elev= 30
  4587.1  263.37  4665.3  261.35  4704.9  259.48  4710.4  258.39  4717.5   258.9
  4736.5  257.91    4750  257.29  4755.6  258.13    4762  257.98  4806.4   255.6
  4839.7  254.73  4868.5  252.67  4906.4  251.27  4941.8  248.33  4973.1   247.5
  4982.4  246.53  4986.9  246.46  5002.2  240.59  5005.7  240.59  5017.5  244.52
  5026.5  246.06  5039.7  247.13    5087  246.99  5136.9  248.47  5331.4  253.13
  5372.1  255.88    5455  259.32  5610.9  270.01  5616.5  270.93  5636.9  271.58
#Mann= 6 ,-1 , 0
  4587.1     .17       0  4736.5     .15       0  4982.4     .17       0
  4986.9     .09       0  5026.5     .17       0  5136.9     .11       0
Bank Sta=4986.9,5026.5
XS Rating Curve= 0 ,0
Exp/Cntr=0.3,0.1

Type RM Length L Ch R = 1 ,29983   ,1150,1150,1150
BEGIN DESCRIPTION:
LANDRUM CREEK 53.0
END DESCRIPTION:
XS GIS Cut Line= 3
      3751318.83     10127567.02      3750481.19     10127061.39
      3750275.22       10126966.
#Sta/Elev= 30
  4023.4  260.69  4043.3   261.9  4122.9  259.27  4138.4  259.96  4246.5  257.45
    4445  254.72  4509.1  251.77  4567.4  252.13  4625.6  248.47  4671.4  247.64
  4751.4  246.47  4757.6  245.98  4763.4  246.88  4787.3  244.58  4807.1  243.47
  4821.6   244.1  4837.2  246.19  4858.5  244.82  4888.9  245.94  4938.1  243.95
  4990.5  243.84  4996.3  241.57  4999.1  238.44  5006.4  238.94 5015.01243.9314
  5018.3  246.17  5027.5  249.24  5041.2  250.86  5058.6  250.81  5228.8  260.35
#Mann= 6 ,-1 , 0
  4023.4     .17       0  4671.4     .15       0  4751.4     .17       0
  4787.3     .15       0  4990.5     .06       0 5015.01     .11       0
Bank Sta=4990.5,5015.01
XS Rating Curve= 0 ,0
Exp/Cntr=0.3,0.1

Type RM Length L Ch R = 1 ,28833   ,511,511,511
BEGIN DESCRIPTION:
LANDRUM CREEK 52.0
END DESCRIPTION:
XS GIS Cut Line= 3
      3751675.55     10126281.44      3750967.99     10126514.64
      3750296.92     10126806.79
#Sta/Elev= 30
    4255  261.38  4266.1  260.62  4442.1  251.22  4491.5  250.07  4547.4  247.24
  4668.7  245.15  4753.6   244.6  4846.2  243.69  4872.7  242.66  4915.9  242.52
  4941.5  241.06    4958   241.6  4979.1  240.82  4989.6  236.61  4994.3  232.88
  5000.5  232.88  5004.6  235.34  5011.1  234.55    5022  240.32    5028  242.35
  5033.5  242.46  5103.8  241.47  5141.9  242.33  5150.6  241.64  5202.4  241.93
  5482.5  250.02    5506   251.4    5634  253.41  5704.3  256.63  5731.9  257.17
#Mann= 7 ,-1 , 0
    4255     .11       0  4266.1     .17       0  4668.7     .11       0
  4753.6     .15       0  4979.1     .09       0    5022     .15       0
  5202.4     .11       0
Bank Sta=4979.1,5022
XS Rating Curve= 0 ,0
Exp/Cntr=0.3,0.1

Type RM Length L Ch R = 1 ,28322   ,699,699,699
BEGIN DESCRIPTION:
LANDRUM CREEK 51.0
END DESCRIPTION:
XS GIS Cut Line= 3
      3751581.76     10126112.18       3750647.8     10126350.96
      3750303.13     10126721.55
#Sta/Elev= 30
    4036  258.62  4130.1  254.01  4145.9  253.63  4232.9  251.58  4380.6  246.43
  4438.7  245.76  4490.8  244.86  4579.2  243.68  4614.9  244.27  4620.1  243.31
  4783.4  240.34  4803.8  241.14  4819.1  239.88  4824.5  241.29  4834.8  241.74
  4859.9  239.11  4900.7  241.29  4922.6  239.34  4927.7  238.48  4941.5  240.14
  4982.4  240.89  4989.6  236.48  4994.2  231.43  5007.1  232.03 5040.44 240.886
  5049.6  242.62    5099   244.2  5106.3  245.35  5389.2  250.86  5506.1  254.83
#Mann= 9 ,-1 , 0
    4036     .11       0  4130.1     .17       0  4145.9     .11       0
  4232.9     .17       0  4438.7     .11       0  4490.8     .15       0
  4922.6     .11       0  4982.4     .06       0 5040.44     .11       0
Bank Sta=4982.4,5040.44
XS Rating Curve= 0 ,0
Exp/Cntr=0.3,0.1

Type RM Length L Ch R = 1 ,27623   ,530,530,530
BEGIN DESCRIPTION:
LANDRUM CREEK 50.0
END DESCRIPTION:
XS GIS Cut Line= 3
      3751267.82     10125561.09      3750498.42     10125903.37
      3749993.25     10126330.91
#Sta/Elev= 30
  4157.9  267.47  4234.5  265.19  4324.7  260.76  4336.2   260.3  4415.6  253.54
  4612.7  243.86  4687.8  241.47  4764.2  240.75  4773.8  240.61  4945.9  239.69
  4959.9  239.27  4983.1  236.56  4994.3  230.34  5005.7  231.06  5013.5  236.82
  5040.9  239.73  5091.5  239.97  5147.4  237.14  5169.5  238.82  5247.5  241.04
  5268.3  243.62  5282.6  243.12  5411.4   246.2  5432.1  246.45  5467.2  249.53
  5473.7  248.63  5510.1  250.42  5573.8  251.03  5607.3  252.93  5661.8  254.59
#Mann= 10 ,-1 , 0
  4157.9     .11       0  4324.7     .17       0  4336.2     .15       0
  4612.7     .17       0  4764.2     .11       0  4773.8     .15       0
  4983.1     .09       0  5013.5     .15       0  5411.4     .17       0
  5607.3     .11       0
Bank Sta=4983.1,5013.5
XS Rating Curve= 0 ,0
Exp/Cntr=0.3,0.1

Type RM Length L Ch R = 1 ,27093   ,467,467,467
BEGIN DESCRIPTION:
LANDRUM CREEK 49.0
END DESCRIPTION:
XS GIS Cut Line= 3
      3751118.24     10125416.86      3750198.04     10125809.32
      3749811.94     10125810.09
#Sta/Elev= 30
  3999.6  262.46  4048.8  259.88  4148.7  252.47  4177.7  251.84  4211.8  249.83
  4320.9  246.15  4391.4   243.6  4472.4  241.86    4630  238.79  4750.2   238.5
  4835.2  239.35  4887.9   237.4    4935  238.47    4946  237.53  4969.6  238.25
  4978.5  238.03  4987.8   234.9  4993.2  236.48  4993.6  230.17  4994.1  229.67
  5010.2  230.85  5020.2  236.09  5030.2   239.5  5090.2  243.22  5100.2  242.94
  5120.2  244.48  5210.2   246.7  5249.1  247.01  5310.2  247.26  5386.1  248.93
#Mann= 7 ,-1 , 0
  3999.6     .17       0  4211.8     .15       0  4320.9     .17       0
  4472.4     .15       0  4993.2     .09       0  5020.2     .15       0
  5249.1     .17       0
Bank Sta=4993.2,5020.2
XS Rating Curve= 0 ,0
Exp/Cntr=0.3,0.1

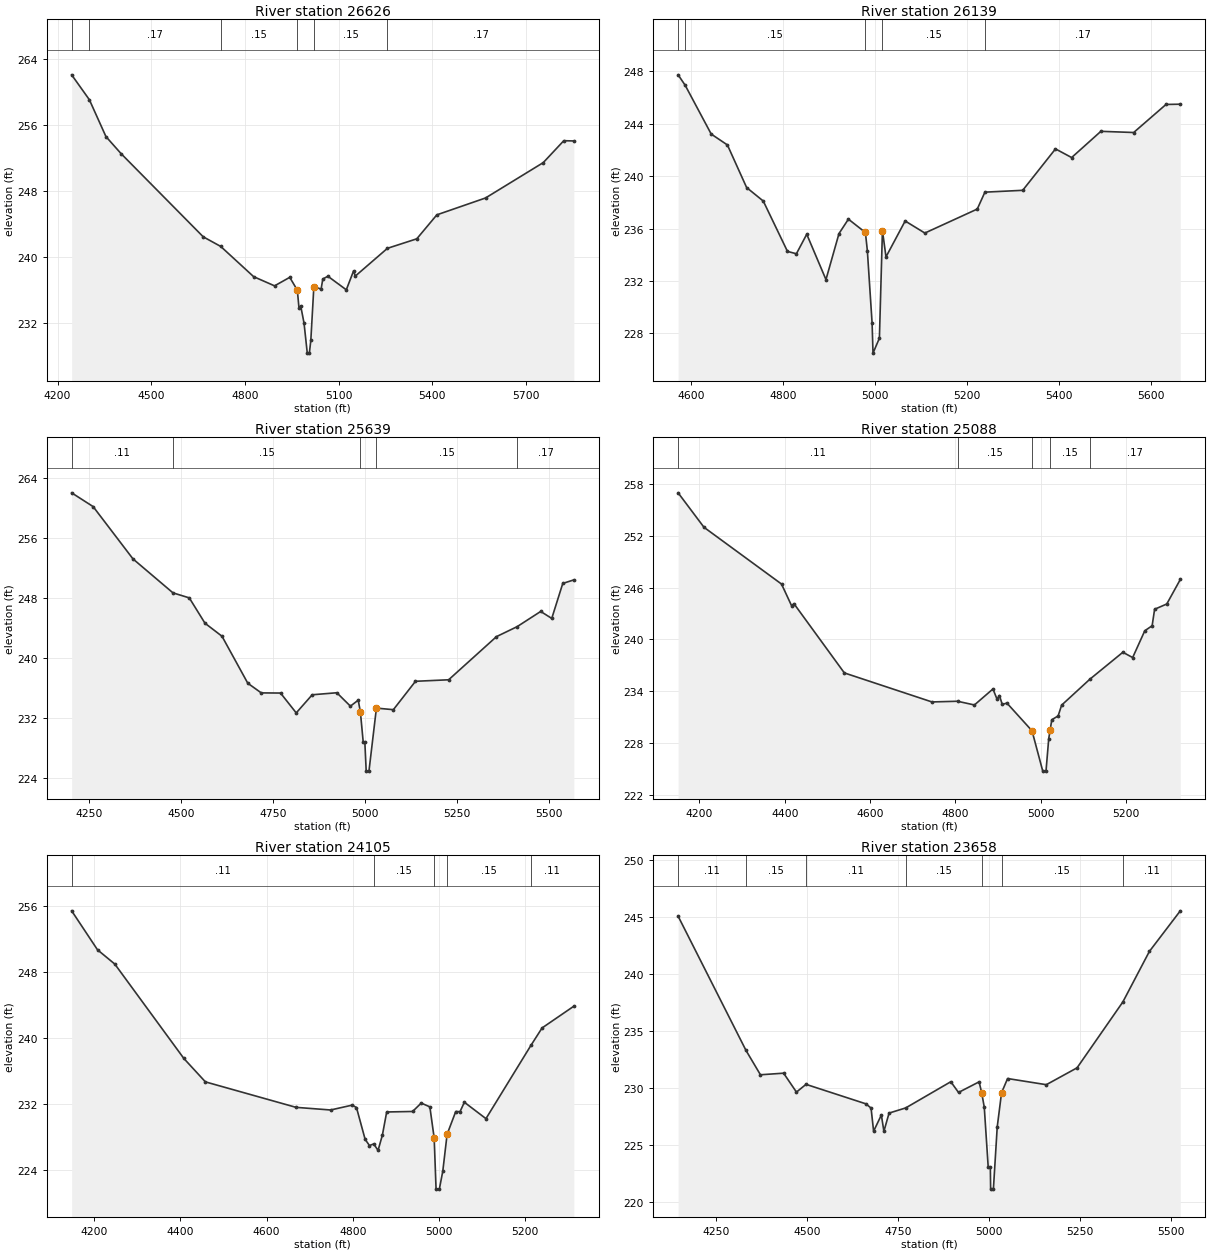
Type RM Length L Ch R = 1 ,26626   ,487,487,487
BEGIN DESCRIPTION:
LANDRUM CREEK 48.0
END DESCRIPTION:
XS GIS Cut Line= 3
      3750979.56      10125127.4      3750278.01     10125405.89
      3749498.42     10125752.81
#Sta/Elev= 30
  4245.2  262.03  4301.9  259.02    4355  254.56  4403.6  252.49  4666.6  242.43
  4722.5  241.27    4828  237.61    4895   236.5  4943.6  237.53  4967.9  235.97
  4973.3  233.76  4978.7  234.07  4989.4  231.98  4999.7  228.36  5006.4  228.36
  5011.1  229.92  5020.8   236.4    5044  236.11  5049.5  237.33  5065.8  237.66
  5124.7  236.02    5148  238.31  5153.5  237.68  5256.4  241.04  5350.4  242.19
  5414.6  245.09  5570.5  247.13  5755.4  251.41  5821.1  254.06  5853.3  254.03
#Mann= 6 ,-1 , 0
  4245.2     .11       0  4301.9     .17       0  4722.5     .15       0
  4967.9     .09       0  5020.8     .15       0  5256.4     .17       0
Bank Sta=4967.9,5020.8
XS Rating Curve= 0 ,0
Exp/Cntr=0.3,0.1

Type RM Length L Ch R = 1 ,26139   ,500,500,500
BEGIN DESCRIPTION:
LANDRUM CREEK 47.0
END DESCRIPTION:
XS GIS Cut Line= 3
      3750567.82     10124861.08       3750152.4     10124961.55
      3749718.46     10125464.93
#Sta/Elev= 30
  4572.6  247.73    4588  246.93  4644.6  243.21  4679.8  242.38  4721.6  239.13
  4757.8   238.1  4810.4  234.26  4829.8  234.08  4852.3  235.57  4894.1  232.11
  4922.4  235.62  4942.9  236.72 4979.83235.7026  4984.1  234.32  4994.4   228.8
  4996.4   226.5  5010.3  227.64  5016.9  235.85  5024.6  233.84  5066.3  236.58
  5109.1  235.66  5223.1  237.49  5239.7  238.78  5321.9  238.92  5393.2  242.08
  5428.3  241.42  5491.9  243.42  5563.2  243.33  5633.5  245.47  5664.6  245.49
#Mann= 5 ,-1 , 0
  4572.6     .17       0    4588     .15       0 4979.83     .09       0
  5016.9     .15       0  5239.7     .17       0
Bank Sta=4979.83,5016.9
XS Rating Curve= 0 ,0
Exp/Cntr=0.3,0.1

Type RM Length L Ch R = 1 ,25639   ,551,551,551
BEGIN DESCRIPTION:
LANDRUM CREEK 46.0
END DESCRIPTION:
XS GIS Cut Line= 3
      3750567.89     10124311.05      3749885.33     10124724.09
      3749317.84     10124761.07
#Sta/Elev= 30
  4202.2  262.08  4260.7  260.24  4369.1  253.26  4477.9  248.73  4522.3  248.06
    4565  244.68  4611.3  242.94  4681.5  236.67  4718.2  235.38  4770.6  235.36
  4813.3  232.71  4856.8  235.13  4923.8   235.4  4960.7  233.61    4982  234.41
  4987.9  232.83  4995.6   228.8    5000   228.8  5003.7  224.94  5011.2  224.94
  5031.5  233.35  5077.6  233.14  5137.8  236.93    5228  237.13  5358.2  242.89
  5414.4  244.22  5478.5  246.25  5508.6  245.32  5538.6  249.99  5568.7  250.46
#Mann= 5 ,-1 , 0
  4202.2     .11       0  4477.9     .15       0  4987.9     .09       0
  5031.5     .15       0  5414.4     .17       0
Bank Sta=4987.9,5031.5
XS Rating Curve= 0 ,0
Exp/Cntr=0.3,0.1

Type RM Length L Ch R = 1 ,25088   ,983,983,983
BEGIN DESCRIPTION:
LANDRUM CREEK 45.0
END DESCRIPTION:
XS GIS Cut Line= 3
      3750446.31     10124091.36      3749664.69      10124424.6
      3749367.85     10124561.07
#Sta/Elev= 30
  4150.3  256.97  4210.9  252.98  4392.5  246.41  4416.1   243.9  4421.6  244.14
  4539.7  236.12  4744.9  232.76  4804.8  232.84  4844.4  232.41  4887.8  234.26
  4897.5  233.07    4903   233.5  4909.6  232.47  4920.5  232.63  4979.3  229.42
  5004.5  224.75  5012.1  224.75  5018.5  228.52 5021.85229.5343  5025.7   230.7
  5040.5  231.14  5048.7  232.39  5114.8  235.39  5192.1  238.51  5215.1   237.9
  5243.5     241  5260.7  241.58  5266.5  243.49    5295   244.1  5326.7  246.94
#Mann= 5 ,-1 , 0
  4150.3     .11       0  4804.8     .15       0  4979.3     .09       0
 5021.85     .15       0  5114.8     .17       0
Bank Sta=4979.3,5021.85
XS Rating Curve= 0 ,0
Exp/Cntr=0.3,0.1

Type RM Length L Ch R = 1 ,24105   ,447,447,447
BEGIN DESCRIPTION:
LANDRUM CREEK 44.0
END DESCRIPTION:
XS GIS Cut Line= 3
      3750367.84     10123761.07      3749516.36     10123726.08
      3749204.15     10123737.18
#Sta/Elev= 30
  4147.8  255.43  4207.8   250.7  4247.9  248.97    4408  237.52    4458  234.68
  4668.2  231.59  4748.3  231.27  4798.3  231.86  4808.3  231.57  4828.4  227.71
  4838.4  226.96  4848.3  227.15  4858.4  226.37  4868.4  228.22  4878.4  231.03
  4938.5  231.09  4958.5  232.11  4978.5  231.65  4988.5  227.88  4992.9  221.67
  5000.5  221.67  5008.5  223.85  5018.5  228.32  5038.5  231.08  5048.5  231.07
  5058.5  232.21  5108.6  230.22  5212.8   239.1  5238.7  241.22  5312.4  243.86
#Mann= 5 ,-1 , 0
  4147.8     .11       0  4848.3     .15       0  4988.5     .09       0
  5018.5     .15       0  5212.8     .11       0
Bank Sta=4988.5,5018.5
XS Rating Curve= 0 ,0
Exp/Cntr=0.3,0.1

Type RM Length L Ch R = 1 ,23658   ,500,500,500
BEGIN DESCRIPTION:
LANDRUM CREEK 43.0
END DESCRIPTION:
XS GIS Cut Line= 3
      3750167.88     10122761.05       3749567.3     10123370.16
      3749167.89     10123711.04
#Sta/Elev= 30
  4144.6  245.09  4331.3  233.31  4370.9  231.18  4434.6  231.32  4469.9  229.66
  4496.2  230.34  4660.9  228.63    4675  228.26    4682  226.23  4703.3  227.65
  4710.3  226.22  4724.5  227.82  4770.1  228.27  4894.2  230.57  4915.4  229.63
    4972  230.56    4979  229.62  4986.2  228.34  4997.1  223.05  5002.9  223.05
  5003.7  221.15  5011.3  221.15  5021.8   226.6 5033.74 229.605  5050.3  230.85
  5156.8  230.31  5241.3  231.79  5367.2  237.57  5440.1     242  5525.1  245.56
#Mann= 7 ,-1 , 0
  4144.6     .11       0  4331.3     .15       0  4496.2     .11       0
  4770.1     .15       0    4979     .09       0 5033.74     .15       0
  5367.2     .11       0
Bank Sta=4979,5033.74
XS Rating Curve= 0 ,0
Exp/Cntr=0.3,0.1