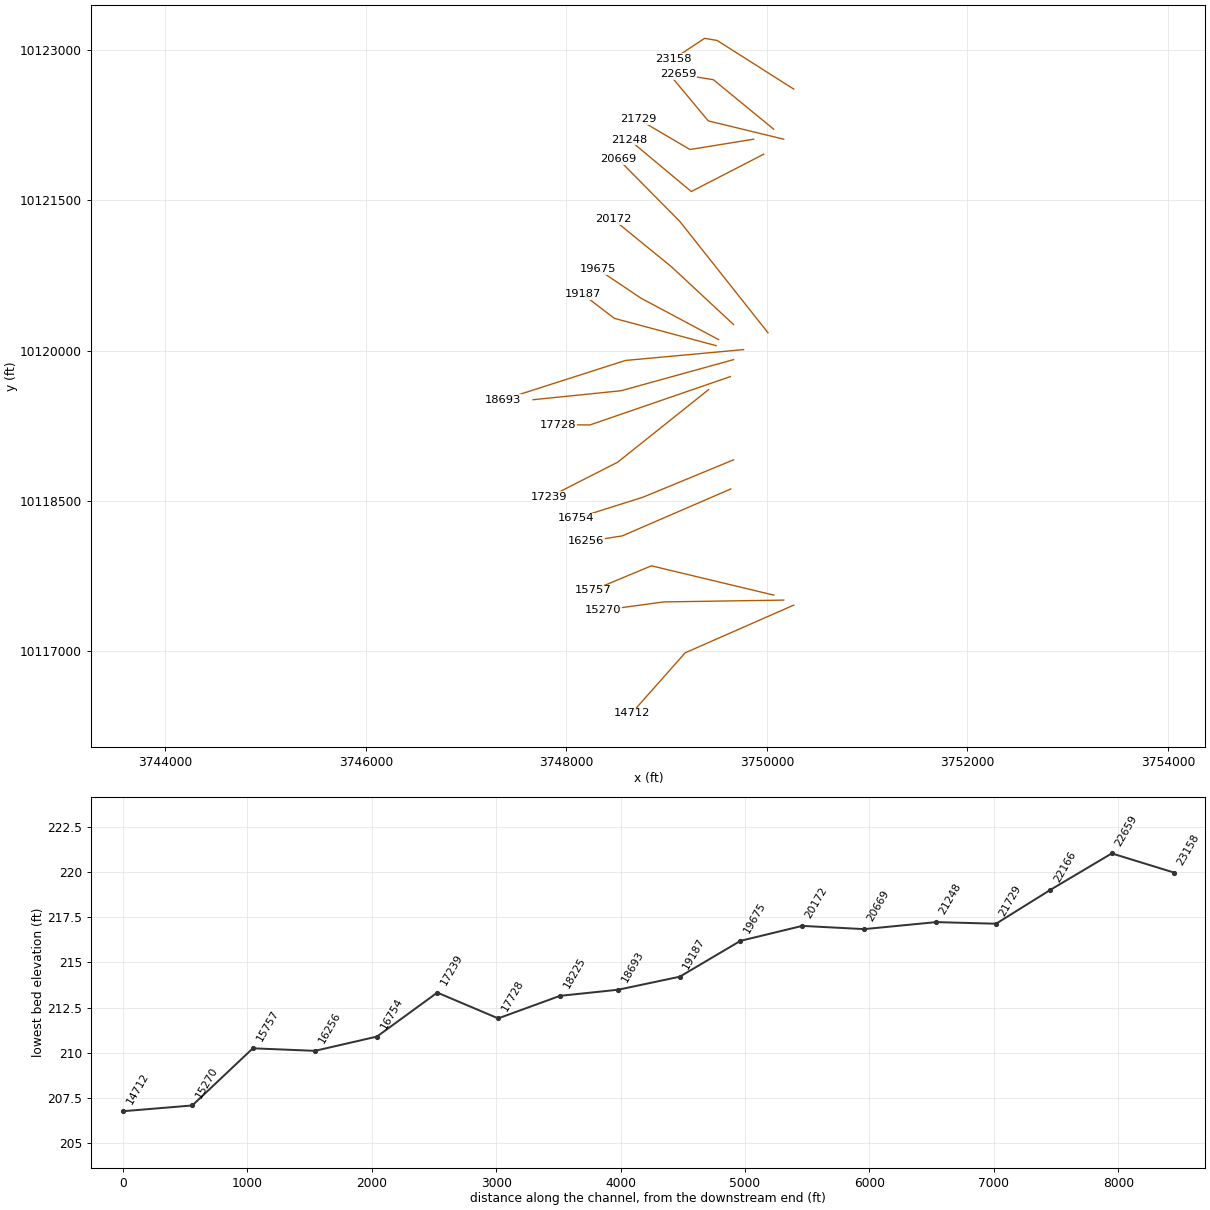
HEC-RAS study LANDRUM CREEK.prj: LANDRUM CREEK Base Level Engineering

--- LANDRUM CREEK.g01 (geometry) --- (continued)

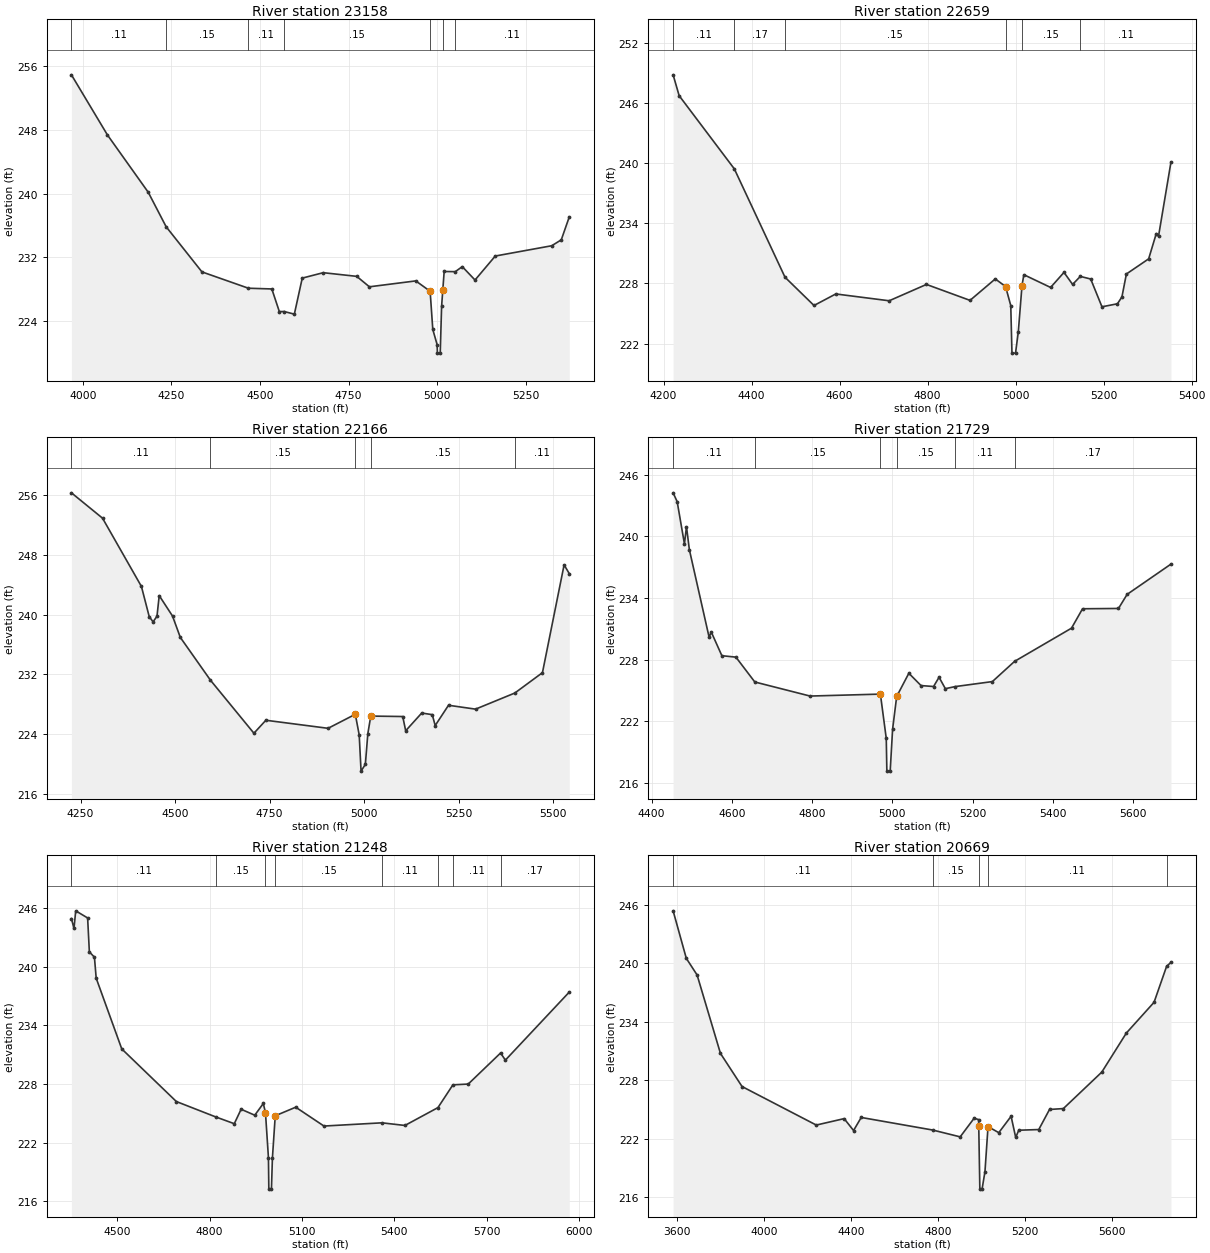
Type RM Length L Ch R = 1 ,23158   ,499,499,499
BEGIN DESCRIPTION:
LANDRUM CREEK 42.0
END DESCRIPTION:
XS GIS Cut Line= 4
      3750267.83     10122611.09      3749503.65     10123096.55
      3749378.46      10123117.7      3749067.82     10122911.05
#Sta/Elev= 30
  3967.7   254.9  4069.3  247.36  4184.5  240.17  4235.1  235.84  4336.1  230.18
  4467.4  228.13  4533.4  228.04  4554.6   225.2    4568  225.21    4597  224.88
  4619.3   229.4  4678.5  230.08  4773.1  229.62  4808.8  228.31  4939.8  229.05
  4980.3  227.75  4987.8  222.96    5000  221.06  5000.8  219.99  5008.8  219.99
  5012.7  225.88 5016.07227.9159  5019.9  230.23  5051.4  230.21    5071  230.84
    5107  229.16  5164.2  232.17  5323.5  233.46  5350.5   234.2  5373.1  237.08
#Mann= 7 ,-1 , 0
  3967.7     .11       0  4235.1     .15       0  4467.4     .11       0
    4568     .15       0  4980.3     .09       0 5016.07     .15       0
  5051.4     .11       0
Bank Sta=4980.3,5016.07
XS Rating Curve= 0 ,0
Exp/Cntr=0.3,0.1

Type RM Length L Ch R = 1 ,22659   ,493,493,493
BEGIN DESCRIPTION:
LANDRUM CREEK 41.0
END DESCRIPTION:
XS GIS Cut Line= 3
      3750067.89     10122211.04      3749466.31     10122704.69
      3749117.84     10122761.07
#Sta/Elev= 30
  4221.8   248.8  4235.5  246.72  4360.9  239.42    4476  228.62  4541.9   225.8
  4591.4  226.95  4712.7  226.27  4797.4   227.9  4896.4  226.31  4953.8  228.45
 4977.19227.6883    4989  225.79  4991.7  221.05  4999.8  221.05  5006.1  223.16
 5014.51227.7728  5018.7  228.87  5079.5   227.6  5109.9   229.1  5129.5   227.9
    5147   228.7  5170.6  228.44  5196.2  225.67  5231.4  225.97  5241.6  226.66
  5251.7  228.94  5302.3  230.45  5319.6  232.97  5324.7   232.7    5353   240.1
#Mann= 6 ,-1 , 0
  4221.8     .11       0  4360.9     .17       0    4476     .15       0
 4977.19     .09       0 5014.51     .15       0    5147     .11       0
Bank Sta=4977.19,5014.51
XS Rating Curve= 0 ,0
Exp/Cntr=0.3,0.1

Type RM Length L Ch R = 1 ,22166   ,437,437,437
BEGIN DESCRIPTION:
LANDRUM CREEK 40.0
END DESCRIPTION:
XS GIS Cut Line= 3
      3750167.83     10122111.08      3749415.38     10122293.76
      3749067.83     10122711.09
#Sta/Elev= 30
  4225.7  256.34    4308  252.94  4410.9  243.79  4431.5  239.75  4441.8  239.04
  4452.1   239.8    4458  242.56  4493.2  239.82  4513.8  236.96  4593.6  231.22
  4708.6  224.11  4740.2  225.85  4904.8  224.77  4976.9  226.65  4987.2  223.88
  4992.1  219.03  5003.5  219.94    5010  224.04  5017.8  226.41  5102.4  226.35
  5110.2  224.44  5152.7  226.82  5180.5   226.6  5188.3  225.14  5223.5  227.86
  5295.1  227.34    5399   229.5  5472.1  232.23  5529.4  246.68  5543.1  245.51
#Mann= 5 ,-1 , 0
  4225.7     .11       0  4593.6     .15       0  4976.9     .09       0
  5017.8     .15       0    5399     .11       0
Bank Sta=4976.9,5017.8
XS Rating Curve= 0 ,0
Exp/Cntr=0.3,0.1

Type RM Length L Ch R = 1 ,21729   ,481,481,481
BEGIN DESCRIPTION:
LANDRUM CREEK 39.0
END DESCRIPTION:
XS GIS Cut Line= 3
      3749867.81     10122111.07      3749232.82     10122008.01
      3748717.88     10122311.06
#Sta/Elev= 30
  4453.6  244.25  4463.7  243.39  4481.8  239.28  4486.9  240.95  4494.1  238.71
  4543.4  230.17  4548.5  230.71  4575.1  228.39  4610.1  228.25  4657.2  225.83
  4794.9  224.46  4970.2  224.65  4984.8  220.34  4986.3  217.15  4994.6  217.15
  5000.6  221.23  5010.8  224.42  5041.1  226.68  5071.5  225.48  5102.7  225.39
  5116.4  226.29  5132.1  225.18  5156.2  225.38  5249.3  225.87  5304.7  227.84
  5446.5  231.07    5474  232.96  5563.6  232.99  5585.1  234.36  5694.4  237.31
#Mann= 6 ,-1 , 0
  4453.6     .11       0  4657.2     .15       0  4970.2     .09       0
  5010.8     .15       0  5156.2     .11       0  5304.7     .17       0
Bank Sta=4970.2,5010.8
XS Rating Curve= 0 ,0
Exp/Cntr=0.3,0.1

Type RM Length L Ch R = 1 ,21248   ,579,579,579
BEGIN DESCRIPTION:
LANDRUM CREEK 38.0
END DESCRIPTION:
XS GIS Cut Line= 3
      3749967.85     10121961.07      3749245.84     10121588.74
      3748628.64     10122104.37
#Sta/Elev= 30
  4351.5  244.94  4359.8  243.94  4365.4  245.74  4404.1  245.01  4409.7  241.54
  4426.2  240.99  4431.9  238.84  4514.9   231.6  4692.2  226.21  4819.6  224.64
  4880.3  223.94  4902.5  225.42  4946.8  224.81  4974.6  226.01  4981.6  225.06
  4991.2  220.47  4992.5  217.24    5001  217.24  5004.1  220.41  5013.3  224.75
  5079.8  225.63  5171.5   223.7  5359.7  224.03  5434.4  223.76  5541.7  225.59
  5590.2  227.92    5640     228    5745  231.18  5760.6  230.45  5968.1  237.42
#Mann= 8 ,-1 , 0
  4351.5     .11       0  4819.6     .15       0  4981.6     .09       0
  5013.3     .15       0  5359.7     .11       0  5541.7     .17       0
  5590.2     .11       0    5745     .17       0
Bank Sta=4981.6,5013.3
XS Rating Curve= 0 ,0
Exp/Cntr=0.3,0.1

Type RM Length L Ch R = 1 ,20669   ,497,497,497
BEGIN DESCRIPTION:
LANDRUM CREEK 37.0
END DESCRIPTION:
XS GIS Cut Line= 3
      3750010.95     10120179.11      3749131.67      10121290.3
      3748517.85     10121911.07
#Sta/Elev= 30
    3583  245.39  3643.6  240.52  3693.3  238.81  3800.7  230.77  3900.1  227.37
  4241.5  223.42  4369.7  224.08    4413  222.86  4448.2   224.2  4776.9  222.91
  4903.4  222.21  4967.5  224.12  4988.3  223.98 4988.84 223.278  4993.9  216.85
  5004.1  216.85  5017.4  218.64  5031.5  223.26    5081  222.64  5137.6  224.32
  5158.8  222.15  5172.9  222.89  5264.9  222.96  5314.4  225.02    5378  225.11
  5554.8  228.85  5667.9  232.86  5795.2  236.01  5852.8  239.69    5873  240.11
#Mann= 5 ,-1 , 0
    3583     .11       0  4776.9     .15       0 4988.84     .09       0
  5031.5     .11       0  5852.8     .17       0
Bank Sta=4988.84,5031.5
XS Rating Curve= 0 ,0
Exp/Cntr=0.3,0.1

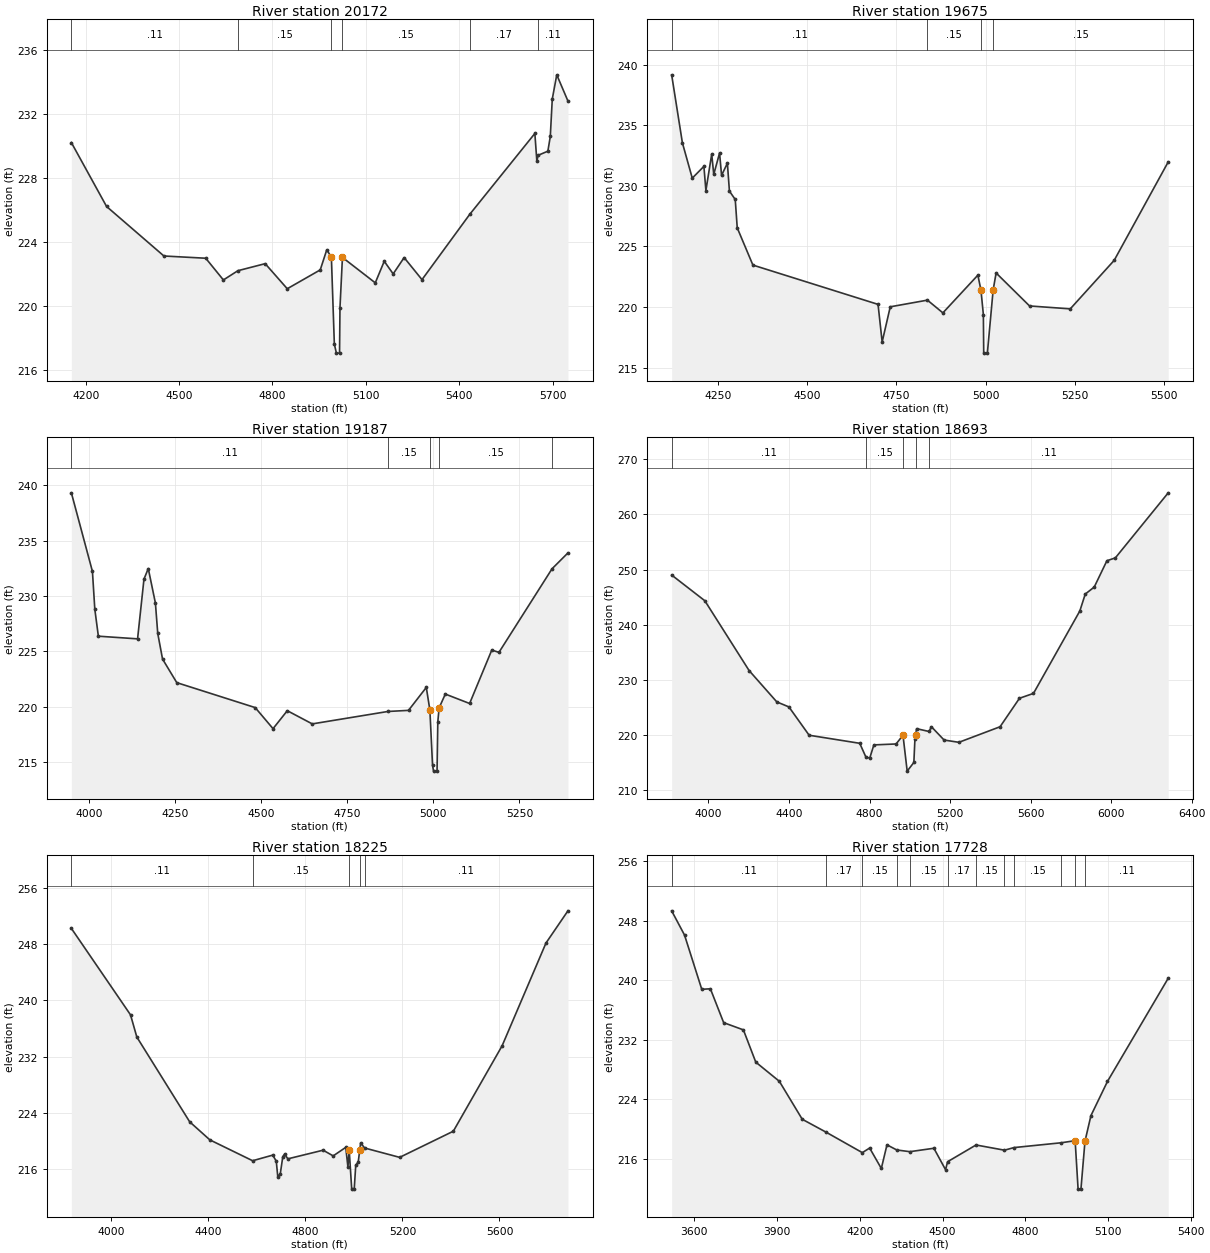
Type RM Length L Ch R = 1 ,20172   ,497,497,497
BEGIN DESCRIPTION:
LANDRUM CREEK 36.0
END DESCRIPTION:
XS GIS Cut Line= 3
      3749667.87     10120261.05      3749048.72     10120837.28
      3748467.85     10121311.07
#Sta/Elev= 30
  4154.2  230.21  4267.3  226.21  4451.5  223.11  4585.9  222.97  4642.6  221.61
  4689.3  222.19  4776.9  222.63  4847.8  221.06  4953.8  222.24  4974.8   223.5
 4989.59223.0291  4999.1   217.6  5005.6  217.03  5015.8  217.03  5017.2  219.88
  5025.1  223.02  5130.6  221.43  5159.4  222.78  5188.1  221.99  5223.3  223.01
  5280.7  221.63  5434.2  225.72  5643.3  230.78  5649.8  229.03  5653.4  229.41
  5685.1  229.67  5692.9  230.59  5699.3  232.94  5713.7  234.45  5749.6  232.81
#Mann= 6 ,-1 , 0
  4154.2     .11       0  4689.3     .15       0 4989.59     .09       0
  5025.1     .15       0  5434.2     .17       0  5653.4     .11       0
Bank Sta=4989.59,5025.1
XS Rating Curve= 0 ,0
Exp/Cntr=0.3,0.1

Type RM Length L Ch R = 1 ,19675   ,488,488,488
BEGIN DESCRIPTION:
LANDRUM CREEK 35.0
END DESCRIPTION:
XS GIS Cut Line= 3
      3749517.87     10120111.06      3748742.09     10120525.62
      3748317.87     10120811.06
#Sta/Elev= 30
  4120.4  239.15  4150.5  233.54  4178.1  230.63  4210.7   231.6  4216.3  229.61
  4232.6  232.61  4238.3  230.94  4254.6   232.7  4260.2  230.86  4276.5  231.86
  4282.2  229.56  4298.5  228.87  4304.1  226.53    4348  223.46  4698.5  220.22
    4710  217.12  4732.7  220.02  4836.8  220.57  4880.1  219.52  4978.1  222.63
 4986.69 221.409  4993.5  219.38  4994.5   216.2  5004.7   216.2  5020.9  221.41
  5029.2  222.81  5122.9  220.09  5236.9  219.85  5359.9  223.85  5511.3  231.97
#Mann= 4 ,-1 , 0
  4120.4     .11       0  4836.8     .15       0 4986.69     .09       0
  5020.9     .15       0
Bank Sta=4986.69,5020.9
XS Rating Curve= 0 ,0
Exp/Cntr=0.3,0.1

Type RM Length L Ch R = 1 ,19187   ,494,494,494
BEGIN DESCRIPTION:
LANDRUM CREEK 34.0
END DESCRIPTION:
XS GIS Cut Line= 3
      3749493.62     10120050.62      3748477.98     10120323.29
      3748167.85     10120561.08
#Sta/Elev= 30
  3948.4  239.31  4009.6  232.22  4016.5  228.81  4026.8  226.38  4140.7  226.14
  4159.3  231.53  4171.8  232.48  4192.5  229.37  4199.3  226.63  4213.2  224.32
  4254.6  222.19  4482.4  219.94  4534.2  218.04  4575.6  219.66  4648.1  218.47
  4867.8  219.59  4927.7  219.69  4979.4  221.76  4989.8  219.71  4997.5  214.74
  5000.4  214.21  5010.6  214.21  5012.8  218.65 5016.59219.9133  5034.6  221.16
  5105.2  220.31  5169.6  225.13  5190.4  224.92  5344.6  232.46  5390.8  233.89
#Mann= 5 ,-1 , 0
  3948.4     .11       0  4867.8     .15       0  4989.8     .09       0
 5016.59     .15       0  5344.6     .11       0
Bank Sta=4989.8,5016.59
XS Rating Curve= 0 ,0
Exp/Cntr=0.3,0.1

Type RM Length L Ch R = 1 ,18693   ,468,468,468
BEGIN DESCRIPTION:
LANDRUM CREEK 33.0
END DESCRIPTION:
XS GIS Cut Line= 3
      3749767.83     10120011.07      3748590.18     10119902.91
      3747367.85     10119511.07
#Sta/Elev= 30
  3817.4  249.01  3982.2  244.35    4202  231.71  4339.6  226.03  4399.8  225.12
  4500.2  219.99  4751.5  218.53  4782.9  215.97  4801.5  215.88  4821.6  218.24
    4932  218.41  4966.3  219.99  4987.1  213.49  5020.3  215.06  5025.6  219.31
 5028.63219.9845    5034  221.18  5095.6  220.67  5107.5  221.53  5170.5  219.12
    5244  218.71  5448.5  221.53  5544.9  226.69  5614.4  227.57  5844.6   242.5
  5871.5  245.56  5916.1  246.83  5979.1   251.6  6021.1  252.12  6283.6   263.9
#Mann= 5 ,-1 , 0
  3817.4     .11       0  4782.9     .15       0  4966.3     .09       0
 5028.63     .15       0  5095.6     .11       0
Bank Sta=4966.3,5028.63
XS Rating Curve= 0 ,0
Exp/Cntr=0.3,0.1

Type RM Length L Ch R = 1 ,18225   ,497,497,497
BEGIN DESCRIPTION:
LANDRUM CREEK 32.0
END DESCRIPTION:
XS GIS Cut Line= 3
      3749667.83     10119911.07      3748545.51     10119600.51
      3747667.85     10119511.07
#Sta/Elev= 30
  3835.5  250.25  4079.3  237.95  4105.3  234.79  4323.1  222.73  4406.2  220.16
  4582.6  217.19  4665.5  217.99  4680.1  217.12  4686.3  214.89  4696.7  215.36
    4707  217.78  4714.5  218.13  4727.8  217.46  4873.1  218.69  4914.6  217.88
  4966.4  219.09  4975.4  216.29  4980.6  218.71    4991  213.15  5001.3  213.15
  5007.7  216.59  5017.7  216.97 5024.34218.7779  5027.8  219.72  5044.4     219
  5188.6  217.67  5409.8  221.39  5610.8  233.54  5791.7  248.17  5882.2  252.75
#Mann= 5 ,-1 , 0
  3835.5     .11       0  4582.6     .15       0  4980.6     .09       0
 5024.34     .15       0  5044.4     .11       0
Bank Sta=4980.6,5024.34
XS Rating Curve= 0 ,0
Exp/Cntr=0.3,0.1

Type RM Length L Ch R = 1 ,17728   ,489,489,489
BEGIN DESCRIPTION:
LANDRUM CREEK 31.0
END DESCRIPTION:
XS GIS Cut Line= 3
      3749635.94      10119741.6      3748235.09     10119259.16
      3747917.89     10119261.07
#Sta/Elev= 30
  3518.4  249.35    3565  246.09  3627.5  238.79  3658.7  238.86  3706.8   234.3
  3778.3  233.33  3823.1  228.99  3908.5  226.41  3991.5   221.3  4078.5  219.55
  4209.1  216.81  4235.6  217.43  4277.9  214.68  4298.4  217.86  4333.8  217.17
  4381.2  216.94  4468.3   217.4  4510.6  214.51    4518  215.59    4621  217.84
    4724  217.14  4758.5  217.49    4930  218.14    4980  218.42  4990.7   211.9
    5001   211.9 5015.62218.3416  5037.2  221.79  5097.2   226.4  5317.2  240.28
#Mann= 12 ,-1 , 0
  3518.4     .11       0  4078.5     .17       0  4209.1     .15       0
  4333.8     .11       0  4381.2     .15       0    4518     .17       0
    4621     .15       0    4724     .17       0  4758.5     .15       0
    4930     .11       0    4980     .06       0 5015.62     .11       0
Bank Sta=4980,5015.62
XS Rating Curve= 0 ,0
Exp/Cntr=0.3,0.1

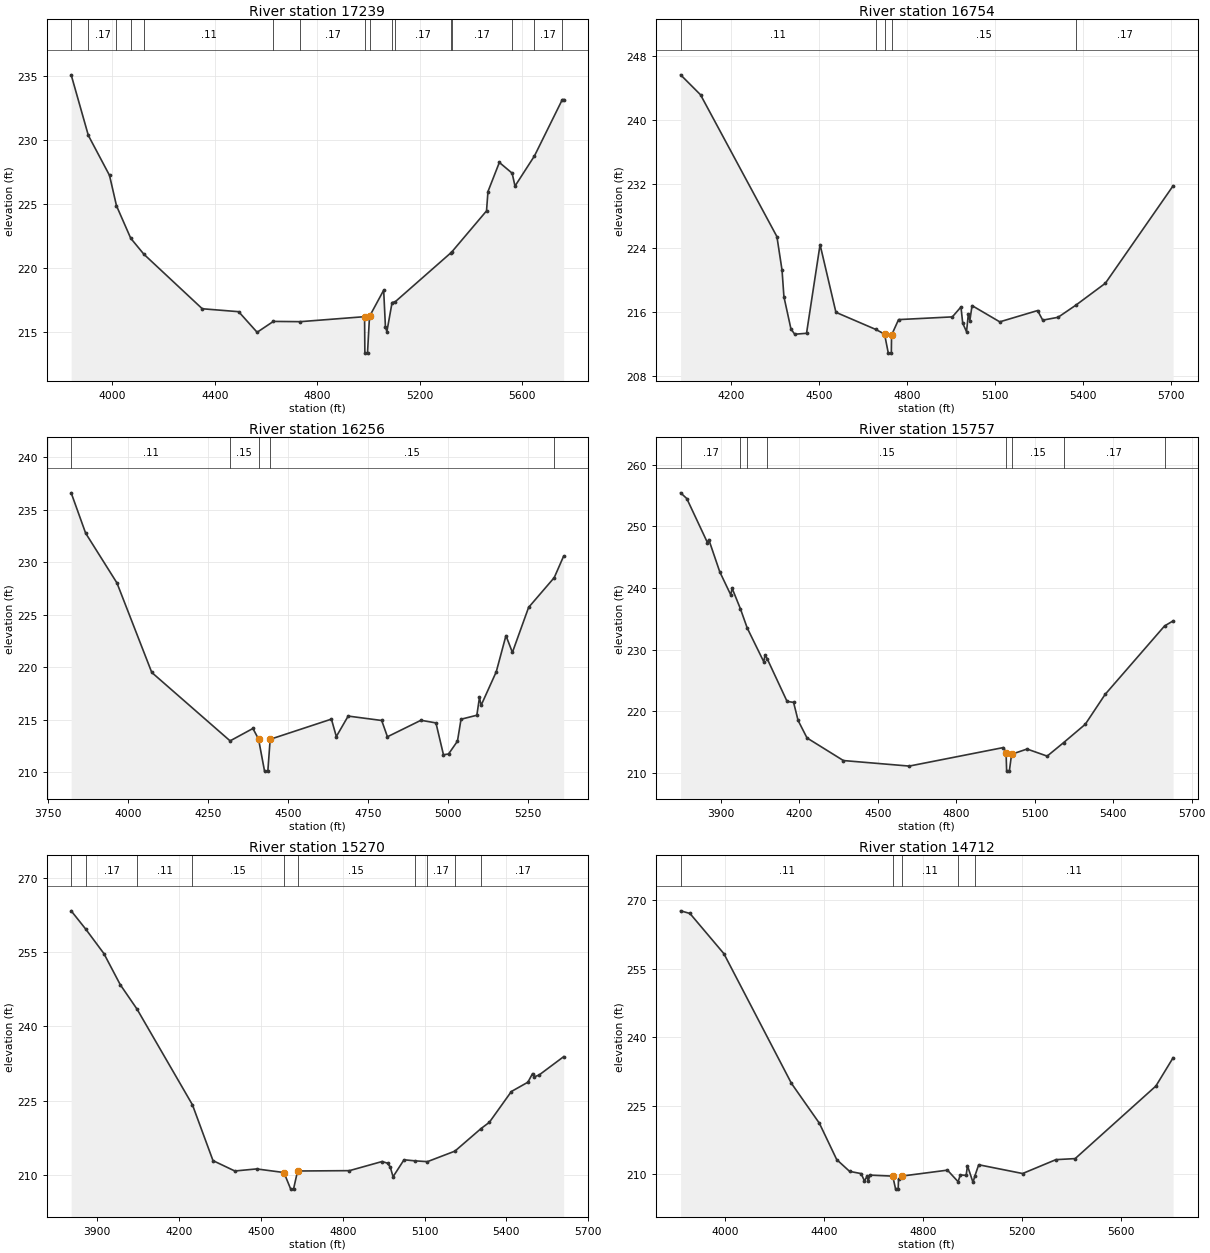
Type RM Length L Ch R = 1 ,17239   ,485,485,485
BEGIN DESCRIPTION:
LANDRUM CREEK 30.0
END DESCRIPTION:
XS GIS Cut Line= 3
      3749417.84     10119611.06      3748511.14     10118886.89
      3747831.59     10118540.82
#Sta/Elev= 30
  3839.6  235.09  3906.7  230.35  3989.3  227.23  4016.6  224.85  4072.2  222.31
  4123.7  221.06  4351.5   216.8  4493.6  216.57  4565.7  214.96  4629.1  215.81
  4734.3  215.79  4985.2  216.18  4986.4  213.33  4996.7  213.33  5004.5216.1997
  5059.8  218.25  5066.7  215.38  5072.3  215.01  5092.6  217.28  5105.6  217.36
  5321.5  221.16    5327  221.27  5461.4  224.45    5467  225.96  5511.5  228.24
  5561.4   227.4  5572.6  226.39  5648.6  228.75  5757.2  233.15  5762.6  233.16
#Mann= 16 ,-1 , 0
  3839.6     .11       0  3906.7     .17       0  4016.6     .11       0
  4072.2     .17       0  4123.7     .11       0  4629.1     .15       0
  4734.3     .17       0  4985.2     .09       0  5004.5     .17       0
  5092.6     .15       0  5105.6     .17       0  5321.5     .11       0
    5327     .17       0  5561.4     .11       0  5648.6     .17       0
  5757.2     .11       0
Bank Sta=4985.2,5004.5
XS Rating Curve= 0 ,0
Exp/Cntr=0.3,0.1

Type RM Length L Ch R = 1 ,16754   ,498,498,498
BEGIN DESCRIPTION:
LANDRUM CREEK 29.0
END DESCRIPTION:
XS GIS Cut Line= 3
      3749667.85     10118911.07      3748768.71     10118539.74
      3748093.59     10118325.82
#Sta/Elev= 30
  4027.2  245.67  4095.1  243.18  4355.9  225.45  4373.4  221.25  4379.8  217.94
  4403.8  213.91  4416.7  213.25    4457  213.37  4503.2  224.45  4557.3  215.99
  4693.3  213.85  4723.2  213.27  4736.1  210.89  4746.4  210.89  4747.2  213.14
  4771.1  215.08  4954.7  215.42  4984.1  216.66  4990.1  214.62  5003.1  213.57
  5009.1  215.73  5014.4  214.95  5021.9  216.83  5116.5   214.8  5245.6  216.21
  5263.2  215.01  5315.6  215.37  5376.5  216.89  5476.9  219.62  5708.2   231.8
#Mann= 5 ,-1 , 0
  4027.2     .11       0  4693.3     .15       0  4723.2     .09       0
  4747.2     .15       0  5376.5     .17       0
#Block Obstruct= 2 , 0
         4501.71  224.41
Bank Sta=4723.2,4747.2
XS Rating Curve= 0 ,0
Exp/Cntr=0.3,0.1

Type RM Length L Ch R = 1 ,16256   ,499,499,499
BEGIN DESCRIPTION:
LANDRUM CREEK 28.0
END DESCRIPTION:
XS GIS Cut Line= 3
      3749639.39     10118620.06      3748557.87     10118151.89
      3748199.41     10118095.92
#Sta/Elev= 30
  3821.5  236.59  3866.8  232.75  3964.8  228.01  4073.8  219.49  4318.9  212.98
  4390.3  214.16 4407.83  213.16  4426.7   210.1    4437   210.1  4444.3  213.13
    4636  215.05  4651.3  213.39  4688.4  215.34  4793.3  214.92  4811.3  213.37
  4916.1  214.94  4963.1  214.69  4986.6  211.66  5002.5  211.73  5030.4  212.95
  5041.6  215.04  5091.1  215.42  5099.3  217.11  5104.4  216.36  5151.8  219.55
  5182.2     223  5202.4   221.4    5253  225.68  5333.3  228.52  5362.8  230.57
#Mann= 5 ,-1 , 0
  3821.5     .11       0  4318.9     .15       0 4407.83     .09       0
  4444.3     .15       0  5333.3     .17       0
Bank Sta=4407.83,4444.3
XS Rating Curve= 0 ,0
Exp/Cntr=0.3,0.1

Type RM Length L Ch R = 1 ,15757   ,487,487,487
BEGIN DESCRIPTION:
LANDRUM CREEK 27.0
END DESCRIPTION:
XS GIS Cut Line= 3
      3750067.89     10117561.06      3748848.48     10117853.13
      3748267.82     10117611.06
#Sta/Elev= 30
  3746.1  255.46  3769.7  254.53  3848.6  247.38  3853.8  247.87  3895.8  242.62
  3937.8  238.88    3943  239.95  3974.7  236.62  4000.8  233.49  4063.9  228.02
  4069.1  229.14  4077.1   228.5  4153.1  221.57    4178  221.41  4195.2  218.48
  4229.4  215.63  4368.4  211.96  4620.2  211.06  4980.1  214.07  4990.4  213.25
  4992.6  210.24  5002.9  210.24  5011.5  212.98  5070.7  213.83  5147.6  212.68
  5210.1  214.86  5293.2  217.85    5369   222.7  5596.4  233.83  5629.1  234.65
#Mann= 8 ,-1 , 0
  3746.1     .17       0  3974.7     .11       0  4000.8     .17       0
  4077.1     .15       0  4990.4     .09       0  5011.5     .15       0
  5210.1     .17       0  5596.4     .15       0
Bank Sta=4990.4,5011.5
XS Rating Curve= 0 ,0
Exp/Cntr=0.3,0.1

Type RM Length L Ch R = 1 ,15270   ,558,558,558
BEGIN DESCRIPTION:
LANDRUM CREEK 26.0
END DESCRIPTION:
XS GIS Cut Line= 3
      3750167.81     10117511.07      3748972.45     10117492.83
      3748367.85     10117411.07
#Sta/Elev= 30
  3804.5   263.4    3858  259.69  3924.5  254.75  3984.5  248.45  4045.9  243.51
  4249.1  224.14  4324.5  212.84  4404.5  210.74  4484.5  211.16  4584.6  210.43
  4609.4  207.07  4619.7  207.07  4634.6  210.74  4824.6  210.81  4944.6  212.66
  4964.6  212.31  4974.6  211.51  4984.6  209.57  5024.8  213.01  5063.9   212.8
  5110.5  212.63  5211.4  214.76  5307.4  219.34  5337.6  220.59  5418.4  226.83
  5478.9  228.71  5496.1  230.46  5501.2  229.79  5519.3  230.14  5610.1  233.88
#Mann= 10 ,-1 , 0
  3804.5     .11       0    3858     .17       0  4045.9     .11       0
  4249.1     .15       0  4584.6     .09       0  4634.6     .15       0
  5063.9     .11       0  5110.5     .17       0  5211.4     .15       0
  5307.4     .17       0
Bank Sta=4584.6,4634.6
XS Rating Curve= 0 ,0
Exp/Cntr=0.3,0.1

Type RM Length L Ch R = 1 ,14712   ,727,727,727
BEGIN DESCRIPTION:
LANDRUM CREEK 25.0
END DESCRIPTION:
XS GIS Cut Line= 3
      3750267.83     10117461.06      3749184.56     10116984.66
      3748649.85      10116380.5
#Sta/Elev= 30
  3819.6  267.73  3857.3  267.15  3994.4  258.35  4267.5  229.92  4380.3  221.19
  4450.4  213.22  4502.5  210.64  4549.2  210.15  4562.4  208.54  4572.5  209.54
    4578  208.53  4584.3  209.82  4676.8   209.6  4688.4  206.75  4698.7  206.75
  4700.2  208.97  4715.4  209.62  4897.9  210.91  4940.9  208.38    4950  209.87
  4973.4  209.75  4978.8  211.88  5001.2  208.22  5008.5  209.61  5024.2  212.09
  5201.6  210.17  5336.2  213.21    5414  213.44  5740.2  229.34  5809.8  235.54
#Mann= 5 ,-1 , 0
  3819.6     .11       0  4676.8     .09       0  4715.4     .11       0
  4940.9     .15       0  5008.5     .11       0
Bank Sta=4676.8,4715.4
XS Rating Curve= 0 ,0
Exp/Cntr=0.3,0.1