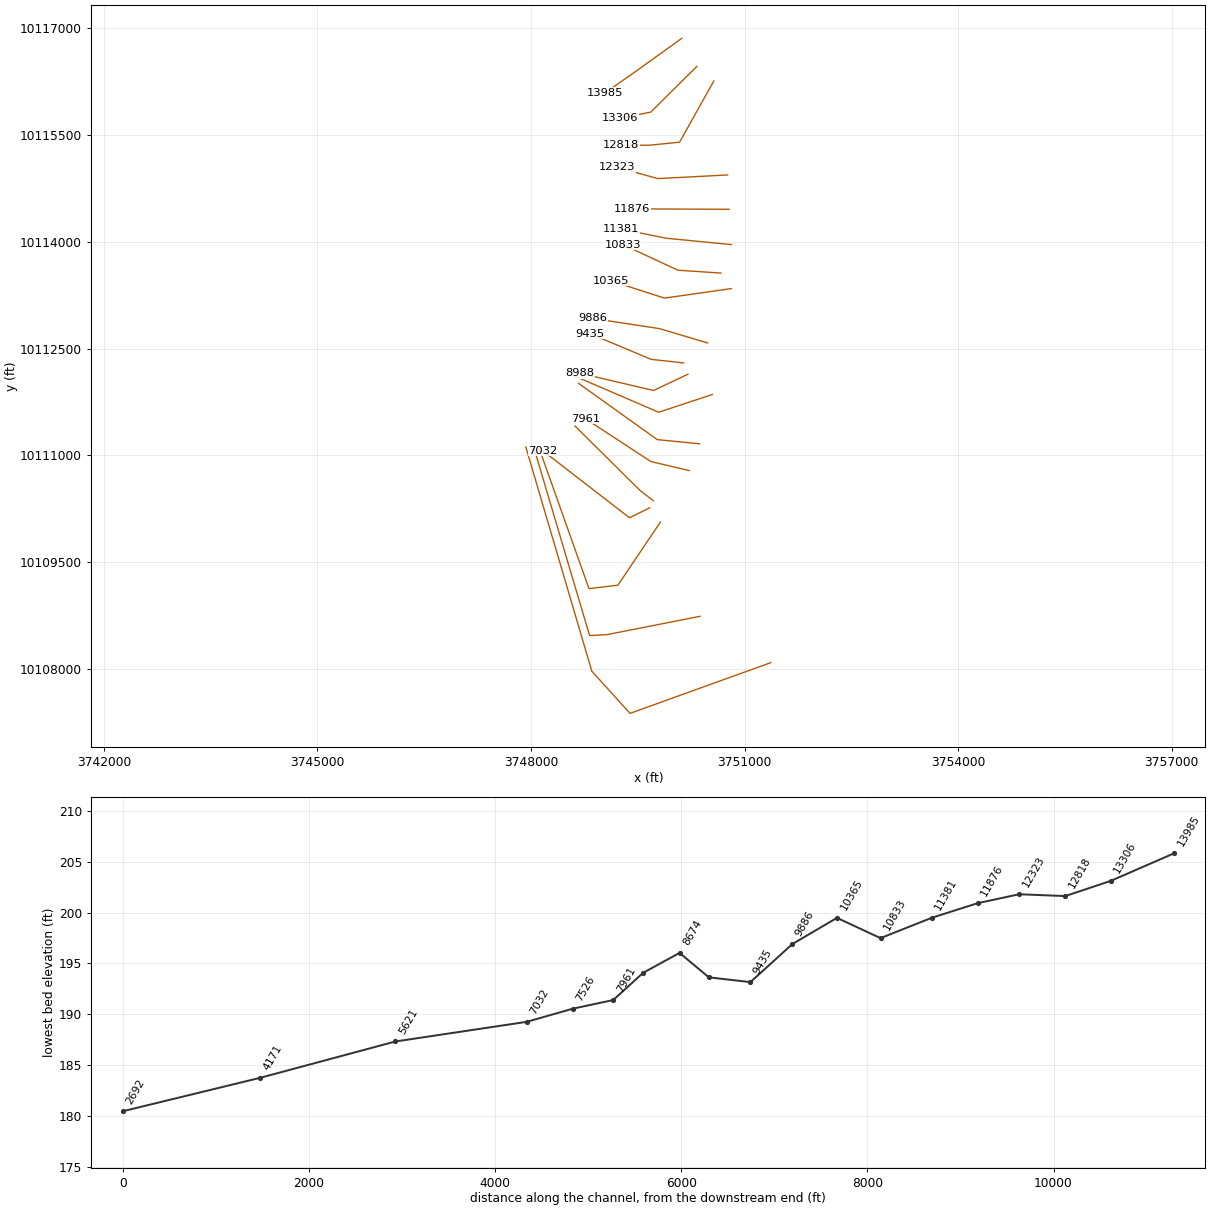
HEC-RAS study LANDRUM CREEK.prj: LANDRUM CREEK Base Level Engineering

--- LANDRUM CREEK.g01 (geometry) --- (continued)

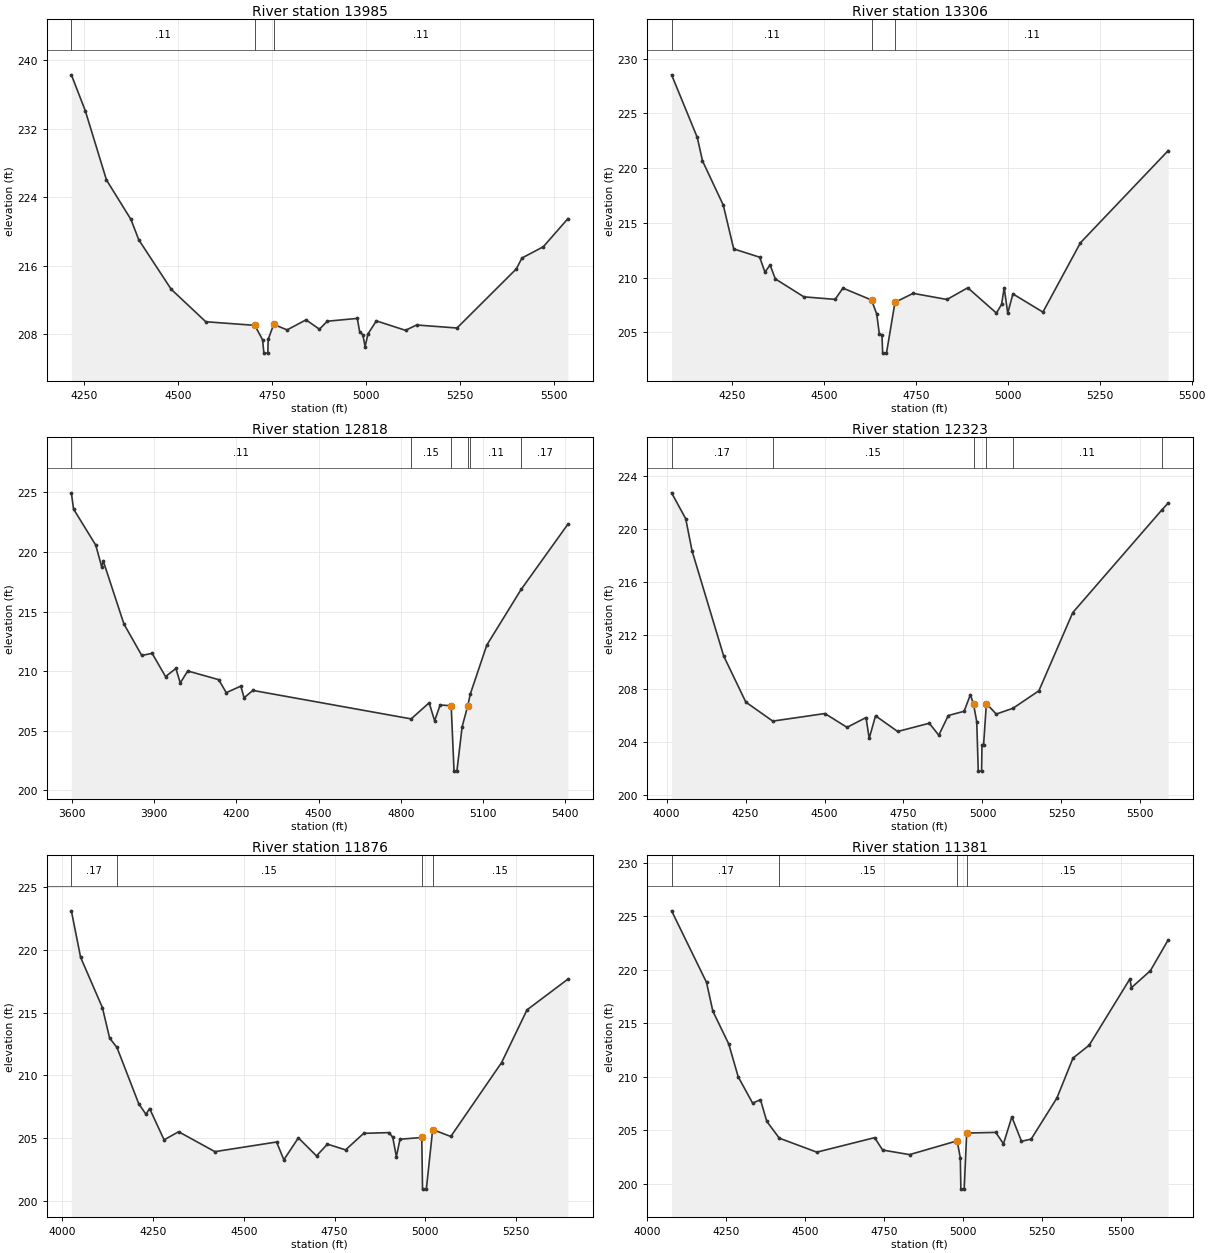
Type RM Length L Ch R = 1 ,13985   ,679,679,679
BEGIN DESCRIPTION:
LANDRUM CREEK 23.0
END DESCRIPTION:
XS GIS Cut Line= 3
      3750117.84     10116861.07      3749483.18      10116404.8
      3749042.72     10116096.13
#Sta/Elev= 30
  4216.6  238.26  4253.4   234.1  4309.9     226  4374.9   221.4  4395.8  219.02
  4481.8  213.26  4573.8  209.47    4704  209.05  4724.8  207.36  4728.2  205.81
  4738.6  205.81  4739.6  207.41  4754.3  209.16  4789.9  208.52  4840.2  209.69
  4875.8   208.6  4896.7  209.53  4976.5  209.86  4982.6  208.32  4991.2  207.94
  4997.2  206.57  5004.8  208.05    5027  209.57  5104.6  208.47  5134.2  209.09
  5241.4  208.74  5399.2  215.64    5414   216.9  5470.7  218.21  5536.1  221.49
#Mann= 3 , 0 , 0
  4216.6     .11       0    4704     .06       0  4754.3     .11       0
Bank Sta=4704,4754.3
XS Rating Curve= 0 ,0
Exp/Cntr=0.3,0.1

Type RM Length L Ch R = 1 ,13306   ,488,488,488
BEGIN DESCRIPTION:
LANDRUM CREEK 22.0
END DESCRIPTION:
XS GIS Cut Line= 3
      3750330.38     10116467.28      3749681.57     10115823.66
      3749254.04     10115738.14
#Sta/Elev= 30
  4086.1  228.53  4155.9  222.81  4170.1  220.67  4226.6  216.63  4254.9  212.63
  4325.6  211.87  4339.8  210.51  4353.9  211.16  4368.1  209.89  4445.8  208.25
  4530.7  208.02  4551.9  209.05  4629.7  207.96  4643.8  206.68  4650.9  204.85
    4658  204.78  4659.9  203.11  4670.3  203.11  4693.4  207.75  4742.8  208.57
  4834.8  208.01  4891.3  209.08  4969.1  206.77  4983.2  207.56  4990.3  209.08
    5000  206.76    5014  208.52  5095.6  206.86  5197.6  213.19    5436   221.6
#Mann= 3 , 0 , 0
  4086.1     .11       0  4629.7     .06       0  4693.4     .11       0
Bank Sta=4629.7,4693.4
XS Rating Curve= 0 ,0
Exp/Cntr=0.3,0.1

Type RM Length L Ch R = 1 ,12818   ,495,495,495
BEGIN DESCRIPTION:
LANDRUM CREEK 21.0
END DESCRIPTION:
XS GIS Cut Line= 4
      3750567.85     10116261.06      3750087.34     10115401.32
      3749671.69     10115359.11       3749261.9     10115356.19
#Sta/Elev= 30
  3597.3  224.96  3605.3   223.6  3686.4  220.57  3708.1  218.75  3713.8  219.24
  3789.2  213.96  3854.3  211.32    3892   211.5  3941.1  209.55  3978.8  210.23
  3994.8  209.02  4022.2  210.02  4135.2  209.29  4162.7   208.2  4215.9  208.75
  4227.8  207.77  4259.7  208.39  4837.6     206  4903.3  207.35  4923.4  205.84
  4943.5  207.17  4983.8   207.1  4994.2  201.62  5004.6  201.62  5023.8  205.35
  5043.8  207.06  5053.6  208.09  5113.8  212.19  5239.2  216.86  5409.8  222.33
#Mann= 6 ,-1 , 0
  3597.3     .11       0  4837.6     .15       0  4983.8     .09       0
  5043.8     .15       0  5053.6     .11       0  5239.2     .17       0
Bank Sta=4983.8,5043.8
XS Rating Curve= 0 ,0
Exp/Cntr=0.3,0.1

Type RM Length L Ch R = 1 ,12323   ,447,447,447
BEGIN DESCRIPTION:
LANDRUM CREEK 20.0
END DESCRIPTION:
XS GIS Cut Line= 3
      3750762.47     10114940.34      3749779.79      10114889.4
      3749213.89     10115047.97
#Sta/Elev= 30
    4016  222.72  4060.7  220.77  4080.7  218.36  4180.8  210.46  4250.9  206.99
  4336.3  205.56  4501.3  206.13  4571.4  205.09  4631.4  205.83  4641.5  204.26
  4661.5  205.96  4731.6  204.78  4831.7   205.4  4861.8   204.5  4891.8  205.98
  4941.9   206.3  4961.9  207.55  4971.9  206.81  4981.9  205.52  4986.7   201.8
  4997.2   201.8  4998.5  203.79  5003.6  203.79  5012.4  206.88  5043.6  206.09
  5097.1  206.53  5178.6  207.84  5285.9  213.72  5566.9  221.41  5587.7  221.95
#Mann= 6 ,-1 , 0
    4016     .17       0  4336.3     .15       0  4971.9     .09       0
  5012.4     .15       0  5097.1     .11       0  5566.9     .17       0
Bank Sta=4971.9,5012.4
XS Rating Curve= 0 ,0
Exp/Cntr=0.3,0.1

Type RM Length L Ch R = 1 ,11876   ,495,495,495
BEGIN DESCRIPTION:
LANDRUM CREEK 19.0
END DESCRIPTION:
XS GIS Cut Line= 3
      3750783.38      10114457.7      3749808.29     10114462.09
      3749415.29     10114464.64
#Sta/Elev= 30
  4024.9  223.12  4050.4  219.41  4110.4   215.4  4130.4  212.96  4150.4  212.23
  4210.4  207.74  4230.4  206.89  4240.4  207.35  4280.4  204.85  4320.4   205.5
  4420.4  203.91  4590.4  204.68  4610.4  203.26  4650.4  205.01  4700.4  203.57
  4730.4  204.51  4780.4  204.05  4830.4  205.37  4900.4  205.43  4910.4  205.05
  4920.4  203.51  4930.4   204.9  4990.4  205.04  4992.5  200.92    5003  200.92
  5020.4  205.67  5070.4  205.12  5210.4  211.02  5280.4  215.22    5393  217.67
#Mann= 4 ,-1 , 0
  4024.9     .17       0  4150.4     .15       0  4990.4     .09       0
  5020.4     .15       0
Bank Sta=4990.4,5020.4
XS Rating Curve= 0 ,0
Exp/Cntr=0.3,0.1

Type RM Length L Ch R = 1 ,11381   ,548,548,548
BEGIN DESCRIPTION:
LANDRUM CREEK 18.0
END DESCRIPTION:
XS GIS Cut Line= 3
      3750817.88     10113961.07      3749898.96     10114050.88
       3749262.7     10114179.88
#Sta/Elev= 30
  4076.7  225.53  4187.3  218.83  4207.3  216.14  4257.6  213.07  4287.7  209.99
  4333.3  207.53  4358.1  207.85  4378.2  205.82  4417.8  204.25  4536.6  202.94
  4719.8   204.3  4744.9  203.14  4830.3  202.71    4981     204  4991.1   202.4
  4992.8  199.48  5003.3  199.48  5011.3  204.73  5103.2  204.79  5127.7  203.72
  5154.2  206.24  5184.8  203.96  5215.4  204.16    5297  208.01    5348  211.75
  5399.1  212.95    5528  219.15  5533.1  218.34  5592.9  219.92  5649.2   222.8
#Mann= 4 ,-1 , 0
  4076.7     .17       0  4417.8     .15       0    4981     .09       0
  5011.3     .15       0
Bank Sta=4981,5011.3
XS Rating Curve= 0 ,0
Exp/Cntr=0.3,0.1

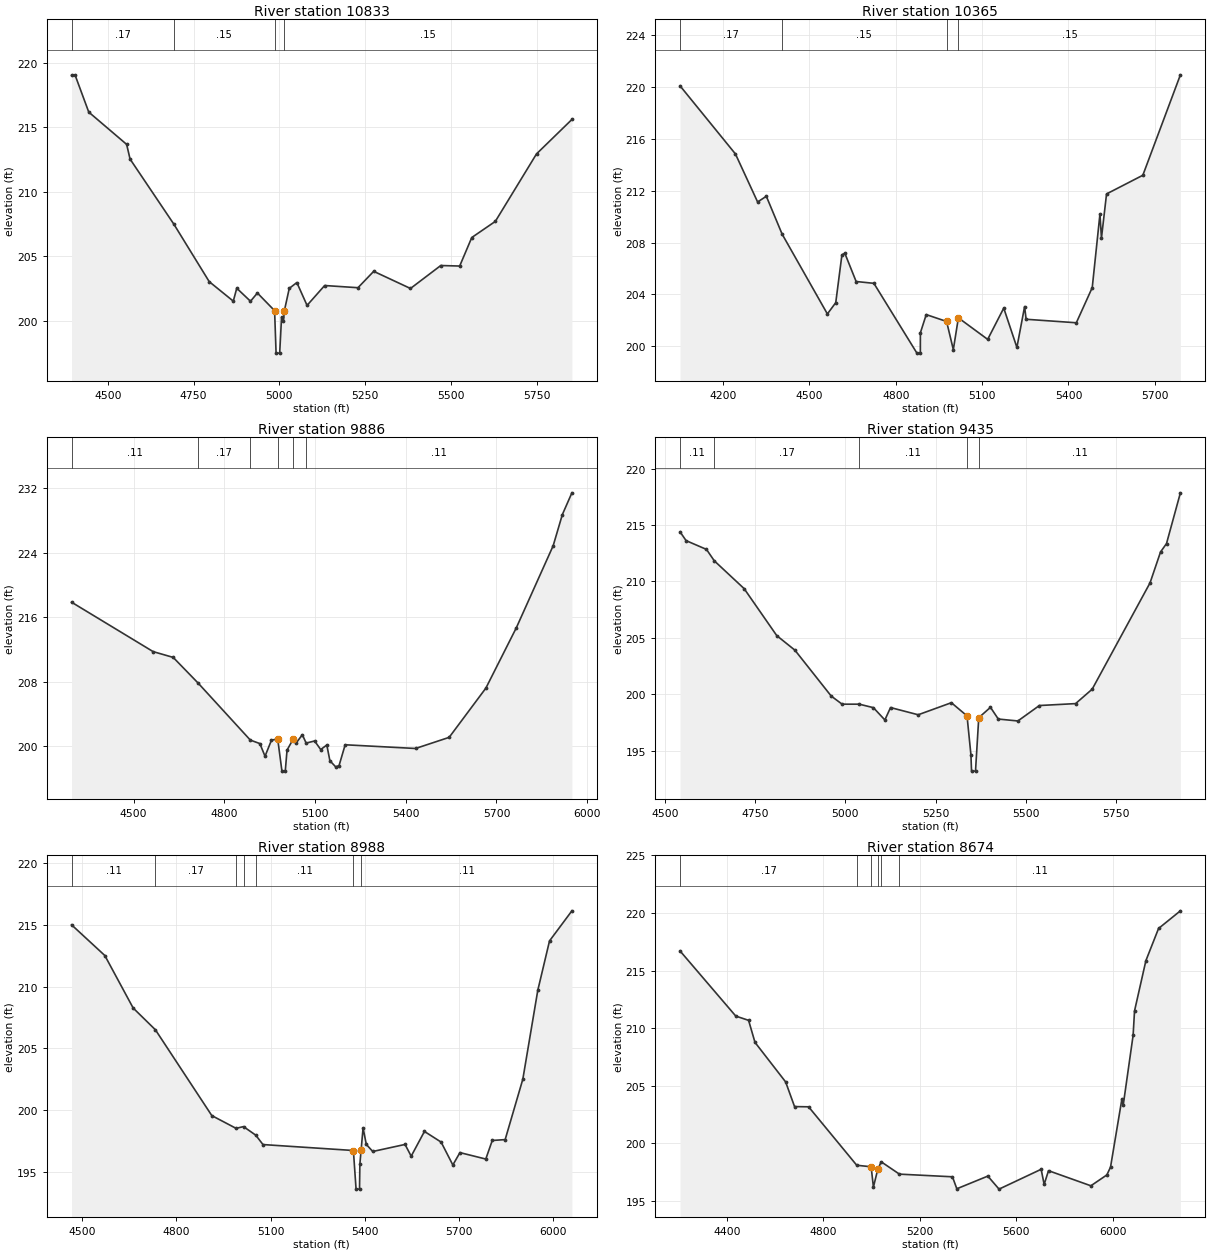
Type RM Length L Ch R = 1 ,10833   ,468,468,468
BEGIN DESCRIPTION:
LANDRUM CREEK 17.0
END DESCRIPTION:
XS GIS Cut Line= 3
      3750667.85     10113561.07      3750063.89     10113601.23
      3749291.59     10113960.56
#Sta/Elev= 30
  4394.7  219.01  4404.7  219.06  4444.8  216.17  4555.1  213.67  4565.1  212.53
    4693  207.47  4795.6  203.03  4865.7  201.52  4875.8  202.52  4915.8  201.51
  4935.9  202.15    4986  200.78  4990.3  197.49  5000.8  197.49  5006.3  200.29
  5011.8     200 5014.47200.7784  5028.7  202.51  5050.8  202.96  5080.5  201.19
  5131.8  202.73  5228.8  202.56  5274.6  203.83  5381.7   202.5  5469.9  204.28
    5525  204.24  5560.2  206.45  5628.8   207.7  5748.7  212.93  5851.8   215.6
#Mann= 4 ,-1 , 0
  4394.7     .17       0    4693     .15       0    4986     .09       0
 5014.47     .15       0
Bank Sta=4986,5014.47
XS Rating Curve= 0 ,0
Exp/Cntr=0.3,0.1

Type RM Length L Ch R = 1 ,10365   ,479,479,479
BEGIN DESCRIPTION:
LANDRUM CREEK 16.0
END DESCRIPTION:
XS GIS Cut Line= 3
      3750814.61     10113343.12      3749874.65     10113208.87
      3749123.64     10113450.74
#Sta/Elev= 30
  4050.5  220.08    4243  214.83    4320  211.13  4350.3  211.57  4405.2  208.65
  4562.4   202.5  4591.5  203.37  4612.9  207.05    4623  207.18  4662.3     205
    4724  204.86  4873.5  199.48  4885.4  199.48  4885.6  201.05  4905.9  202.45
  4976.6  201.92    5000  199.75  5017.6   202.2  5119.4  200.54  5175.2  202.95
  5220.9  199.92  5247.7  203.07  5252.9  202.09  5427.4  201.82  5482.7  204.53
  5509.5   210.2  5514.7  208.35  5532.4  211.75  5658.5  213.19    5789  220.93
#Mann= 4 ,-1 , 0
  4050.5     .17       0  4405.2     .15       0  4976.6     .09       0
  5017.6     .15       0
Bank Sta=4976.6,5017.6
XS Rating Curve= 0 ,0
Exp/Cntr=0.3,0.1

Type RM Length L Ch R = 1 ,9886    ,451,451,451
BEGIN DESCRIPTION:
LANDRUM CREEK 15.0
END DESCRIPTION:
XS GIS Cut Line= 3
      3750481.21     10112579.24      3749805.21     10112780.05
      3748866.63     10112922.98
#Sta/Elev= 30
  4294.8  217.87  4564.5  211.74  4630.9  211.02  4713.7  207.82    4886  200.76
  4917.4  200.33  4934.6  198.76  4955.8  200.74  4976.4  200.92  4990.5  196.91
  5001.5  196.91  5007.4  199.52  5027.7  200.88  5036.4  200.34    5058  201.43
  5070.5  200.39  5098.5  200.65  5118.7  199.59  5138.9  200.15  5149.1   198.2
  5168.5  197.43  5179.4   197.6  5199.6  200.18  5432.3  199.72  5543.5   201.1
  5664.9  207.21  5765.8  214.71  5887.5  224.88  5917.8  228.74  5949.4  231.44
#Mann= 6 ,-1 , 0
  4294.8     .11       0  4713.7     .17       0    4886     .15       0
  4976.4     .09       0  5027.7     .15       0  5070.5     .11       0
Bank Sta=4976.4,5027.7
XS Rating Curve= 0 ,0
Exp/Cntr=0.3,0.1

Type RM Length L Ch R = 1 ,9435    ,447,447,447
BEGIN DESCRIPTION:
LANDRUM CREEK 14.0
END DESCRIPTION:
XS GIS Cut Line= 3
      3750144.47     10112297.97      3749688.89     10112347.76
      3748832.37     10112707.51
#Sta/Elev= 30
  4541.7   214.4  4558.4  213.62    4615  212.84  4636.6  211.83  4719.4  209.36
  4809.9  205.19  4860.2   203.9  4960.8  199.83    4991  199.11  5038.6  199.11
  5077.8   198.8  5109.6  197.71  5125.3  198.81    5202  198.17    5294  199.24
  5337.4  198.07  5348.2  194.62  5349.9  193.17  5360.9  193.17  5369.9  197.91
  5402.4  198.83  5424.1  197.79  5478.4  197.62    5538  198.99  5638.4  199.16
  5684.4  200.44  5844.8  209.87  5873.9  212.61  5890.5  213.36    5929  217.86
#Mann= 5 ,-1 , 0
  4541.7     .11       0  4636.6     .17       0  5038.6     .11       0
  5337.4     .09       0  5369.9     .11       0
Bank Sta=5337.4,5369.9
XS Rating Curve= 0 ,0
Exp/Cntr=0.3,0.1

Type RM Length L Ch R = 1 ,8988    ,314,314,314
BEGIN DESCRIPTION:
LANDRUM CREEK 13.0
END DESCRIPTION:
XS GIS Cut Line= 3
      3750203.43     10112138.24      3749721.87     10111910.26
      3748691.19     10112151.76
#Sta/Elev= 30
  4467.2  214.99    4573  212.51  4663.1  208.27  4733.9  206.51  4913.3  199.58
  4990.4  198.55  5014.1  198.69    5053     198    5076  197.24  5363.6  196.76
  5372.1  193.64  5383.1  193.64  5384.2  195.66  5388.2196.8051  5394.4  198.58
  5404.7  197.25  5425.2  196.68  5527.9  197.25  5547.4   196.3  5589.6   198.3
  5642.6  197.44  5679.9  195.59  5702.5  196.59  5784.7  196.07  5805.3  197.57
  5846.3  197.64  5902.5  202.52  5950.1   209.7  5987.4  213.69  6058.6  216.12
#Mann= 7 ,-1 , 0
  4467.2     .11       0  4733.9     .17       0  4990.4     .11       0
  5014.1     .17       0    5053     .11       0  5363.6    .065       0
  5388.2     .11       0
Bank Sta=5363.6,5388.2
XS Rating Curve= 0 ,0
Exp/Cntr=0.3,0.1

Type RM Length L Ch R = 1 ,8674    ,392,392,392
BEGIN DESCRIPTION:
LANDRUM CREEK 12.0
END DESCRIPTION:
XS GIS Cut Line= 3
      3750547.26     10111853.55      3749793.05      10111604.7
      3748617.81     10112111.09
#Sta/Elev= 30
  4205.8   216.7  4436.8  211.05  4489.9  210.68  4516.4  208.77  4643.4  205.34
  4680.4   203.2  4738.6  203.18  4938.2  198.11  4997.8  197.98  5007.3  196.22
  5025.4  197.76  5039.6  198.41  5115.1  197.34  5334.9  197.11    5353  196.07
  5481.5  197.17    5528  196.04  5702.5  197.76    5715  196.45    5733  197.64
  5908.6  196.33  5974.8  197.27  5990.1  197.95  6037.1  203.84  6042.6  203.31
  6083.7  209.38  6089.6   211.5  6136.7  215.86  6189.2  218.65  6279.7  220.18
#Mann= 6 ,-1 , 0
  4205.8     .17       0  4938.2     .15       0  4997.8     .09       0
  5025.4     .11       0  5039.6     .17       0  5115.1     .11       0
Bank Sta=4997.8,5025.4
XS Rating Curve= 0 ,0
Exp/Cntr=0.3,0.1

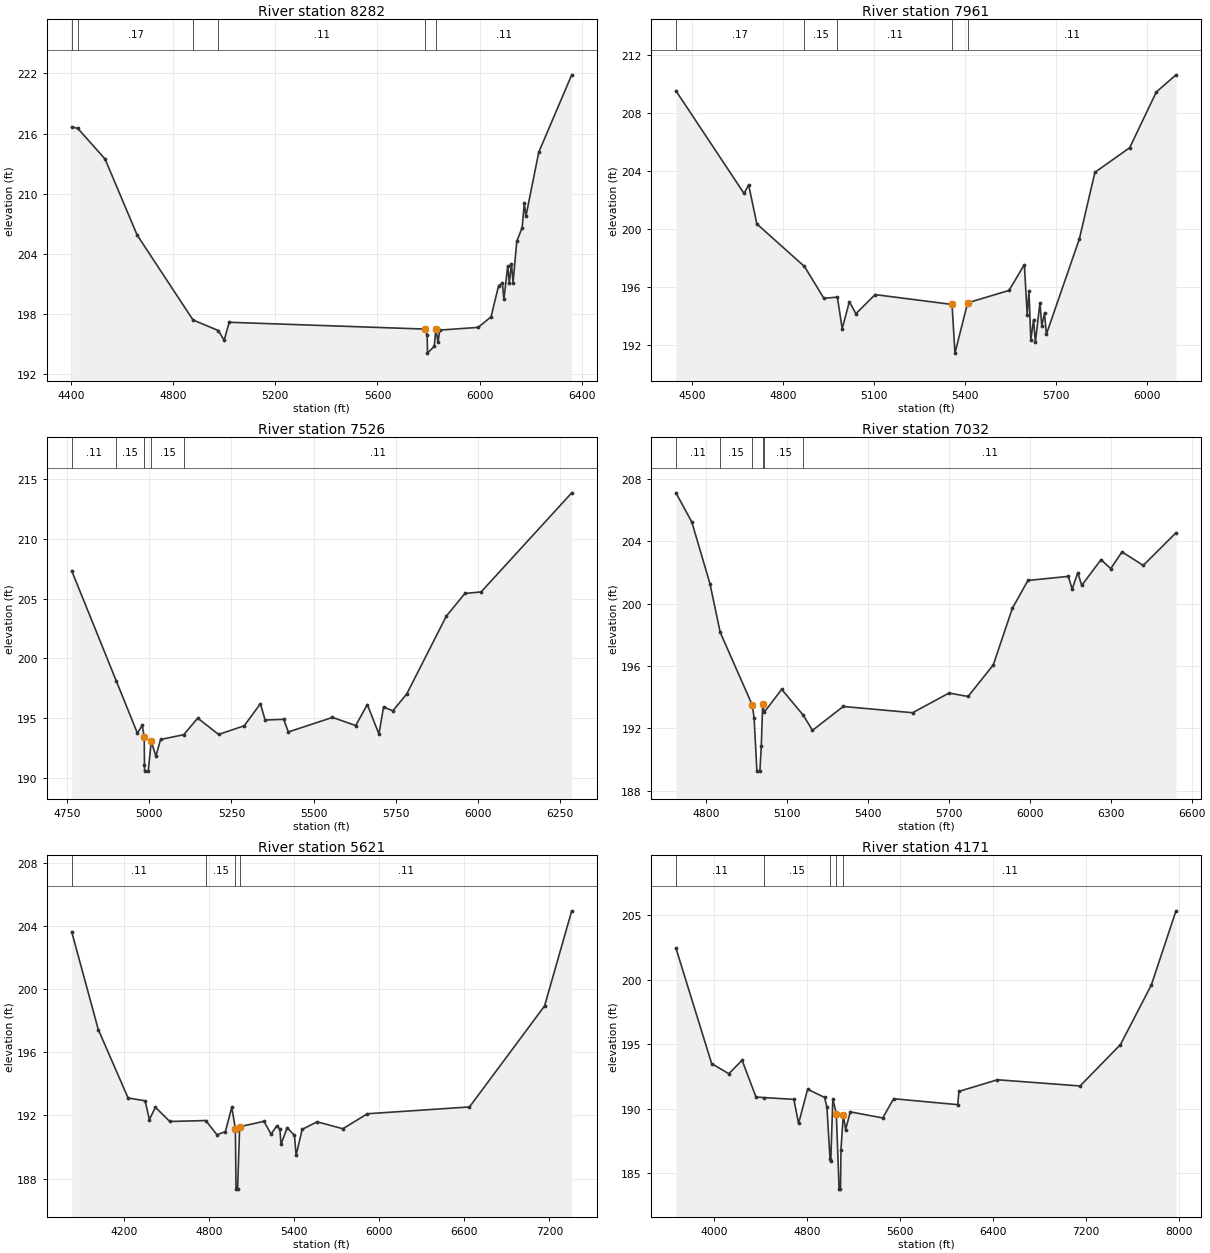
Type RM Length L Ch R = 1 ,8282    ,321,321,321
BEGIN DESCRIPTION:
LANDRUM CREEK 11.0
END DESCRIPTION:
XS GIS Cut Line= 3
      3750367.81     10111161.08      3749773.96     10111219.28
      3748667.85     10112011.08
#Sta/Elev= 30
  4403.3  216.67  4427.3  216.51  4533.9  213.46  4659.5  205.87  4878.2  197.39
  4977.7  196.33    5000  195.35  5019.8  197.16  5786.6  196.48  5794.6  195.91
  5795.8  194.08  5822.2  194.75 5828.74196.5144    5837  195.15  5843.8  196.38
  5994.2  196.65  6044.6  197.71  6074.1  200.82  6088.8  201.05  6094.9  199.46
  6109.7  202.77  6115.8  201.12  6124.4  203.01  6130.6  201.12  6145.3  205.25
  6166.2   206.6  6174.8  209.05  6180.9  207.74  6231.3  214.14  6360.3  221.86
#Mann= 6 ,-1 , 0
  4403.3     .11       0  4427.3     .17       0  4878.2     .15       0
  4977.7     .11       0  5786.6     .07       0 5828.74     .11       0
Bank Sta=5786.6,5828.74
XS Rating Curve= 0 ,0
Exp/Cntr=0.3,0.1

Type RM Length L Ch R = 1 ,7961    ,435,435,435
BEGIN DESCRIPTION:
LANDRUM CREEK 10.0
END DESCRIPTION:
XS GIS Cut Line= 3
      3750220.86     10110784.08      3749683.68     10110911.99
      3748767.82     10111511.09
#Sta/Elev= 30
  4447.8  209.52  4672.1  202.43  4687.3  203.03  4714.2  200.33  4871.1  197.39
  4935.2  195.19  4979.4  195.28  4995.3   193.1  5018.9  194.96  5040.4  194.13
  5103.7  195.45    5357  194.77  5366.6  191.41  5408.3  194.88  5544.7  195.74
  5595.2  197.52  5604.4  194.07  5610.3   195.7  5616.4  192.31  5625.5  193.73
  5631.4  192.15  5646.5  194.89  5652.5  193.31  5661.6  194.17  5667.6  192.71
  5776.2  199.29  5827.5  203.89    5942  205.59  6029.5  209.43  6094.4  210.62
#Mann= 5 ,-1 , 0
  4447.8     .17       0  4871.1     .15       0  4979.4     .11       0
    5357    .065       0  5408.3     .11       0
Bank Sta=5357,5408.3
XS Rating Curve= 0 ,0
Exp/Cntr=0.3,0.1

Type RM Length L Ch R = 1 ,7526    ,494,494,494
BEGIN DESCRIPTION:
LANDRUM CREEK 9.0
END DESCRIPTION:
XS GIS Cut Line= 3
      3749717.86     10110361.07       3749530.9     10110505.74
      3748617.85     10111411.07
#Sta/Elev= 30
  4763.6  207.35  4899.3  198.12  4963.7  193.74  4978.2  194.39  4984.5  193.44
  4985.2  191.06  4985.7  190.56  4996.7  190.56  5005.9  193.06    5020  191.81
  5034.2  193.21  5104.7  193.61  5147.3     195    5211  193.63  5288.8  194.36
  5338.3  196.21  5352.4  194.84    5409   194.9  5423.1  193.84  5557.5  195.06
  5628.2  194.38  5663.6  196.14  5698.9  193.66    5713  195.93  5741.3  195.61
  5783.7  197.03    5904  203.54  5960.6  205.44    6010  205.57  6285.8  213.87
#Mann= 5 ,-1 , 0
  4763.6     .11       0  4899.3     .15       0  4984.5     .09       0
  5005.9     .15       0  5104.7     .11       0
Bank Sta=4984.5,5005.9
XS Rating Curve= 0 ,0
Exp/Cntr=0.3,0.1

Type RM Length L Ch R = 1 ,7032    ,1411,1411,1411
BEGIN DESCRIPTION:
LANDRUM CREEK 8.0
END DESCRIPTION:
XS GIS Cut Line= 3
      3749667.82     10110261.06      3749384.02     10110120.89
      3748167.87     10111061.05
#Sta/Elev= 30
  4688.3  207.09  4747.2  205.22  4814.5  201.27  4852.4  198.16  4971.6  193.49
  4978.2  192.65  4988.5  189.27  4999.5  189.27  5004.8  190.87  5009.8  193.59
  5016.1  193.05  5080.4  194.51  5160.4  192.85  5194.5  191.88  5308.6  193.41
  5565.8  193.01  5700.7  194.27  5771.4  194.05  5864.7  196.07  5935.3  199.69
  5993.2  201.48  6142.7  201.74  6157.2  200.93    6178  201.98  6192.5  201.16
    6264  202.81  6300.3  202.24  6341.9  203.31  6420.7  202.44    6542  204.53
#Mann= 6 ,-1 , 0
  4688.3     .11       0  4852.4     .15       0  4971.6     .09       0
  5009.8     .12       0  5016.1     .15       0  5160.4     .11       0
Bank Sta=4971.6,5009.8
XS Rating Curve= 0 ,0
Exp/Cntr=0.3,0.1

Type RM Length L Ch R = 1 ,5621    ,1450,1450,1450
BEGIN DESCRIPTION:
LANDRUM CREEK 7.0
END DESCRIPTION:
XS GIS Cut Line= 4
      3749817.86     10110061.08      3749220.83     10109172.98
      3748814.58     10109124.36      3748130.53     10111051.49
#Sta/Elev= 30
    3833  203.63  4020.5  197.44  4230.5  193.11  4351.1  192.93  4380.5  191.74
  4423.4  192.52  4524.5  191.62  4777.6  191.68  4857.2  190.78  4916.2  190.98
  4961.4  192.52  4986.7  191.17  4991.3  187.34  5002.3  187.34  5016.9  191.29
  5188.1  191.63  5238.5  190.82  5278.8  191.35  5300.9  191.12  5308.1  190.17
  5351.9  191.23    5403  190.74  5414.9  189.48  5457.3  191.12  5563.5   191.6
  5743.8  191.16  5917.1  192.11  6636.6  192.54  7165.7  198.93  7357.2  204.95
#Mann= 4 ,-1 , 0
    3833     .11       0  4777.6     .15       0  4986.7    .065       0
  5016.9     .11       0
Bank Sta=4986.7,5016.9
XS Rating Curve= 0 ,0
Exp/Cntr=0.3,0.1

Type RM Length L Ch R = 1 ,4171    ,1479,1479,1479
BEGIN DESCRIPTION:
LANDRUM CREEK 4.0
END DESCRIPTION:
XS GIS Cut Line= 4
      3750375.09     10108735.64      3749068.46     10108478.42
      3748822.95      10108464.8      3748046.91     10111084.59
#Sta/Elev= 30
  3668.3  202.47  3976.5  193.51  4124.1  192.73  4238.5  193.77  4358.5  190.92
  4425.7  190.88  4684.7  190.74  4725.4  188.87  4803.5  191.53  4949.7  190.89
    4970  190.11  4996.5  186.13  5002.8  185.93  5020.6  190.77  5050.7  189.63
  5074.7  183.78  5086.7  183.78  5090.8  186.85  5110.8  189.55  5130.8  188.39
  5170.9  189.77  5450.6   189.3  5544.5  190.79  6097.2  190.33  6107.6  191.36
  6439.8  192.26  7151.7  191.78  7499.8  194.99  7765.9  199.61  7978.2  205.36
#Mann= 5 ,-1 , 0
  3668.3     .11       0  4425.7     .15       0  4996.5     .11       0
  5050.7     .06       0  5110.8     .11       0
Bank Sta=5050.7,5110.8
XS Rating Curve= 0 ,0
Exp/Cntr=0.3,0.1

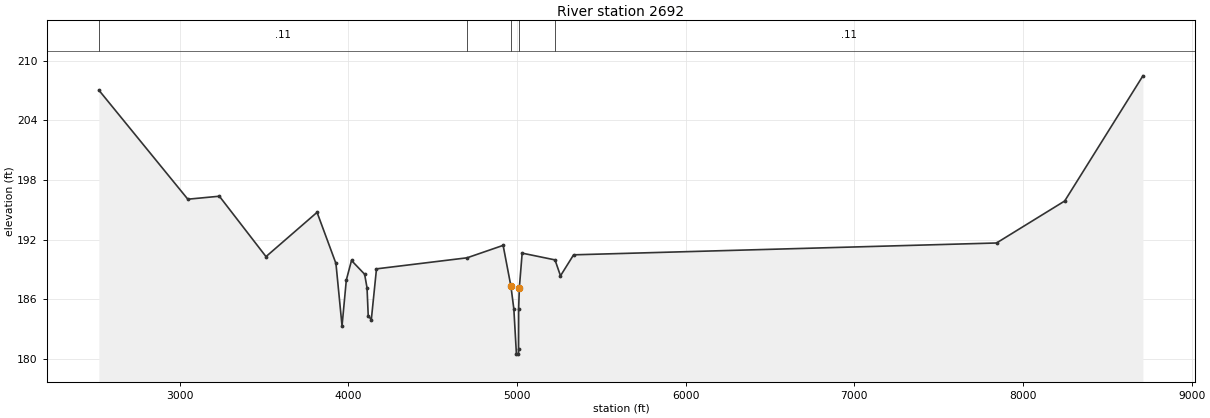
Type RM Length L Ch R = 1 ,2692    ,0,0,0
BEGIN DESCRIPTION:
LANDRUM CREEK 2.0
END DESCRIPTION:
XS GIS Cut Line= 4
      3751369.82     10108084.59      3749390.66     10107371.05
       3748854.2      10107964.8      3747927.11     10111115.89
#Sta/Elev= 30
    2522  207.02  3049.3  196.06  3236.3  196.36  3512.7  190.29  3815.3  194.74
  3927.3   189.6  3963.4  183.33  3988.8  187.94  4019.5   189.9  4097.3  188.52
  4111.6  187.15  4118.6  184.36  4136.9  183.94  4167.6  189.06  4704.5  190.17
  4918.3  191.42  4964.7187.2906  4981.8  185.03  4997.1  180.49  5009.3  180.49
  5009.8  180.99  5010.2  185.04  5014.5  187.18  5031.1  190.64  5225.8  189.96
  5258.3  188.36    5336  190.47  7842.9  191.66    8247  195.88  8710.7  208.46
#Mann= 5 ,-1 , 0
    2522     .11       0  4704.5     .15       0  4964.7     .06       0
  5014.5     .15       0  5225.8     .11       0
Bank Sta=4964.7,5014.5
XS Rating Curve= 0 ,0
Exp/Cntr=0.3,0.1

Chan Stop Cuts=-1
Use User Specified Reach Order=0
Composite Channel Slope=5