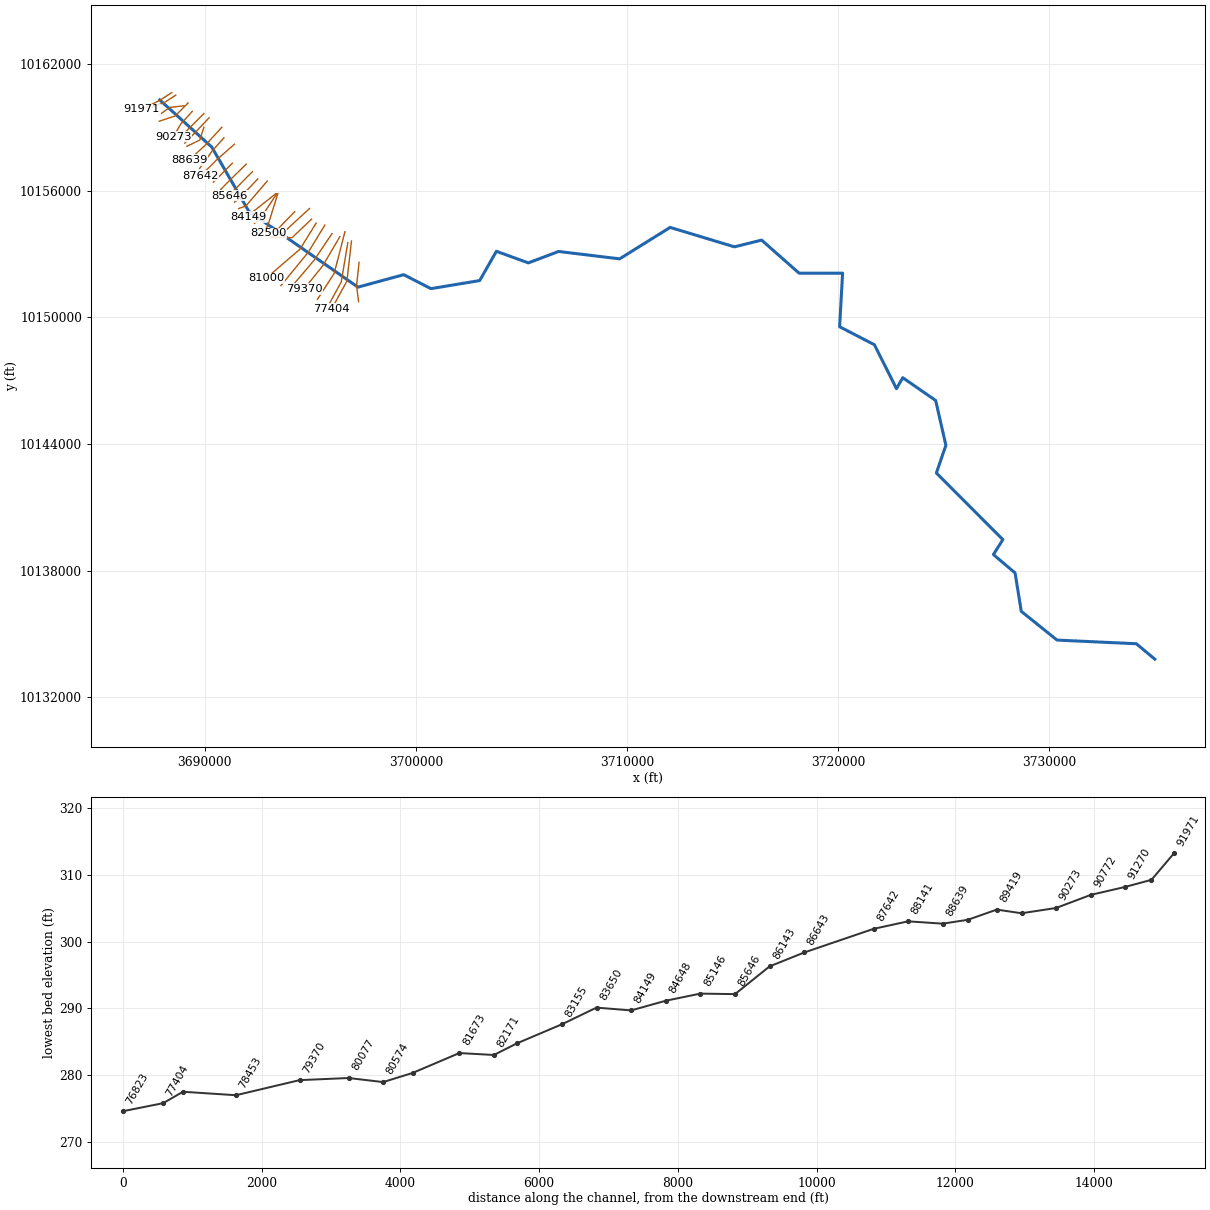
--- LITTLE CANEY CREEK.prj (project) ---

Proj Title=LITTLE CANEY CREEK Base Level Engineering
Current Plan=p01
Default Exp/Contr=0.3,0.1
English Units
Geom File=g01
Flow File=f01
Plan File=p01
Y Axis Title=Elevation
X Axis Title(PF)=Main Channel Distance
X Axis Title(XS)=Station
BEGIN DESCRIPTION:
LITTLE CANEY CREEK
END DESCRIPTION:
DSS Export Rating Curves= 0
DSS Export Rating Curve Sorted= 0
DSS Export Volume Flow Curves= 0
DXF OffsetX= 0
DXF OffsetY= 0
DXF ScaleX= 1
DXF ScaleY= 10

--- LITTLE CANEY CREEK.p01 (plan) ---

Plan Title=Multiple Run
Short Identifier=Multiple
Geom File=g01
Flow File=f01
Subcritical Flow
K Sum by GR= 0
Std Step Tol= 0.01
Critical Tol= 0.01
Num of Std Step Trials= 20
Max Error Tol= 0.3
Flow Tol Ratio= 0.001
Split Flow NTrial= 30
Split Flow Tol= 0.02
Split Flow Ratio= 0.02
Log Output Level= 0
Friction Slope Method= 1
Unsteady Friction Slope Method= 2
Unsteady Bridges Friction Slope Method= 1
Parabolic Critical Depth
Global Vel Dist=  1 , 1 , 1
Global Log Level= 0
CheckData=True
Encroach Param= -1, 0, 0, 0
BEGIN DESCRIPTION:
Multiple Run
END DESCRIPTION:

--- LITTLE CANEY CREEK.f01 (steady flow) ---

Flow Title=Multiple
Program Version=4.10
Number of Profiles= 7
Profile Names=10-year,25-year,50-year,1pct_min,100-year,1pct_plu,500-year
River Rch & RM=LITTLE CANEY CRE,Reach-1         ,91971
    1672    2361    3279    1490    4501   13593    8787
River Rch & RM=LITTLE CANEY CRE,Reach-1         ,91648
    1672    2361    3279    1490    4501   13593    8787
River Rch & RM=LITTLE CANEY CRE,Reach-1         ,82500
    2142    3075    4318    1984    5993   18099   11964
River Rch & RM=LITTLE CANEY CRE,Reach-1         ,81000
    3199    4645    6575    3042    9187   27744   18586
River Rch & RM=LITTLE CANEY CRE,Reach-1         ,75222
    3377    4914    6964    3227    9744   29426   19758
River Rch & RM=LITTLE CANEY CRE,Reach-1         ,74293
    3376    4897    6923    3199    9660   29173   19484
River Rch & RM=LITTLE CANEY CRE,Reach-1         ,70335
    3534    5133    7263    3359   10144   30634   20496
River Rch & RM=LITTLE CANEY CRE,Reach-1         ,68063
    3597    5224    7395    3420   10329   31193   20870
River Rch & RM=LITTLE CANEY CRE,Reach-1         ,65596
    4153    6033    8539    3947   11920   35998   24052
River Rch & RM=LITTLE CANEY CRE,Reach-1         ,61673
    4411    6435    9133    4234   12786   38613   25946
River Rch & RM=LITTLE CANEY CRE,Reach-1         ,56057
    4493    6491    9152    4210   12715   38399   25422
River Rch & RM=LITTLE CANEY CRE,Reach-1         ,51087
    4759    6917    9792    4525   13666   41271   27558
River Rch & RM=LITTLE CANEY CRE,Reach-1         ,49482
    5072    7380   10456    4834   14599   44088   29474
River Rch & RM=LITTLE CANEY CRE,Reach-1         ,47292
    4879    7060    9967    4590   13862   41863   27766
River Rch & RM=LITTLE CANEY CRE,Reach-1         ,37578
    4799    6900    9697    4445   13423   40537   26629
River Rch & RM=LITTLE CANEY CRE,Reach-1         ,25514
    5213    7552   10669    4916   14847   44837   29773
River Rch & RM=LITTLE CANEY CRE,Reach-1         ,23192
    5379    7755   10919    5015   15144   45734   30150
River Rch & RM=LITTLE CANEY CRE,Reach-1         ,21335
    5262    7557   10612    4860   14678   44327   29059
River Rch & RM=LITTLE CANEY CRE,Reach-1         ,14972
    5061    7229   10114    4614   13935   42083   27374
River Rch & RM=LITTLE CANEY CRE,Reach-1         ,11050
    5486    7892   11096    5088   15365   46402   30489
River Rch & RM=LITTLE CANEY CRE,Reach-1         ,5592
    4965    7065    9857    4484   13540   40890   26442
Boundary for River Rch & Prof#=LITTLE CANEY CRE,Reach-1         , 1
Up Type= 0
Dn Type= 3
Dn Slope=0.0007
Boundary for River Rch & Prof#=LITTLE CANEY CRE,Reach-1         , 2
Up Type= 0
Dn Type= 3
Dn Slope=0.0007
Boundary for River Rch & Prof#=LITTLE CANEY CRE,Reach-1         , 3
Up Type= 0
Dn Type= 3
Dn Slope=0.0007
Boundary for River Rch & Prof#=LITTLE CANEY CRE,Reach-1         , 4
Up Type= 0
Dn Type= 3
Dn Slope=0.0007
Boundary for River Rch & Prof#=LITTLE CANEY CRE,Reach-1         , 5
Up Type= 0
Dn Type= 3
Dn Slope=0.0007
Boundary for River Rch & Prof#=LITTLE CANEY CRE,Reach-1         , 6
Up Type= 0
Dn Type= 3
Dn Slope=0.0007
Boundary for River Rch & Prof#=LITTLE CANEY CRE,Reach-1         , 7
Up Type= 0
Dn Type= 3
Dn Slope=0.0007
DSS Import GetInterval= 0
DSS Import GetPeak= 0
DSS Import FillOption= 0

--- LITTLE CANEY CREEK.g01 (geometry) ---

Geom Title=Existing Conditions
Program Version=4.10

River Reach=LITTLE CANEY CRE,Reach-1
Reach XY= 30
      3687878.23     10160306.84       3690342.6     10158072.28
      3692094.17     10155031.99      3697262.51     10151437.76
      3699429.27     10152027.04       3700719.4     10151366.56
      3703024.89     10151747.93      3703816.41     10153136.73
      3705329.49     10152586.73      3706760.52     10153126.87
      3709652.05     10152777.52      3712042.29     10154267.26
       3715086.2     10153347.12      3716374.24     10153665.63
      3718148.81     10152098.68      3720208.23     10152096.84
      3720066.73      10149561.9      3721715.01     10148708.69
      3722758.23     10146626.84      3723058.23     10147146.84
       3724615.2     10146068.46      3725098.23     10143946.84
      3724648.13     10142634.99      3727795.19     10139478.48
      3727349.14     10138770.21      3728375.28     10137898.39
      3728666.76     10136081.45      3730359.87     10134718.48
      3734116.01     10134545.43      3734988.23     10133816.84

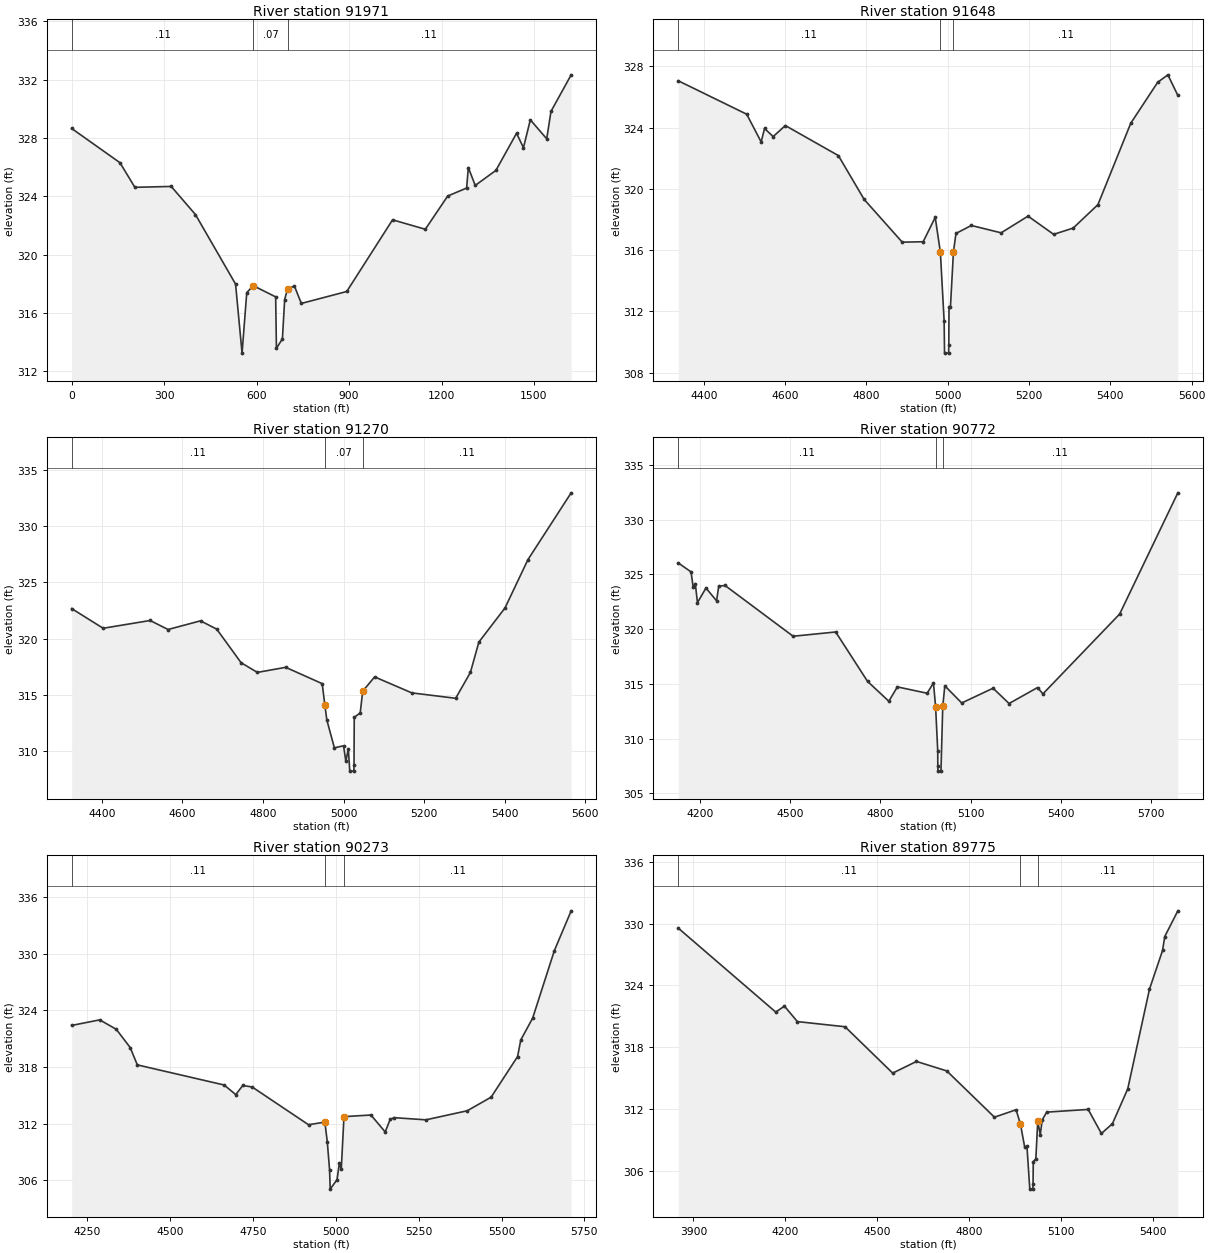
Type RM Length L Ch R = 1 ,91971   ,323,323,323
XS GIS Cut Line= 3
      3688450.43     10160653.56      3687890.53     10160293.32
      3687035.58      10159864.7
#Sta/Elev= 30
       0  328.66   156.7  326.31   205.2  324.62   323.1  324.68   401.7  322.75
   531.8  317.98   552.9  313.24   568.1  317.39   589.2  317.87   661.9   317.1
   664.4  313.57   683.8  314.22   691.1  316.92   700.5  317.65   722.8  317.84
   745.2  316.65   892.5  317.47  1041.2  322.39  1147.4  321.74    1220  324.02
  1281.4  324.57    1287  325.97  1309.4  324.75  1376.4  325.78  1443.4  328.33
  1465.8  327.34  1488.1  329.25  1541.3  327.95  1555.1  329.83  1620.6  332.34
#Mann= 3 , 0 , 0
       0     .11       0   589.2     .07       0   700.5     .11       0
Bank Sta=589.2,700.5
XS Rating Curve= 0 ,0
Exp/Cntr=0.3,0.1

Type RM Length L Ch R = 1 ,91648   ,378,378,378
BEGIN DESCRIPTION:
LITTLE CANEY CREEK 126.0
END DESCRIPTION:
XS GIS Cut Line= 3
      3688639.27     10160532.06      3688079.33     10160171.79
      3687551.33     10159977.03
#Sta/Elev= 30
  4337.5  327.05  4505.7  324.87  4541.3  323.06  4549.6  323.94  4570.7  323.41
  4600.8  324.13  4731.2  322.17  4794.6  319.31  4888.3  316.52  4939.8  316.55
  4969.4  318.14  4982.1  315.86  4991.3  311.37  4992.3  309.28  5002.3  309.28
  5002.8  309.78  5003.3  312.28  5006.8  312.28 5014.19315.8849  5020.4  317.09
  5058.2  317.61  5131.5  317.13  5197.7  318.22  5260.7  317.03  5308.7  317.44
  5369.6  318.97  5450.3  324.28  5516.5  326.95  5541.6  327.44  5566.1   326.1
#Mann= 3 , 0 , 0
  4337.5     .11       0  4982.1     .07       0 5014.19     .11       0
Bank Sta=4982.1,5014.19
XS Rating Curve= 0 ,0
Exp/Cntr=0.3,0.1

Type RM Length L Ch R = 1 ,91270   ,498,498,498
BEGIN DESCRIPTION:
LITTLE CANEY CREEK 125.0
END DESCRIPTION:
XS GIS Cut Line= 3
      3689025.56     10160028.57      3688355.25     10159950.87
      3687893.57     10159625.53
#Sta/Elev= 30
  4325.2  322.66  4403.4  320.91  4519.9   321.6  4564.5   320.8    4645  321.57
  4685.3  320.83  4745.7  317.85  4786.1  316.99  4856.4  317.44    4947  315.99
  4953.5   314.1  4958.5  312.76  4977.2  310.29    5000  310.47  5005.6  309.09
  5011.8   310.2  5015.4  308.22  5025.4  308.22  5025.9  308.72  5026.5     313
  5041.3  313.39  5047.5  315.32  5077.1  316.59  5169.4  315.17  5278.2  314.69
  5314.8  316.99  5335.7  319.68  5400.5  322.71  5457.6  327.01  5564.8  332.94
#Mann= 3 , 0 , 0
  4325.2     .11       0  4953.5     .07       0  5047.5     .11       0
Bank Sta=4953.5,5047.5
XS Rating Curve= 0 ,0
Exp/Cntr=0.3,0.1

Type RM Length L Ch R = 1 ,90772   ,499,499,499
BEGIN DESCRIPTION:
LITTLE CANEY CREEK 124.0
END DESCRIPTION:
XS GIS Cut Line= 3
      3689217.86     10160161.08      3688604.77     10159540.86
      3687853.63     10159299.39
#Sta/Elev= 30
  4127.9  326.05  4170.3  325.23  4177.4  323.83  4184.4  324.16  4191.6  322.42
  4219.8  323.76  4255.2  322.59  4262.3  323.93  4283.4  323.99  4509.7  319.35
  4651.2  319.74  4757.3  315.22    4828  313.41  4856.3  314.72  4955.3  314.14
  4976.4  315.08  4983.6  312.88  4990.6  308.86  4990.8  307.52  4991.3  307.02
  5001.3  307.02  5007.3  312.93  5014.1  314.82  5070.3  313.25  5174.6   314.6
  5227.8   313.2  5322.4  314.66  5340.3  314.08  5595.5  321.38    5789  332.46
#Mann= 3 , 0 , 0
  4127.9     .11       0  4983.6     .07       0  5007.3     .11       0
Bank Sta=4983.6,5007.3
XS Rating Curve= 0 ,0
Exp/Cntr=0.3,0.1

Type RM Length L Ch R = 1 ,90273   ,498,498,498
BEGIN DESCRIPTION:
LITTLE CANEY CREEK 123.0
END DESCRIPTION:
XS GIS Cut Line= 3
      3689417.85     10159761.07      3688879.93     10159172.15
      3688517.85     10158561.07
#Sta/Elev= 30
  4202.4   322.4  4287.2  322.99  4337.2  321.99  4379.1  320.06  4400.7  318.22
  4662.8  316.09  4697.9  315.07  4718.9  316.04  4747.3  315.88  4917.5  311.88
  4966.8  312.16  4974.2  310.05    4981   307.1  4982.9  305.06  5003.5  306.06
  5010.5  307.79  5016.3  307.17  5024.5  312.74  5105.9  312.91  5148.9  311.12
    5164  312.45  5176.1  312.63  5271.7   312.4  5396.5  313.36  5468.6   314.8
  5548.5   319.1  5558.3  320.87  5594.1  323.18  5659.6  330.33  5710.3  334.54
#Mann= 3 , 0 , 0
  4202.4     .11       0  4966.8     .07       0  5024.5     .11       0
Bank Sta=4966.8,5024.5
XS Rating Curve= 0 ,0
Exp/Cntr=0.3,0.1

Type RM Length L Ch R = 1 ,89775   ,356,356,356
BEGIN DESCRIPTION:
LITTLE CANEY CREEK 122.0
END DESCRIPTION:
XS GIS Cut Line= 3
      3689967.87     10159661.09      3689156.24     10158847.08
      3688867.88     10158461.11
#Sta/Elev= 30
  3850.5  329.55  4168.7  321.42    4197     322  4239.4   320.5    4395     320
  4550.6  315.51  4628.3  316.64  4727.3  315.72  4882.9  311.24  4953.6  311.96
  4967.8  310.57  4981.9  308.31    4989  308.45  4998.4  304.27  5008.5  304.27
    5009  304.77  5009.7  306.93  5018.1  307.21  5024.3  310.86  5032.5  309.55
  5038.9  310.97  5053.5  311.73    5189  311.99  5232.2  309.66  5268.2  310.61
  5318.2  313.98  5389.1  323.63  5431.9  327.39  5439.1  328.74  5481.8  331.23
#Mann= 3 , 0 , 0
  3850.5     .11       0  4967.8     .06       0  5024.3     .11       0
Bank Sta=4967.8,5024.3
XS Rating Curve= 0 ,0
Exp/Cntr=0.3,0.1

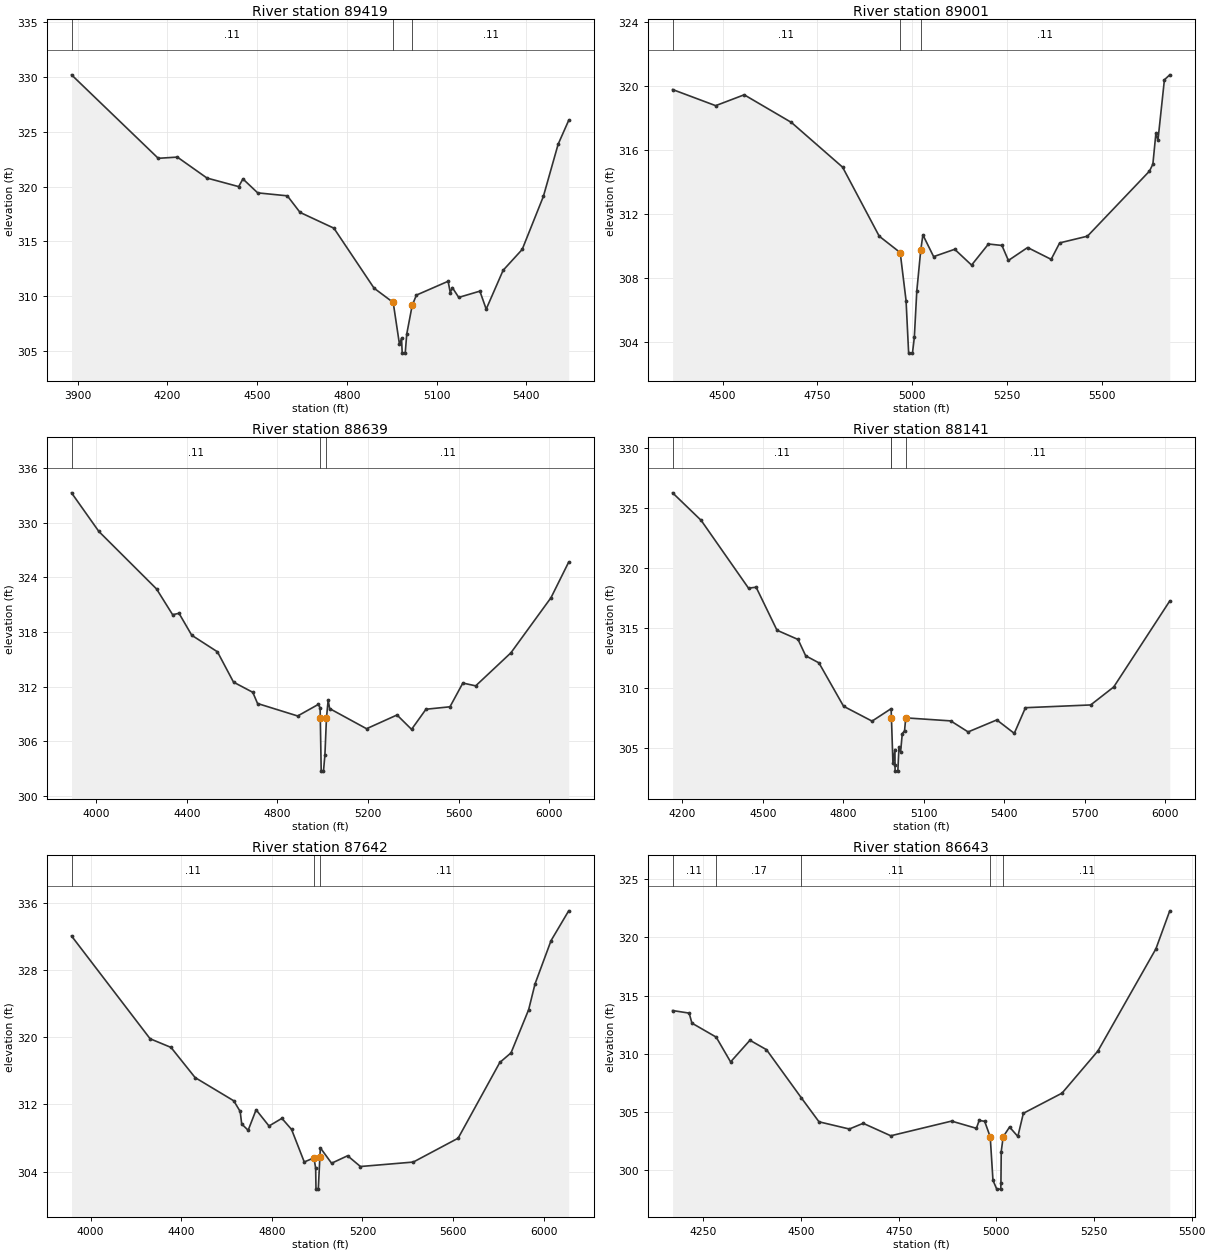
Type RM Length L Ch R = 1 ,89419   ,418,418,418
BEGIN DESCRIPTION:
LITTLE CANEY CREEK 121.0
END DESCRIPTION:
XS GIS Cut Line= 3
      3690217.87      10159461.1      3689446.31     10158648.29
      3689067.89     10158261.11
#Sta/Elev= 30
  3879.3  330.19  4169.2  322.58  4233.1  322.69  4332.2  320.78  4438.1     320
  4452.3   320.7  4501.7  319.43  4600.8  319.16  4643.2  317.65  4756.5  316.21
  4890.8  310.74  4954.7  309.44  4975.7  305.62  4982.6  306.17  4984.8  304.82
  4994.9  304.82    5000  306.56  5018.2  309.17  5032.3  310.11  5138.3  311.37
  5145.5  310.34  5152.5  310.79  5173.8   309.9  5244.5  310.47  5265.6  308.83
  5322.2  312.37  5385.9  314.27  5456.7   319.1  5506.1  323.86  5541.4  326.04
#Mann= 3 , 0 , 0
  3879.3     .11       0  4954.7     .06       0  5018.2     .11       0
Bank Sta=4954.7,5018.2
XS Rating Curve= 0 ,0
Exp/Cntr=0.3,0.1

Type RM Length L Ch R = 1 ,89001   ,362,362,362
BEGIN DESCRIPTION:
LITTLE CANEY CREEK 120.0
END DESCRIPTION:
XS GIS Cut Line= 3
      3689967.86     10159011.11      3689778.88     10158408.24
      3689167.81     10158111.05
#Sta/Elev= 30
  4368.2  319.79  4481.8  318.78  4557.1  319.46  4681.6  317.73  4816.6  314.93
  4913.2  310.61 4968.54 309.584    4984  306.58  4990.8  303.29  5000.9  303.29
  5005.8  304.27  5012.3  307.17  5022.8  309.75  5028.4  310.69  5056.7  309.33
  5112.3  309.79  5156.8   308.8  5201.3  310.12  5236.9  310.03  5253.9  309.09
  5304.6   309.9  5366.7  309.16  5389.2  310.19  5462.4  310.61  5625.9  314.68
    5635  315.12  5642.9  317.04  5648.4  316.62  5665.4   320.4  5679.5  320.71
#Mann= 3 , 0 , 0
  4368.2     .11       0 4968.54     .06       0  5022.8     .11       0
Bank Sta=4968.54,5022.8
XS Rating Curve= 0 ,0
Exp/Cntr=0.3,0.1

Type RM Length L Ch R = 1 ,88639   ,498,498,498
BEGIN DESCRIPTION:
LITTLE CANEY CREEK 119.0
END DESCRIPTION:
XS GIS Cut Line= 3
      3690817.82     10159011.04      3690068.85     10158193.97
      3689267.85     10157461.07
#Sta/Elev= 30
  3891.6  333.29  4012.1  329.05  4266.8  322.73  4337.7   319.9    4366  320.05
  4422.2  317.64  4535.6  315.82  4606.5  312.49  4691.6  311.37  4712.6  310.14
  4889.6  308.77  4981.4  310.05  4988.8  309.63 4989.51308.5448  4993.5  302.71
  5003.6  302.71  5009.9  304.51  5016.7  308.54  5024.1  310.49  5030.9  309.58
  5193.7  307.37  5328.1  308.88  5392.3   307.3  5455.8  309.51  5561.8  309.78
  5618.6  312.39  5675.3  312.08  5830.7  315.71  6007.7  321.77  6085.7  325.68
#Mann= 3 , 0 , 0
  3891.6     .11       0 4989.51     .06       0  5016.7     .11       0
Bank Sta=4989.51,5016.7
XS Rating Curve= 0 ,0
Exp/Cntr=0.3,0.1

Type RM Length L Ch R = 1 ,88141   ,499,499,499
BEGIN DESCRIPTION:
LITTLE CANEY CREEK 118.0
END DESCRIPTION:
XS GIS Cut Line= 3
      3690917.85     10158511.07      3690360.99     10157887.52
      3689767.83     10157061.05
#Sta/Elev= 30
    4164  326.27  4270.6  323.97    4447  318.32  4475.4   318.4  4553.2  314.81
  4631.7  314.04  4660.1  312.68  4709.5  312.09  4801.4  308.47  4907.6  307.23
  4978.7  308.27 4979.89307.4619  4985.4  303.72  4992.9  304.86  4993.1  303.56
  4993.6  303.06  5003.7  303.06  5007.9  305.07    5014  304.67  5020.2  306.18
  5028.8  306.44 5033.12307.5023  5200.7  307.25  5265.7  306.33  5372.6  307.33
  5437.7  306.21  5479.4  308.35  5722.6  308.58  5808.5  310.08  6017.3  317.25
#Mann= 4 ,-1 , 0
    4164     .11       0  4978.7     .09       0 4979.89     .06       0
 5033.12     .11       0
Bank Sta=4979.89,5033.12
XS Rating Curve= 0 ,0
Exp/Cntr=0.3,0.1

Type RM Length L Ch R = 1 ,87642   ,999,999,999
BEGIN DESCRIPTION:
LITTLE CANEY CREEK 117.0
END DESCRIPTION:
XS GIS Cut Line= 3
      3691417.85     10158211.07      3690602.95     10157495.94
      3689817.87     10156711.09
#Sta/Elev= 30
  3915.8  332.05  4262.6  319.82  4354.9  318.79  4461.3   315.2  4631.8  312.44
  4660.2  311.17  4666.9  309.68  4695.4  308.93  4730.5  311.37  4787.4  309.44
  4844.3  310.35    4887  309.03    4943  305.16  4985.7  305.65  4993.3  304.43
  4994.8  301.93    5005  301.93 5011.84 305.694  5014.1  306.84  5063.6  305.01
  5134.3   305.9  5190.9  304.62  5424.2  305.15  5622.2  307.99  5806.1     317
  5855.6  318.14  5933.4  323.28  5961.6  326.35  6032.3   331.5  6110.1  335.04
#Mann= 3 , 0 , 0
  3915.8     .11       0  4985.7     .06       0 5011.84     .11       0
Bank Sta=4985.7,5011.84
XS Rating Curve= 0 ,0
Exp/Cntr=0.3,0.1

Type RM Length L Ch R = 1 ,86643   ,500,500,500
BEGIN DESCRIPTION:
LITTLE CANEY CREEK 116.0
END DESCRIPTION:
XS GIS Cut Line= 3
      3691317.84     10157311.06      3690732.02     10156724.64
      3690417.84     10156411.06
#Sta/Elev= 30
  4171.1  313.72  4213.5   313.5  4220.6  312.64  4282.7  311.44  4319.6  309.31
  4369.1  311.17  4411.5  310.36  4500.2  306.25  4545.9  304.17  4623.6  303.55
    4659  304.04  4729.7  302.97  4885.3  304.23  4948.9  303.61    4956  304.29
  4970.1  304.21  4984.3  302.87  4991.3  299.15    5001  298.39  5011.2  298.39
  5011.7  298.89  5012.5  301.62  5017.5302.8876  5033.8  303.72    5055  302.91
  5069.1   304.9  5168.1  306.63    5260  310.25  5408.5  319.02  5443.9  322.28
#Mann= 5 ,-1 , 0
  4171.1     .11       0  4282.7     .17       0  4500.2     .11       0
  4984.3     .07       0  5017.5     .11       0
Bank Sta=4984.3,5017.5
XS Rating Curve= 0 ,0
Exp/Cntr=0.3,0.1

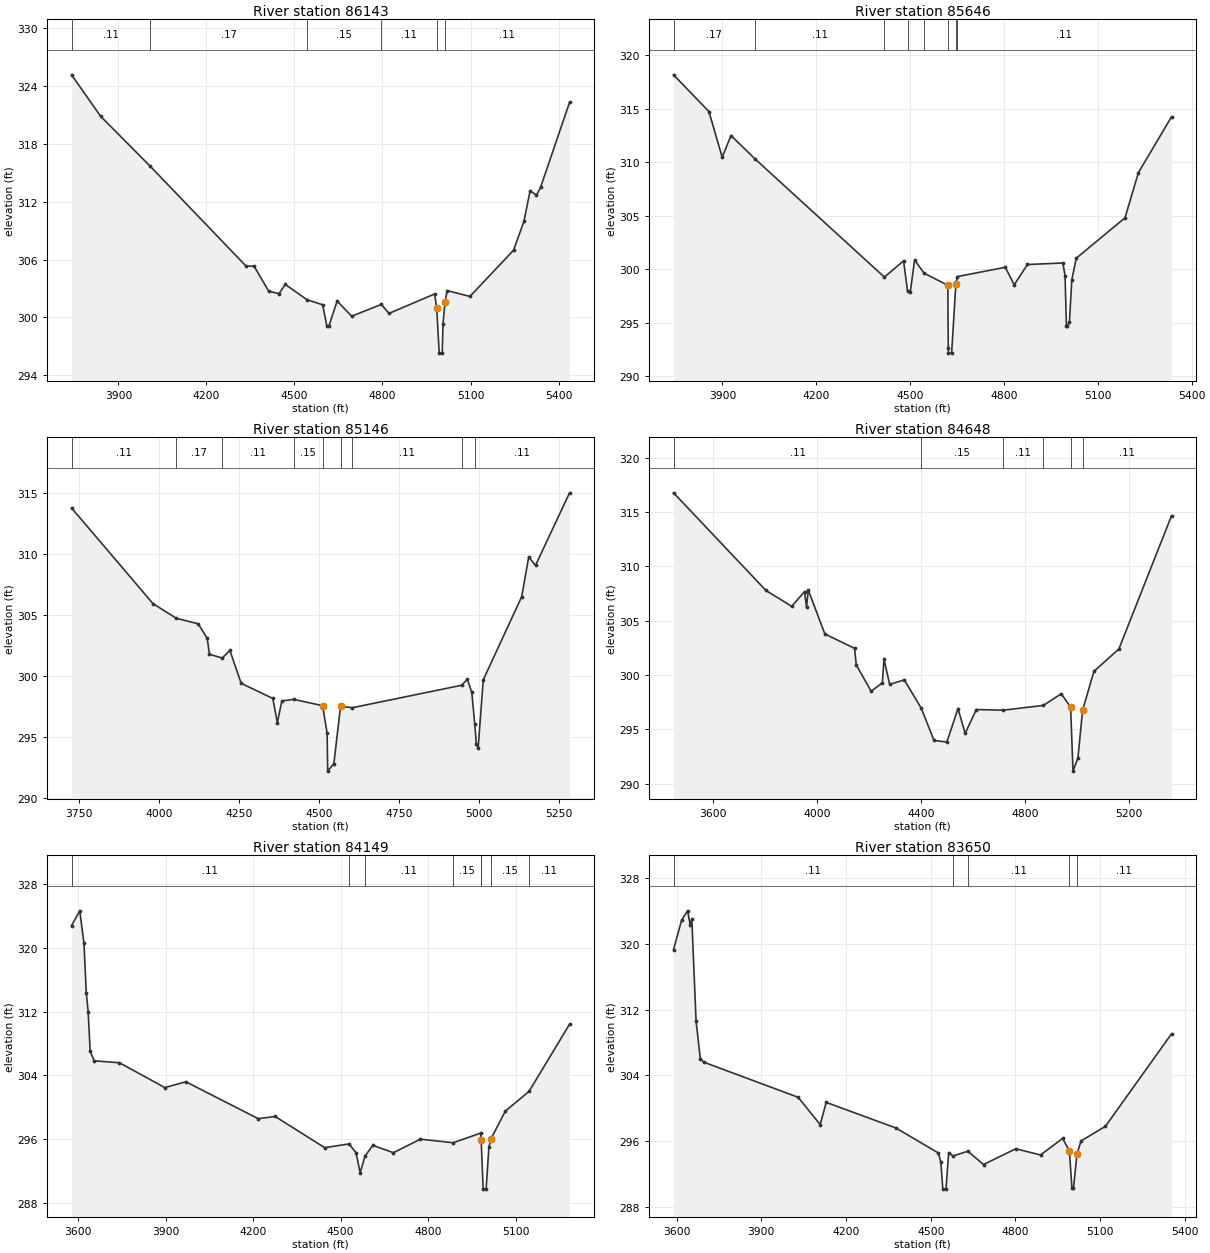
Type RM Length L Ch R = 1 ,86143   ,497,497,497
BEGIN DESCRIPTION:
LITTLE CANEY CREEK 115.0
END DESCRIPTION:
XS GIS Cut Line= 3
      3691967.89      10157261.1      3691070.59     10156376.96
      3690767.88      10156061.1
#Sta/Elev= 30
  3740.3  325.17  3839.3  320.87  4008.9  315.67  4334.3  305.35  4362.6  305.31
  4412.2  302.72  4447.5  302.47  4468.7  303.43  4542.7  301.84    4596  301.32
  4610.2  299.13  4617.2  299.11  4645.5  301.71    4695  300.13  4795.9  301.35
  4822.2  300.42  4977.8  302.44  4984.9  300.93  4993.3   296.3  5003.5   296.3
  5006.2  299.36  5013.1  301.57  5020.4  302.79    5098  302.18  5246.5  306.97
    5282  309.96  5303.1  313.15  5324.5  312.68  5338.6  313.49  5437.5  322.31
#Mann= 6 ,-1 , 0
  3740.3     .11       0  4008.9     .17       0  4542.7     .15       0
  4795.9     .11       0  4984.9     .07       0  5013.1     .11       0
Bank Sta=4984.9,5013.1
XS Rating Curve= 0 ,0
Exp/Cntr=0.3,0.1

Type RM Length L Ch R = 1 ,85646   ,500,500,500
BEGIN DESCRIPTION:
LITTLE CANEY CREEK 114.0
END DESCRIPTION:
XS GIS Cut Line= 3
      3692267.87     10156911.09      3691386.68     10156015.52
      3691167.85     10155761.07
#Sta/Elev= 30
  3743.6  318.15  3856.7  314.72  3899.1  310.46  3927.4  312.48  4002.8  310.33
  4417.7  299.25    4479  300.77  4491.9  297.91  4500.3  297.83  4514.4  300.86
  4544.3  299.62  4620.5  298.49  4621.9  292.65  4622.4  292.15  4632.6  292.15
  4646.2298.6042  4650.8   299.3  4804.3  300.17  4832.6  298.53    4875  300.43
  4988.2  300.57  4995.2   299.4  4999.6  294.67  5002.9  294.67  5009.2  295.03
  5016.8  298.99  5031.1  301.02  5186.9  304.79  5229.7  309.01  5335.6  314.23
#Mann= 8 ,-1 , 0
  3743.6     .17       0  4002.8     .11       0  4417.7     .15       0
  4491.9     .11       0  4544.3     .15       0  4620.5     .07       0
  4646.2     .15       0  4650.8     .11       0
Bank Sta=4620.5,4646.2
XS Rating Curve= 0 ,0
Exp/Cntr=0.3,0.1

Type RM Length L Ch R = 1 ,85146   ,498,498,498
BEGIN DESCRIPTION:
LITTLE CANEY CREEK 113.0
END DESCRIPTION:
XS GIS Cut Line= 3
      3692517.88      10156561.1      3691640.27     10155637.72
      3691417.88      10155461.1
#Sta/Elev= 30
  3726.1  313.77  3980.8  305.94  4053.9  304.74  4122.3  304.29  4150.6  303.09
  4157.5  301.79  4197.5  301.49  4221.4  302.11  4256.6  299.42  4355.7  298.18
  4369.9   296.2    4384  297.98  4421.6   298.1  4511.4  297.59  4525.6  295.34
  4527.4  292.23  4546.6  292.84  4567.7  297.54  4604.4  297.42  4946.6  299.26
  4964.1  299.75  4978.2  298.68  4987.4   296.1  4992.4  294.46  4998.1  294.14
  5014.1  299.71  5134.2   306.5  5156.3  309.76  5177.5  309.07    5284  315.01
#Mann= 9 ,-1 , 0
  3726.1     .11       0  4053.9     .17       0  4197.5     .11       0
  4421.6     .15       0  4511.4     .07       0  4567.7     .15       0
  4604.4     .11       0  4946.6     .15       0  4987.4     .11       0
Bank Sta=4511.4,4567.7
XS Rating Curve= 0 ,0
Exp/Cntr=0.3,0.1

Type RM Length L Ch R = 1 ,84648   ,499,499,499
BEGIN DESCRIPTION:
LITTLE CANEY CREEK 112.0
END DESCRIPTION:
XS GIS Cut Line= 3
      3692967.83     10156461.04       3691958.3     10155284.61
      3691617.82     10155161.06
#Sta/Elev= 30
  3449.8  316.78  3804.8  307.79  3903.6  306.33    3953  307.69  3960.6  306.24
  3967.2  307.83  4030.9  303.79    4145  302.46  4151.6  300.93  4208.7  298.52
  4251.5  299.28    4258  301.45  4279.9  299.15    4336  299.56  4401.6  296.93
  4450.1  293.98  4499.5  293.84  4542.3  296.92  4569.8  294.63  4612.5  296.83
  4715.6  296.77  4869.9  297.21  4938.8  298.28  4974.7  297.05  4983.9  291.16
  5002.9  292.39  5020.7  296.76  5064.3  300.35    5160   302.4  5362.2  314.67
#Mann= 6 ,-1 , 0
  3449.8     .11       0  4401.6     .15       0  4715.6     .11       0
  4869.9     .15       0  4974.7     .09       0  5020.7     .11       0
Bank Sta=4974.7,5020.7
XS Rating Curve= 0 ,0
Exp/Cntr=0.3,0.1

Type RM Length L Ch R = 1 ,84149   ,499,499,499
BEGIN DESCRIPTION:
LITTLE CANEY CREEK 111.0
END DESCRIPTION:
XS GIS Cut Line= 3
      3693367.88      10155861.1       3692253.4      10154977.6
      3692067.88     10154761.11
#Sta/Elev= 30
  3577.8  322.83  3605.9  324.68  3620.3   320.6  3628.3  314.36  3634.7     312
  3641.6  307.02  3655.5  305.83  3742.1  305.59  3897.5  302.47  3969.6   303.2
    4218  298.56  4275.7  298.84  4445.6  294.92  4529.1  295.39  4552.9  294.29
  4567.3  291.76  4583.8  293.86  4610.6  295.21  4681.1  294.29    4774  295.99
    4886  295.54  4980.8  296.75 4982.01295.8839  4988.9  289.71  4999.1  289.71
  5008.6     295  5015.7  296.04  5065.1  299.52  5146.2  301.99  5285.1  310.43
#Mann= 8 ,-1 , 0
  3577.8     .11       0  4529.1     .15       0  4583.8     .11       0
    4886     .15       0  4980.8     .12       0 4982.01     .09       0
  5015.7     .15       0  5146.2     .11       0
Bank Sta=4982.01,5015.7
XS Rating Curve= 0 ,0
Exp/Cntr=0.3,0.1

Type RM Length L Ch R = 1 ,83650   ,495,495,495
BEGIN DESCRIPTION:
LITTLE CANEY CREEK 110.0
END DESCRIPTION:
XS GIS Cut Line= 3
      3693417.87     10155861.11       3692641.3     10154683.51
      3692367.85     10154461.07
#Sta/Elev= 30
  3589.4  319.32    3618   322.9  3639.1  324.04  3648.2  322.37  3654.2     323
  3669.2  310.61  3684.3  306.02  3697.2  305.59  4030.6  301.32  4108.8  297.99
  4129.9   300.7  4376.8  297.58  4527.3  294.53  4535.8  293.39  4542.8  290.13
    4554  290.13  4563.5  294.56  4579.2  294.17  4631.3  294.75  4686.9  293.13
  4801.3  295.05  4888.7  294.29    4967  296.31  4990.9  294.79    5000  290.24
  5005.4  290.24  5017.8  294.42  5032.2     296  5118.4  297.78  5352.5  309.05
#Mann= 5 ,-1 , 0
  3589.4     .11       0  4579.2     .15       0  4631.3     .11       0
  4990.9     .06       0  5017.8     .11       0
Bank Sta=4990.9,5017.8
XS Rating Curve= 0 ,0
Exp/Cntr=0.3,0.1

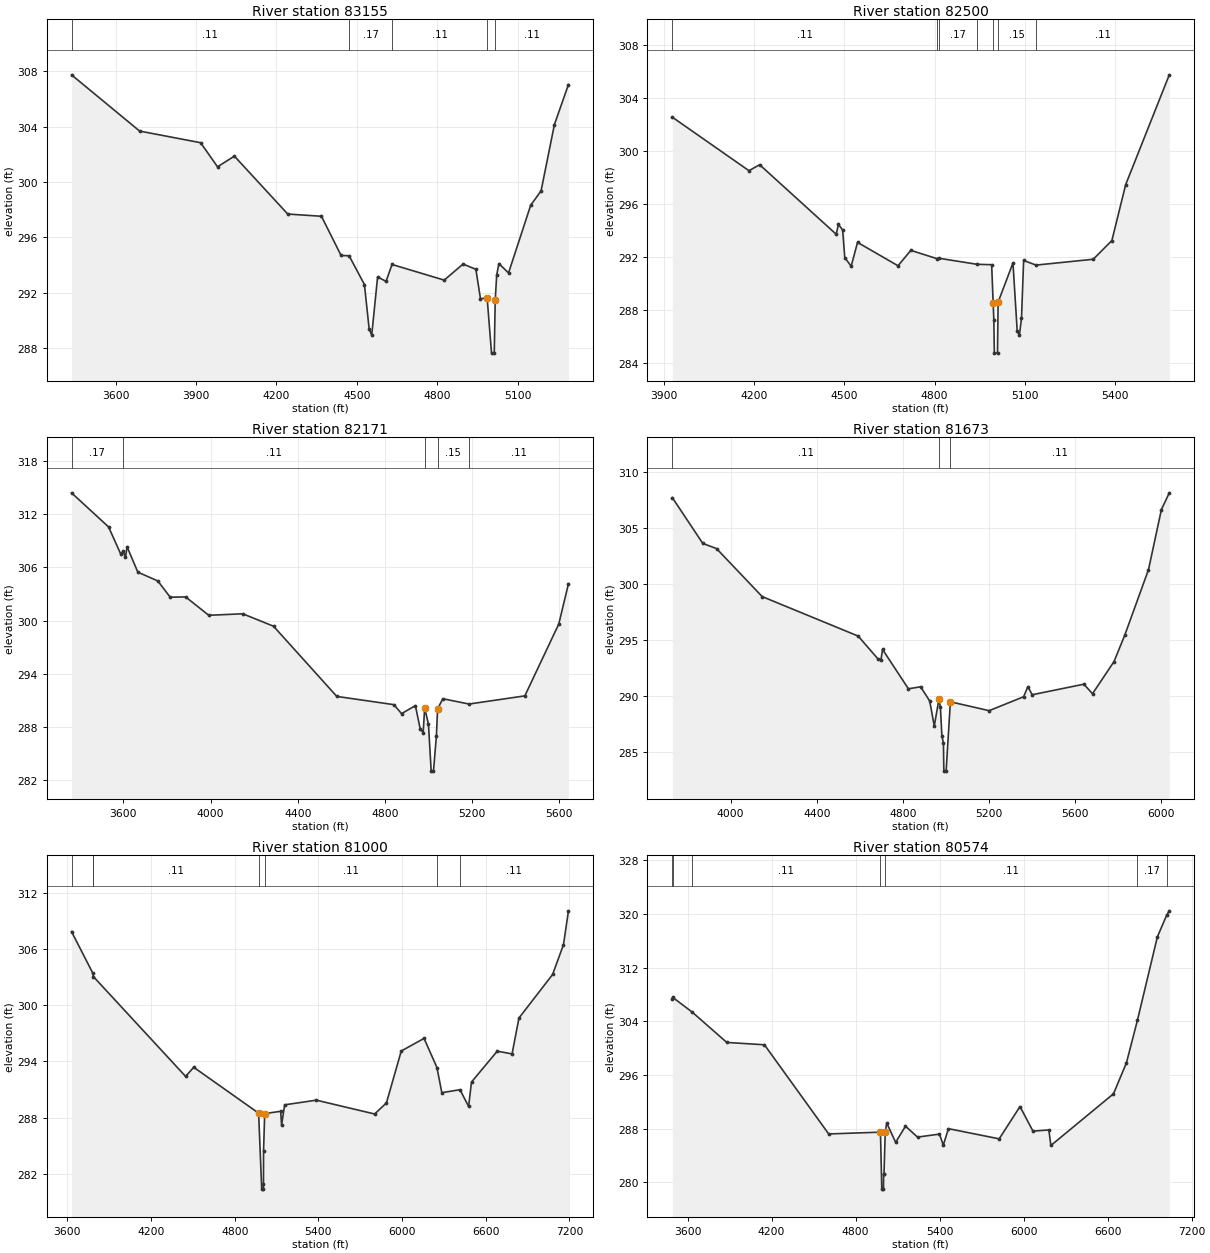
Type RM Length L Ch R = 1 ,83155   ,655,655,655
BEGIN DESCRIPTION:
LITTLE CANEY CREEK 109.0
END DESCRIPTION:
XS GIS Cut Line= 3
      3693467.84     10155861.03      3693001.68     10154367.69
      3692867.86     10154111.09
#Sta/Elev= 30
  3435.6  307.74  3689.7  303.68  3917.2  302.84  3980.3   301.1  4043.2  301.87
  4242.2  297.69  4367.9  297.53  4441.2   294.7  4471.1  294.68  4528.3   292.6
    4546  289.38  4555.5  288.95  4577.4  293.15  4608.9  292.83  4631.2  294.05
  4825.9  292.92  4896.2  294.08  4944.1   293.7  4961.2  291.57    4986  291.65
  5002.4  287.65  5012.6  287.65  5016.1  291.46  5021.7  293.29    5030  294.11
  5065.9  293.44  5148.6  298.33  5187.2  299.36    5237  304.15  5289.4  307.04
#Mann= 5 ,-1 , 0
  3435.6     .11       0  4471.1     .17       0  4631.2     .11       0
    4986     .06       0  5016.1     .11       0
Bank Sta=4986,5016.1
XS Rating Curve= 0 ,0
Exp/Cntr=0.3,0.1

Type RM Length L Ch R = 1 ,82500   ,329,329,329
BEGIN DESCRIPTION:
LITTLE CANEY CREEK 108.0
END DESCRIPTION:
XS GIS Cut Line= 3
      3694267.83     10155011.04      3693417.88      10154136.2
      3693011.34     10153993.48
#Sta/Elev= 30
  3928.9  302.53  4183.4   298.5  4218.9  298.95  4473.3  293.71  4480.5  294.46
  4494.6  294.03  4501.6  291.96  4522.9   291.3    4544   293.1  4678.5  291.34
    4721   292.5  4807.1  291.88    4813  291.91  4941.1  291.45  4989.5  291.42
 4994.47288.5622  4996.7  287.28  4998.4  284.76  5008.9  284.76  5010.9   288.6
  5060.3  291.55  5074.4  286.41  5081.6  286.12  5088.6  287.37  5095.7  291.74
  5136.8  291.39  5326.9  291.83  5388.8  293.24  5434.8  297.46  5579.5  305.72
#Mann= 7 ,-1 , 0
  3928.9     .11       0  4807.1     .15       0    4813     .17       0
  4941.1     .15       0 4994.47     .09       0  5010.9     .15       0
  5136.8     .11       0
Bank Sta=4994.47,5010.9
XS Rating Curve= 0 ,0
Exp/Cntr=0.3,0.1

Type RM Length L Ch R = 1 ,82171   ,498,498,498
BEGIN DESCRIPTION:
LITTLE CANEY CREEK 107.0
END DESCRIPTION:
XS GIS Cut Line= 3
      3694967.87     10155161.09      3693763.66     10154050.87
      3693167.81     10153811.05
#Sta/Elev= 30
  3362.1  314.39    3532  310.55  3588.7  307.45    3599  307.83  3609.7  307.12
    3617  308.32  3666.4  305.45  3758.2  304.46  3814.9  302.63  3885.8  302.66
  3991.9  300.59  4147.8  300.76    4289  299.36  4579.3  291.45  4841.3  290.52
  4876.5  289.51    4940  290.41  4961.6  287.83  4975.7  287.37  4982.5  290.17
    5000  288.29  5012.4  283.03  5022.9  283.03  5036.4     287  5041.8  290.05
    5066  291.19  5186.1  290.59  5442.1  291.51  5597.9  299.61  5642.3  304.15
#Mann= 5 ,-1 , 0
  3362.1     .17       0    3599     .11       0  4982.5     .09       0
  5041.8     .15       0  5186.1     .11       0
Bank Sta=4982.5,5041.8
XS Rating Curve= 0 ,0
Exp/Cntr=0.3,0.1

Type RM Length L Ch R = 1 ,81673   ,673,673,673
BEGIN DESCRIPTION:
LITTLE CANEY CREEK 106.0
END DESCRIPTION:
XS GIS Cut Line= 3
      3695067.84     10154661.06      3694148.19      10153783.9
      3693111.29     10153784.64
#Sta/Elev= 30
  3729.1   307.7  3870.5  303.62  3934.3  303.16  4146.3  298.88    4592  295.36
  4683.8  293.33    4698  293.25  4705.2  294.17  4825.4  290.66    4882  290.84
  4924.4  289.57  4945.5  287.34  4966.9  289.71  4973.8  289.07    4981  286.42
    4988  285.85    4990  283.32  5000.5  283.32  5020.3   289.5  5200.3  288.71
  5360.3  289.95  5380.3  290.85  5400.3  290.13  5640.3  291.07  5680.3  290.22
  5780.3  293.09  5830.3  295.45  5940.3  301.28  6000.3  306.64  6036.9  308.13
#Mann= 3 , 0 , 0
  3729.1     .11       0  4966.9     .06       0  5020.3     .11       0
Bank Sta=4966.9,5020.3
XS Rating Curve= 0 ,0
Exp/Cntr=0.3,0.1

Type RM Length L Ch R = 1 ,81000   ,426,426,426
BEGIN DESCRIPTION:
LITTLE CANEY CREEK 105.0
END DESCRIPTION:
XS GIS Cut Line= 3
      3695284.19     10154471.26      3694518.57      10153236.9
      3692917.82     10151861.04
#Sta/Elev= 30
  3629.8   307.9  3780.8   303.5  3787.4  303.07    4448   292.4  4505.9  293.38
  4971.5  288.47  4993.6  280.34  5005.7  280.34  5006.2  280.84  5006.8  284.42
    5015  288.42  5129.5  288.67  5136.1  287.19    5158  289.36  5385.2  289.86
  5803.3  288.38  5887.8  289.56  5994.2  295.12  6157.7  296.47  6250.4  293.34
    6285  290.66  6415.2  290.98    6477  289.19  6497.9   291.8  6682.3   295.1
  6788.7  294.81  6838.1  298.65  7079.5  303.31  7157.4   306.5  7193.1  310.12
#Mann= 7 ,-1 , 0
  3629.8     .11       0  3780.8     .17       0  3787.4     .11       0
  4971.5     .06       0    5015     .11       0  6250.4     .17       0
  6415.2     .11       0
Bank Sta=4971.5,5015
XS Rating Curve= 0 ,0
Exp/Cntr=0.3,0.1

Type RM Length L Ch R = 1 ,80574   ,497,497,497
BEGIN DESCRIPTION:
LITTLE CANEY CREEK 104.0
END DESCRIPTION:
XS GIS Cut Line= 3
      3695695.66     10154377.53       3694909.1      10153090.2
      3693617.88     10151511.11
#Sta/Elev= 30
  3491.4  307.36  3493.7  307.58  3632.9  305.38  3880.1  300.85  4149.1   300.5
  4607.8   287.2  4977.5  287.47  4986.9  278.97    4999  278.97    5000  281.25
  5002.7  281.25 5011.52287.4509    5022  288.84  5085.8  285.95  5156.2  288.36
  5242.3  286.73  5398.8  287.18  5426.1  285.52  5462.7  287.99  5825.2  286.47
  5973.8  291.29  6066.4  287.62  6179.9   287.8  6194.2  285.48  6641.4  293.19
    6734  297.82  6812.1  304.14  6954.4  316.57  7021.3  319.85  7039.8  320.48
#Mann= 7 ,-1 , 0
  3491.4     .11       0  3493.7     .17       0  3632.9     .11       0
  4977.5     .06       0 5011.52     .11       0  6812.1     .17       0
  7021.3     .11       0
Bank Sta=4977.5,5011.52
XS Rating Curve= 0 ,0
Exp/Cntr=0.3,0.1

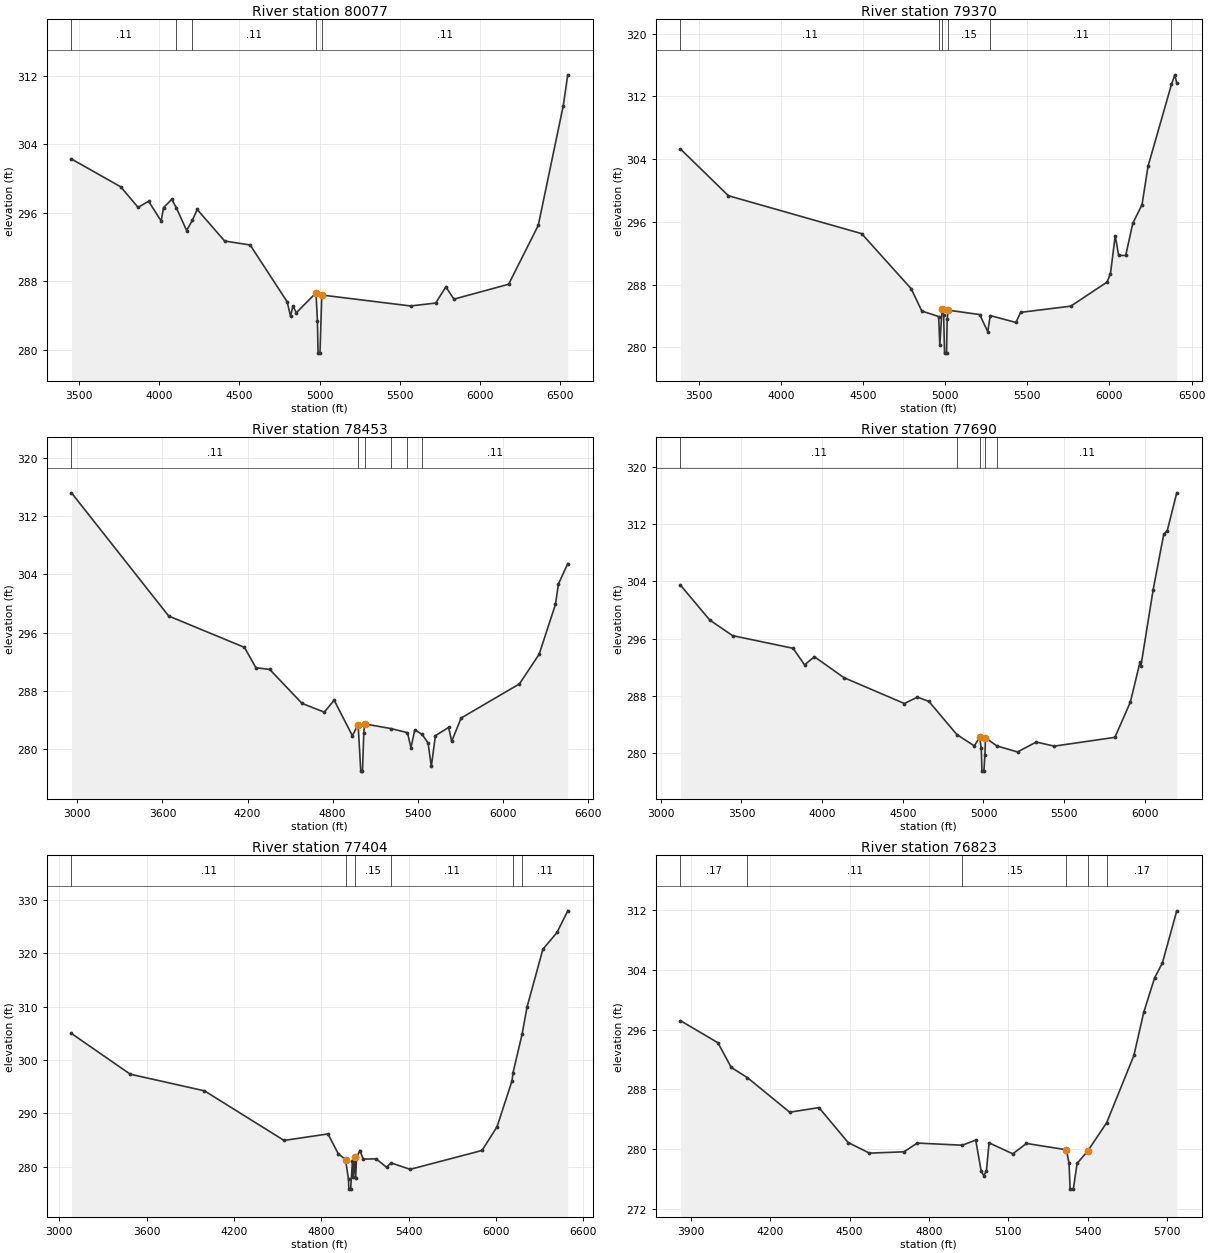
Type RM Length L Ch R = 1 ,80077   ,707,707,707
BEGIN DESCRIPTION:
LITTLE CANEY CREEK 103.0
END DESCRIPTION:
XS GIS Cut Line= 3
      3696034.22      10153971.3      3695168.86     10152690.06
      3694167.86     10151511.09
#Sta/Elev= 30
  3453.9   302.3    3761  299.04  3868.9  296.64  3934.8  297.35  4012.8  295.03
  4027.7  296.61  4078.7  297.58    4108  296.57  4171.6  293.93  4206.9  295.12
  4237.5  296.39  4408.4   292.7  4567.2  292.24    4798  285.59    4819  283.91
    4834  285.11    4855   284.3  4977.8  286.64  4986.7  283.36  4990.4  279.58
  5002.5  279.58  5013.8  286.38  5567.4   285.1  5723.4  285.44  5787.1  287.33
  5837.6   285.9  6178.1  287.64  6362.7  294.52  6518.6  308.53  6546.6  312.15
#Mann= 5 ,-1 , 0
  3453.9     .11       0    4108     .17       0  4206.9     .11       0
  4977.8     .06       0  5013.8     .11       0
Bank Sta=4977.8,5013.8
XS Rating Curve= 0 ,0
Exp/Cntr=0.3,0.1

Type RM Length L Ch R = 1 ,79370   ,917,917,917
BEGIN DESCRIPTION:
LITTLE CANEY CREEK 102.0
END DESCRIPTION:
XS GIS Cut Line= 3
      3696409.22     10153830.69      3695586.28     10152434.81
      3694706.06     10151346.26
#Sta/Elev= 30
  3389.1  305.29    3681  299.33  4491.5   294.5  4793.3  287.47  4857.9  284.63
  4960.2  283.93  4967.4  280.28  4980.8  284.93  4990.6  284.16  4996.2  279.26
  5008.3  279.26  5012.2  283.55  5017.8  284.74  5209.7  284.18  5259.3     282
  5274.2  284.05  5430.4  283.17  5459.1  284.46  5764.5  285.25  5985.2  288.32
    6006   289.4  6034.8  294.23    6056  291.73  6098.7  291.71  6141.9  295.82
  6197.9  298.18  6234.6  303.09  6377.1  313.52  6397.7  314.75  6409.4  313.69
#Mann= 6 ,-1 , 0
  3389.1     .11       0  4960.2     .15       0  4980.8     .09       0
  5017.8     .15       0  5274.2     .11       0  6377.1     .17       0
Bank Sta=4980.8,5017.8
XS Rating Curve= 0 ,0
Exp/Cntr=0.3,0.1

Type RM Length L Ch R = 1 ,78453   ,763,763,763
BEGIN DESCRIPTION:
LITTLE CANEY CREEK 101.0
END DESCRIPTION:
XS GIS Cut Line= 3
      3696648.78     10154065.03      3696138.36     10152091.06
      3695346.71     10150861.93
#Sta/Elev= 30
  2958.1   315.2  3643.9  298.29    4178  293.99  4259.2  291.19  4356.6  290.96
  4584.3   286.3  4741.6  285.09  4811.1  286.74  4939.6  281.87  4980.3  283.37
    4999     277  5011.1     277  5020.2  282.28  5026.2  283.48  5209.9  282.85
  5328.4  282.28    5353  280.21    5380  282.68  5430.9  282.05  5473.8  280.87
  5496.6  277.64  5525.3  281.87    5619     283  5640.2  281.09  5706.8  284.29
  6118.1  288.97  6257.4  293.05  6372.3  299.89  6393.4  302.69    6459  305.48
#Mann= 6 ,-1 , 0
  2958.1     .11       0  4980.3     .06       0  5026.2     .11       0
  5209.9     .11       0  5328.4     .17       0  5430.9     .11       0
Bank Sta=4980.3,5026.2
XS Rating Curve= 0 ,0
Exp/Cntr=0.3,0.1

Type RM Length L Ch R = 1 ,77690   ,286,286,286
BEGIN DESCRIPTION:
LITTLE CANEY CREEK 100.0
END DESCRIPTION:
XS GIS Cut Line= 3
       3696784.2     10153549.41       3696471.7     10151684.81
      3695904.77     10150644.58
#Sta/Elev= 30
  3122.3  303.49  3303.1  298.63  3445.1  296.44  3820.2  294.67  3891.2  292.36
  3952.1   293.5  4134.6  290.58  4509.7  286.96  4590.8  287.86  4661.8  287.25
  4834.8  282.63    4943  281.05  4976.1  282.23  4986.3  280.68  4990.4  277.52
  5002.5  277.52  5008.8  279.77  5012.3  282.16    5083  281.04  5210.8   280.2
  5327.1  281.58  5438.5  281.01  5814.4  282.24  5910.1  287.16  5969.9  292.74
  5975.6  292.22  6051.6  302.88  6117.1  310.61  6138.9  311.11  6197.6  316.38
#Mann= 5 ,-1 , 0
  3122.3     .11       0  4834.8     .15       0  4976.1     .09       0
  5012.3     .15       0    5083     .11       0
Bank Sta=4976.1,5012.3
XS Rating Curve= 0 ,0
Exp/Cntr=0.3,0.1

Type RM Length L Ch R = 1 ,77404   ,581,581,581
BEGIN DESCRIPTION:
LITTLE CANEY CREEK 99.0
END DESCRIPTION:
XS GIS Cut Line= 3
      3696956.07     10153622.27      3696740.05     10151718.89
      3696017.84     10150411.05
#Sta/Elev= 30
  3084.4  304.99  3488.2  297.36  3998.1  294.24  4544.9  284.94  4846.8  286.16
  4917.3  282.44  4967.6  281.35  4987.7  277.62  4990.3  275.81  5002.4  275.81
  5014.8  281.08  5020.5  278.03  5030.8   281.9  5036.5  277.83  5043.2  281.75
    5066  283.05  5088.9  281.44  5177.5  281.49  5248.8  279.92  5279.9  280.73
  5411.2  279.52    5905  283.06  6008.2   287.5  6111.3  296.13  6117.6   297.6
  6180.6  304.89  6214.4  309.96  6323.2  320.79  6420.6  323.95    6494  327.99
#Mann= 6 ,-1 , 0
  3084.4     .11       0  4967.6     .09       0  5030.8     .15       0
  5279.9     .11       0  6117.6     .17       0  6180.6     .11       0
Bank Sta=4967.6,5030.8
XS Rating Curve= 0 ,0
Exp/Cntr=0.3,0.1

Type RM Length L Ch R = 1 ,76823   ,417,417,417
BEGIN DESCRIPTION:
LITTLE CANEY CREEK 98.0
END DESCRIPTION:
XS GIS Cut Line= 3
      3697315.45     10152611.93      3697195.65      10151486.9
      3697294.62     10150747.28
#Sta/Elev= 30
    3860   297.2  4001.7  294.24  4051.9  290.93  4112.8  289.57  4273.2  284.92
  4383.8  285.54  4494.4  280.85  4574.9  279.43  4705.6  279.61  4755.9  280.78
  4926.5  280.49  4977.1  281.19  4997.3  277.09  5007.4  276.39  5017.4  277.05
  5027.5  280.81  5117.2  279.34  5168.8  280.73  5320.1  279.88  5330.2  278.04
  5334.2   274.6  5346.3   274.6  5360.5  278.05  5400.8  279.71  5472.5  283.52
  5575.4  292.53  5612.7  298.32  5653.5  302.91  5683.3  304.95  5737.6  311.94
#Mann= 6 ,-1 , 0
    3860     .17       0  4112.8     .11       0  4926.5     .15       0
  5320.1     .09       0  5400.8     .11       0  5472.5     .17       0
Bank Sta=5320.1,5400.8
XS Rating Curve= 0 ,0
Exp/Cntr=0.3,0.1