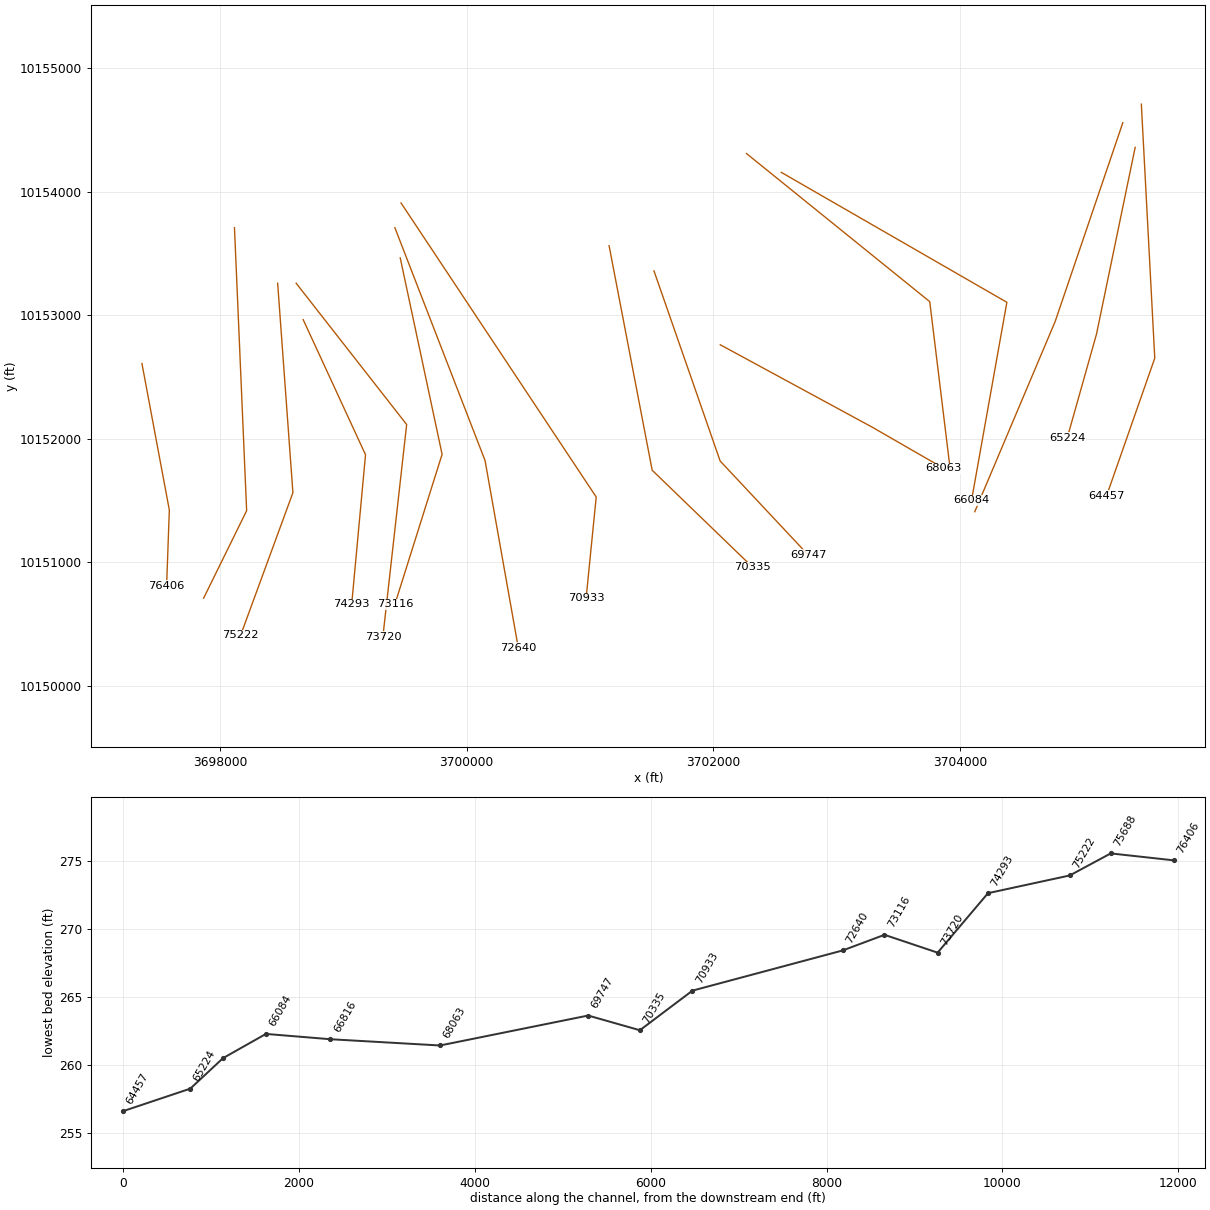
HEC-RAS study LITTLE CANEY CREEK.prj: LITTLE CANEY CREEK Base Level Engineering

--- LITTLE CANEY CREEK.g01 (geometry) --- (continued)

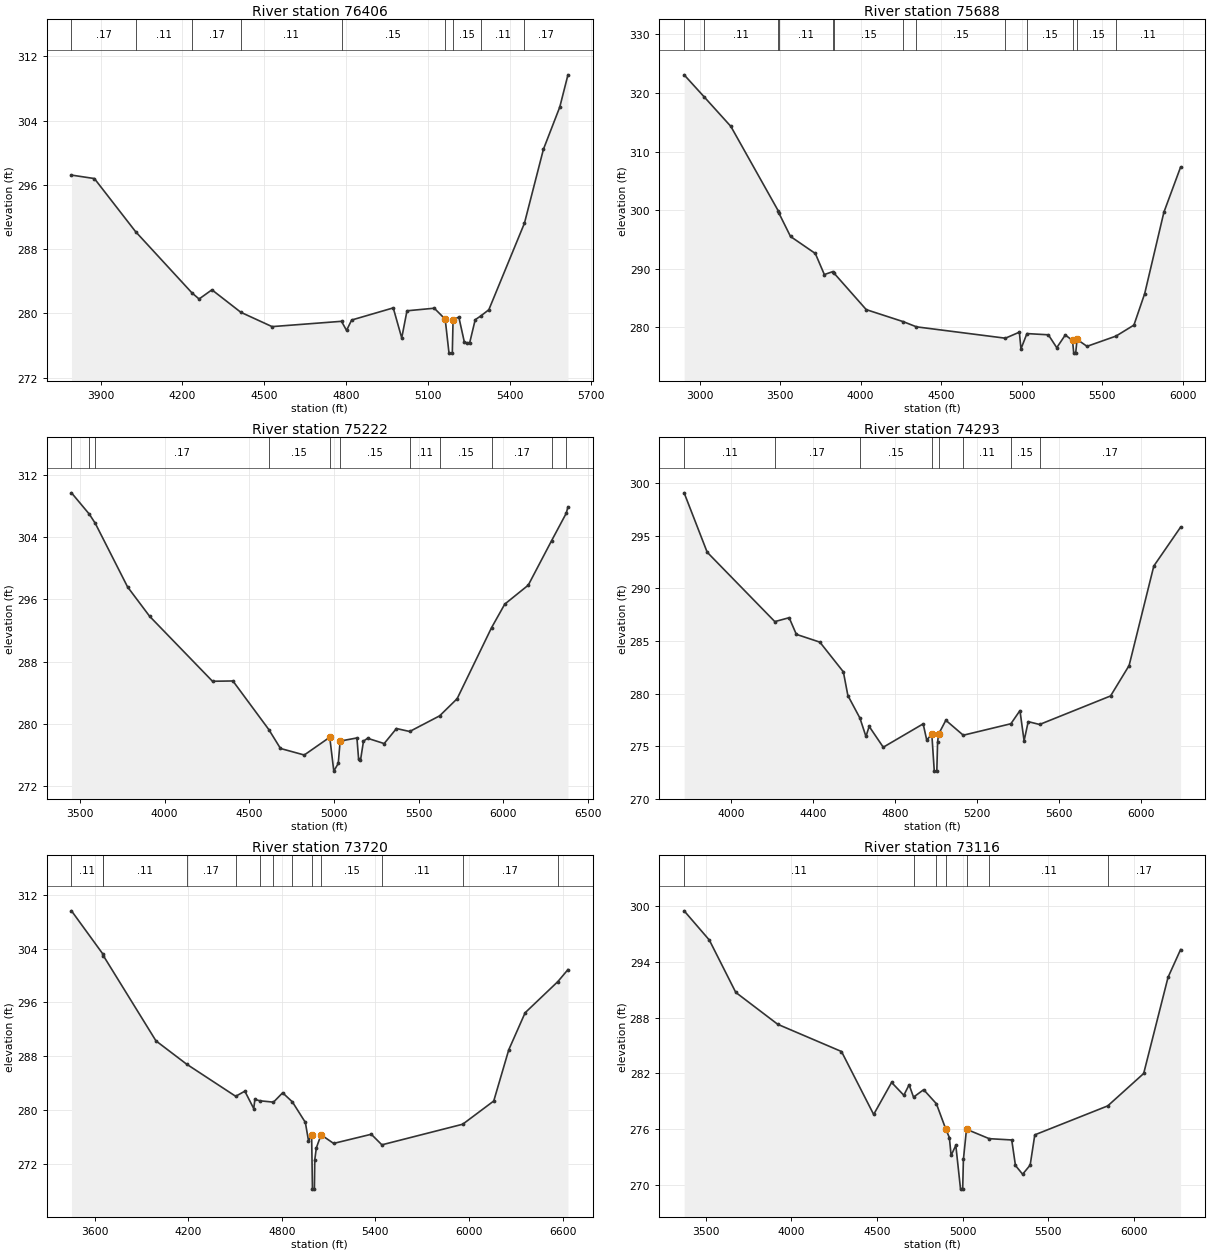
Type RM Length L Ch R = 1 ,76406   ,718,718,718
BEGIN DESCRIPTION:
LITTLE CANEY CREEK 97.0
END DESCRIPTION:
XS GIS Cut Line= 3
      3697367.85      10152611.1      3697589.91     10151424.81
      3697567.85      10150811.1
#Sta/Elev= 30
  3793.1  297.21  3877.1  296.78    4028  290.18  4235.2  282.54  4261.1  281.79
  4308.2  282.93  4414.4  280.13  4528.8  278.35  4783.5  279.01    4802  277.88
  4820.7  279.17  4973.3  280.68  5004.4  276.94  5023.7  280.32  5123.8  280.64
  5163.8  279.28  5177.8  275.05  5189.9  275.05  5192.7   279.2  5213.9  279.53
  5233.9  276.45  5243.9  276.32  5253.9  276.37  5273.9  279.21  5293.7  279.66
  5323.9  280.45  5454.5  291.22  5524.1  300.42  5584.1  305.68  5614.1  309.69
#Mann= 9 ,-1 , 0
  3793.1     .17       0    4028     .11       0  4235.2     .17       0
  4414.4     .11       0  4783.5     .15       0  5163.8     .09       0
  5192.7     .15       0  5293.7     .11       0  5454.5     .17       0
Bank Sta=5163.8,5192.7
XS Rating Curve= 0 ,0
Exp/Cntr=0.3,0.1

Type RM Length L Ch R = 1 ,75688   ,466,466,466
BEGIN DESCRIPTION:
LITTLE CANEY CREEK 96.0
END DESCRIPTION:
XS GIS Cut Line= 3
      3698117.85     10153711.02      3698216.49     10151419.19
      3697867.87     10150711.11
#Sta/Elev= 30
  2903.8   323.1  3028.7  319.32    3194  314.29    3488  299.88    3491  299.56
  3564.4  295.49  3718.6  292.58  3774.6  288.98  3826.6  289.48  3833.2  289.27
  4034.8  282.99  4265.3  280.93  4346.8  280.05  4898.9  278.11  4985.7  279.14
  4995.7  276.28  5032.7   278.9  5165.8  278.69  5217.9  276.49    5271  278.66
  5315.9  277.72  5323.4  275.56  5335.5  275.56    5344  277.91  5405.8  276.72
  5585.9  278.47  5697.2  280.35  5764.1  285.73  5883.2  299.62    5987  307.34
#Mann= 13 ,-1 , 0
  2903.8     .17       0  3028.7     .11       0    3488     .17       0
    3491     .11       0  3826.6     .17       0  3833.2     .15       0
  4265.3     .17       0  4346.8     .15       0  4898.9     .11       0
  5032.7     .15       0  5315.9     .06       0    5344     .15       0
  5585.9     .11       0
Bank Sta=5315.9,5344
XS Rating Curve= 0 ,0
Exp/Cntr=0.3,0.1

Type RM Length L Ch R = 1 ,75222   ,929,929,929
BEGIN DESCRIPTION:
LITTLE CANEY CREEK 95.0
END DESCRIPTION:
XS GIS Cut Line= 3
      3698467.85     10153261.11      3698591.49     10151565.02
      3698167.87     10150411.11
#Sta/Elev= 30
  3450.8  309.68  3556.4  306.93  3591.5  305.75  3781.7   297.6  3912.1  293.82
    4283  285.48  4403.4  285.52  4615.2  279.28  4684.1  276.85  4824.5  276.01
  4974.9  278.29  4998.8  273.94    5025  274.93  5036.3   277.8  5135.3   278.2
  5145.3  275.45  5156.2  275.32    5174  277.79  5198.2  278.16    5296  277.48
  5368.6  279.41  5446.6  279.03  5623.4  281.04  5726.6  283.24  5929.7  292.36
  6007.8  295.39  6146.3  297.82  6284.2  303.54  6370.6  307.06  6380.6  307.88
#Mann= 11 ,-1 , 0
  3450.8     .17       0  3556.4     .11       0  3591.5     .17       0
  4615.2     .15       0  4974.9     .09       0  5036.3     .15       0
  5446.6     .11       0  5623.4     .15       0  5929.7     .17       0
  6284.2     .11       0  6370.6     .17       0
Bank Sta=4974.9,5036.3
XS Rating Curve= 0 ,0
Exp/Cntr=0.3,0.1

Type RM Length L Ch R = 1 ,74293   ,573,573,573
BEGIN DESCRIPTION:
LITTLE CANEY CREEK 94.0
END DESCRIPTION:
XS GIS Cut Line= 3
       3698674.8      10152966.1      3699180.03     10151872.31
      3699067.85     10150661.03
#Sta/Elev= 30
  3771.6  299.07    3884  293.43  4213.9  286.84  4283.8  287.21  4318.9  285.63
  4433.6  284.89  4548.2  282.07  4570.2  279.82  4628.9  277.68  4658.4  275.93
    4674  276.89  4742.8  274.91  4937.4  277.13  4954.8  275.59  4979.6  276.16
  4991.6  272.64    5004  272.64  5007.8  275.42 5012.78276.1596    5048  277.47
    5133  276.05  5365.3  277.14  5409.5  278.39  5429.6  275.52  5449.7  277.34
  5505.2  277.07  5851.4  279.78  5941.8  282.67  6062.3  292.12  6192.9  295.81
#Mann= 8 ,-1 , 0
  3771.6     .11       0  4213.9     .17       0  4628.9     .15       0
  4979.6     .09       0 5012.78     .15       0    5133     .11       0
  5365.3     .15       0  5505.2     .17       0
Bank Sta=4979.6,5012.78
XS Rating Curve= 0 ,0
Exp/Cntr=0.3,0.1

Type RM Length L Ch R = 1 ,73720   ,604,604,604
BEGIN DESCRIPTION:
LITTLE CANEY CREEK 93.0
END DESCRIPTION:
XS GIS Cut Line= 3
      3698617.87     10153261.04      3699513.36      10152117.1
      3699320.65     10150398.33
#Sta/Elev= 30
  3451.8  309.61  3651.2  303.25  3656.2  302.94  3993.4  290.29  4189.5  286.84
  4504.3  282.06    4563  282.82  4620.1  280.23  4627.2  281.59  4660.6  281.39
  4746.6  281.19  4805.3  282.58  4867.7  281.23  4950.9  278.18    4971  275.46
  4991.1  276.26  4996.3  268.27  5008.8  268.27  5011.3  272.63  5021.3   274.4
  5051.5  276.34    5132  275.06  5373.5  276.42  5441.4  274.85  5959.4  277.91
  6158.4  281.36  6254.7  288.97  6359.6  294.47  6569.4   299.1  6634.1  300.88
#Mann= 13 ,-1 , 0
  3451.8     .11       0  3651.2     .17       0  3656.2     .11       0
  4189.5     .17       0  4504.3     .11       0  4660.6     .15       0
  4746.6     .11       0  4867.7     .15       0  4991.1     .09       0
  5051.5     .15       0  5441.4     .11       0  5959.4     .17       0
  6569.4     .11       0
Bank Sta=4991.1,5051.5
XS Rating Curve= 0 ,0
Exp/Cntr=0.3,0.1

Type RM Length L Ch R = 1 ,73116   ,476,476,476
BEGIN DESCRIPTION:
LITTLE CANEY CREEK 92.0
END DESCRIPTION:
XS GIS Cut Line= 3
      3699461.28     10153466.05      3699800.59     10151875.95
      3699417.86     10150661.11
#Sta/Elev= 30
  3374.1  299.47  3521.3  296.33  3675.7  290.71  3921.1  287.28  4293.2  284.36
  4481.1   277.6  4585.8  281.04  4657.3  279.66    4688  280.79  4713.9  279.46
  4773.1  280.26  4847.5  278.75  4902.7  276.01  4923.2  275.12  4933.4   273.2
  4960.9  274.28  4988.5  269.58    5001  269.58  5005.2  272.77  5023.3  276.01
  5155.9     275  5287.5  274.86  5309.2  272.12  5351.1  271.18  5395.1  272.16
  5422.2  275.41  5848.2  278.52  6058.1     282  6200.4  292.33  6273.7  295.31
#Mann= 7 ,-1 , 0
  3374.1     .11       0  4713.9     .15       0  4847.5     .11       0
  4902.7     .09       0  5023.3     .15       0  5155.9     .11       0
  5848.2     .17       0
Bank Sta=4902.7,5023.3
XS Rating Curve= 0 ,0
Exp/Cntr=0.3,0.1

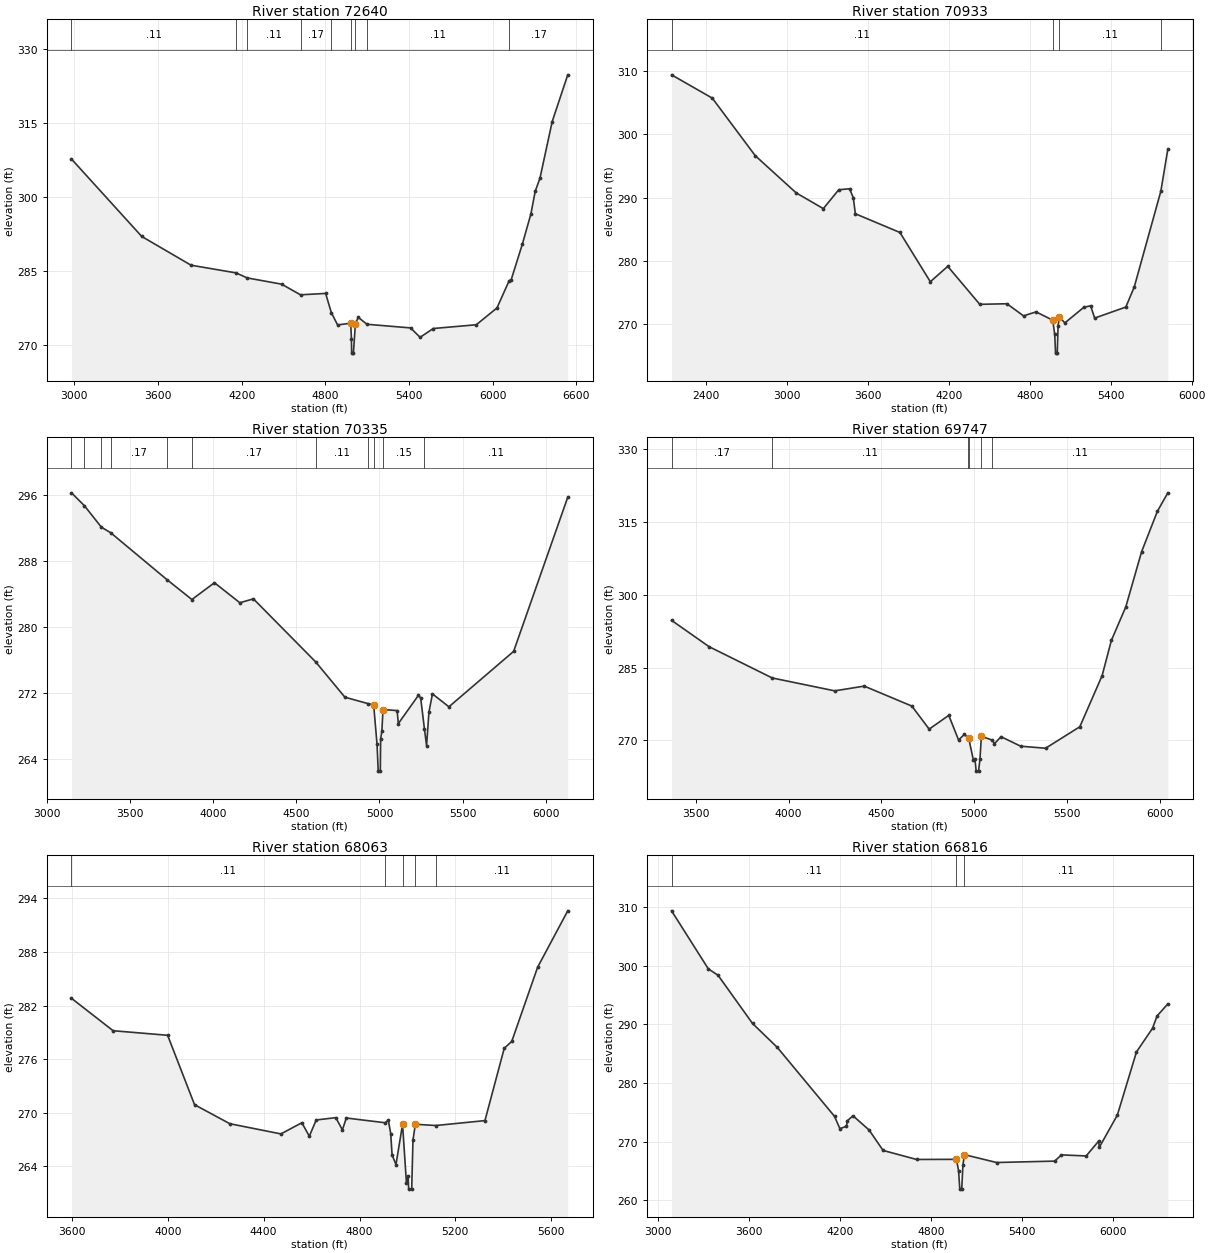
Type RM Length L Ch R = 1 ,72640   ,1707,1707,1707
BEGIN DESCRIPTION:
LITTLE CANEY CREEK 91.0
END DESCRIPTION:
XS GIS Cut Line= 3
      3699417.84     10153711.09      3700148.78     10151825.44
      3700417.84     10150311.12
#Sta/Elev= 30
    2979  307.77  3483.1  292.08    3837  286.25  4160.2  284.69  4238.7  283.68
  4486.4  282.41  4622.3  280.25  4802.3  280.53  4843.3  276.64  4888.1  274.15
  4982.1  274.49  4987.5  271.39  4989.1  268.43  5001.6  268.43    5016   274.4
  5036.3  275.69  5098.9  274.28  5412.1  273.54    5480  271.63  5574.6  273.42
  5883.2  274.18  6031.6  277.59  6119.3  283.12  6133.2  283.26  6214.4  290.58
  6275.4  296.68  6305.8  301.21  6340.4  303.92  6427.7  315.35  6539.4  324.84
#Mann= 9 ,-1 , 0
    2979     .11       0  4160.2     .17       0  4238.7     .11       0
  4622.3     .17       0  4843.3     .15       0  4982.1     .09       0
    5016     .15       0  5098.9     .11       0  6119.3     .17       0
Bank Sta=4982.1,5016
XS Rating Curve= 0 ,0
Exp/Cntr=0.3,0.1

Type RM Length L Ch R = 1 ,70933   ,598,598,598
BEGIN DESCRIPTION:
LITTLE CANEY CREEK 90.0
END DESCRIPTION:
XS GIS Cut Line= 3
      3699467.86     10153911.06      3701049.69     10151530.12
      3700967.85      10150711.1
#Sta/Elev= 30
  2141.5  309.33  2443.6  305.66  2762.4  296.59  3065.9  290.73  3267.5  288.25
  3381.7  291.22  3462.1  291.38  3489.9  289.96    3505  287.44  3835.7  284.49
  4061.2  276.73  4190.5  279.15    4428  273.17  4629.5  273.26  4752.7  271.35
  4845.9  271.98  4969.2  270.67  4984.2  268.42  4990.2  265.48  5002.7  265.48
  5009.1  269.82  5019.1  271.17  5059.3  270.24    5200   272.7  5250.3  272.94
  5280.4     271  5511.6  272.74  5574.3  275.91  5771.3  290.99  5823.1   297.6
#Mann= 4 ,-1 , 0
  2141.5     .11       0  4969.2     .06       0  5019.1     .11       0
  5771.3     .17       0
Bank Sta=4969.2,5019.1
XS Rating Curve= 0 ,0
Exp/Cntr=0.3,0.1

Type RM Length L Ch R = 1 ,70335   ,588,588,588
BEGIN DESCRIPTION:
LITTLE CANEY CREEK 89.0
END DESCRIPTION:
XS GIS Cut Line= 3
      3701153.99     10153565.01      3701503.32     10151746.87
      3702317.86     10150961.06
#Sta/Elev= 30
  3148.6  296.22    3226  294.67  3328.6  292.06  3383.4  291.41  3722.7  285.72
  3872.5  283.32    4008  285.35  4160.7  282.93  4242.2   283.4  4616.9  275.77
  4792.1  271.51    4930  270.74  4965.2  270.57  4985.5  265.79  4992.5  262.57
  5005.1  262.57  5007.2  266.49  5014.4   267.4  5021.3  270.02  5106.2  269.89
  5113.4  268.32  5233.6  271.72  5247.7  271.43  5270.1  267.71  5283.2  265.64
  5297.4  269.71  5318.5  271.91  5417.5  270.35  5806.5  277.05  6131.8  295.69
#Mann= 11 ,-1 , 0
  3148.6     .11       0    3226     .17       0  3328.6     .11       0
  3383.4     .17       0  3722.7     .11       0  3872.5     .17       0
  4616.9     .11       0    4930     .15       0  4965.2     .09       0
  5021.3     .15       0  5270.1     .11       0
Bank Sta=4965.2,5021.3
XS Rating Curve= 0 ,0
Exp/Cntr=0.3,0.1

Type RM Length L Ch R = 1 ,69747   ,1684,1684,1684
BEGIN DESCRIPTION:
LITTLE CANEY CREEK 88.0
END DESCRIPTION:
XS GIS Cut Line= 3
      3701517.84     10153361.11      3702054.34      10151821.4
      3702767.86     10151061.06
#Sta/Elev= 30
  3369.5  294.74  3571.6  289.31  3911.7  282.86  4248.5   280.2  4407.3  281.18
    4664  277.06  4757.2  272.31  4862.7  275.15  4915.6  270.07  4947.4  271.25
  4967.7   270.4  4969.5  270.56  4995.3  265.93  5003.7  266.13  5010.4  263.65
    5023  263.65  5030.9  266.09  5038.2  270.83  5097.5  270.04    5109  269.31
  5144.2  270.75  5250.2  268.79  5384.5  268.37  5568.7   272.8  5688.8  283.34
  5738.6   290.6  5816.3  297.51  5901.3  308.87  5986.3   317.2  6042.7  321.03
#Mann= 6 ,-1 , 0
  3369.5     .17       0  3911.7     .11       0  4967.7     .15       0
  4969.5     .09       0  5038.2     .15       0  5097.5     .11       0
Bank Sta=4969.5,5038.2
XS Rating Curve= 0 ,0
Exp/Cntr=0.3,0.1

Type RM Length L Ch R = 1 ,68063   ,1247,1247,1247
BEGIN DESCRIPTION:
LITTLE CANEY CREEK 87.0
END DESCRIPTION:
XS GIS Cut Line= 3
      3702055.05     10152762.93      3703287.88     10152094.89
      3703867.87     10151761.06
#Sta/Elev= 30
  3597.8  282.81  3771.6  279.18  3999.1  278.67  4111.5   270.9  4258.9  268.77
  4471.9  267.63  4559.4  268.88  4590.5  267.37  4619.3  269.19  4701.1  269.45
  4728.7  268.08  4744.8  269.41  4906.7  268.88  4920.3  269.16  4930.3  267.67
    4936  265.27  4952.2   264.2  4979.7  268.69  4995.9  262.16  5002.9  262.95
  5005.2  261.45  5017.9  261.45  5023.2  266.96  5033.3  268.71  5118.4  268.57
  5323.6  269.12  5404.1  277.21  5435.6  277.99  5543.5  286.29  5669.2   292.6
#Mann= 5 ,-1 , 0
  3597.8     .11       0  4906.7     .15       0  4979.7     .09       0
  5033.3     .15       0  5118.4     .11       0
Bank Sta=4979.7,5033.3
XS Rating Curve= 0 ,0
Exp/Cntr=0.3,0.1

Type RM Length L Ch R = 1 ,66816   ,732,732,732
BEGIN DESCRIPTION:
LITTLE CANEY CREEK 86.0
END DESCRIPTION:
XS GIS Cut Line= 3
      3702267.82      10154311.1      3703752.95      10153111.9
      3703917.85     10151761.07
#Sta/Elev= 30
  3090.3  309.38  3332.6  299.48  3396.6  298.39  3623.7  290.17  3786.8  286.09
  4164.2  274.32  4199.4  272.22  4242.5  272.63    4249  273.58  4285.7  274.42
  4391.3  272.01    4484  268.51  4704.7  266.97    4967  266.99  4981.4  265.06
  4989.4  261.91  5002.1  261.91    5010  266.02  5020.1  267.79  5231.7  266.45
  5614.5  266.69  5659.2  267.75  5822.3  267.57  5903.9  270.09  5908.9  269.06
  6027.5  274.54  6153.6  285.32  6259.3  289.35  6289.5  291.46    6360   293.5
#Mann= 3 , 0 , 0
  3090.3     .11       0    4967     .06       0  5020.1     .11       0
Bank Sta=4967,5020.1
XS Rating Curve= 0 ,0
Exp/Cntr=0.3,0.1

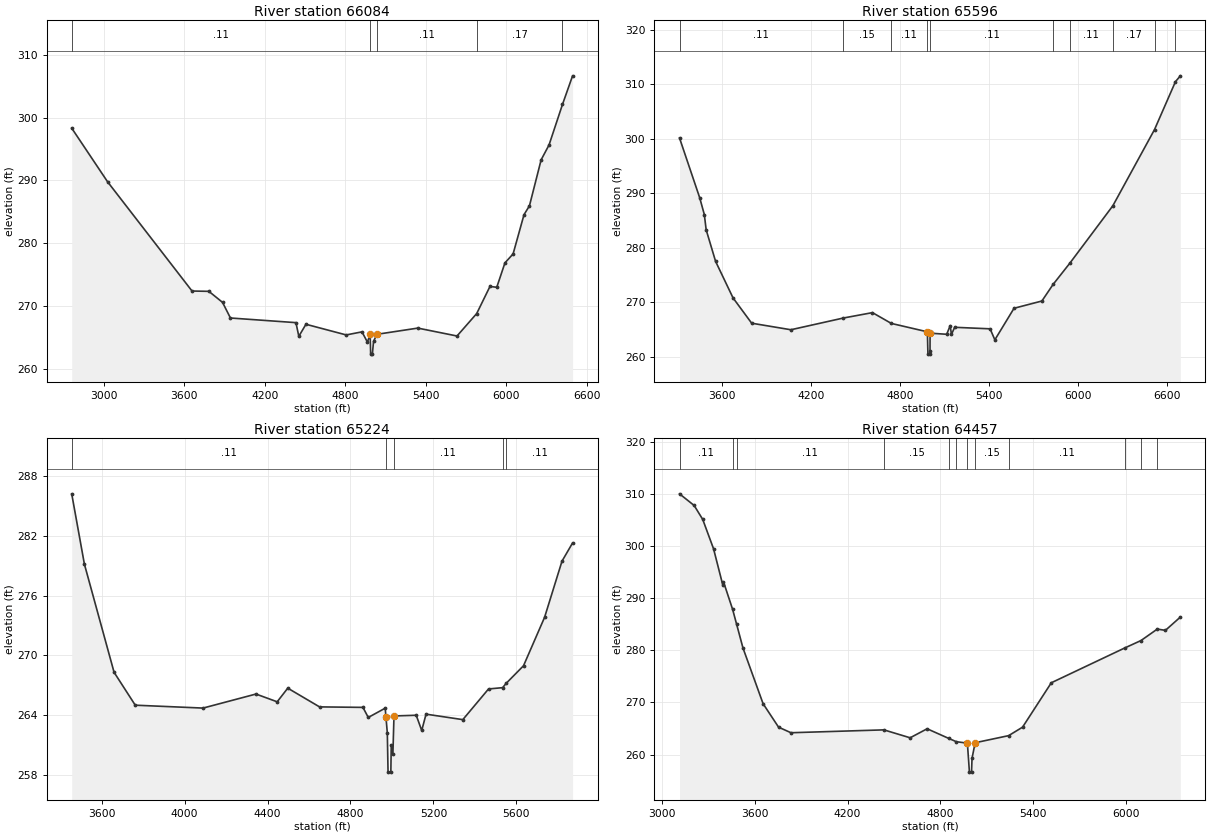
Type RM Length L Ch R = 1 ,66084   ,488,488,488
BEGIN DESCRIPTION:
LITTLE CANEY CREEK 85.0
END DESCRIPTION:
XS GIS Cut Line= 3
      3702549.81     10154158.78      3704377.95     10153106.69
       3704091.8      10151504.3
#Sta/Elev= 30
  2759.1  298.33  3026.6  289.78  3656.8  272.36  3782.5  272.31  3884.5  270.55
  3943.4  268.06  4432.1  267.32  4453.6  265.14  4506.8  267.06  4807.1  265.36
  4924.9  265.85  4965.5  264.21  4985.8  265.49  4989.6   262.3  5002.3   262.3
  5011.2  264.34  5036.6  265.46  5341.3  266.45  5633.9  265.19  5780.8  268.77
  5879.7  273.09  5930.5  272.96  5991.5  276.85  6052.4  278.28  6133.7  284.53
  6174.3  285.95  6261.6  293.28  6320.5  295.65  6420.8  302.11  6496.1  306.67
#Mann= 5 ,-1 , 0
  2759.1     .11       0  4985.8     .06       0  5036.6     .11       0
  5780.8     .17       0  6420.8     .11       0
Bank Sta=4985.8,5036.6
XS Rating Curve= 0 ,0
Exp/Cntr=0.3,0.1

Type RM Length L Ch R = 1 ,65596   ,372,372,372
BEGIN DESCRIPTION:
LITTLE CANEY CREEK 84.0
END DESCRIPTION:
XS GIS Cut Line= 3
      3705317.85     10154561.08      3704769.44     10152951.31
      3704117.86     10151411.08
#Sta/Elev= 30
  3315.7  300.16  3451.5  289.21  3482.9  286.11  3495.3  283.31  3558.7  277.53
  3676.2  270.83  3801.7  266.19  4065.8  264.99  4419.1  267.14  4615.1  268.13
  4742.2  266.15  4984.9  264.61  4988.7  260.52  5002.2  260.52  5002.7  261.02
  5003.2  264.36    5115  264.16  5138.7  265.75  5146.9  264.12  5168.6  265.44
  5407.5  265.16  5439.3  263.14  5568.6  268.93  5756.1  270.26  5831.5   273.3
  5944.5   277.2  6234.1  287.73  6514.5  301.69  6655.8  310.49  6688.7  311.55
#Mann= 10 ,-1 , 0
  3315.7     .11       0  4419.1     .15       0  4742.2     .11       0
  4984.9     .06       0  5003.2     .11       0  5831.5     .17       0
  5944.5     .11       0  6234.1     .17       0  6514.5     .11       0
  6655.8     .17       0
Bank Sta=4984.9,5003.2
XS Rating Curve= 0 ,0
Exp/Cntr=0.3,0.1

Type RM Length L Ch R = 1 ,65224   ,767,767,767
BEGIN DESCRIPTION:
LITTLE CANEY CREEK 83.0
END DESCRIPTION:
XS GIS Cut Line= 3
      3705417.86     10154361.11      3705104.43     10152849.15
      3704867.86      10152011.1
#Sta/Elev= 30
  3455.9  286.22  3517.2  279.15  3660.2   268.3  3762.3     265  4089.1  264.71
  4344.4  266.12  4446.6  265.34  4497.6  266.71  4650.8  264.83  4860.1  264.78
  4885.7  263.77  4967.4   264.7 4970.94263.8358  4977.6  262.21  4981.1  258.28
  4994.6  258.28  4996.5  260.96  5004.5   260.1  5009.7  263.92  5116.9  263.99
  5143.5  262.46  5164.3   264.1  5341.6  263.55  5465.6  266.63  5533.5  266.76
  5551.3  267.21  5634.3  268.96  5735.8  273.82  5819.8  279.46  5870.8  281.29
#Mann= 5 ,-1 , 0
  3455.9     .11       0 4970.94     .06       0  5009.7     .11       0
  5533.5     .15       0  5551.3     .11       0
Bank Sta=4970.94,5009.7
XS Rating Curve= 0 ,0
Exp/Cntr=0.3,0.1

Type RM Length L Ch R = 1 ,64457   ,432,432,432
BEGIN DESCRIPTION:
LITTLE CANEY CREEK 82.0
END DESCRIPTION:
XS GIS Cut Line= 3
      3705467.85     10154711.07      3705576.73     10152654.43
       3705186.1     10151539.82
#Sta/Elev= 30
  3112.8  310.03  3207.7  307.79    3263  305.12  3333.1  299.48  3392.4  292.58
  3397.4  293.15  3456.4  287.86  3481.7  285.07  3523.4  280.45  3653.6  269.75
  3753.7  265.25  3833.8  264.18  4435.2  264.73  4604.9  263.21    4715  264.94
  4855.6  263.08  4903.8  262.46  4975.4  262.18  4988.6  256.62  5002.2  256.62
  5005.4  259.26  5025.5  262.26    5242  263.62  5332.4  265.25  5518.4  273.77
  5992.8  280.44  6098.4  281.87    6204  284.07  6256.7  283.83  6353.4  286.38
#Mann= 12 ,-1 , 0
  3112.8     .11       0  3456.4     .15       0  3481.7     .11       0
  4435.2     .15       0  4855.6     .11       0  4903.8     .15       0
  4975.4     .09       0  5025.5     .15       0    5242     .11       0
  5992.8     .17       0  6098.4     .11       0    6204     .17       0
Bank Sta=4975.4,5025.5
XS Rating Curve= 0 ,0
Exp/Cntr=0.3,0.1