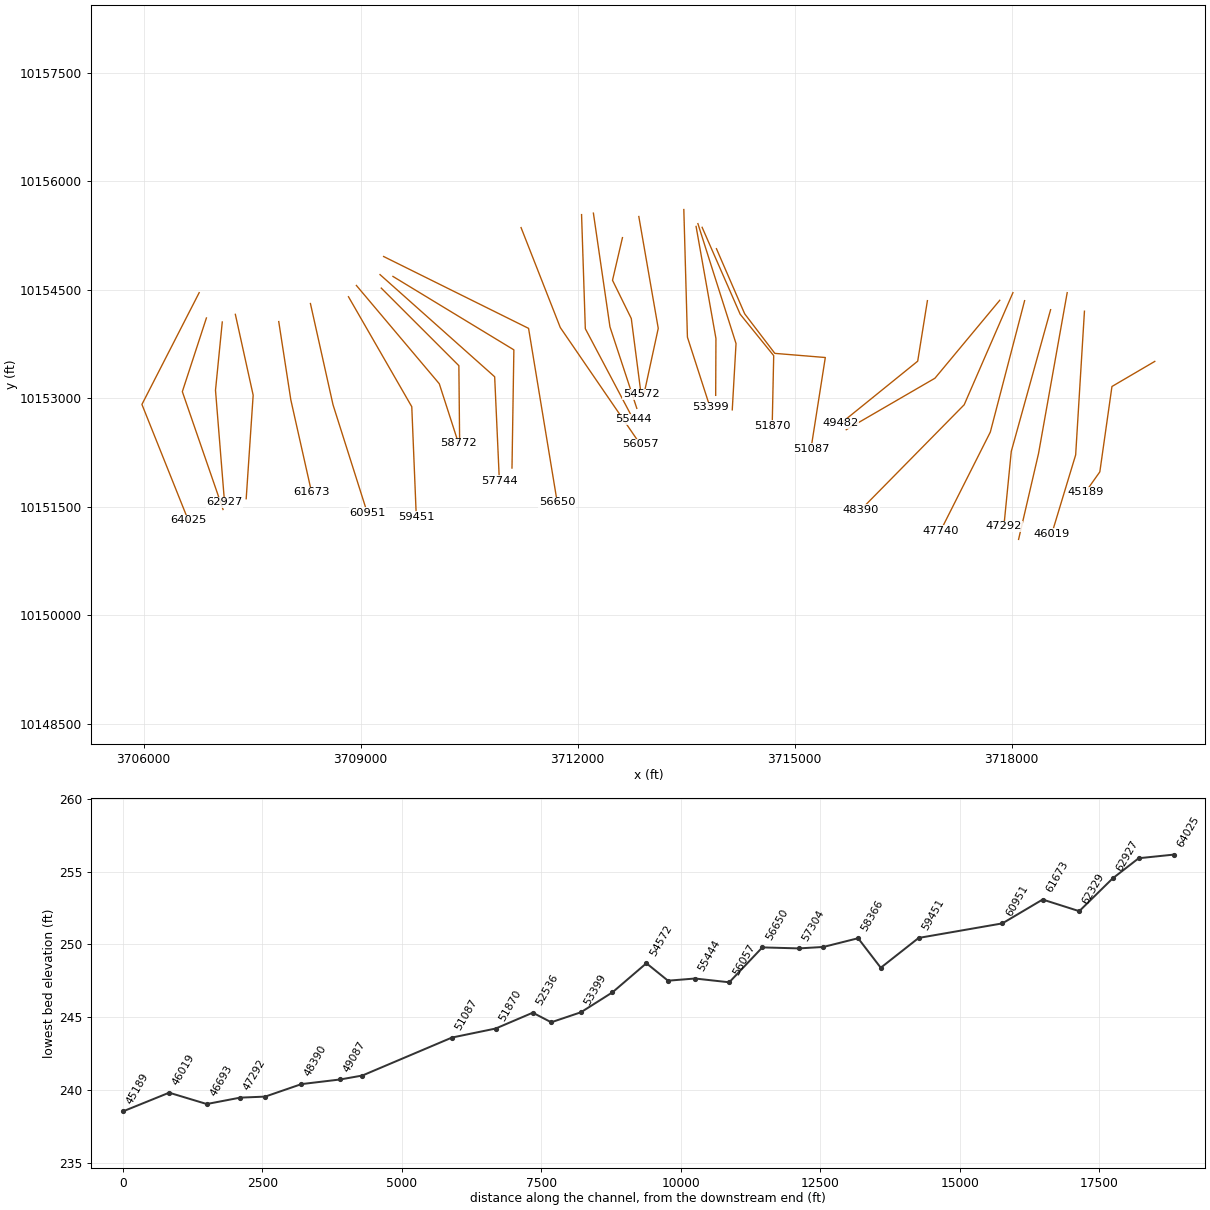
HEC-RAS study LITTLE CANEY CREEK.prj: LITTLE CANEY CREEK Base Level Engineering

--- LITTLE CANEY CREEK.g01 (geometry) --- (continued)

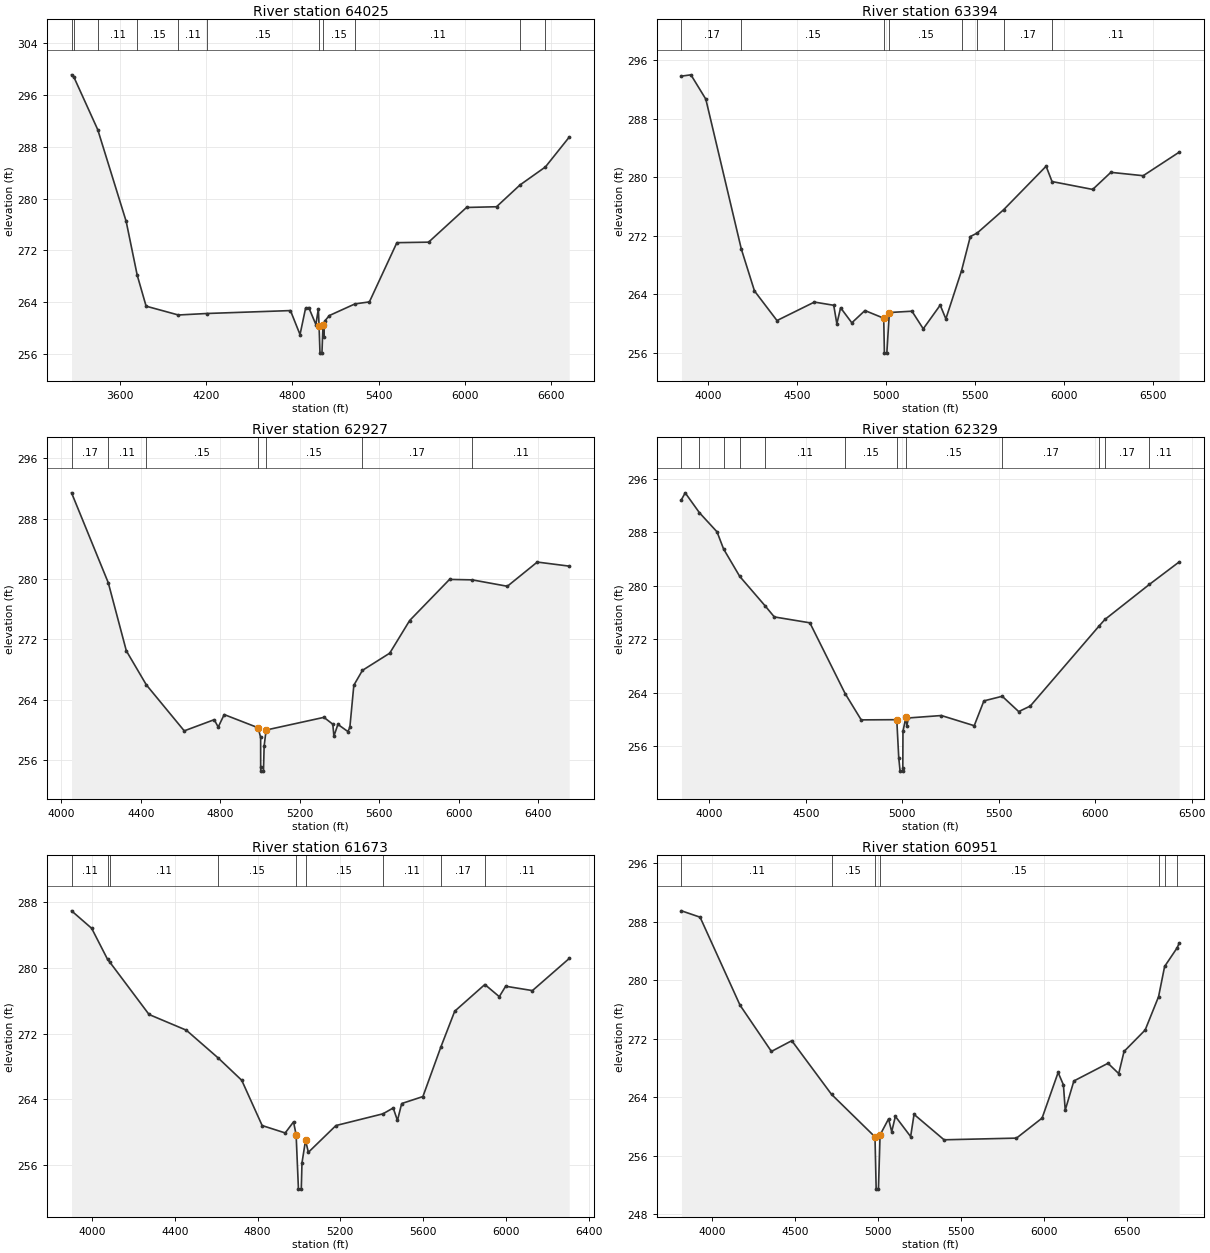
Type RM Length L Ch R = 1 ,64025   ,631,631,631
BEGIN DESCRIPTION:
LITTLE CANEY CREEK 81.0
END DESCRIPTION:
XS GIS Cut Line= 3
      3706767.83     10154461.03      3705976.49     10152915.21
      3706617.85     10151311.07
#Sta/Elev= 30
  3263.4  299.08  3279.7  298.73  3445.8  290.62  3643.5  276.49  3720.3   268.2
  3782.4  263.41  4006.9  262.05    4204  262.28  4787.1  262.73  4853.7  259.03
  4892.3  263.09  4914.7  263.19  4964.1  260.58  4981.3     263 4986.22260.3905
  4992.7  256.17  5006.3  256.17  5013.5  260.46  5018.9   258.7    5026  261.13
  5058.3  261.97  5236.2  263.76  5336.6  264.07  5527.9   273.2  5748.7  273.28
  6012.6  278.63  6221.4  278.74  6385.5  282.11  6561.9  284.88  6727.6  289.48
#Mann= 11 ,-1 , 0
  3263.4     .11       0  3279.7     .17       0  3445.8     .11       0
  3720.3     .15       0  4006.9     .11       0    4204     .15       0
 4986.22     .09       0  5013.5     .15       0  5236.2     .11       0
  6385.5     .17       0  6561.9     .11       0
Bank Sta=4986.22,5013.5
XS Rating Curve= 0 ,0
Exp/Cntr=0.3,0.1

Type RM Length L Ch R = 1 ,63394   ,467,467,467
BEGIN DESCRIPTION:
LITTLE CANEY CREEK 80.0
END DESCRIPTION:
XS GIS Cut Line= 3
      3706867.86     10154111.09      3706535.06     10153091.93
      3707097.55     10151461.76
#Sta/Elev= 30
    3849  293.84  3902.1  294.02  3985.8  290.69  4185.2  270.18  4259.3  264.43
  4385.7  260.38  4595.9  262.91  4704.6  262.47  4722.1  259.93  4743.2  262.13
  4806.3  260.07  4879.9  261.75  4985.5   260.7  4989.3  255.92  5002.9  255.92
  5017.2  261.48  5144.2  261.66  5207.6  259.25  5302.9  262.49  5334.6  260.61
  5422.7   267.2  5472.1  271.88  5510.6  272.36  5659.2  275.55    5898  281.51
  5931.2  279.41  6159.7  278.33  6261.8  280.67  6443.6  280.21  6645.6  283.43
#Mann= 8 ,-1 , 0
    3849     .17       0  4185.2     .15       0  4985.5     .09       0
  5017.2     .15       0  5422.7     .17       0  5510.6     .11       0
  5659.2     .17       0  5931.2     .11       0
Bank Sta=4985.5,5017.2
XS Rating Curve= 0 ,0
Exp/Cntr=0.3,0.1

Type RM Length L Ch R = 1 ,62927   ,598,598,598
BEGIN DESCRIPTION:
LITTLE CANEY CREEK 79.0
END DESCRIPTION:
XS GIS Cut Line= 3
      3707087.14     10154055.43      3706993.53     10153111.06
       3707118.4     10151560.68
#Sta/Elev= 30
    4051  291.43  4235.9   279.5  4326.7  270.48  4427.3  265.97  4618.1  259.87
  4768.9  261.35    4789  260.37  4819.1  262.03  4989.9  260.28  5002.5  258.99
  5002.7  255.03  5003.2  254.53  5016.8  254.53  5020.1  257.85  5030.1  259.98
    5321  261.66  5365.7  260.75  5371.2  259.16  5391.3  260.73  5441.4  259.78
  5451.4  260.32  5471.5  265.92  5514.7  267.89  5652.1  270.17  5752.4   274.5
  5953.1  279.95  6067.3  279.89    6244  279.04  6394.5  282.25  6555.4  281.71
#Mann= 7 ,-1 , 0
    4051     .17       0  4235.9     .11       0  4427.3     .15       0
  4989.9     .09       0  5030.1     .15       0  5514.7     .17       0
  6067.3     .11       0
Bank Sta=4989.9,5030.1
XS Rating Curve= 0 ,0
Exp/Cntr=0.3,0.1

Type RM Length L Ch R = 1 ,62329   ,656,656,656
BEGIN DESCRIPTION:
LITTLE CANEY CREEK 78.0
END DESCRIPTION:
XS GIS Cut Line= 3
      3707267.86     10154161.05      3707514.19     10153043.28
      3707417.85     10151611.11
#Sta/Elev= 30
  3855.4  292.86  3874.7  293.88  3948.4  290.91  4039.7  288.05  4073.5   285.5
  4157.4  281.39  4288.3  277.01  4336.7  275.33    4521  274.45  4703.9  263.87
  4787.2  259.94  4971.5  259.97  4981.8  254.27  4988.7  252.28  5002.3  252.28
  5002.8  252.78  5003.6  258.23  5018.6  260.31  5023.6  259.08  5032.3  260.23
  5202.7  260.59    5373  259.07  5423.2  262.78  5518.2  263.47  5603.6  261.18
  5663.7  262.01  6020.5  273.98  6050.5  274.95  6281.5   280.2  6435.4  283.55
#Mann= 12 ,-1 , 0
  3855.4     .11       0  3948.4     .17       0  4073.5     .11       0
  4157.4     .17       0  4288.3     .11       0  4703.9     .15       0
  4971.5     .09       0  5018.6     .15       0  5518.2     .17       0
  6020.5     .11       0  6050.5     .17       0  6281.5     .11       0
Bank Sta=4971.5,5018.6
XS Rating Curve= 0 ,0
Exp/Cntr=0.3,0.1

Type RM Length L Ch R = 1 ,61673   ,722,722,722
BEGIN DESCRIPTION:
LITTLE CANEY CREEK 77.0
END DESCRIPTION:
XS GIS Cut Line= 3
      3707867.85     10154061.07      3708035.06     10152977.35
      3708321.51     10151701.35
#Sta/Elev= 30
  3901.4  286.96  3998.6  284.83  4075.3  281.06  4086.6   280.7  4275.8  274.34
  4455.8  272.43    4611  269.02  4723.6  266.33  4822.2  260.82  4933.5  259.92
  4973.9  261.27  4986.3  259.69  4997.5  253.08  5011.2  253.08  5014.6  256.27
  5031.8  259.03  5045.4  257.56  5178.6  260.82    5406  262.25  5455.3  262.96
  5475.8  261.44  5496.3   263.5  5598.8  264.35  5685.8   270.4  5752.5  274.74
    5898  277.99  5967.8  276.51  5998.5  277.78  6127.9  277.25  6305.7  281.16
#Mann= 9 ,-1 , 0
  3901.4     .11       0  4075.3     .17       0  4086.6     .11       0
    4611     .15       0  4986.3     .09       0  5031.8     .15       0
    5406     .11       0  5685.8     .17       0    5898     .11       0
Bank Sta=4986.3,5031.8
XS Rating Curve= 0 ,0
Exp/Cntr=0.3,0.1

Type RM Length L Ch R = 1 ,60951   ,1500,1500,1500
BEGIN DESCRIPTION:
LITTLE CANEY CREEK 76.0
END DESCRIPTION:
XS GIS Cut Line= 3
      3708305.89     10154310.72       3708618.4     10152909.64
      3709092.16     10151415.46
#Sta/Elev= 30
  3813.2  289.52  3925.5  288.65  4166.5  276.61  4355.9  270.28  4478.8  271.75
  4718.5  264.41  4980.9  258.59    4988  251.44  5001.7  251.44  5011.6  258.86
  5062.8  261.05  5081.8  259.29  5103.8   261.4    5196  258.63  5216.5  261.67
  5397.6  258.19  5834.7  258.42  5989.1  261.16  6085.9   267.4  6117.9   265.7
  6128.7  262.25  6180.9  266.24  6386.9  268.66  6451.5  267.25  6483.7  270.28
    6611  273.21  6691.9  277.77  6728.5  281.91  6803.8  284.45  6816.2  285.09
#Mann= 7 ,-1 , 0
  3813.2     .11       0  4718.5     .15       0  4980.9     .09       0
  5011.6     .15       0  6691.9     .17       0  6728.5     .11       0
  6803.8     .17       0
Bank Sta=4980.9,5011.6
XS Rating Curve= 0 ,0
Exp/Cntr=0.3,0.1

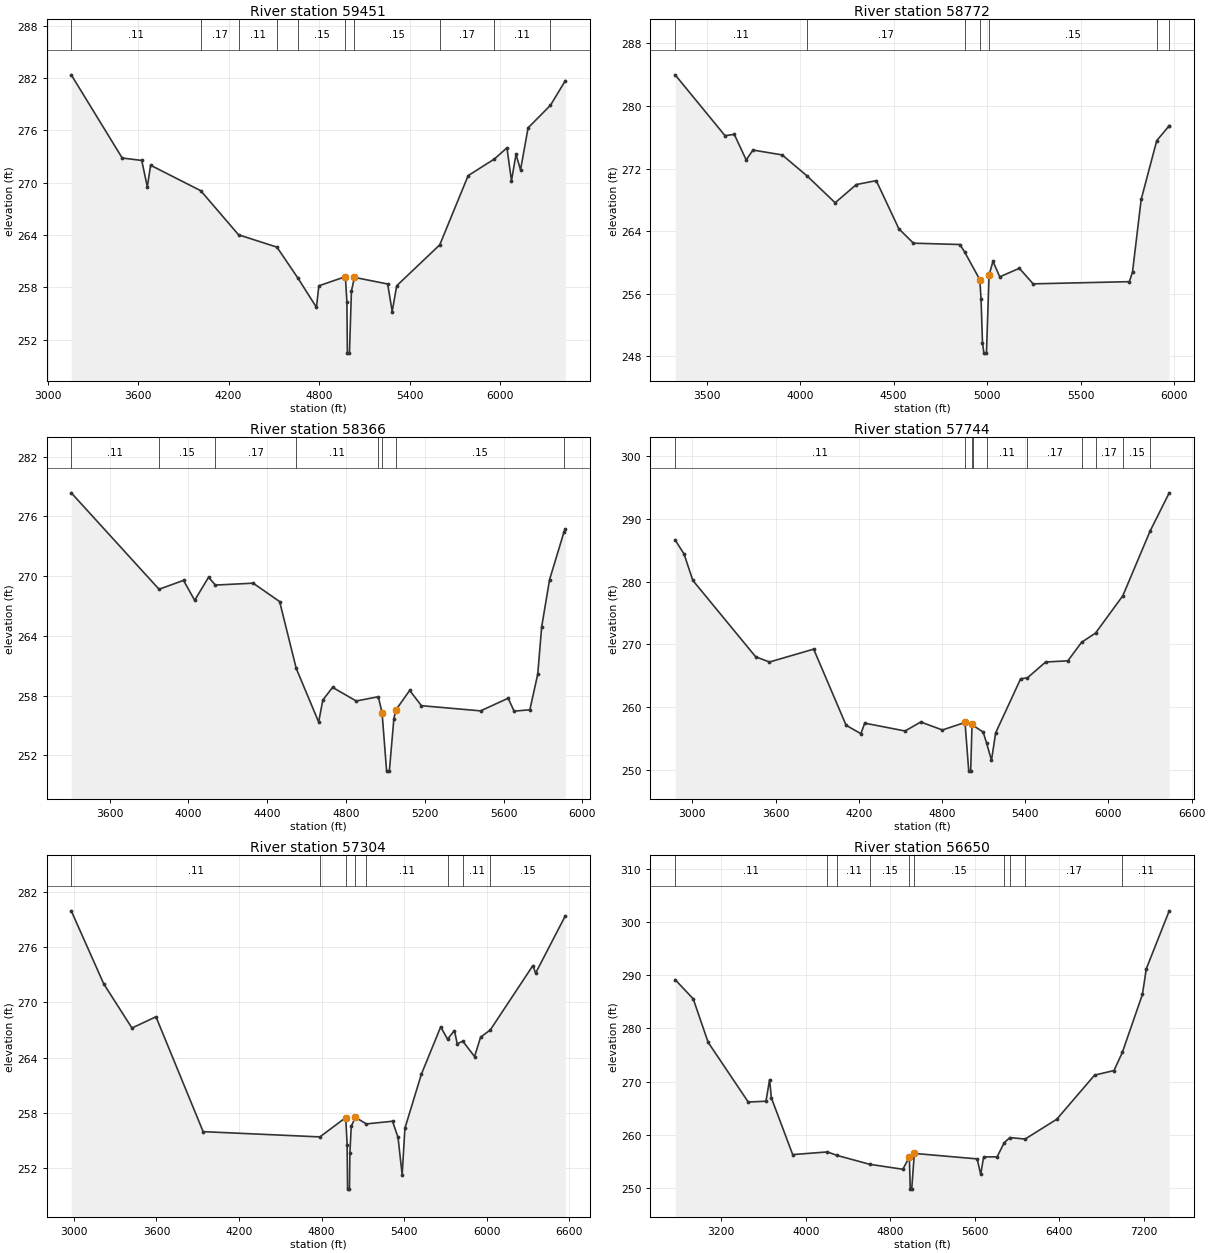
Type RM Length L Ch R = 1 ,59451   ,679,679,679
BEGIN DESCRIPTION:
LITTLE CANEY CREEK 75.0
END DESCRIPTION:
XS GIS Cut Line= 3
      3708831.95     10154404.41      3709706.94      10152883.6
      3709769.37     10151364.44
#Sta/Elev= 30
  3156.9  282.36  3494.6  272.82    3624  272.54  3661.3  269.51  3682.9  271.99
  4015.2  269.07  4266.1  264.01  4520.2   262.6  4657.8  259.09  4782.3  255.69
  4798.1  258.16    4974  259.21  4984.1  256.34  4987.2  250.44    5001  250.44
  5014.1  257.56  5034.1  259.13  5254.3  258.37  5284.3  255.21  5314.3  258.17
  5599.5  262.86  5787.9   270.8  5961.3   272.7  6044.9  273.99    6075  270.21
    6105  273.24    6135  271.46  6185.1  276.28  6333.1  278.86  6431.9  281.69
#Mann= 10 ,-1 , 0
  3156.9     .11       0  4015.2     .17       0  4266.1     .11       0
  4520.2     .17       0  4657.8     .15       0    4974     .09       0
  5034.1     .15       0  5599.5     .17       0  5961.3     .11       0
  6333.1     .17       0
Bank Sta=4974,5034.1
XS Rating Curve= 0 ,0
Exp/Cntr=0.3,0.1

Type RM Length L Ch R = 1 ,58772   ,406,406,406
BEGIN DESCRIPTION:
LITTLE CANEY CREEK 74.0
END DESCRIPTION:
XS GIS Cut Line= 3
      3708941.34     10154560.65      3710087.15     10153201.31
      3710352.79     10152378.34
#Sta/Elev= 30
  3331.7  283.98  3598.5   276.2    3648  276.37  3711.7   273.1    3748  274.36
  3904.1  273.74  4037.4  271.05  4187.6  267.62  4300.8  269.95  4407.4  270.45
  4528.3  264.29  4606.3  262.45  4854.7  262.28  4880.5  261.31  4961.3  257.78
  4967.9  255.28  4975.6  249.74    4983  248.39  4996.8  248.39  5010.8  258.37
  5031.6  260.13  5067.9  258.15  5172.8  259.24  5246.4  257.25  5761.3  257.53
  5778.1  258.79  5824.3  268.04  5907.7  275.57  5971.4  277.39  5974.3  277.39
#Mann= 7 ,-1 , 0
  3331.7     .11       0  4037.4     .17       0  4880.5     .15       0
  4961.3     .09       0  5010.8     .15       0  5907.7     .17       0
  5971.4     .15       0
Bank Sta=4961.3,5010.8
XS Rating Curve= 0 ,0
Exp/Cntr=0.3,0.1

Type RM Length L Ch R = 1 ,58366   ,622,622,622
BEGIN DESCRIPTION:
LITTLE CANEY CREEK 73.0
END DESCRIPTION:
XS GIS Cut Line= 3
       3709285.1     10154524.19      3710357.98     10153451.31
      3710367.85     10152461.04
#Sta/Elev= 30
  3405.3  278.36  3850.9  268.68  3975.1  269.57  4031.7  267.57  4102.4  269.89
  4136.7   269.1  4328.7  269.29    4463  267.44  4547.2  260.73    4661  255.35
  4682.2  257.56  4731.7  258.83  4851.9  257.46  4963.7  257.89  4982.8  256.29
  5005.9  250.42  5019.7  250.42  5042.8   255.7  5052.8  256.56  5122.8  258.52
  5182.8  256.99  5482.8  256.47  5622.9  257.74  5652.9  256.44  5732.9  256.58
  5772.9  260.16  5792.9  264.91  5832.9  269.64  5905.8  274.41  5912.9  274.69
#Mann= 8 ,-1 , 0
  3405.3     .11       0  3850.9     .15       0  4136.7     .17       0
  4547.2     .11       0  4963.7     .15       0  4982.8     .09       0
  5052.8     .15       0  5905.8     .17       0
Bank Sta=4982.8,5052.8
XS Rating Curve= 0 ,0
Exp/Cntr=0.3,0.1

Type RM Length L Ch R = 1 ,57744   ,440,440,440
BEGIN DESCRIPTION:
LITTLE CANEY CREEK 72.0
END DESCRIPTION:
XS GIS Cut Line= 3
      3709267.86     10154711.06      3710852.93     10153297.83
      3710917.85     10151861.09
#Sta/Elev= 30
  2876.4  286.62  2940.3   284.4  3003.9  280.18    3457  268.02  3556.5  267.19
  3875.1  269.24    4109  257.12  4215.4  255.78    4243  257.46  4533.9  256.21
  4646.8  257.64  4803.1  256.37  4966.1  257.57  4993.1  249.82  5006.9  249.82
  5016.8  257.35  5023.1  257.11  5096.9  256.04  5121.4  254.32  5156.9  251.54
  5186.9  255.91  5367.1  264.52    5416  264.67  5547.3  267.19  5707.5  267.38
  5806.2  270.32  5907.2   271.8  6103.6  277.73  6300.1  288.02  6438.2  294.12
#Mann= 10 ,-1 , 0
  2876.4     .11       0  4966.1     .06       0  5016.8     .11       0
  5023.1     .15       0  5121.4     .11       0    5416     .17       0
  5806.2     .15       0  5907.2     .17       0  6103.6     .15       0
  6300.1     .17       0
Bank Sta=4966.1,5016.8
XS Rating Curve= 0 ,0
Exp/Cntr=0.3,0.1

Type RM Length L Ch R = 1 ,57304   ,654,654,654
BEGIN DESCRIPTION:
LITTLE CANEY CREEK 71.0
END DESCRIPTION:
XS GIS Cut Line= 3
      3709446.54     10154685.67       3711118.4     10153670.06
      3711092.37     10152035.32
#Sta/Elev= 30
  2980.6  279.93  3216.5  272.01  3421.9  267.21  3596.3  268.43  3939.3  255.96
    4788  255.39  4975.7  257.49  4985.8  254.54  4988.9  249.72  5002.7  249.72
  5005.8  253.61  5015.8  256.55  5045.8  257.51  5125.4   256.8  5315.8  257.09
  5355.8  255.33  5385.8  251.27  5405.8  256.33  5525.8  262.21  5665.8  267.33
  5715.6     266  5765.8  266.93  5785.9   265.5  5826.6  265.78    5912  264.11
  5955.9  266.22  6026.4     267  6335.9  273.99  6355.9  273.17  6571.7  279.39
#Mann= 8 ,-1 , 0
  2980.6     .11       0    4788     .15       0  4975.7     .09       0
  5045.8     .15       0  5125.4     .11       0  5715.6     .15       0
  5826.6     .11       0  6026.4     .15       0
Bank Sta=4975.7,5045.8
XS Rating Curve= 0 ,0
Exp/Cntr=0.3,0.1

Type RM Length L Ch R = 1 ,56650   ,593,593,593
BEGIN DESCRIPTION:
LITTLE CANEY CREEK 70.0
END DESCRIPTION:
XS GIS Cut Line= 3
      3709317.82     10154961.09      3711321.57     10153967.21
      3711717.86     10151561.02
#Sta/Elev= 30
  2763.3  289.15  2934.2  285.55  3075.9  277.36  3455.4  266.15  3622.9  266.31
  3657.1  270.38  3673.9  266.94  3875.7  256.28  4204.5  256.78  4296.3  256.12
  4605.5  254.45  4917.9  253.52  4979.6  255.82  4988.2  249.79  5002.1  249.79
  5026.5   256.5  5621.3  255.47  5654.8  252.55  5682.5  255.85  5809.9  255.85
  5877.1  258.51  5930.3  259.48  6075.1   259.2  6374.4  262.92  6732.5  271.21
  6916.1  272.07  6995.2  275.49  7185.2  286.39  7221.9   291.2  7438.6  302.08
#Mann= 10 ,-1 , 0
  2763.3     .11       0  4204.5     .17       0  4296.3     .11       0
  4605.5     .15       0  4979.6     .09       0  5026.5     .15       0
  5877.1     .17       0  5930.3     .15       0  6075.1     .17       0
  6995.2     .11       0
Bank Sta=4979.6,5026.5
XS Rating Curve= 0 ,0
Exp/Cntr=0.3,0.1

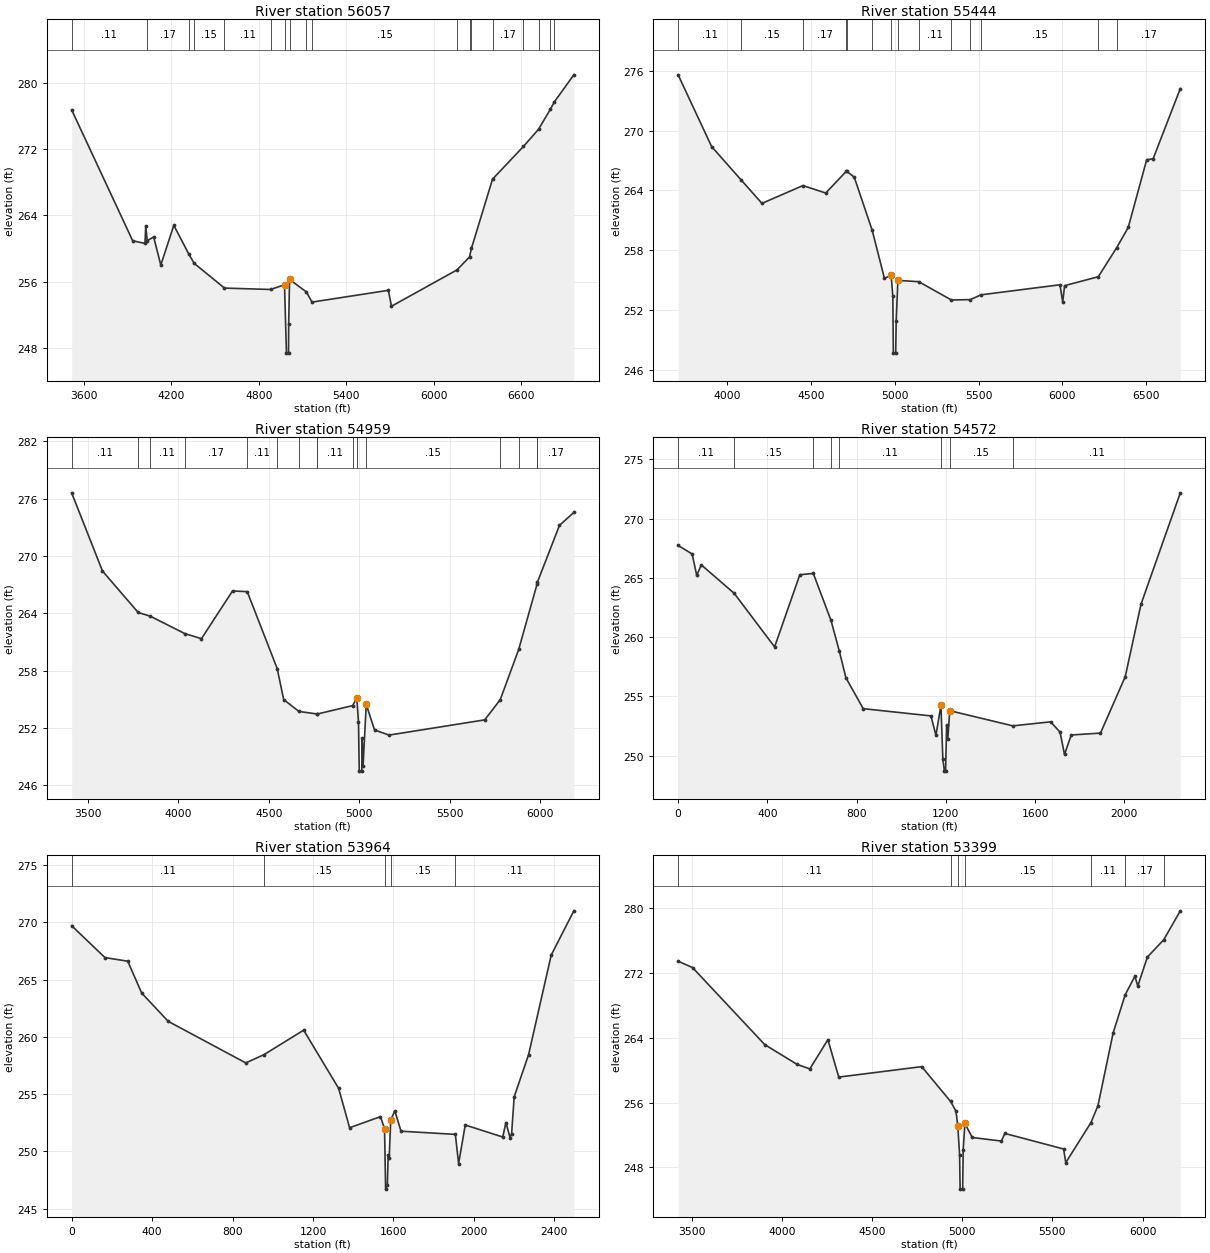
Type RM Length L Ch R = 1 ,56057   ,613,613,613
BEGIN DESCRIPTION:
LITTLE CANEY CREEK 69.0
END DESCRIPTION:
XS GIS Cut Line= 3
      3711217.85     10155361.08       3711759.9     10153978.97
      3712867.85     10152361.08
#Sta/Elev= 30
  3515.4  276.71  3934.3  260.93  4018.5  260.61  4023.9  262.75  4033.7  260.94
  4078.1  261.39    4127  258.01  4216.4  262.79  4317.9  259.37  4355.9  258.21
    4564  255.23  4880.1  255.06  4975.8  255.63  4989.2  247.39  5003.2  247.39
  5004.4  250.87  5010.4  256.27  5126.4  254.76  5164.4  253.54  5688.3  254.96
  5709.8  253.04  6159.3  257.42  6245.1  258.98  6258.6  260.03  6403.1  268.36
  6615.3   272.3  6718.5  274.37  6800.5  276.79  6826.5  277.65  6960.9  280.93
#Mann= 18 ,-1 , 0
  3515.4     .11       0  4033.7     .17       0  4317.9     .11       0
  4355.9     .15       0    4564     .11       0  4880.1     .15       0
  4975.8     .09       0  5010.4     .15       0  5126.4     .11       0
  5164.4     .15       0  6159.3     .11       0  6245.1     .17       0
  6258.6     .11       0  6403.1     .17       0  6615.3     .11       0
  6718.5     .17       0  6800.5     .11       0  6826.5     .17       0
Bank Sta=4975.8,5010.4
XS Rating Curve= 0 ,0
Exp/Cntr=0.3,0.1

Type RM Length L Ch R = 1 ,55444   ,485,485,485
BEGIN DESCRIPTION:
LITTLE CANEY CREEK 68.0
END DESCRIPTION:
XS GIS Cut Line= 3
      3712054.16     10155540.74      3712106.24     10153962.59
      3712767.83     10152711.11
#Sta/Elev= 30
  3708.7  275.62  3908.5  268.41  4083.2  265.08  4208.6   262.7  4453.2  264.49
  4588.9  263.74  4711.3  265.92  4715.1  265.91  4758.9  265.34  4865.9     260
    4939  255.17  4979.1  255.46  4989.1  253.36  4992.1  247.65  5006.1  247.65
  5009.1  250.91  5019.1  254.96  5143.4  254.83  5338.4  252.99  5451.6  253.03
  5514.7  253.51  5985.8  254.52    6002  252.78  6013.5  254.43  6214.3  255.33
  6323.3  258.23  6392.7  260.28  6502.7  267.08  6541.1  267.18  6703.3  274.24
#Mann= 14 ,-1 , 0
  3708.7     .11       0  4083.2     .15       0  4453.2     .17       0
  4711.3     .11       0  4715.1     .17       0  4865.9     .15       0
  4979.1     .09       0  5019.1     .15       0  5143.4     .11       0
  5338.4     .15       0  5451.6     .11       0  5514.7     .15       0
  6214.3     .11       0  6323.3     .17       0
Bank Sta=4979.1,5019.1
XS Rating Curve= 0 ,0
Exp/Cntr=0.3,0.1

Type RM Length L Ch R = 1 ,54959   ,387,387,387
BEGIN DESCRIPTION:
LITTLE CANEY CREEK 67.0
END DESCRIPTION:
XS GIS Cut Line= 3
      3712217.85     10155561.07      3712446.79     10153987.84
      3712817.85     10152861.06
#Sta/Elev= 30
  3410.2   276.6  3580.4  268.43  3777.9  264.09  3843.8  263.71  4034.9  261.89
  4127.7  261.35  4299.5  266.34  4380.8  266.27  4546.4  258.23  4582.4  254.98
  4666.8  253.74  4765.6  253.48  4767.7  253.47  4963.2  254.35  4986.6  255.12
  4995.8  252.62  5000.1   247.5  5014.1   247.5  5015.9  250.97  5021.1  248.03
  5038.7  254.47  5084.7   251.8    5165  251.27  5693.7  252.86  5779.4  254.97
  5881.6  260.23  5983.8  267.11  5985.3  267.27  6106.8   273.2  6186.3  274.55
#Mann= 16 ,-1 , 0
  3410.2     .11       0  3777.9     .15       0  3843.8     .11       0
  4034.9     .17       0  4380.8     .11       0  4546.4     .15       0
  4666.8     .17       0  4765.6     .15       0  4767.7     .11       0
  4963.2     .15       0  4986.6     .09       0  5038.7     .15       0
  5779.4     .11       0  5881.6     .17       0  5983.8     .11       0
  5985.3     .17       0
Bank Sta=4986.6,5038.7
XS Rating Curve= 0 ,0
Exp/Cntr=0.3,0.1

Type RM Length L Ch R = 1 ,54572   ,608,608,608
BEGIN DESCRIPTION:
LITTLE CANEY CREEK 66.0
END DESCRIPTION:
XS GIS Cut Line= 4
      3712619.58     10155222.31      3712482.01     10154632.22
      3712741.66     10154103.22      3712877.08     10153056.34
#Sta/Elev= 30
       0  267.74    62.9  267.02    83.4  265.22     104   266.1   251.4   263.7
   432.5  259.18   545.5  265.27   605.9  265.38   685.2  261.42   722.7  258.81
     752  256.58   829.6  253.97  1133.1  253.36  1155.6  251.72    1178  254.26
  1186.5  249.71  1193.6   248.7  1198.8   248.7  1203.4  252.58  1208.5   251.4
  1217.5   253.8  1499.9  252.52  1669.2  252.86  1711.6     252  1731.8  250.11
    1762  251.75  1893.1  251.91    2004  256.67  2074.6  262.78  2250.8  272.18
#Mann= 8 ,-1 , 0
       0     .11       0   251.4     .15       0   605.9     .11       0
   685.2     .15       0   722.7     .11       0    1178     .06       0
  1217.5     .15       0  1499.9     .11       0
Bank Sta=1178,1217.5
XS Rating Curve= 0 ,0
Exp/Cntr=0.3,0.1

Type RM Length L Ch R = 1 ,53964   ,565,565,565
BEGIN DESCRIPTION:
LITTLE CANEY CREEK 65.0
END DESCRIPTION:
XS GIS Cut Line= 3
      3712845.74     10155514.27      3713114.31     10153967.49
      3712917.85     10153061.07
#Sta/Elev= 30
       0   269.7   165.6  266.92   278.9   266.6   348.3  263.82   480.3  261.35
     866  257.72   957.3  258.45  1153.7  260.58  1327.7   255.5  1382.3  252.06
  1535.8  253.03  1556.1  251.96  1561.3   246.7  1569.9  247.04  1574.1   249.7
  1579.2  249.41  1586.7  252.74  1607.2  253.54  1637.9  251.76  1908.2  251.48
  1924.4  248.93  1957.3   252.3  2143.8  251.25  2159.7  252.51  2180.2   251.2
  2187.9  251.53  2200.7  254.76  2272.3  258.44  2384.8  267.13  2497.4     271
#Mann= 5 ,-1 , 0
       0     .11       0   957.3     .15       0  1556.1     .09       0
  1586.7     .15       0  1908.2     .11       0
Bank Sta=1556.1,1586.7
XS Rating Curve= 0 ,0
Exp/Cntr=0.3,0.1

Type RM Length L Ch R = 1 ,53399   ,533,533,533
BEGIN DESCRIPTION:
LITTLE CANEY CREEK 64.0
END DESCRIPTION:
XS GIS Cut Line= 3
      3713467.85     10155611.06       3713517.7      10153845.4
      3713830.21     10152876.62
#Sta/Elev= 30
  3425.2  273.45  3505.2  272.66  3905.4  263.16  4085.4  260.71  4155.5  260.16
  4255.5  263.77  4315.8  259.15  4775.7  260.44  4935.8  256.15  4965.8  254.95
  4975.8  253.14  4985.8  249.55  4988.8  245.33  5002.8  245.33  5005.8  250.18
  5015.2  253.44  5055.8   251.7  5217.1  251.26  5236.9   252.2  5562.6  250.28
  5574.4   248.6  5713.9  253.53    5753  255.63  5837.1   264.6    5904  269.31
  5957.7   271.6  5973.7  270.38  6027.1  273.96  6117.5  276.09  6209.5  279.66
#Mann= 7 ,-1 , 0
  3425.2     .11       0  4935.8     .15       0  4975.8     .09       0
  5015.2     .15       0  5713.9     .11       0    5904     .17       0
  6117.5     .11       0
Bank Sta=4975.8,5015.2
XS Rating Curve= 0 ,0
Exp/Cntr=0.3,0.1

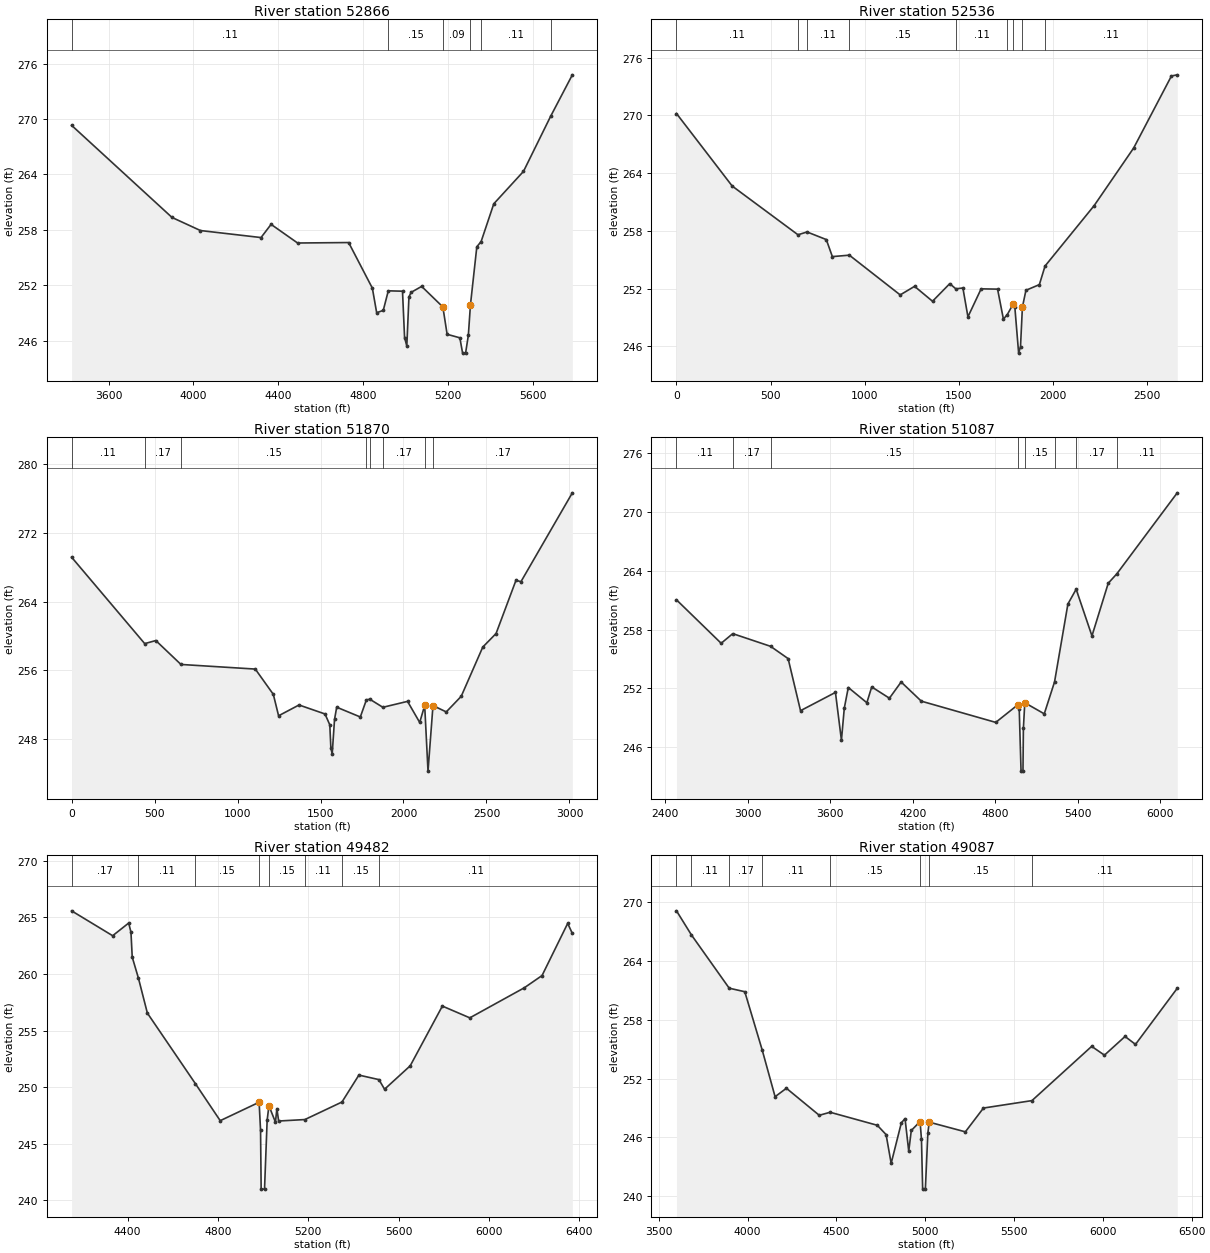
Type RM Length L Ch R = 1 ,52866   ,330,330,330
BEGIN DESCRIPTION:
LITTLE CANEY CREEK 63.0
END DESCRIPTION:
XS GIS Cut Line= 3
      3713637.38      10155377.1      3713911.95     10153827.03
      3713908.33     10153040.74
#Sta/Elev= 30
  3425.8  269.32  3899.1  259.34  4033.3  257.92  4318.8  257.16  4366.2  258.59
  4491.2  256.57  4731.8  256.62  4843.6  251.68  4863.9  249.02    4895  249.27
  4918.7  251.39  4985.7  251.35  4995.4  246.33    5006  245.41    5016  250.72
    5026  251.22    5076  251.87    5176  249.64    5196  246.68    5256   246.3
    5269  244.64    5283  244.64    5296  246.55    5306  249.88    5336  256.16
  5356.3  256.73    5416  260.82    5556  264.33  5683.8  270.29  5786.3  274.79
#Mann= 6 ,-1 , 0
  3425.8     .11       0  4918.7     .15       0    5176     .09       0
    5306     .15       0  5356.3     .11       0  5683.8     .17       0
Bank Sta=5176,5306
XS Rating Curve= 0 ,0
Exp/Cntr=0.3,0.1

Type RM Length L Ch R = 1 ,52536   ,666,666,666
BEGIN DESCRIPTION:
LITTLE CANEY CREEK 62.0
END DESCRIPTION:
XS GIS Cut Line= 3
      3713662.57     10155415.81      3714189.58     10153756.86
      3714137.49     10152840.19
#Sta/Elev= 30
       0   270.2   295.9  262.66     645   257.6   693.4  257.89   795.4   257.1
   827.6  255.33   917.8  255.48  1187.7  251.35  1264.1  252.24  1359.4  250.69
  1450.9  252.52  1483.2  251.98  1520.7  252.07  1547.4  249.07  1617.5  251.98
  1704.8  251.95  1735.8  248.83  1756.5  249.31  1786.5  250.36  1796.5  250.07
  1816.6   245.3  1826.6  245.98  1836.6  250.08  1855.4  251.83  1926.7  252.42
  1956.8  254.35  2217.2  260.62  2427.5  266.62  2627.9   274.1  2658.8  274.22
#Mann= 9 ,-1 , 0
       0     .11       0     645     .17       0   693.4     .11       0
   917.8     .15       0  1483.2     .11       0  1756.5     .17       0
  1786.5     .09       0  1836.6     .15       0  1956.8     .11       0
Bank Sta=1786.5,1836.6
XS Rating Curve= 0 ,0
Exp/Cntr=0.3,0.1

Type RM Length L Ch R = 1 ,51870   ,783,783,783
BEGIN DESCRIPTION:
LITTLE CANEY CREEK 61.0
END DESCRIPTION:
XS GIS Cut Line= 4
      3713720.91     10155364.76      3714246.87     10154163.11
      3714710.41     10153590.19      3714689.58     10152621.44
#Sta/Elev= 30
       0  269.18   440.7  259.09   507.6  259.45     659  256.66  1107.1  256.12
  1215.7  253.17  1247.4  250.67  1370.6  251.93  1527.2  250.88    1556  249.61
  1562.4  246.93  1570.4  246.21  1584.5  250.24  1597.6  251.67  1739.9  250.53
  1776.6  252.53  1797.4   252.6  1875.8  251.66  2024.5  252.35  2097.8  249.89
  2127.8  251.88  2147.8  244.21  2177.8  251.86  2257.8  251.12  2347.9  252.94
  2477.9  258.69  2557.9  260.27  2677.9  266.48  2707.9  266.32  3017.6  276.69
#Mann= 8 ,-1 , 0
       0     .11       0   440.7     .17       0     659     .15       0
  1776.6     .15       0  1797.4     .11       0  1875.8     .17       0
  2127.8     .09       0  2177.8     .17       0
Bank Sta=2127.8,2177.8
XS Rating Curve= 0 ,0
Exp/Cntr=0.3,0.1

Type RM Length L Ch R = 1 ,51087   ,1605,1605,1605
BEGIN DESCRIPTION:
LITTLE CANEY CREEK 60.0
END DESCRIPTION:
XS GIS Cut Line= 5
      3713918.74     10155069.38      3714309.37     10154168.32
      3714726.04     10153621.44      3715423.95     10153564.15
      3715226.21     10152304.86
#Sta/Elev= 30
    2481  261.02  2806.1   256.6  2890.5  257.58  3165.7  256.29  3293.5  255.04
  3383.8  249.74  3637.9   251.6  3681.5  246.73  3702.3     250  3731.4   252.1
  3866.5  250.55  3901.9  252.16  4030.7  251.01    4116  252.66  4262.8  250.71
  4804.6  248.55  4965.3  250.34  4975.5  249.87  4988.7  243.59  5002.7  243.59
  5005.8  247.96    5016  250.55  5157.7  249.42  5232.5  252.67  5329.8   260.6
  5389.8   262.1  5504.8  257.35  5623.3  262.71  5685.9  263.67  6125.6  271.91
#Mann= 8 ,-1 , 0
    2481     .11       0  2890.5     .17       0  3165.7     .15       0
  4965.3     .09       0    5016     .15       0  5232.5     .11       0
  5389.8     .17       0  5685.9     .11       0
Bank Sta=4965.3,5016
XS Rating Curve= 0 ,0
Exp/Cntr=0.3,0.1

Type RM Length L Ch R = 1 ,49482   ,395,395,395
BEGIN DESCRIPTION:
LITTLE CANEY CREEK 58.0
END DESCRIPTION:
XS GIS Cut Line= 3
      3716835.41     10154350.58      3716701.24     10153513.57
      3715637.46     10152652.67
#Sta/Elev= 30
  4152.3  265.58  4334.1  263.38    4405   264.5  4415.1  263.69  4420.7  261.49
  4448.4  259.61  4487.7  256.54    4700  250.31  4810.1  247.03  4982.3  248.66
  4988.6  246.18  4991.3  240.98  5006.2  240.98  5017.8  247.07  5025.7  248.35
  5054.5   246.9  5060.9  248.09  5068.7     247  5184.8  247.13  5348.9  248.68
  5423.8  251.06  5512.5  250.66  5537.4  249.81  5650.9  251.88  5793.2  257.16
  5914.7  256.12  6156.1  258.78  6234.4  259.86  6347.9  264.47  6368.5  263.58
#Mann= 8 ,-1 , 0
  4152.3     .17       0  4448.4     .11       0    4700     .15       0
  4982.3     .09       0  5025.7     .15       0  5184.8     .11       0
  5348.9     .15       0  5512.5     .11       0
Bank Sta=4982.3,5025.7
XS Rating Curve= 0 ,0
Exp/Cntr=0.3,0.1

Type RM Length L Ch R = 1 ,49087   ,697,697,697
BEGIN DESCRIPTION:
LITTLE CANEY CREEK 57.0
END DESCRIPTION:
XS GIS Cut Line= 3
       3717835.4     10154355.81      3716939.58     10153277.69
      3715713.25      10152565.8
#Sta/Elev= 30
  3599.3  269.13  3683.4  266.67  3896.1  261.23  3983.9  260.87  4082.2   254.9
  4154.5  250.15  4218.3  251.01  4403.2  248.25  4464.5  248.56    4730  247.23
  4779.5  246.28  4808.1  243.34  4865.4  247.48  4886.2  247.91  4907.1  244.58
  4921.4   246.7  4970.9  247.61  4978.7  245.81  4985.4  240.71  5000.7  240.71
  5014.6  246.42  5022.3  247.55  5225.9  246.56  5327.8  248.99  5600.9  249.75
  5937.1  255.29    6009  254.39    6125   256.3  6183.8  255.49    6419  261.22
#Mann= 8 ,-1 , 0
  3599.3     .17       0  3683.4     .11       0  3896.1     .17       0
  4082.2     .11       0  4464.5     .15       0  4970.9     .09       0
  5022.3     .15       0  5600.9     .11       0
Bank Sta=4970.9,5022.3
XS Rating Curve= 0 ,0
Exp/Cntr=0.3,0.1

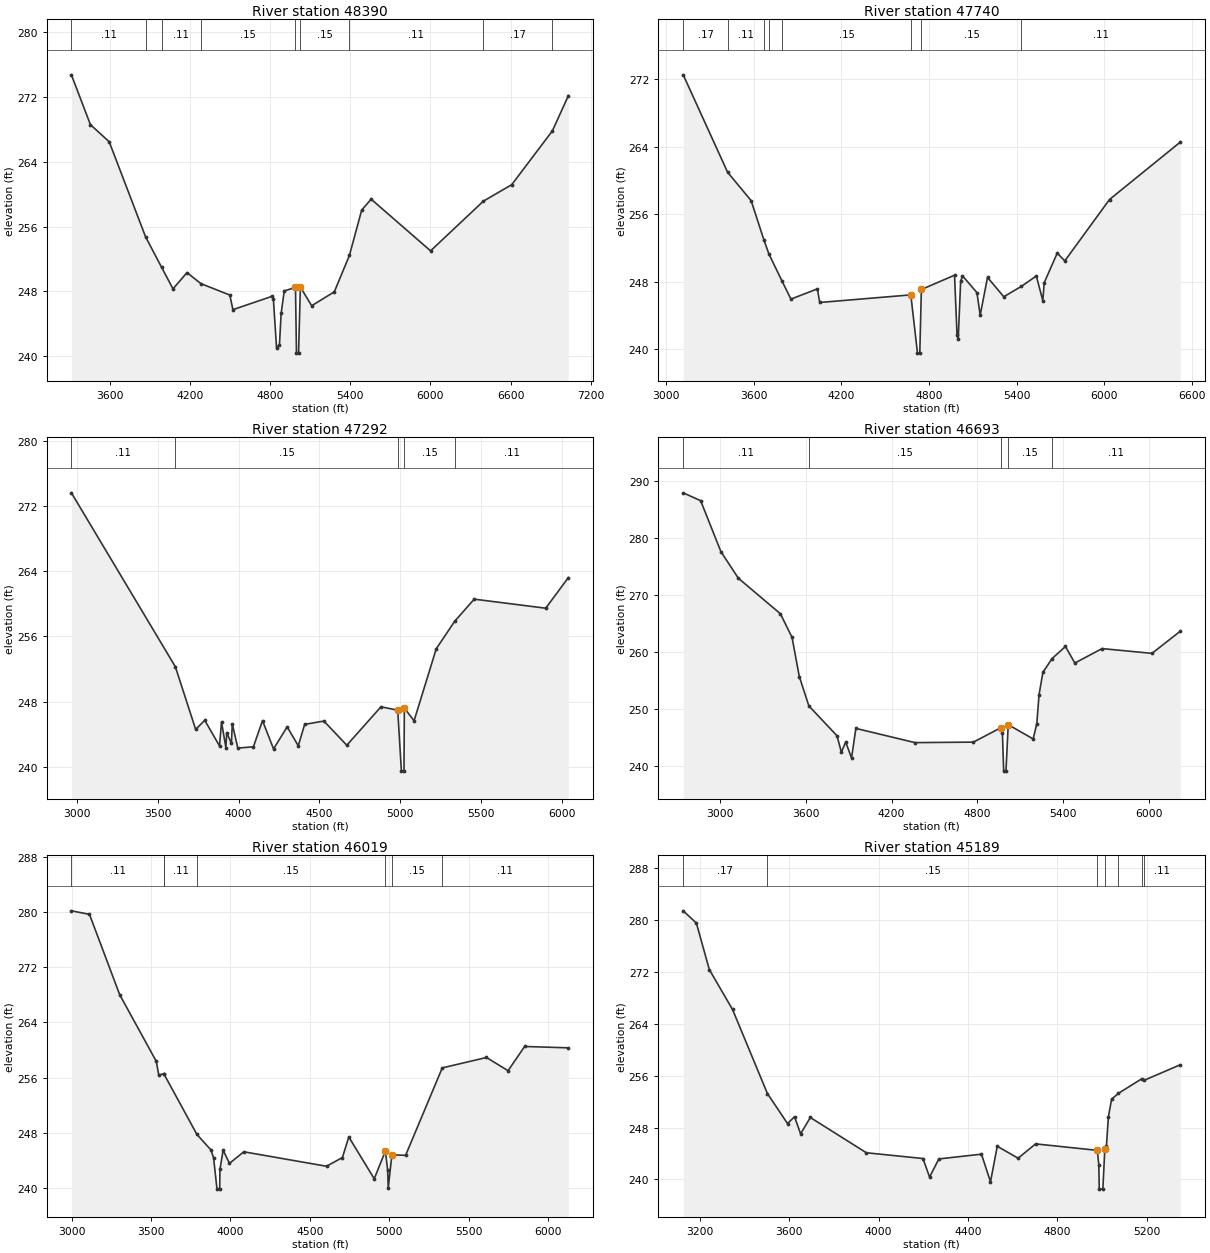
Type RM Length L Ch R = 1 ,48390   ,650,650,650
BEGIN DESCRIPTION:
LITTLE CANEY CREEK 56.0
END DESCRIPTION:
XS GIS Cut Line= 3
      3718017.83     10154461.03      3717343.79     10152910.51
      3715917.83     10151461.05
#Sta/Elev= 30
  3309.3   274.7  3451.8  268.56  3592.5  266.45  3865.2  254.73  3984.9  250.98
  4070.7  248.31  4175.4  250.32  4279.7  248.96  4496.5  247.55  4519.6  245.75
    4814   247.4  4823.1  247.02  4846.6  241.03  4868.5  241.45  4880.9  245.28
  4904.4  248.06  4988.5  248.49  4995.9  240.39  5011.6  240.39  5025.1  248.54
  5109.9  246.23  5279.6  247.95  5392.5  252.43  5484.7  258.03  5555.4  259.37
  6000.8     253    6396  259.12    6609  261.16  6913.6  267.79  7033.3  272.13
#Mann= 9 ,-1 , 0
  3309.3     .11       0  3865.2     .17       0  3984.9     .11       0
  4279.7     .15       0  4988.5     .09       0  5025.1     .15       0
  5392.5     .11       0    6396     .17       0  6913.6     .11       0
Bank Sta=4988.5,5025.1
XS Rating Curve= 0 ,0
Exp/Cntr=0.3,0.1

Type RM Length L Ch R = 1 ,47740   ,448,448,448
BEGIN DESCRIPTION:
LITTLE CANEY CREEK 55.0
END DESCRIPTION:
XS GIS Cut Line= 3
      3718179.15     10154350.59       3717705.2      10152532.9
      3717017.72     10151168.36
#Sta/Elev= 30
  3115.3   272.5  3419.5  260.96  3580.6   257.6    3669  252.91  3703.2  251.25
  3793.7  248.03  3853.7  245.93  4034.6  247.14    4051  245.53  4675.3  246.43
    4721  239.53  4736.8  239.53  4747.6  247.07    4975  248.76  4992.1  241.65
  5000.2  241.21  5016.9  248.03  5029.4  248.69  5128.5   246.7  5150.8  244.03
    5201   248.5  5312.5  246.21  5433.2  247.44  5535.6  248.67  5580.3  245.73
  5589.3  247.86  5678.9  251.38  5730.8  250.46  6037.2  257.73  6521.7  264.52
#Mann= 8 ,-1 , 0
  3115.3     .17       0  3419.5     .11       0    3669     .17       0
  3703.2     .11       0  3793.7     .15       0  4675.3     .09       0
  4747.6     .15       0  5433.2     .11       0
Bank Sta=4675.3,4747.6
XS Rating Curve= 0 ,0
Exp/Cntr=0.3,0.1

Type RM Length L Ch R = 1 ,47292   ,599,599,599
BEGIN DESCRIPTION:
LITTLE CANEY CREEK 54.0
END DESCRIPTION:
XS GIS Cut Line= 3
      3718538.53     10154225.57      3717994.82     10152265.59
      3717892.78     10151231.61
#Sta/Elev= 30
    2966  273.64  3608.9  252.28  3734.4  244.58  3790.5   245.7  3881.9  242.56
  3894.3  245.49  3921.3  242.36  3926.5  244.19  3955.6  242.86  3960.8  245.27
  3995.1  242.29  4091.5  242.45  4147.7  245.66    4216  242.19  4300.4   244.9
  4368.9  242.57  4408.4   245.2  4527.3  245.61    4669  242.64  4880.2  247.36
  4983.9  246.94  5006.6  239.46  5022.6  239.46  5024.8  247.21  5084.9  245.64
  5222.1  254.49    5336  257.86  5456.7  260.58  5898.9  259.47    6039  263.23
#Mann= 5 ,-1 , 0
    2966     .11       0  3608.9     .15       0  4983.9     .09       0
  5024.8     .15       0    5336     .11       0
Bank Sta=4983.9,5024.8
XS Rating Curve= 0 ,0
Exp/Cntr=0.3,0.1

Type RM Length L Ch R = 1 ,46693   ,674,674,674
BEGIN DESCRIPTION:
LITTLE CANEY CREEK 53.0
END DESCRIPTION:
XS GIS Cut Line= 3
      3718767.85     10154461.07       3718371.8     10152237.16
      3718095.82     10151048.48
#Sta/Elev= 30
  2741.1  287.94    2863  286.56  3005.2  277.59  3127.1  272.93  3421.6  266.68
  3502.9  262.53  3553.7  255.65  3620.7  250.49  3817.8  245.23  3848.2  242.35
  3878.7  244.14  3919.4  241.32  3949.8  246.53  4363.9  244.03  4772.6  244.12
  4965.6  246.66  4975.7  245.67  4984.5  239.02  5000.5  239.02  5016.5  247.18
    5191  244.68  5216.6  247.39  5232.1  252.45  5259.2  256.38  5323.5  258.81
  5416.9  260.93  5482.7  258.02  5673.5  260.56  6022.6  259.72  6220.3   263.6
#Mann= 5 ,-1 , 0
  2741.1     .11       0  3620.7     .15       0  4965.6     .09       0
  5016.5     .15       0  5323.5     .11       0
Bank Sta=4965.6,5016.5
XS Rating Curve= 0 ,0
Exp/Cntr=0.3,0.1

Type RM Length L Ch R = 1 ,46019   ,830,830,830
BEGIN DESCRIPTION:
LITTLE CANEY CREEK 52.0
END DESCRIPTION:
XS GIS Cut Line= 3
      3719006.42      10154204.8      3718884.89     10152216.93
      3718555.04     10151127.56
#Sta/Elev= 30
  2998.9   280.2  3112.8  279.69  3303.2  268.02  3533.6  258.35  3548.8  256.39
  3580.7  256.53  3582.6  256.48  3789.2  247.75    3878  245.48  3894.3  244.37
  3915.9   239.8  3932.9   239.8  3934.4  242.65  3954.4  245.45  3994.5  243.54
  4084.7  245.22  4605.6  243.12  4705.8  244.39  4745.9  247.37  4906.2   241.3
  4976.3  245.33  4990.5  242.58  4994.4     240  5017.5  244.78  5103.7  244.71
  5334.6   257.4  5613.1  258.91  5748.9  256.99  5853.4  260.51  6128.7  260.31
#Mann= 7 ,-1 , 0
  2998.9     .11       0  3580.7     .15       0  3582.6     .11       0
  3789.2     .15       0  4976.3     .09       0  5017.5     .15       0
  5334.6     .11       0
Bank Sta=4976.3,5017.5
XS Rating Curve= 0 ,0
Exp/Cntr=0.3,0.1

Type RM Length L Ch R = 1 ,45189   ,1177,1177,1177
BEGIN DESCRIPTION:
LITTLE CANEY CREEK 51.0
END DESCRIPTION:
XS GIS Cut Line= 4
      3719978.63     10153510.33      3719386.66     10153163.35
      3719219.09     10151982.56      3719019.44     10151700.44
#Sta/Elev= 30
  3125.8  281.44  3184.7  279.55  3242.6  272.38  3346.4  266.23  3502.7  253.25
  3592.6  248.63    3624  249.68  3651.2  247.04  3694.7  249.56  3945.6  244.12
    4199  243.23  4228.4  240.37    4270  243.17  4460.7   243.9  4501.1  239.64
  4531.4  245.12  4624.7  243.28  4703.1  245.49  4979.3  244.49  4985.9  242.25
    4988  238.51    5004  238.51 5012.85244.7134  5020.1  245.19  5028.7  249.63
  5043.2  252.39  5073.9  253.29  5178.9  255.55  5190.4  255.32  5350.2  257.69
#Mann= 7 ,-1 , 0
  3125.8     .17       0  3502.7     .15       0  4979.3     .09       0
 5012.85     .15       0  5073.9     .17       0  5178.9     .15       0
  5190.4     .11       0
Bank Sta=4979.3,5012.85
XS Rating Curve= 0 ,0
Exp/Cntr=0.3,0.1