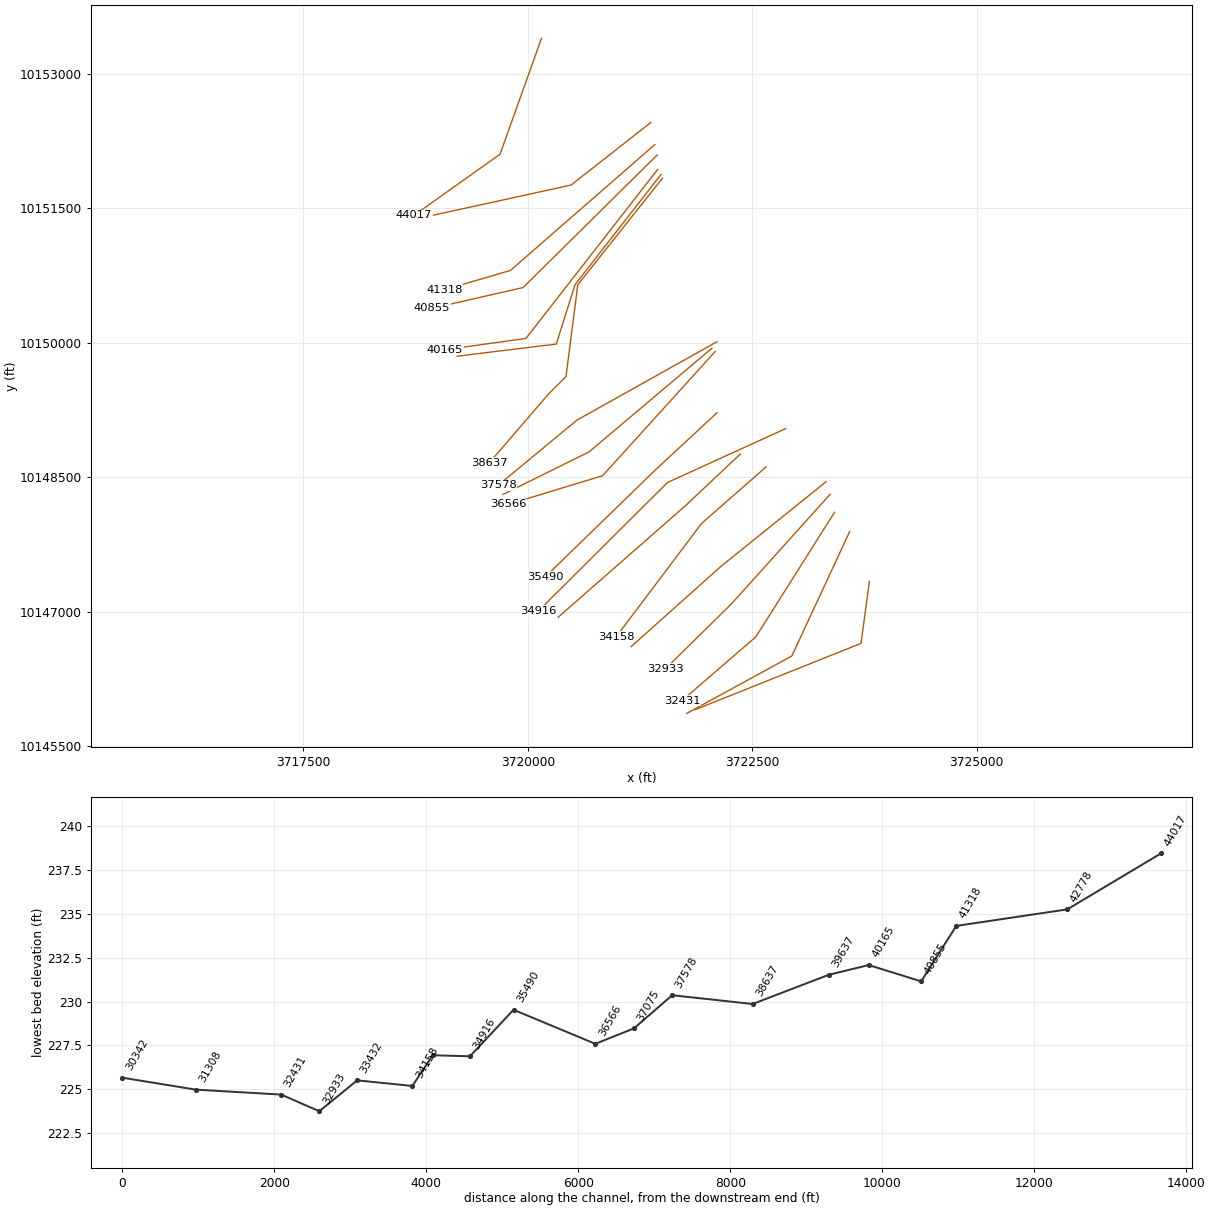
HEC-RAS study LITTLE CANEY CREEK.prj: LITTLE CANEY CREEK Base Level Engineering

--- LITTLE CANEY CREEK.g01 (geometry) --- (continued)

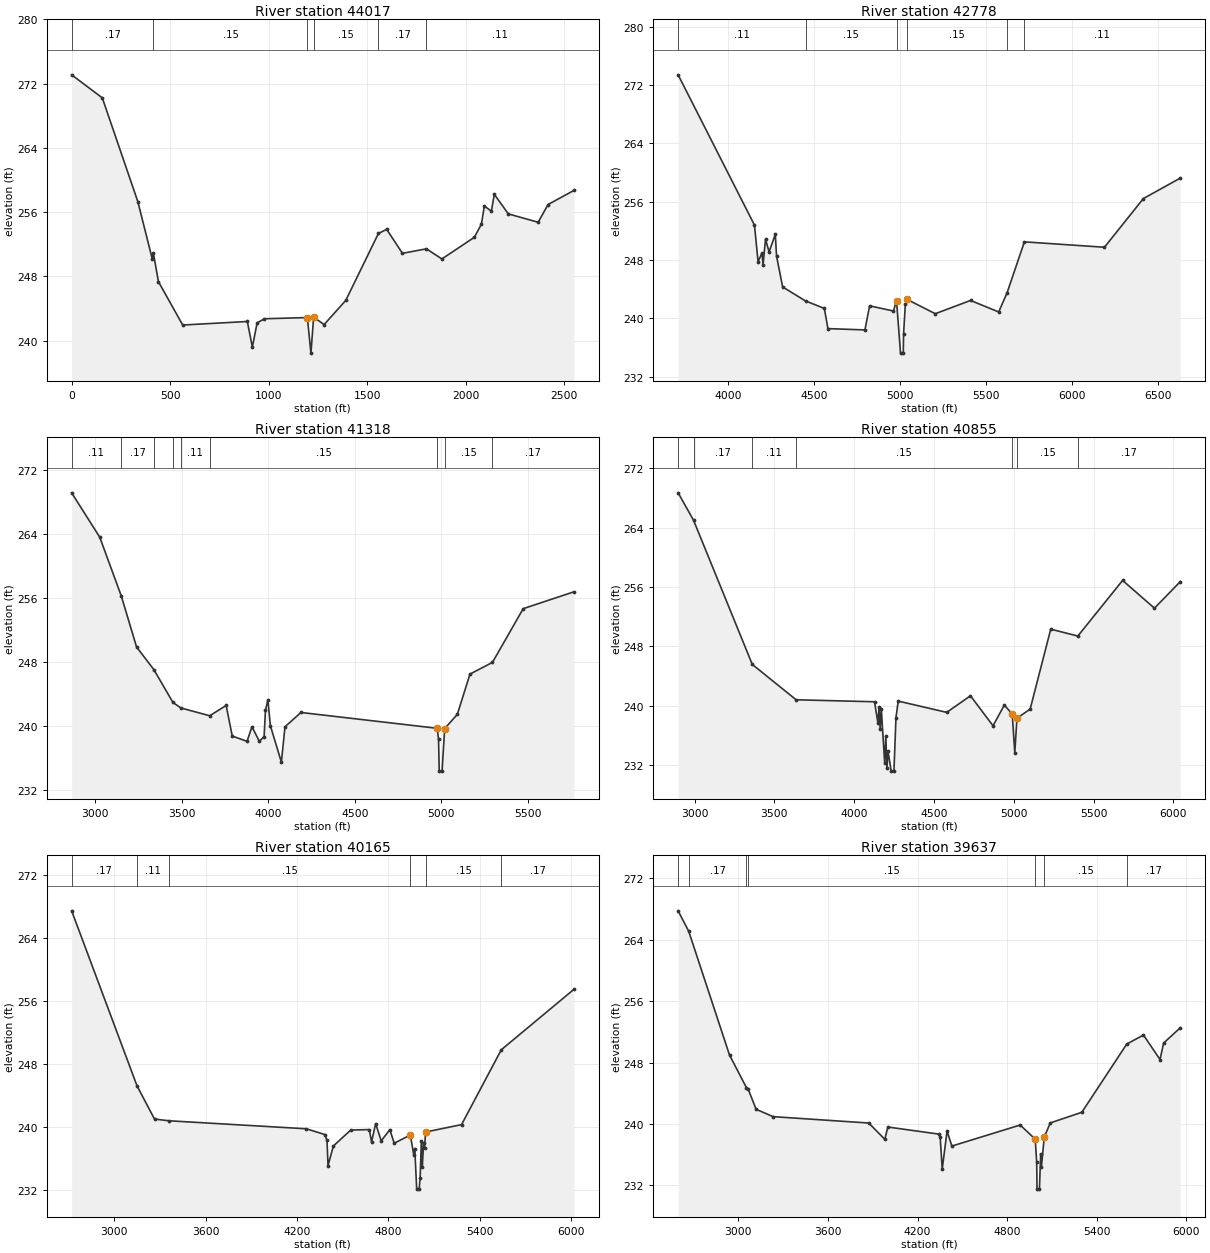
Type RM Length L Ch R = 1 ,44017   ,1234,1234,1234
BEGIN DESCRIPTION:
LITTLE CANEY CREEK 50.0
END DESCRIPTION:
XS GIS Cut Line= 3
      3720152.25     10153397.49      3719690.31     10152104.75
      3718731.27     10151422.84
#Sta/Elev= 30
       0   273.1   155.5  270.23     336   257.3   409.7  250.11     415  250.87
   440.4  247.34   563.6  241.94   891.6  242.38   917.1  239.18   941.3  242.21
   978.7  242.72  1196.2  242.87  1214.4  238.44    1228  242.92  1281.3     242
    1391     245    1557  253.35  1598.8  253.85  1678.8  250.87  1800.5  251.43
  1878.9  250.17    2044  252.87  2079.7  254.52  2094.5  256.76  2130.1  256.12
  2144.9  258.22  2216.2  255.78  2367.5  254.74  2417.9  256.95  2548.6   258.7
#Mann= 6 ,-1 , 0
       0     .17       0     415     .15       0  1196.2     .09       0
    1228     .15       0    1557     .17       0  1800.5     .11       0
Bank Sta=1196.2,1228
XS Rating Curve= 0 ,0
Exp/Cntr=0.3,0.1

Type RM Length L Ch R = 1 ,42778   ,1460,1460,1460
BEGIN DESCRIPTION:
LITTLE CANEY CREEK 49.0
END DESCRIPTION:
XS GIS Cut Line= 3
      3721371.88       10152460.      3720482.11      10151761.2
       3718737.3     10151379.25
#Sta/Elev= 30
  3711.2  273.39  4154.9  252.79  4175.7  247.78  4198.2  248.97  4204.6  247.34
    4219  250.85  4239.8  249.13  4275.8  251.53  4283.2  248.52  4318.5  244.32
  4451.4   242.4  4560.7  241.38  4581.5  238.61  4796.5  238.43  4823.7  241.73
  4962.4  241.02    4980  242.46  5003.3  235.25  5019.4  235.25    5021  237.89
  5031.2  241.95  5041.4  242.61  5205.2  240.65    5410  242.47  5573.7  240.89
  5622.7  243.54  5722.9   250.5    6188  249.76    6414  256.43  6628.7  259.24
#Mann= 6 ,-1 , 0
  3711.2     .11       0  4451.4     .15       0    4980     .09       0
  5041.4     .15       0  5622.7     .17       0  5722.9     .11       0
Bank Sta=4980,5041.4
XS Rating Curve= 0 ,0
Exp/Cntr=0.3,0.1

Type RM Length L Ch R = 1 ,41318   ,463,463,463
BEGIN DESCRIPTION:
LITTLE CANEY CREEK 48.0
END DESCRIPTION:
XS GIS Cut Line= 3
      3721415.26     10152212.58      3719806.02     10150808.76
      3719072.15     10150593.85
#Sta/Elev= 30
  2864.5  269.14  3026.7  263.59  3150.7  256.26  3239.4  249.85  3339.4  247.01
  3449.6   242.9  3495.8  242.21  3662.2  241.24  3756.8  242.53  3791.9   238.7
  3877.3  238.04  3905.8  239.86  3948.5  238.04    3976  238.63  3983.6   241.9
  3997.9  243.24  4012.1     240  4075.7  235.44  4096.6  239.86  4188.7  241.65
  4975.7  239.67  4983.3   238.3  4987.4  234.31  5003.6  234.31  5018.9  239.64
  5091.9  241.42  5164.8  246.45  5294.7  247.92  5472.2  254.64  5764.7  256.75
#Mann= 9 ,-1 , 0
  2864.5     .11       0  3150.7     .17       0  3339.4     .11       0
  3449.6     .17       0  3495.8     .11       0  3662.2     .15       0
  4975.7     .09       0  5018.9     .15       0  5294.7     .17       0
Bank Sta=4975.7,5018.9
XS Rating Curve= 0 ,0
Exp/Cntr=0.3,0.1

Type RM Length L Ch R = 1 ,40855   ,690,690,690
BEGIN DESCRIPTION:
LITTLE CANEY CREEK 47.0
END DESCRIPTION:
XS GIS Cut Line= 3
      3721442.15     10152097.11      3719947.39     10150617.97
      3718929.96     10150385.71
#Sta/Elev= 30
  2896.7  268.71  2993.1  265.02  3361.5  245.55  3636.1  240.78  4127.3  240.51
  4148.5  237.67  4155.6  239.76  4162.7  236.79  4169.7   239.6    4191  232.26
    4198  235.87  4205.1  231.63  4212.1   233.8  4231.8  231.15    4249  231.15
  4261.7  238.38  4275.8   240.6  4579.9  239.08  4728.4  241.32  4869.8  237.27
  4940.5  240.06    4990  238.87  5006.2  233.62  5019.6  238.29  5102.4  239.52
  5231.4  250.31  5401.1  249.38  5681.7  256.89  5881.2  253.14  6043.2  256.73
#Mann= 7 ,-1 , 0
  2896.7     .11       0  2993.1     .17       0  3361.5     .11       0
  3636.1     .15       0    4990     .09       0  5019.6     .15       0
  5401.1     .17       0
Bank Sta=4990,5019.6
XS Rating Curve= 0 ,0
Exp/Cntr=0.3,0.1

Type RM Length L Ch R = 1 ,40165   ,528,528,528
BEGIN DESCRIPTION:
LITTLE CANEY CREEK 46.0
END DESCRIPTION:
XS GIS Cut Line= 3
      3721447.36     10151935.65      3719978.64     10150050.26
      3719077.61     10149925.27
#Sta/Elev= 30
  2719.1   267.5  3149.1   245.2  3263.5     241  3357.4  240.78  4260.5  239.76
  4382.7  239.03  4397.1  238.27  4403.5  235.08  4438.8  237.57  4552.8   239.6
  4674.9  239.66  4689.4  238.07  4716.5  240.42  4753.1  238.22  4809.7  239.65
  4838.7  237.92  4944.5  238.97  4967.1  236.43  4973.5  237.25  4986.2  232.08
  5002.4  232.08  5008.7  233.52  5016.9  238.21  5023.2  234.87  5031.4  237.98
  5037.7  237.31  5044.6  239.35  5280.8  240.29  5542.2  249.82  6018.7   257.5
#Mann= 6 ,-1 , 0
  2719.1     .17       0  3149.1     .11       0  3357.4     .15       0
  4944.5     .09       0  5044.6     .15       0  5542.2     .17       0
Bank Sta=4944.5,5044.6
XS Rating Curve= 0 ,0
Exp/Cntr=0.3,0.1

Type RM Length L Ch R = 1 ,39637   ,1000,1000,1000
BEGIN DESCRIPTION:
LITTLE CANEY CREEK 45.0
END DESCRIPTION:
XS GIS Cut Line= 4
      3721483.88     10151878.42      3720525.52     10150649.22
      3720317.18     10149987.76        3719213.     10149852.34
#Sta/Elev= 30
    2596  267.77  2666.9  265.11  2940.3  248.99  3053.9  244.73    3065  244.57
  3118.5  241.92  3232.5  240.96  3873.3  240.13  3980.6  238.01  4001.4  239.61
  4341.4  238.69  4351.9   238.3  4365.4  234.12  4397.8  239.08  4430.2  237.13
  4887.8  239.87  4988.5  238.03  4998.6     235  5000.6  231.52  5016.8  231.52
  5025.1  236.13  5030.1  234.42    5049  238.29  5089.3  240.14  5300.8  241.53
    5602  250.42  5713.9  251.59  5824.7   248.4  5848.9  250.55  5960.6  252.54
#Mann= 7 ,-1 , 0
    2596     .11       0  2666.9     .17       0  3053.9     .11       0
    3065     .15       0  4988.5     .09       0    5049     .15       0
    5602     .17       0
Bank Sta=4988.5,5049
XS Rating Curve= 0 ,0
Exp/Cntr=0.3,0.1

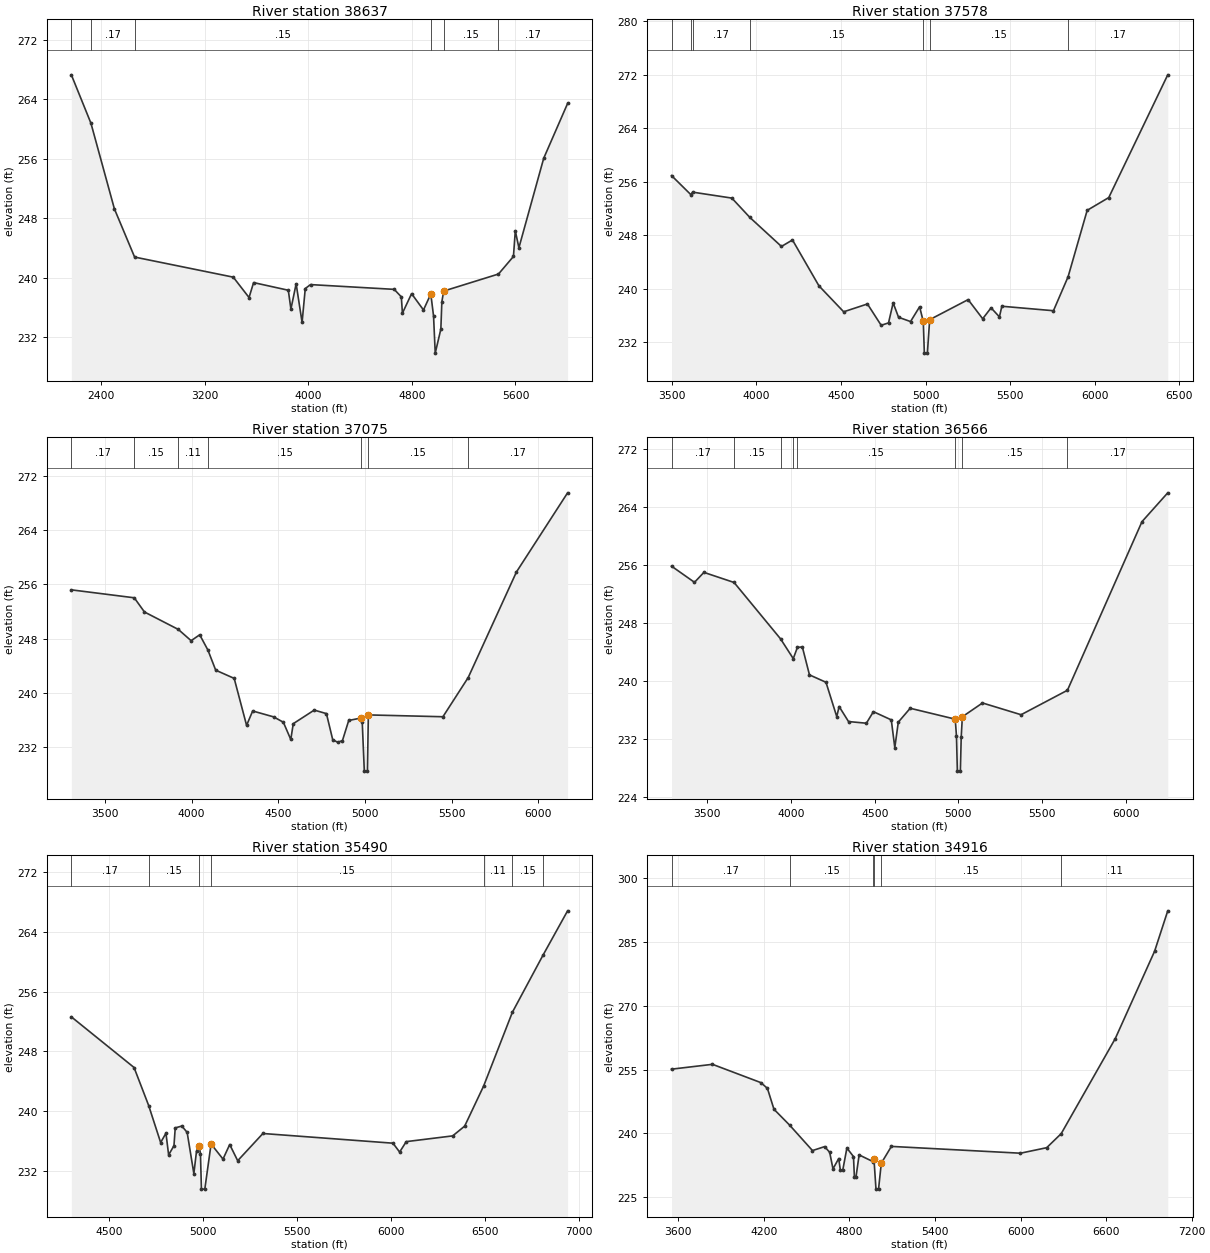
Type RM Length L Ch R = 1 ,38637   ,1059,1059,1059
BEGIN DESCRIPTION:
LITTLE CANEY CREEK 44.0
END DESCRIPTION:
XS GIS Cut Line= 5
      3721499.48     10151836.74      3720556.77     10150649.22
      3720425.31     10149624.43      3720226.24     10149426.26
      3719573.12      10148665.7
#Sta/Elev= 30
  2169.7  267.26  2321.1  260.75  2502.3  249.24  2658.2  242.77  3420.3  240.07
  3542.1  237.33  3577.3  239.34  3845.4  238.31  3865.5  235.78  3905.9  239.18
  3951.8  233.99  3976.4  238.54  4016.8  239.07  4663.4  238.43  4718.3  237.42
  4726.8  235.23  4797.5  237.85  4889.4  235.66    4946  237.81  4967.2  234.85
  4980.2  229.86  5023.6  233.09  5031.3  236.75  5045.5   238.2  5468.8  240.49
  5584.3  242.85  5598.6  246.29  5626.4  244.02  5818.1  256.05  6002.5  263.41
#Mann= 6 ,-1 , 0
  2169.7     .11       0  2321.1     .17       0  2658.2     .15       0
    4946     .09       0  5045.5     .15       0  5468.8     .17       0
Bank Sta=4946,5045.5
XS Rating Curve= 0 ,0
Exp/Cntr=0.3,0.1

Type RM Length L Ch R = 1 ,37578   ,503,503,503
BEGIN DESCRIPTION:
LITTLE CANEY CREEK 43.0
END DESCRIPTION:
XS GIS Cut Line= 3
      3722108.89     10150013.83      3720546.35     10149138.81
      3719667.88     10148411.09
#Sta/Elev= 30
  3499.3  256.91  3613.4  254.06    3624  254.43  3855.8  253.54  3962.5  250.64
  4148.8  246.31  4213.9  247.28  4370.3  240.42  4516.4  236.54  4656.8  237.71
  4737.9  234.52  4781.3  234.88  4808.7  237.87  4840.6  235.72  4911.4  235.08
    4965  237.29  4986.7  235.09    4993  230.36  5010.9  230.36  5024.4  235.36
  5251.6  238.36  5337.6   235.5  5387.1  237.13  5436.5  235.78  5450.9  237.37
  5755.7   236.7  5842.2  241.78  5954.9  251.71  6082.5  253.62  6430.9  271.97
#Mann= 7 ,-1 , 0
  3499.3     .17       0  3613.4     .11       0    3624     .17       0
  3962.5     .15       0  4986.7     .09       0  5024.4     .15       0
  5842.2     .17       0
Bank Sta=4986.7,5024.4
XS Rating Curve= 0 ,0
Exp/Cntr=0.3,0.1

Type RM Length L Ch R = 1 ,37075   ,509,509,509
BEGIN DESCRIPTION:
LITTLE CANEY CREEK 42.0
END DESCRIPTION:
XS GIS Cut Line= 3
      3722051.52     10149940.86      3720681.77     10148784.64
      3719723.46      10148310.7
#Sta/Elev= 30
  3306.7  255.17  3669.5     254  3728.2  251.91  3923.5  249.34  3997.4  247.68
  4046.8  248.55  4094.2   246.3  4139.1  243.34  4245.7  242.13  4317.2  235.21
  4352.3  237.33  4473.2  236.46  4529.2  235.67  4572.1  233.13  4586.4  235.46
  4707.3  237.46  4777.6  236.94  4813.9   233.1  4842.5  232.72  4869.9  232.96
  4906.2  235.93  4976.5  236.29  4984.2  235.66  4996.1  228.47    5014  228.47
  5019.4  236.75  5449.4  236.48  5595.3  242.26  5873.3   257.8  6168.3  269.46
#Mann= 7 ,-1 , 0
  3306.7     .17       0  3669.5     .15       0  3923.5     .11       0
  4094.2     .15       0  4976.5     .09       0  5019.4     .15       0
  5595.3     .17       0
Bank Sta=4976.5,5019.4
XS Rating Curve= 0 ,0
Exp/Cntr=0.3,0.1

Type RM Length L Ch R = 1 ,36566   ,1076,1076,1076
BEGIN DESCRIPTION:
LITTLE CANEY CREEK 41.0
END DESCRIPTION:
XS GIS Cut Line= 3
      3722088.02     10149904.44      3720832.81     10148519.01
      3719785.94     10148201.31
#Sta/Elev= 30
  3286.6  255.83  3423.8   253.6  3480.1  254.97  3660.2  253.58  3938.2   245.8
  4013.7  243.09  4038.4  244.63  4067.9   244.7  4110.5  240.85  4209.1  239.83
  4273.4   235.1  4287.6  236.49  4343.7  234.42  4450.4  234.19  4492.3  235.78
  4599.1  234.65  4620.1  230.83    4641  234.34    4712  236.25    4981  234.75
  4988.4  232.42  4993.7  227.59  5011.6  227.59  5016.8  232.34  5023.5  235.08
  5143.8  236.98  5374.2  235.36    5651  238.73  6096.3  261.96  6250.1  265.93
#Mann= 8 ,-1 , 0
  3286.6     .17       0  3660.2     .15       0  3938.2     .11       0
  4013.7     .17       0  4038.4     .15       0    4981     .09       0
  5023.5     .15       0    5651     .17       0
Bank Sta=4981,5023.5
XS Rating Curve= 0 ,0
Exp/Cntr=0.3,0.1

Type RM Length L Ch R = 1 ,35490   ,574,574,574
BEGIN DESCRIPTION:
LITTLE CANEY CREEK 40.0
END DESCRIPTION:
XS GIS Cut Line= 3
      3722108.86     10149222.15      3721419.55       10148582.
      3720198.48     10147395.07
#Sta/Elev= 30
  4297.1  252.63  4631.1  245.84    4709  240.74  4772.8  235.78  4801.1  237.03
  4815.3  234.12  4843.7  235.35  4850.5  237.74  4885.6  237.99    4914  237.14
  4949.7  231.61  4963.8  234.61    4978  235.36  4984.8  234.28  4990.1  229.53
    5008  229.53  5041.5  235.58    5105  233.56  5140.7  235.51  5183.2  233.34
  5317.5  236.99  6010.4  235.69  6045.9   234.5  6081.2   235.9  6328.6  236.67
  6392.4  237.98  6493.5  243.36  6646.6  253.25  6809.2  260.88  6940.7  266.85
#Mann= 7 ,-1 , 0
  4297.1     .17       0    4709     .15       0    4978     .09       0
  5041.5     .15       0  6493.5     .11       0  6646.6     .15       0
  6809.2     .11       0
Bank Sta=4978,5041.5
XS Rating Curve= 0 ,0
Exp/Cntr=0.3,0.1

Type RM Length L Ch R = 1 ,34916   ,490,490,490
BEGIN DESCRIPTION:
LITTLE CANEY CREEK 39.0
END DESCRIPTION:
XS GIS Cut Line= 3
      3722874.51     10149045.07      3721557.92     10148444.48
      3720117.83     10147011.05
#Sta/Elev= 30
  3552.9   255.1  3840.1  256.24  4179.1  251.94  4225.2  250.59  4271.2  245.67
  4380.9  241.94  4541.2  235.95  4626.4  236.88  4661.8  235.54  4684.9  231.65
  4725.3  234.08  4736.5  231.36    4754  231.44  4782.5  236.55  4828.6  234.54
  4835.2  229.71  4846.2  229.72  4868.2  234.93  4966.8  233.33  4972.3  233.93
  4986.4  226.88  5004.4  226.88  5023.7  232.98  5094.4  236.93  5999.5  235.33
  6183.3  236.63  6284.9  239.93  6664.2  262.31  6939.9  282.86  7031.9  292.35
#Mann= 6 ,-1 , 0
  3552.9     .17       0  4380.9     .15       0  4966.8     .12       0
  4972.3     .09       0  5023.7     .15       0  6284.9     .11       0
Bank Sta=4972.3,5023.7
XS Rating Curve= 0 ,0
Exp/Cntr=0.3,0.1

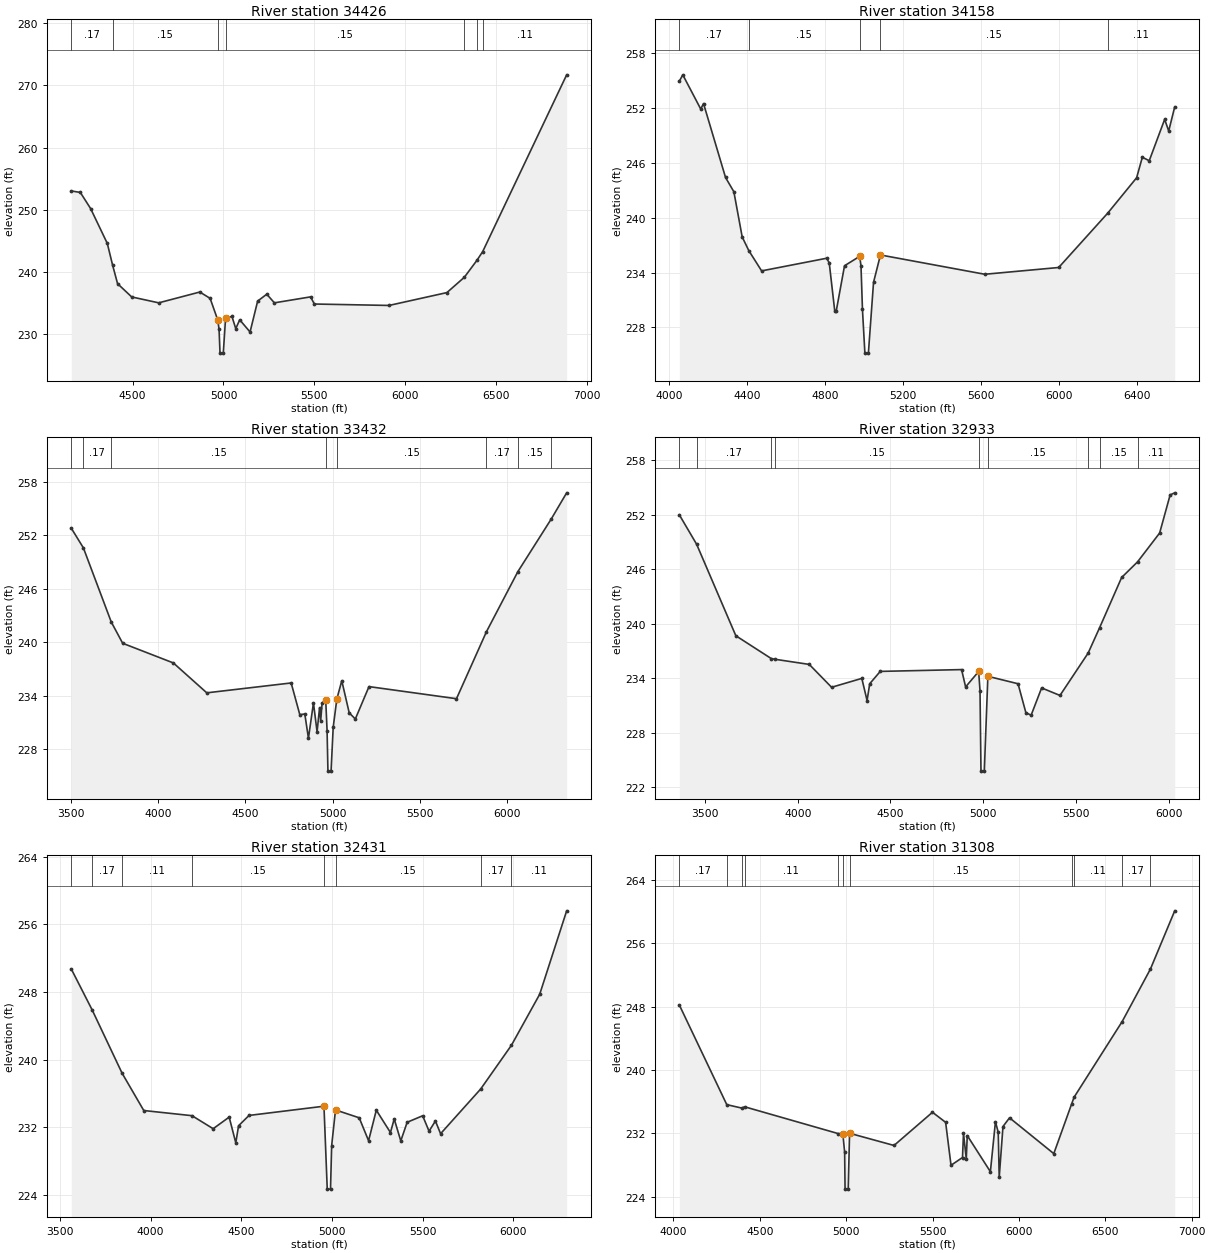
Type RM Length L Ch R = 1 ,34426   ,268,268,268
BEGIN DESCRIPTION:
LITTLE CANEY CREEK 38.0
END DESCRIPTION:
XS GIS Cut Line= 3
      3722367.87     10148761.09      3721758.52     10148186.55
      3720338.03      10146940.9
#Sta/Elev= 30
  4162.5  253.03  4212.1  252.79  4268.7   250.2  4360.6  244.59  4390.2  241.05
  4417.2  238.11  4494.9  235.98  4643.6  235.03  4869.9  236.77  4926.6  235.75
  4969.1  232.23  4975.9  230.76  4981.1  226.94  4999.1  226.94  5011.7  232.56
  5046.8  232.84  5067.7  230.88  5089.5   232.3  5146.5  230.34  5188.2  235.31
  5238.5  236.42  5280.3  235.03  5479.6  235.99  5500.4  234.84  5911.4  234.61
  6230.2  236.68  6325.9  239.14  6394.9  241.85    6427  243.27  6889.3  271.71
#Mann= 7 ,-1 , 0
  4162.5     .17       0  4390.2     .15       0  4969.1     .09       0
  5011.7     .15       0  6325.9     .11       0  6394.9     .15       0
    6427     .11       0
Bank Sta=4969.1,5011.7
XS Rating Curve= 0 ,0
Exp/Cntr=0.3,0.1

Type RM Length L Ch R = 1 ,34158   ,726,726,726
BEGIN DESCRIPTION:
LITTLE CANEY CREEK 37.0
END DESCRIPTION:
XS GIS Cut Line= 3
      3722655.72     10148617.97      3721936.97     10147987.76
      3720983.84     10146722.13
#Sta/Elev= 30
  4051.3  254.92  4068.9  255.61  4160.9  251.87  4175.2  252.47  4288.1  244.39
  4330.8  242.83  4373.5  237.89  4407.3   236.4  4473.1  234.18  4806.2  235.56
  4819.8  235.07    4848  229.83  4855.6  229.77  4898.3  234.74  4976.1  235.77
  4982.8  234.72  4990.3  229.96  5002.7  225.19  5020.7  225.19  5047.1  232.93
  5082.5  235.92  5617.6  233.81  5996.6  234.55    6248  240.49  6396.3  244.36
  6425.5   246.6  6460.9  246.22    6540  250.74  6560.8  249.47  6591.6  252.11
#Mann= 5 ,-1 , 0
  4051.3     .17       0  4407.3     .15       0  4976.1     .09       0
  5082.5     .15       0    6248     .11       0
Bank Sta=4976.1,5082.5
XS Rating Curve= 0 ,0
Exp/Cntr=0.3,0.1

Type RM Length L Ch R = 1 ,33432   ,499,499,499
BEGIN DESCRIPTION:
LITTLE CANEY CREEK 36.0
END DESCRIPTION:
XS GIS Cut Line= 3
      3723322.41     10148451.32      3722154.27     10147509.87
      3721151.65     10146613.78
#Sta/Elev= 30
  3499.7  252.81  3569.1   250.6    3729  242.28  3794.7  239.88  4085.8  237.67
  4277.8  234.31  4762.4  235.42    4812  231.86  4840.8  231.93  4861.6  229.21
  4890.4  233.17  4911.2  229.94  4925.6  232.65    4932  231.19    4940  233.14
  4960.8  233.54  4968.7  230.05  4973.6  225.51  4991.6  225.51  5003.8  230.43
  5024.7  233.61  5053.1  235.67  5095.8  232.06  5130.9  231.37  5209.4  235.01
  5711.9  233.65    5884  241.18  6064.4  247.93  6256.2  253.85  6344.7  256.79
#Mann= 8 ,-1 , 0
  3499.7     .11       0  3569.1     .17       0    3729     .15       0
  4960.8     .09       0  5024.7     .15       0    5884     .17       0
  6064.4     .15       0  6256.2     .11       0
Bank Sta=4960.8,5024.7
XS Rating Curve= 0 ,0
Exp/Cntr=0.3,0.1

Type RM Length L Ch R = 1 ,32933   ,502,502,502
BEGIN DESCRIPTION:
LITTLE CANEY CREEK 35.0
END DESCRIPTION:
XS GIS Cut Line= 3
      3723367.84     10148311.05      3722271.94     10147092.98
      3721535.95     10146367.99
#Sta/Elev= 30
  3361.5  251.99  3454.7  248.75  3666.1  238.67  3857.5  236.15  3879.7  236.07
  4062.2  235.51  4182.5  232.99  4345.5  233.97  4373.9  231.53  4388.1  233.38
  4444.9  234.74  4883.6  234.94  4905.3  233.03  4975.7  234.73    4983  232.62
  4988.2  223.75  5006.2  223.75  5025.4   234.2  5188.1  233.38  5230.5  230.18
  5258.8  229.92  5315.3  232.92  5414.3  232.09  5566.2  236.76  5628.3  239.57
  5746.8  245.09  5832.6  246.81  5951.8  249.99  6008.4  254.19  6033.1  254.42
#Mann= 9 ,-1 , 0
  3361.5     .11       0  3454.7     .17       0  3857.5     .11       0
  3879.7     .15       0  4975.7     .09       0  5025.4     .15       0
  5566.2     .11       0  5628.3     .15       0  5832.6     .11       0
Bank Sta=4975.7,5025.4
XS Rating Curve= 0 ,0
Exp/Cntr=0.3,0.1

Type RM Length L Ch R = 1 ,32431   ,1123,1123,1123
BEGIN DESCRIPTION:
LITTLE CANEY CREEK 34.0
END DESCRIPTION:
XS GIS Cut Line= 3
      3723417.83     10148111.04      3722541.14     10146722.14
      3721717.85     10146011.07
#Sta/Elev= 30
  3563.5  250.71  3678.6  245.87  3843.4   238.4  3962.9  233.99  4228.7  233.38
  4345.4  231.84  4433.6  233.21  4470.1  230.17  4485.4  232.19  4543.1  233.41
  4956.1   234.5  4974.2   224.7  4992.2   224.7  4998.5  229.84  5019.7  234.06
  5150.3  233.13    5202  230.42  5244.6  234.03  5322.5  231.39  5343.3  232.99
  5379.5   230.4  5414.6   232.6  5500.1  233.37  5535.3  231.55  5570.4  232.75
  5598.9  231.25  5820.2  236.54  5989.3   241.7  6145.2  247.73  6293.8  257.59
#Mann= 8 ,-1 , 0
  3563.5     .11       0  3678.6     .17       0  3843.4     .11       0
  4228.7     .15       0  4956.1     .09       0  5019.7     .15       0
  5820.2     .17       0  5989.3     .11       0
Bank Sta=4956.1,5019.7
XS Rating Curve= 0 ,0
Exp/Cntr=0.3,0.1

Type RM Length L Ch R = 1 ,31308   ,966,966,966
BEGIN DESCRIPTION:
Mapping XS 043cb405
END DESCRIPTION:
XS GIS Cut Line= 3
      3723588.04     10147899.27      3722942.18      10146508.6
       3721771.6     10145868.68
#Sta/Elev= 30
  4034.6  248.21  4309.1  235.64  4395.5  235.21  4412.6  235.37  4953.8  231.99
  4980.8  231.97  4991.4  229.64  4993.8  224.98    5012  224.98  5019.9  232.03
  5277.2  230.49  5499.8  234.68  5575.9  233.41  5607.1  227.99  5673.6  228.97
  5679.3  232.03  5695.4   228.8  5701.1  231.74    5835  227.18  5864.3  233.49
  5880.4  232.15  5886.1  226.47  5907.9  232.88  5945.8  233.98    6202  229.46
  6304.9   235.7  6319.5  236.58  6597.9  246.13  6761.3  252.75    6902   260.1
#Mann= 11 ,-1 , 0
  4034.6     .17       0  4309.1     .11       0  4395.5     .17       0
  4412.6     .11       0  4953.8     .15       0  4980.8     .09       0
  5019.9     .15       0  6304.9     .17       0  6319.5     .11       0
  6597.9     .17       0  6761.3     .11       0
Bank Sta=4980.8,5019.9
XS Rating Curve= 0 ,0
Exp/Cntr=0.3,0.1

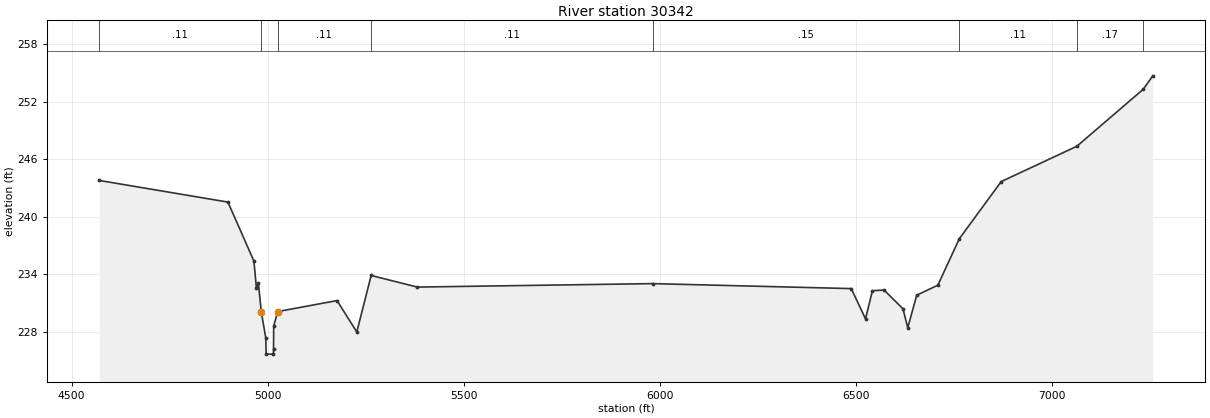
Type RM Length L Ch R = 1 ,30342   ,569,569,569
BEGIN DESCRIPTION:
LITTLE CANEY CREEK 33.0
END DESCRIPTION:
XS GIS Cut Line= 3
      3723806.77     10147341.98      3723713.02     10146649.22
      3721867.85     10145911.07
#Sta/Elev= 30
  4570.3  243.79  4898.5  241.53  4964.8  235.37  4971.1  232.57  4976.1  233.11
 4983.51230.0795    4995  227.36    4996  225.66  5014.3  225.66  5014.8  226.16
  5015.2  228.58  5025.3   230.1  5176.7  231.25  5227.1  227.97  5263.7  233.87
  5381.4  232.66  5981.7  233.02    6488   232.5  6524.3  229.34  6541.9  232.28
  6571.5  232.35  6619.9  230.39    6632  228.42  6654.9  231.81  6708.8  232.86
  6763.4   237.7  6870.3  243.67  7063.3  247.36  7232.8  253.32  7256.7  254.71
#Mann= 8 ,-1 , 0
  4570.3     .11       0 4983.51     .06       0  5025.3     .11       0
  5263.7     .11       0  5981.7     .15       0  6763.4     .11       0
  7063.3     .17       0  7232.8     .11       0
Bank Sta=4983.51,5025.3
XS Rating Curve= 0 ,0
Exp/Cntr=0.3,0.1