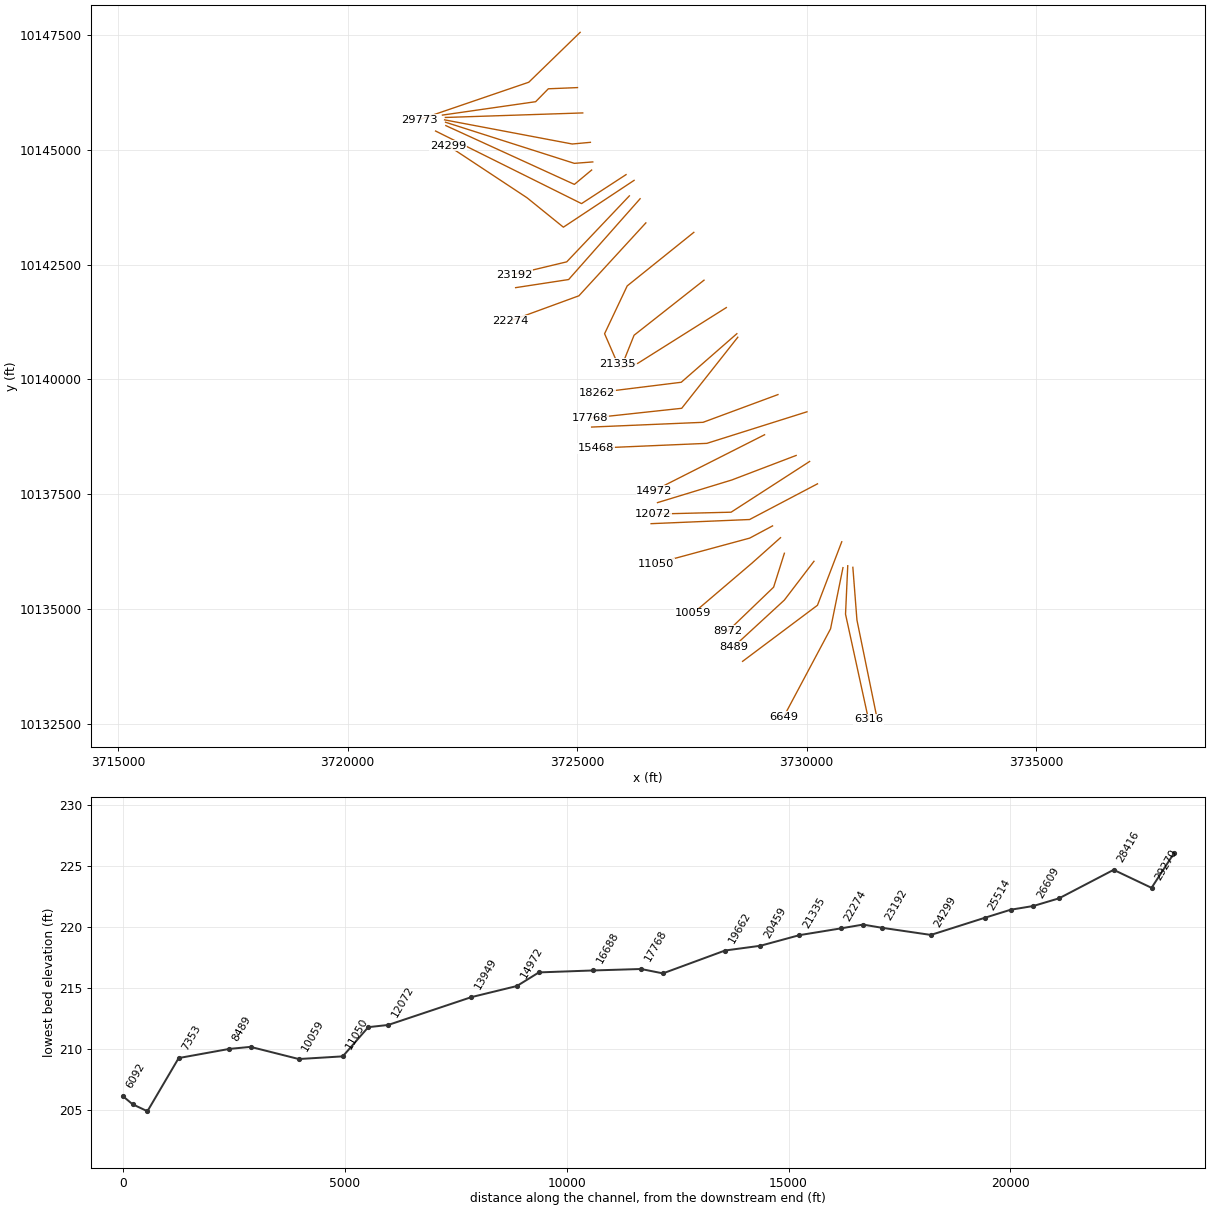
HEC-RAS study LITTLE CANEY CREEK.prj: LITTLE CANEY CREEK Base Level Engineering

--- LITTLE CANEY CREEK.g01 (geometry) --- (continued)

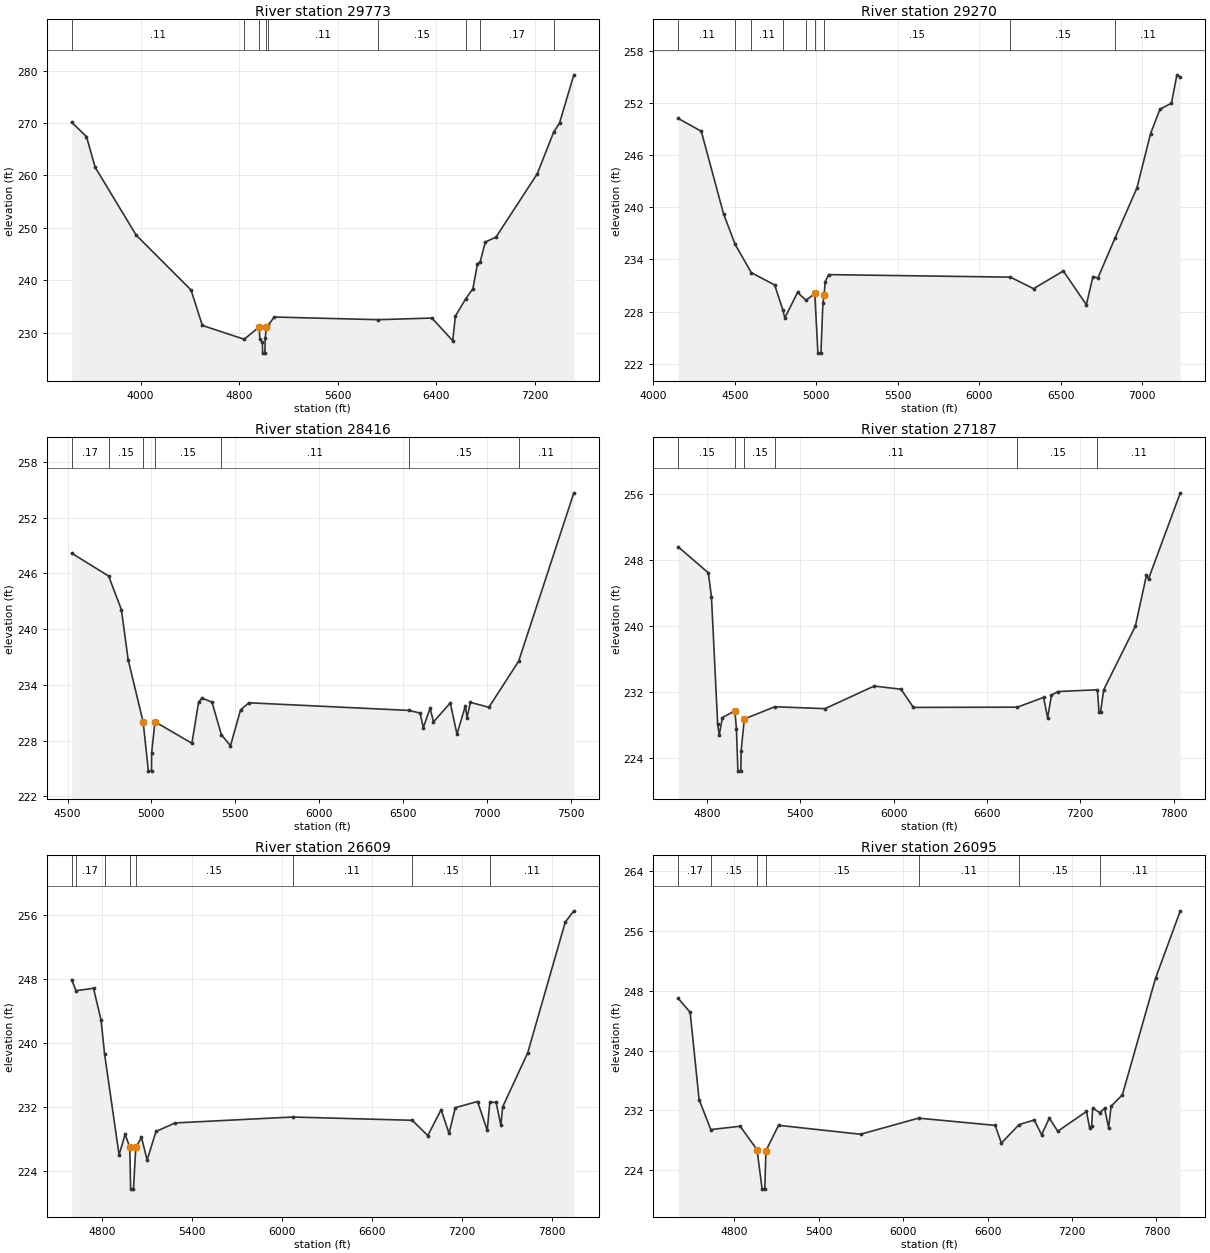
Type RM Length L Ch R = 1 ,29773   ,503,503,503
BEGIN DESCRIPTION:
LITTLE CANEY CREEK 32.0
END DESCRIPTION:
XS GIS Cut Line= 3
      3725067.84     10147561.06      3723948.57     10146474.39
      3721567.86     10145661.08
#Sta/Elev= 30
    3440  270.16  3560.2  267.43    3631  261.56  3963.3  248.62  4408.8  238.13
  4500.7  231.35    4840  228.71 4962.33231.0602  4967.5  228.82  4988.6   228.1
  4989.6  226.06  5007.9  226.06  5011.3  229.03  5021.2  231.07  5034.4  231.35
  5083.8  232.96    5926  232.45    6364  232.76    6533  228.43  6554.2  233.12
  6637.1   236.4  6696.5  238.37  6733.8  243.13    6755  243.45  6797.2  247.28
  6884.4  248.24  7218.3   260.3  7351.9  268.27  7399.6  270.02  7515.8  279.23
#Mann= 9 ,-1 , 0
    3440     .11       0    4840     .15       0 4962.33     .09       0
  5021.2     .15       0  5034.4     .11       0    5926     .15       0
  6637.1     .11       0    6755     .17       0  7351.9     .11       0
Bank Sta=4962.33,5021.2
XS Rating Curve= 0 ,0
Exp/Cntr=0.3,0.1

Type RM Length L Ch R = 1 ,29270   ,854,854,854
BEGIN DESCRIPTION:
Mapping XS 7f5975b1
END DESCRIPTION:
XS GIS Cut Line= 4
      3725009.87     10146357.55      3724374.47     10146331.51
      3724098.43     10146050.26      3722067.17      10145758.6
#Sta/Elev= 30
  4152.4  250.23  4294.5  248.75  4431.2  239.26  4502.7  235.73  4601.3  232.49
  4744.9  231.07  4794.4  228.24  4807.4  227.28  4885.3  230.21  4937.6  229.31
  4991.3  230.09  5010.3  223.23  5028.9  223.23  5040.9  228.95  5047.9  229.86
    5055  231.43  5076.2  232.26  6192.3  231.97  6333.6  230.64  6516.5  232.68
    6658   228.8  6698.4  232.04  6728.7  231.88  6834.3  236.49  6968.5  242.24
    7052  248.48  7109.5  251.28  7180.1  251.98  7213.6  255.24  7234.5  254.98
#Mann= 9 ,-1 , 0
  4152.4     .11       0  4502.7     .17       0  4601.3     .11       0
  4794.4     .17       0  4937.6     .15       0  4991.3     .09       0
  5047.9     .15       0  6192.3     .15       0  6834.3     .11       0
Bank Sta=4991.3,5047.9
XS Rating Curve= 0 ,0
Exp/Cntr=0.3,0.1

Type RM Length L Ch R = 1 ,28416   ,1229,1229,1229
BEGIN DESCRIPTION:
Mapping XS c1141ef3
END DESCRIPTION:
XS GIS Cut Line= 2
      3725124.51     10145805.47      3722131.25     10145706.57
#Sta/Elev= 30
  4524.6  248.18  4745.1  245.72  4821.4   242.1  4861.4  236.73 4951.37229.9665
  4982.1  224.71  5000.9  224.71  5001.5  226.65  5021.5  230.03  5241.7  227.71
  5281.7  232.14  5301.7  232.57  5361.7  232.14  5417.5  228.63  5471.8  227.44
  5531.8   231.3  5581.8  232.07  6534.8  231.25  6602.4  230.97  6621.7  229.39
  6662.4   231.5  6682.4  230.01  6782.5  232.05  6822.5   228.7  6872.5  231.72
  6882.5  230.48  6902.6  232.12  7012.6  231.58  7190.4  236.55  7519.5  254.68
#Mann= 7 ,-1 , 0
  4524.6     .17       0  4745.1     .15       0 4951.37     .09       0
  5021.5     .15       0  5417.5     .11       0  6534.8     .15       0
  7190.4     .11       0
Bank Sta=4951.37,5021.5
XS Rating Curve= 0 ,0
Exp/Cntr=0.3,0.1

Type RM Length L Ch R = 1 ,27187   ,578,578,578
BEGIN DESCRIPTION:
LITTLE CANEY CREEK 31.0
END DESCRIPTION:
XS GIS Cut Line= 3
      3725291.15     10145164.85      3724895.31     10145128.39
      3722114.04     10145654.43
#Sta/Elev= 30
  4615.3  249.55  4809.4   246.4  4829.5  243.52  4869.7  228.04  4879.7  226.75
  4899.8  228.86  4980.1  229.67  4990.2  227.49  4999.6  222.37  5018.4  222.37
  5020.4  224.83  5040.8  228.69  5236.8  230.17  5559.8  229.94  5875.3  232.68
  6048.3  232.29  6127.5  230.09  6796.2  230.12  6964.3   231.3  6990.5  228.84
  7015.2  231.56  7055.9  232.01  7310.8  232.23  7320.5  229.51  7330.7  229.54
    7351  232.23  7554.6  239.94  7625.8   246.1    7639  245.66  7843.4  256.09
#Mann= 6 ,-1 , 0
  4615.3     .15       0  4980.1     .09       0  5040.8     .15       0
  5236.8     .11       0  6796.2     .15       0  7310.8     .11       0
Bank Sta=4980.1,5040.8
XS Rating Curve= 0 ,0
Exp/Cntr=0.3,0.1

Type RM Length L Ch R = 1 ,26609   ,514,514,514
BEGIN DESCRIPTION:
LITTLE CANEY CREEK 30.0
END DESCRIPTION:
XS GIS Cut Line= 3
      3725343.24     10144737.76      3724940.42     10144706.86
      3722134.87     10145602.35
#Sta/Elev= 30
    4596  247.95  4625.2  246.56  4741.8  246.86    4792   242.9  4815.8  238.61
  4912.3  226.02  4952.4  228.59 4983.54227.0053  4989.4  221.74  5008.2  221.74
  5023.7  226.95  5061.8   228.2  5099.2  225.38  5158.4  228.95  5286.1  230.02
    6069  230.76  6867.6  230.35  6970.8  228.44  7060.1  231.68  7112.6  228.71
  7154.6  231.93  7303.1   232.7  7367.5  229.09  7384.7  232.61  7426.7   232.6
  7458.8   229.7  7469.5  231.99  7637.5   238.8  7887.8  255.14    7945  256.55
#Mann= 8 ,-1 , 0
    4596     .15       0  4625.2     .17       0  4815.8     .15       0
 4983.54     .09       0  5023.7     .15       0    6069     .11       0
  6867.6     .15       0  7384.7     .11       0
Bank Sta=4983.54,5023.7
XS Rating Curve= 0 ,0
Exp/Cntr=0.3,0.1

Type RM Length L Ch R = 1 ,26095   ,581,581,581
BEGIN DESCRIPTION:
LITTLE CANEY CREEK 29.0
END DESCRIPTION:
XS GIS Cut Line= 3
      3725317.87     10144561.09      3724942.18     10144248.18
       3722141.5     10145528.79
#Sta/Elev= 30
    4401  246.98  4486.3  245.13  4550.1  233.43    4633  229.41  4841.7  229.85
  4961.6  226.72  4998.2  221.43    5017  221.43  5025.1  226.58  5114.6  229.98
  5697.2  228.78  6109.4  230.94    6654  229.97    6698   227.6  6824.1  230.08
  6931.7  230.69  6983.9  228.71  7038.9  230.95  7098.3  229.18  7302.8  231.83
  7324.8  229.66  7339.5  229.89  7346.8  232.29  7396.3  231.68  7431.6  232.26
  7460.1  229.62  7477.6  232.53  7557.7  234.06  7793.4  249.67  7969.5  258.71
#Mann= 7 ,-1 , 0
    4401     .17       0    4633     .15       0  4961.6     .09       0
  5025.1     .15       0  6109.4     .11       0  6824.1     .15       0
  7396.3     .11       0
Bank Sta=4961.6,5025.1
XS Rating Curve= 0 ,0
Exp/Cntr=0.3,0.1

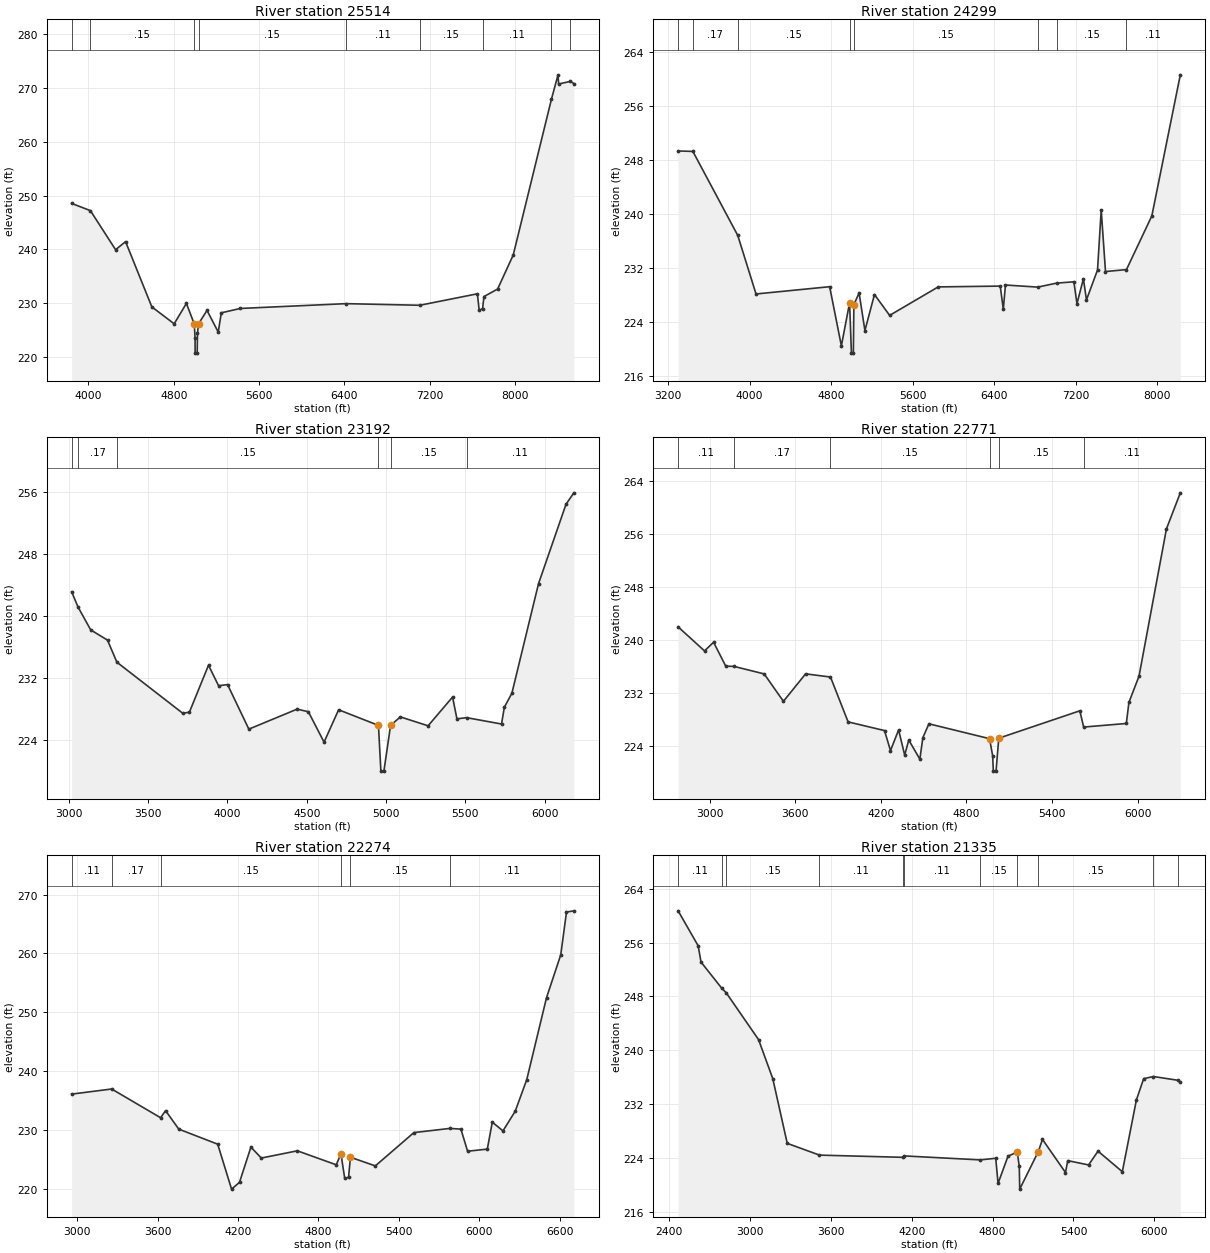
Type RM Length L Ch R = 1 ,25514   ,1215,1215,1215
BEGIN DESCRIPTION:
LITTLE CANEY CREEK 28.0
END DESCRIPTION:
XS GIS Cut Line= 3
      3726067.89      10144461.1      3725098.31      10143829.6
      3721917.89     10145411.05
#Sta/Elev= 30
  3842.9  248.55  4018.7  247.21  4254.9  239.96  4348.5  241.46  4594.8  229.35
  4804.3  226.21  4918.9     230 4993.14226.1545    5000  223.56  5000.8  220.77
  5019.8  220.77  5022.8  224.45  5032.7  226.21  5112.2   228.7  5217.5  224.67
  5246.2  228.25  5424.9  229.06  6416.2  229.95  7107.5  229.65  7647.6  231.78
  7664.4  228.69  7696.3  229.05  7709.2  231.27  7837.2  232.66  7983.6  238.98
  8341.7  267.87  8403.6  272.41  8409.2   270.7  8519.9   271.2  8551.9  270.79
#Mann= 9 ,-1 , 0
  3842.9     .17       0  4018.7     .15       0 4993.14     .09       0
  5032.7     .15       0  6416.2     .11       0  7107.5     .15       0
  7696.3     .11       0  8341.7     .17       0  8519.9     .11       0
Bank Sta=4993.14,5032.7
XS Rating Curve= 0 ,0
Exp/Cntr=0.3,0.1

Type RM Length L Ch R = 1 ,24299   ,1107,1107,1107
BEGIN DESCRIPTION:
LITTLE CANEY CREEK 27.0
END DESCRIPTION:
XS GIS Cut Line= 4
      3726242.87     10144336.08       3724702.6     10143315.89
      3723910.93     10143956.51      3722192.52     10145091.71
#Sta/Elev= 30
  3298.6  249.37  3443.4   249.3  3883.6  236.83  4062.7  228.14  4784.8  229.22
  4899.9  220.44  4980.3  226.83  4998.3  219.36  5017.3  219.36  5022.4  226.55
  5073.6   228.3  5130.7  222.71  5224.4  228.06  5373.1  224.96  5849.6  229.19
  6457.9  229.31    6488  225.87  6509.1  229.47  6826.3  229.16  7010.4  229.75
  7180.3  229.95  7210.4   226.7  7273.6  230.39  7303.7  227.27  7412.1   231.7
  7448.2  240.61  7490.3  231.47    7696  231.76  7944.8  239.73    8224  260.67
#Mann= 8 ,-1 , 0
  3298.6     .11       0  3443.4     .17       0  3883.6     .15       0
  4980.3     .09       0  5022.4     .15       0  6826.3     .11       0
  7010.4     .15       0    7696     .11       0
Bank Sta=4980.3,5022.4
XS Rating Curve= 0 ,0
Exp/Cntr=0.3,0.1

Type RM Length L Ch R = 1 ,23192   ,421,421,421
BEGIN DESCRIPTION:
LITTLE CANEY CREEK 26.0
END DESCRIPTION:
XS GIS Cut Line= 3
      3726140.12      10143998.2      3724775.52     10142560.68
      3723624.43     10142284.63
#Sta/Elev= 30
  3017.8   243.1  3058.1  241.13  3137.8  238.18  3243.8  236.86  3302.9  234.01
  3717.5  227.43  3759.9  227.55  3880.5  233.62    3944  230.97  4000.6  231.12
  4134.9  225.37  4439.1  227.95  4509.9  227.62    4609  223.69  4700.8  227.87
 4951.93 225.851  4967.2  219.95  4986.2  219.95  5028.3  225.85    5090  226.95
  5264.8   225.8  5419.1  229.51  5446.6   226.7  5508.3  226.85  5727.6  226.03
  5745.8  228.21    5793     230    5961  244.15  6134.2  254.39  6183.6  255.87
#Mann= 6 ,-1 , 0
  3017.8     .11       0  3058.1     .17       0  3302.9     .15       0
 4951.93     .09       0  5028.3     .15       0  5508.3     .11       0
Bank Sta=4951.93,5028.3
XS Rating Curve= 0 ,0
Exp/Cntr=0.3,0.1

Type RM Length L Ch R = 1 ,22771   ,497,497,497
BEGIN DESCRIPTION:
LITTLE CANEY CREEK 25.0
END DESCRIPTION:
XS GIS Cut Line= 3
      3726374.47     10143935.68      3724817.18     10142175.26
      3723661.92     10141998.33
#Sta/Elev= 30
  2779.3  241.95  2964.3  238.33  3027.8  239.63  3113.2  236.03  3171.2  235.99
  3382.5  234.86  3517.2  230.73  3672.8  234.87  3847.1  234.39  3970.5  227.63
  4225.7  226.32  4267.5   223.3  4324.4  226.42    4367  222.62  4395.5   224.9
  4473.3  222.01  4494.4  225.26  4536.8  227.34  4961.7   225.1  4983.5  222.52
  4988.2  220.21  5007.2  220.21  5026.2  225.17  5594.4   229.3    5621  226.85
  5920.1  227.39  5938.3  230.57  6009.1  234.52  6201.3  256.72  6298.4  262.15
#Mann= 6 ,-1 , 0
  2779.3     .11       0  3171.2     .17       0  3847.1     .15       0
  4961.7     .09       0  5026.2     .15       0    5621     .11       0
Bank Sta=4961.7,5026.2
XS Rating Curve= 0 ,0
Exp/Cntr=0.3,0.1

Type RM Length L Ch R = 1 ,22274   ,939,939,939
BEGIN DESCRIPTION:
LITTLE CANEY CREEK 24.0
END DESCRIPTION:
XS GIS Cut Line= 3
      3726499.46     10143409.62      3725041.14      10141821.1
      3723546.35     10141274.22
#Sta/Elev= 30
  2958.2  236.07  3256.9  236.94  3622.1  232.05  3659.1  233.26  3757.8  230.11
  4048.2  227.55  4151.7   219.9    4211  221.06  4296.1  227.05  4373.8  225.19
  4642.6  226.42    4933  224.04  4968.2   225.9  4996.5  221.71  5024.9  221.93
  5039.1  225.33  5224.6  223.85  5512.5  229.52  5780.7  230.23  5863.5  230.11
  5913.2  226.35  6060.5  226.71  6097.7   231.3  6177.3  229.81  6268.9  233.16
  6355.1  238.55  6502.4  252.48  6608.6  259.77  6651.5  267.05  6706.3  267.26
#Mann= 6 ,-1 , 0
  2958.2     .11       0  3256.9     .17       0  3622.1     .15       0
  4968.2     .09       0  5039.1     .15       0  5780.7     .11       0
Bank Sta=4968.2,5039.1
XS Rating Curve= 0 ,0
Exp/Cntr=0.3,0.1

Type RM Length L Ch R = 1 ,21335   ,876,876,876
BEGIN DESCRIPTION:
Mapping XS d066ba0c
END DESCRIPTION:
XS GIS Cut Line= 4
      3727544.58     10143203.01      3726093.22     10142036.37
      3725600.17     10140994.71      3725884.91     10140341.88
#Sta/Elev= 30
  2466.1  260.74  2615.1  255.53    2636  253.12  2790.9   249.2  2822.7  248.56
  3063.1  241.58  3168.7  235.77  3275.9  226.15  3515.1   224.4  4136.8  224.07
  4143.8  224.28  4708.3  223.69  4823.2  223.93  4840.4  220.19  4914.2  224.24
  4982.4  224.85  4997.9  222.74  5001.2  219.34 5138.86224.9156    5170  226.74
  5340.9  221.81  5357.5  223.58  5512.2  222.94  5582.4  224.99  5762.7  221.93
  5867.3  232.63    5921  235.77  5993.6  236.09  6175.9  235.53  6192.9  235.23
#Mann= 11 ,-1 , 0
  2466.1     .11       0  2790.9     .17       0  2822.7     .15       0
  3515.1     .11       0  4136.8     .15       0  4143.8     .11       0
  4708.3     .15       0  4982.4     .09       0 5138.86     .15       0
  5993.6     .17       0  6175.9     .11       0
Bank Sta=4982.4,5138.86
XS Rating Curve= 0 ,0
Exp/Cntr=0.3,0.1

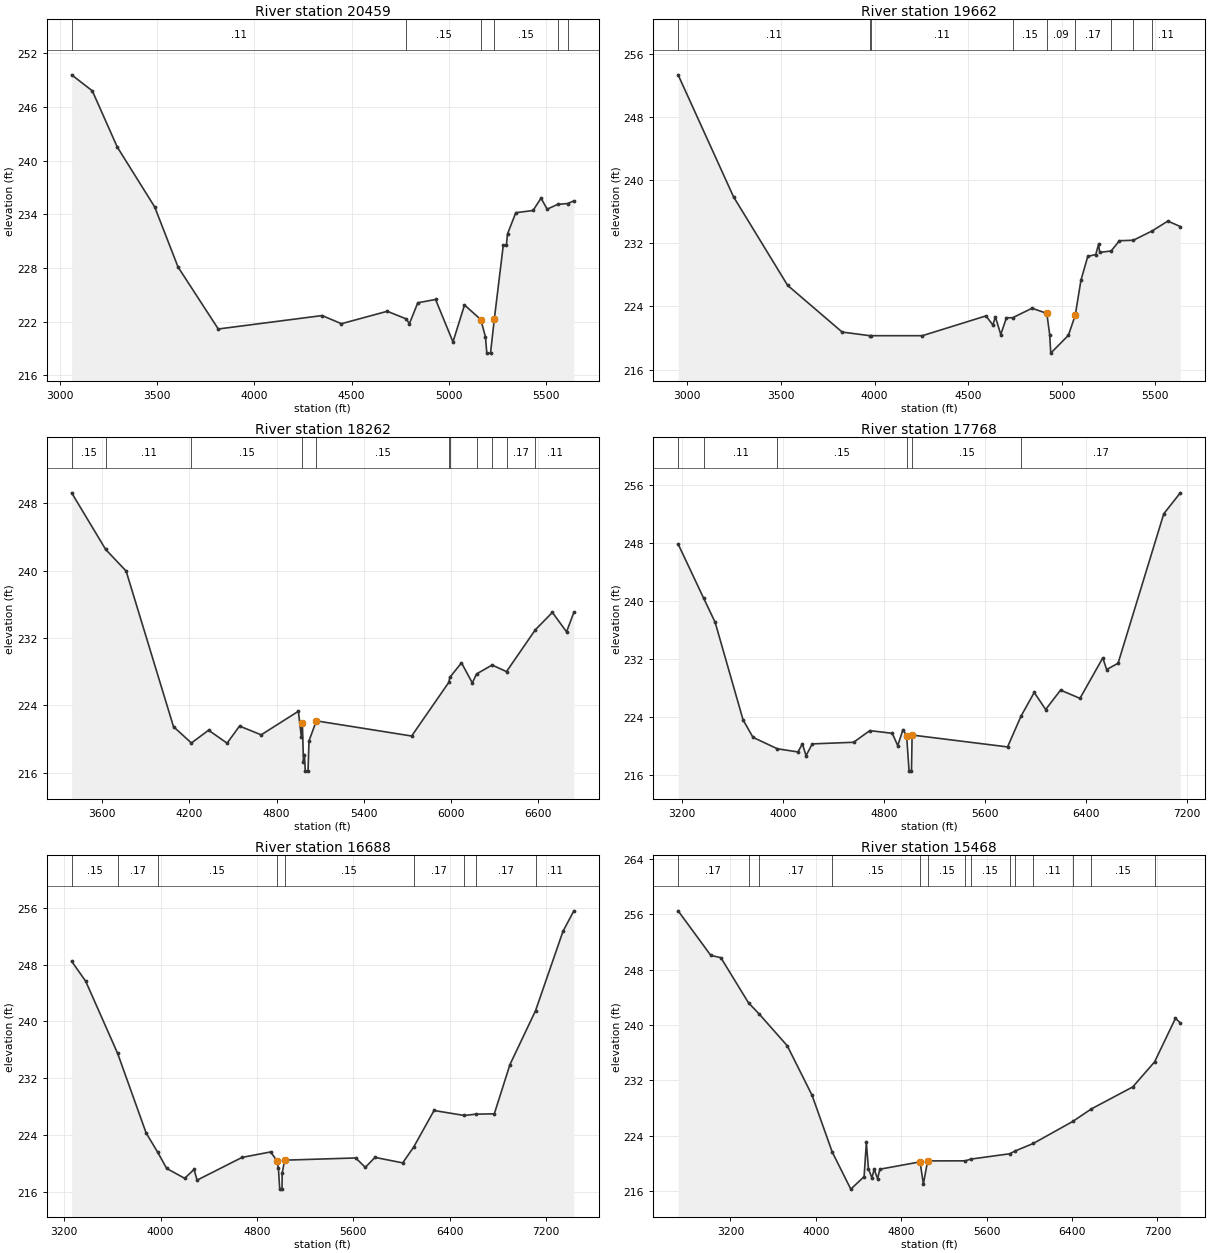
Type RM Length L Ch R = 1 ,20459   ,797,797,797
BEGIN DESCRIPTION:
LITTLE CANEY CREEK 23.0
END DESCRIPTION:
XS GIS Cut Line= 3
      3727766.82     10142161.36      3726242.74     10140961.36
      3726003.59     10140364.38
#Sta/Elev= 30
  3060.2  249.59  3166.4   247.8  3294.7  241.52  3487.2  234.82  3607.4   228.1
  3814.3  221.17  4348.3  222.67  4447.7  221.76  4683.5  223.15  4780.6   222.3
  4797.3  221.76  4840.6   224.1    4932  224.47  5021.5  219.72  5080.7  223.85
  5164.2  222.23  5188.4   220.3  5195.5  218.47  5214.5  218.47 5234.46222.3374
  5280.4  230.57    5296  230.51  5301.9   231.8  5344.5  234.17  5433.3  234.42
  5474.3   235.8  5505.9  234.57  5559.7   235.1  5610.9   235.2  5643.1  235.49
#Mann= 6 ,-1 , 0
  3060.2     .11       0  4780.6     .15       0  5164.2     .09       0
 5234.46     .15       0  5559.7     .17       0  5610.9     .11       0
Bank Sta=5164.2,5234.46
XS Rating Curve= 0 ,0
Exp/Cntr=0.3,0.1

Type RM Length L Ch R = 1 ,19662   ,1400,1400,1400
BEGIN DESCRIPTION:
Mapping XS c4b4fec1
END DESCRIPTION:
XS GIS Cut Line= 3
      3728252.93     10141564.14      3726322.39     10140348.87
       3725933.5     10140244.71
#Sta/Elev= 30
  2950.3  253.36  3246.4   237.9  3535.3  226.68  3826.9  220.75  3975.3  220.29
  3981.6  220.29  4255.4  220.29  4595.7   222.8  4632.2  221.65    4646  222.67
  4674.6  220.44  4705.1  222.57  4737.4  222.56  4841.8  223.77  4920.7  223.12
    4936  220.44  4941.8  218.08  5036.1  220.34  5072.6  222.89  5103.2  227.33
  5139.7  230.35  5182.1  230.57  5197.4  231.88  5203.3  230.85  5264.4  231.03
  5308.7  232.33    5383  232.39  5484.2  233.58  5567.5  234.82  5634.1  234.13
#Mann= 9 ,-1 , 0
  2950.3     .11       0  3975.3     .15       0  3981.6     .11       0
  4737.4     .15       0  4920.7     .09       0  5072.6     .17       0
  5264.4     .15       0    5383     .17       0  5484.2     .11       0
Bank Sta=4920.7,5072.6
XS Rating Curve= 0 ,0
Exp/Cntr=0.3,0.1

Type RM Length L Ch R = 1 ,18262   ,494,494,494
BEGIN DESCRIPTION:
LITTLE CANEY CREEK 22.0
END DESCRIPTION:
XS GIS Cut Line= 3
      3728482.11     10140994.71      3727270.62     10139936.77
      3725441.61     10139710.13
#Sta/Elev= 30
  3391.6  249.25  3625.3  242.53    3766  239.96  4091.6  221.48  4214.5  219.54
  4332.7  221.06  4459.9  219.52  4545.3  221.55  4694.3  220.51  4949.7  223.31
  4970.6  220.23  4977.2  221.95  4984.8  217.32  4991.4  218.17  4997.2   216.2
  5016.2   216.2  5022.9   219.8  5073.3  222.17  5728.3  220.37  5984.3  226.76
  5990.3  227.33  6070.9  229.06  6145.3  226.68  6174.4  227.74  6281.2   228.8
  6380.2  228.02  6578.1  232.98  6695.6  235.05    6793  232.74    6843  235.05
#Mann= 11 ,-1 , 0
  3391.6     .15       0  3625.3     .11       0  4214.5     .15       0
  4977.2     .09       0  5073.3     .15       0  5984.3     .17       0
  5990.3     .15       0  6174.4     .17       0  6281.2     .11       0
  6380.2     .17       0  6578.1     .11       0
Bank Sta=4977.2,5073.3
XS Rating Curve= 0 ,0
Exp/Cntr=0.3,0.1

Type RM Length L Ch R = 1 ,17768   ,1080,1080,1080
BEGIN DESCRIPTION:
LITTLE CANEY CREEK 21.0
END DESCRIPTION:
XS GIS Cut Line= 3
      3728502.92     10140918.28      3727280.72     10139369.71
      3725287.69     10139154.43
#Sta/Elev= 30
    3167   247.9  3368.4  240.45  3460.2   237.1  3681.5  223.63  3760.1  221.22
  3953.8  219.64    4116  219.21  4151.2  220.32  4180.1   218.7  4229.8  220.32
  4556.8  220.54  4685.1  222.15    4863  221.78  4906.4  220.08    4948  222.29
  4976.9  221.44  4996.2  216.56  5015.2  216.56  5020.2  221.54  5776.3   219.9
  5882.6  224.14  5987.5  227.42  6078.1  225.06  6195.8  227.74  6349.6   226.6
  6530.7  232.19  6560.9  230.58  6651.4  231.44  7013.5  252.07  7144.4  254.96
#Mann= 6 ,-1 , 0
    3167     .15       0  3368.4     .11       0  3953.8     .15       0
  4976.9     .09       0  5020.2     .15       0  5882.6     .17       0
Bank Sta=4976.9,5020.2
XS Rating Curve= 0 ,0
Exp/Cntr=0.3,0.1

Type RM Length L Ch R = 1 ,16688   ,1220,1220,1220
BEGIN DESCRIPTION:
LITTLE CANEY CREEK 20.0
END DESCRIPTION:
XS GIS Cut Line= 3
      3729377.93     10139668.31        3727746.     10139064.15
      3725317.86     10138961.07
#Sta/Elev= 30
  3260.6  248.46  3377.5  245.65  3642.6  235.51  3879.2  224.33  3973.9  221.66
  4049.9  219.35    4199  217.96  4277.1  219.21  4302.2   217.7    4676   220.9
  4913.8  221.67    4964  220.45  4977.5  219.43  4988.5  216.44  5007.5  216.44
  5008.9  218.66  5028.9  220.51  5619.5  220.82  5699.5   219.5  5779.6   220.9
  6009.8  220.13  6101.6  222.37  6270.1  227.49  6521.5  226.79  6620.1  226.98
  6770.5  227.02  6900.6  233.95  7113.1  241.52    7341  252.67  7431.1  255.55
#Mann= 9 ,-1 , 0
  3260.6     .15       0  3642.6     .17       0  3973.9     .15       0
    4964     .09       0  5028.9     .15       0  6101.6     .17       0
  6521.5     .15       0  6620.1     .17       0  7113.1     .11       0
Bank Sta=4964,5028.9
XS Rating Curve= 0 ,0
Exp/Cntr=0.3,0.1

Type RM Length L Ch R = 1 ,15468   ,496,496,496
BEGIN DESCRIPTION:
LITTLE CANEY CREEK 19.0
END DESCRIPTION:
XS GIS Cut Line= 3
      3730009.88     10139293.32      3727829.33     10138605.82
      3725412.74     10138501.66
#Sta/Elev= 30
  2709.7   256.5  3015.9  250.06  3110.3  249.73  3369.4   243.2  3471.7  241.55
  3732.8  236.99  3964.5  229.85  4153.2  221.66  4327.5  216.28  4452.4  218.09
  4473.4  223.02  4492.7  219.26  4525.1   217.9  4546.7  219.16  4578.2  217.79
  4600.3  219.16  4976.6  220.22  5007.6  217.02  5047.6  220.36  5400.6  220.37
  5452.4  220.62  5815.9  221.39  5869.8  221.81  6037.5  222.88  6410.1  226.09
  6581.3  227.87  6969.4  231.05    7174  234.67  7369.7  240.97  7414.9  240.31
#Mann= 14 ,-1 , 0
  2709.7     .17       0  3369.4     .11       0  3471.7     .17       0
  4153.2     .15       0  4976.6     .09       0  5047.6     .15       0
  5400.6     .11       0  5452.4     .15       0  5815.9     .11       0
  5869.8     .15       0  6037.5     .11       0  6410.1     .17       0
  6581.3     .15       0    7174     .11       0
#Block Obstruct= 2 , 0
         4470.35  222.81
Bank Sta=4976.6,5047.6
XS Rating Curve= 0 ,0
Exp/Cntr=0.3,0.1

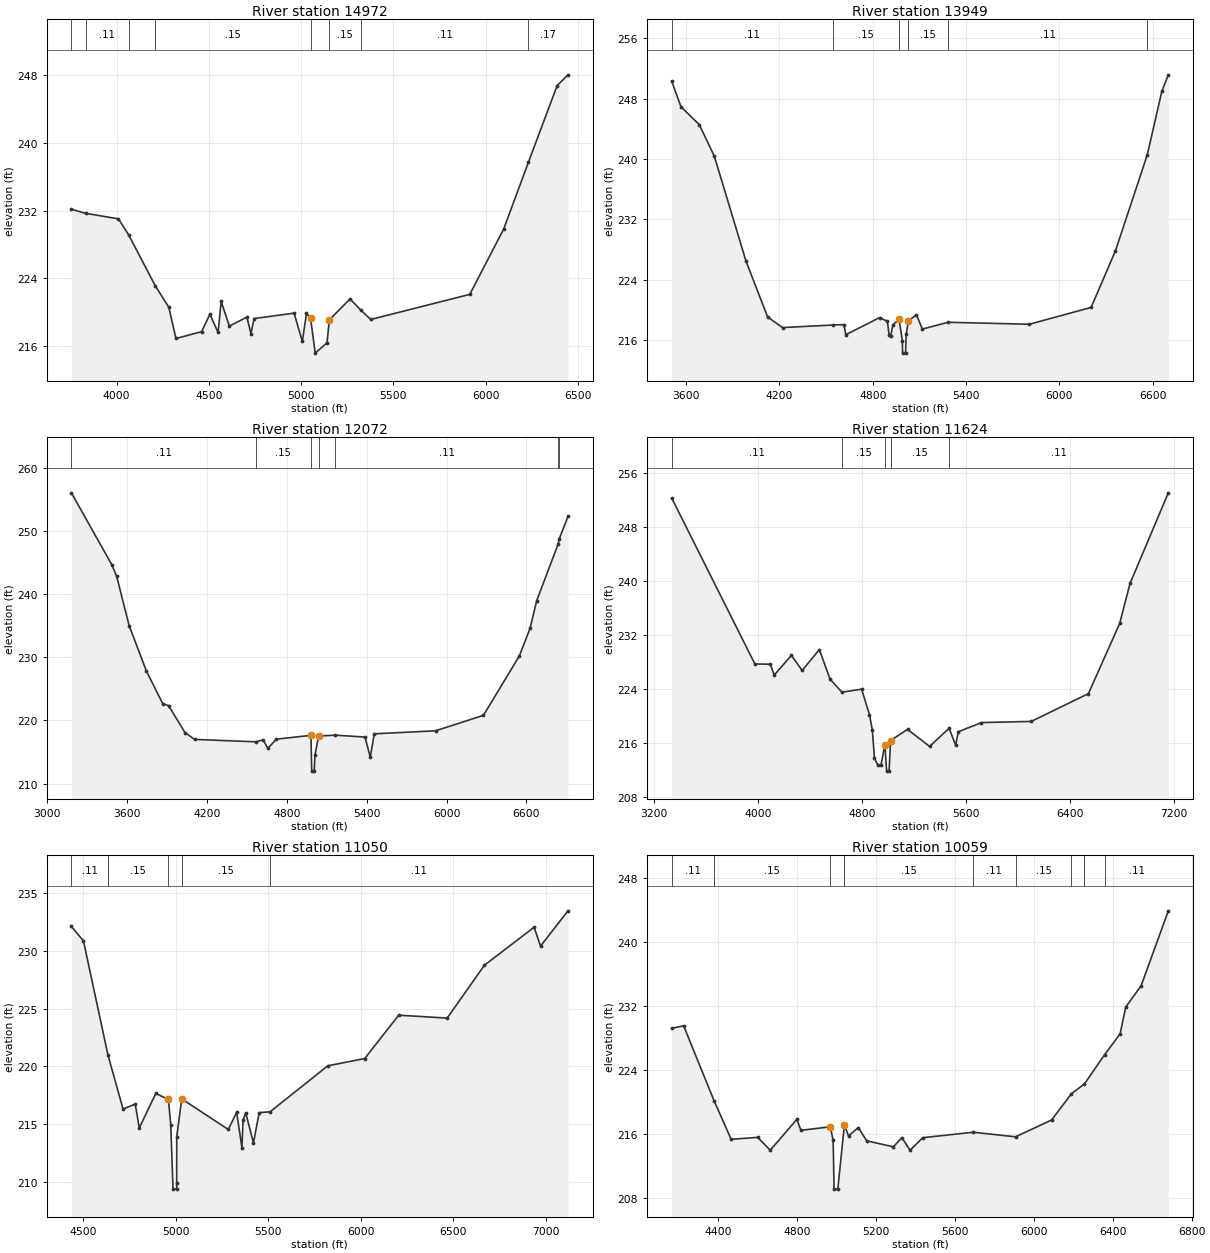
Type RM Length L Ch R = 1 ,14972   ,1023,1023,1023
BEGIN DESCRIPTION:
Mapping XS aeb53616
END DESCRIPTION:
XS GIS Cut Line= 2
      3729086.27     10138793.31      3726683.51     10137578.05
#Sta/Elev= 30
  3754.4  232.17  3832.1  231.69  4009.5  231.04  4064.9  229.15    4209  223.13
  4282.5   220.6  4321.4  216.89  4460.8   217.7  4505.3  219.76  4549.9   217.6
  4566.6  221.27  4611.1  218.36  4705.9  219.41  4728.2  217.47  4744.9  219.25
  4962.1  219.89  5006.7  216.54    5029  219.85  5051.2   219.3  5076.7  215.16
  5140.4  216.39  5153.4   219.1  5265.5  221.57  5324.5  220.23  5377.5  219.14
  5914.7  222.11  6098.6  229.85  6232.3  237.72  6388.3   246.8    6447  248.07
#Mann= 8 ,-1 , 0
  3754.4     .17       0  3832.1     .11       0  4064.9     .17       0
    4209     .15       0  5051.2     .09       0  5153.4     .15       0
  5324.5     .11       0  6232.3     .17       0
#Block Obstruct= 2 , 0
          4566.6  221.28
Bank Sta=5051.2,5153.4
XS Rating Curve= 0 ,0
Exp/Cntr=0.3,0.1

Type RM Length L Ch R = 1 ,13949   ,1877,1877,1877
BEGIN DESCRIPTION:
LITTLE CANEY CREEK 18.0
END DESCRIPTION:
XS GIS Cut Line= 3
      3729773.76     10138341.92        3728371.     10137807.21
      3726752.97     10137314.16
#Sta/Elev= 30
  3507.3  250.32  3567.1  246.92  3684.9  244.54  3781.5  240.36  3984.5  226.48
  4123.6  219.06    4220  217.64  4543.7  217.98  4614.6  218.03  4626.6  216.69
  4844.6  218.97  4894.1  218.46  4904.9  216.68  4915.6  216.52  4929.6  218.02
  4969.1  218.71  4990.5  215.85  4991.7  214.25  5010.7  214.25  5014.7  216.75
 5029.48218.5188  5080.4  219.36  5118.5  217.44    5284  218.34  5806.5  218.08
  6203.6  220.31  6360.4  227.83  6564.8  240.55  6658.7  249.01    6700  251.16
#Mann= 6 ,-1 , 0
  3507.3     .11       0  4543.7     .15       0  4969.1     .09       0
 5029.48     .15       0    5284     .11       0  6564.8     .17       0
Bank Sta=4969.1,5029.48
XS Rating Curve= 0 ,0
Exp/Cntr=0.3,0.1

Type RM Length L Ch R = 1 ,12072   ,448,448,448
BEGIN DESCRIPTION:
LITTLE CANEY CREEK 17.0
END DESCRIPTION:
XS GIS Cut Line= 3
      3730067.86     10138211.08      3728357.11     10137105.82
      3726662.75     10137064.15
#Sta/Elev= 30
  3180.9  256.01  3484.7  244.63    3521  242.82  3614.7  235.01  3744.7   227.8
  3868.7  222.59    3911  222.34    4035  218.05  4107.5  216.98  4566.2   216.6
  4621.5  216.91  4657.2  215.56  4721.1  217.02  4981.1  217.62  4986.8  211.96
  5005.8  211.96  5011.4  214.53  5038.5  217.53  5165.5  217.65  5386.9  217.35
    5427  214.17    5457  217.87  5917.1  218.34  6277.2  220.79  6547.3   230.2
  6627.3  234.54  6677.3  238.93  6837.6  247.85  6847.6  248.78  6912.5  252.27
#Mann= 7 ,-1 , 0
  3180.9     .11       0  4566.2     .15       0  4981.1     .09       0
  5038.5     .15       0  5165.5     .11       0  6837.6     .17       0
  6847.6     .11       0
Bank Sta=4981.1,5038.5
XS Rating Curve= 0 ,0
Exp/Cntr=0.3,0.1

Type RM Length L Ch R = 1 ,11624   ,574,574,574
BEGIN DESCRIPTION:
LITTLE CANEY CREEK 16.0
END DESCRIPTION:
XS GIS Cut Line= 3
      3730239.05     10137723.87      3728759.89      10136946.1
      3726614.07     10136855.82
#Sta/Elev= 30
  3337.9  252.34  3977.7  227.69  4096.2  227.66  4126.3  226.05  4258.6  228.97
  4341.1  226.73  4473.3  229.83  4555.9  225.43  4647.1   223.5  4798.3  223.95
  4858.8  220.17  4880.8  217.89  4897.2  213.67  4924.9  212.63    4947  212.67
  4977.5  215.72  4990.6  211.78  5009.6  211.78  5021.1  216.32  5151.2  217.98
  5321.4  215.45  5471.4  218.15  5521.6  215.62  5541.6  217.63  5720.1  218.99
  6102.1  219.16  6542.5  223.29  6782.7  233.71  6862.8  239.67  7156.8  253.11
#Mann= 5 ,-1 , 0
  3337.9     .11       0  4647.1     .15       0  4977.5     .09       0
  5021.1     .15       0  5471.4     .11       0
Bank Sta=4977.5,5021.1
XS Rating Curve= 0 ,0
Exp/Cntr=0.3,0.1

Type RM Length L Ch R = 1 ,11050   ,991,991,991
BEGIN DESCRIPTION:
LITTLE CANEY CREEK 15.0
END DESCRIPTION:
XS GIS Cut Line= 3
      3729259.89     10136807.21      3728762.93     10136541.35
      3726718.24     10135987.77
#Sta/Elev= 30
  4436.4  232.11  4501.7  230.86  4633.8  220.99  4715.5  216.31  4781.3  216.74
  4803.2  214.67  4892.3  217.66  4960.4  217.14  4973.1  214.95  4985.5  209.38
  5004.5  209.38    5005  209.88  5005.3  213.89 5032.39 217.187  5283.9  214.54
    5329  216.03  5357.5  212.96  5363.6  215.36  5378.2  215.97  5419.7  213.38
  5450.7     216  5509.4  216.07  5821.2  220.05  6020.5  220.68  6204.1  224.43
    6466  224.18  6666.8  228.75  6935.4  232.04  6970.1  230.41  7118.3  233.46
#Mann= 5 ,-1 , 0
  4436.4     .11       0  4633.8     .15       0  4960.4     .09       0
 5032.39     .15       0  5509.4     .11       0
Bank Sta=4960.4,5032.39
XS Rating Curve= 0 ,0
Exp/Cntr=0.3,0.1

Type RM Length L Ch R = 1 ,10059   ,1087,1087,1087
BEGIN DESCRIPTION:
LITTLE CANEY CREEK 14.0
END DESCRIPTION:
XS GIS Cut Line= 3
      3729433.49     10136550.25      3728810.79     10135995.15
      3727530.75     10134904.45
#Sta/Elev= 30
  4165.8  229.23  4226.2  229.55  4380.2  220.21    4467  215.38  4601.6  215.62
  4665.2  214.02  4799.8  217.87  4820.7   216.5  4969.5  216.94  4983.7  215.24
  4988.4  209.16  5007.4  209.16  5040.8  217.21  5061.6  215.79    5111  216.85
  5153.9  215.19  5288.9  214.44  5331.8  215.59  5373.5  214.01  5437.4  215.58
  5693.7  216.26  5907.7  215.69  6090.5  217.79  6190.6  221.06  6256.5  222.28
  6359.6  225.96  6437.5  228.54    6466  231.89    6544  234.55  6681.7   243.9
#Mann= 9 ,-1 , 0
  4165.8     .11       0  4380.2     .15       0  4969.5     .09       0
  5040.8     .15       0  5693.7     .11       0  5907.7     .15       0
  6190.6     .11       0  6256.5     .15       0  6359.6     .11       0
Bank Sta=4969.5,5040.8
XS Rating Curve= 0 ,0
Exp/Cntr=0.3,0.1

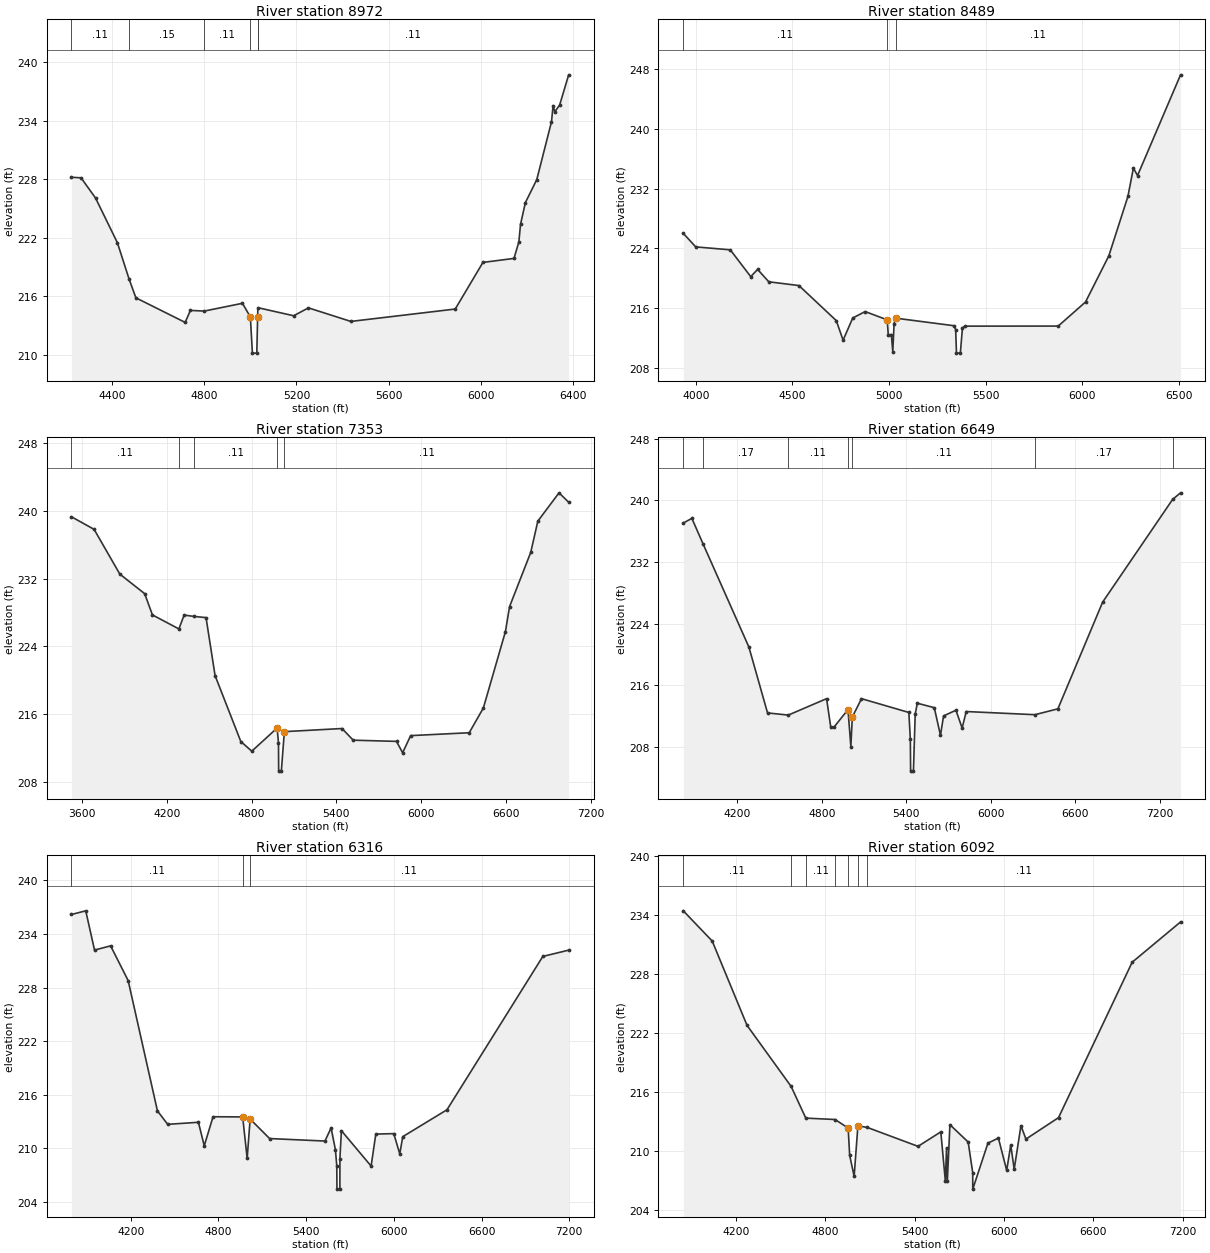
Type RM Length L Ch R = 1 ,8972    ,483,483,483
BEGIN DESCRIPTION:
LITTLE CANEY CREEK 13.0
END DESCRIPTION:
XS GIS Cut Line= 3
      3729517.84     10136211.05      3729283.19     10135471.59
      3728287.92     10134515.78
#Sta/Elev= 30
  4224.2  228.19  4266.1  228.13  4329.1  226.05  4423.5  221.48  4474.6  217.73
  4503.7  215.83  4717.3  213.31  4740.1  214.54    4800  214.47  4965.9  215.27
    5000  213.86  5008.9  210.16  5027.9  210.16 5031.55213.8559  5032.5  214.82
  5187.9  213.99  5251.7   214.8  5435.7  213.41  5888.2  214.68  6008.3  219.46
  6142.9  219.87    6164  221.56  6171.2  223.36  6192.3  225.59  6241.7  227.95
  6305.5  233.88  6312.4  235.54  6319.7   234.9  6340.8  235.59  6379.9  238.69
#Mann= 6 ,-1 , 0
  4224.2     .11       0  4474.6     .15       0    4800     .11       0
    5000     .06       0 5031.55     .08       0  5032.5     .11       0
Bank Sta=5000,5031.55
XS Rating Curve= 0 ,0
Exp/Cntr=0.3,0.1

Type RM Length L Ch R = 1 ,8489    ,1136,1136,1136
BEGIN DESCRIPTION:
LITTLE CANEY CREEK 12.0
END DESCRIPTION:
XS GIS Cut Line= 3
      3730162.66     10136036.37       3729516.7     10135190.02
      3728405.76     10134168.35
#Sta/Elev= 30
  3935.3  226.01  3999.7   224.2  4178.5  223.81  4284.5  220.22  4319.9  221.19
    4378  219.53  4533.9  219.03  4727.2  214.34  4762.5  211.72  4812.4  214.69
  4876.8  215.55  4991.1  214.44  4996.2  212.43  5012.3  212.47  5019.7  210.19
  5026.5  213.95  5033.9  214.67  5338.1  213.65  5345.2  213.14  5349.4  209.99
  5369.4  209.99  5380.4  213.38  5394.6   213.6  5876.1  213.61  6017.4  216.83
  6138.1  223.01  6236.8  230.95  6265.1  234.74  6286.7  233.75  6509.3  247.22
#Mann= 3 , 0 , 0
  3935.3     .11       0  4991.1     .06       0  5033.9     .11       0
Bank Sta=4991.1,5033.9
XS Rating Curve= 0 ,0
Exp/Cntr=0.3,0.1

Type RM Length L Ch R = 1 ,7353    ,704,704,704
BEGIN DESCRIPTION:
LITTLE CANEY CREEK 11.0
END DESCRIPTION:
XS GIS Cut Line= 3
      3730767.86     10136461.09      3730239.06     10135078.04
      3728607.26     10133855.93
#Sta/Elev= 30
  3524.7  239.33  3685.3  237.84  3867.3  232.55  4043.3  230.23  4098.1  227.72
  4285.5  226.06  4322.5   227.7  4392.3  227.54  4477.6   227.4  4541.6  220.54
  4723.8  212.74  4801.4   211.6  4980.7  214.34  4990.4  212.58  4991.6  209.24
  5010.6  209.24  5031.9  213.91  5440.2  214.28  5519.1   212.9  5825.7  212.76
    5869  211.41  5925.7  213.44  6340.3  213.78  6440.4  216.71  6596.6  225.75
  6625.8   228.7  6775.8  235.12  6825.9  238.81  6975.9  242.16  7044.1  241.05
#Mann= 5 ,-1 , 0
  3524.7     .11       0  4285.5     .17       0  4392.3     .11       0
  4980.7     .06       0  5031.9     .11       0
Bank Sta=4980.7,5031.9
XS Rating Curve= 0 ,0
Exp/Cntr=0.3,0.1

Type RM Length L Ch R = 1 ,6649    ,333,333,333
BEGIN DESCRIPTION:
LITTLE CANEY CREEK 10.0
END DESCRIPTION:
XS GIS Cut Line= 3
      3730794.62      10135897.5      3730523.78     10134564.15
      3729502.97     10132647.53
#Sta/Elev= 30
  3815.6  237.05  3876.5  237.66  3954.9  234.39  4281.5  220.97    4414  212.42
  4561.6  212.14  4833.3  214.27    4863  210.58    4884  210.53  4985.4  212.85
  5005.9  208.06  5016.1  211.88  5081.4  214.27  5417.7  212.48  5428.3  209.03
  5430.3  204.87  5450.3  204.87  5462.9  212.28  5477.9  213.68  5598.4   213.1
  5642.3  209.52  5664.3  212.03  5752.2  212.77  5796.1  210.46  5825.5   212.6
  6313.3  212.19  6476.4  212.95  6794.5   226.8  7291.9  240.13  7347.7  240.97
#Mann= 7 ,-1 , 0
  3815.6     .11       0  3954.9     .17       0  4561.6     .11       0
  4985.4     .06       0  5016.1     .11       0  6313.3     .17       0
  7291.9     .11       0
Bank Sta=4985.4,5016.1
XS Rating Curve= 0 ,0
Exp/Cntr=0.3,0.1

Type RM Length L Ch R = 1 ,6316    ,224,224,224
BEGIN DESCRIPTION:
Mapping XS cb9e1d0a
END DESCRIPTION:
XS GIS Cut Line= 3
      3730898.78     10135939.11      3730850.17      10134883.6
      3731350.17     10132591.94
#Sta/Elev= 30
  3793.9  236.17    3892  236.58  3952.1  232.19  4062.2  232.66  4182.3  228.77
  4382.6  214.19  4452.6  212.69  4662.9  212.92  4702.9  210.29    4763  213.54
  4965.7  213.52  4996.4  208.89  5016.9  213.28  5149.9   211.1  5528.6  210.82
  5570.7  212.29  5600.3  209.84  5609.6  208.03  5610.8  205.44  5630.8  205.44
    5631  208.84  5641.2  211.98  5844.5  208.02  5876.6   211.6  5999.5  211.65
  6040.7  209.38  6060.9  211.31  6363.6  214.32  7019.5  231.48  7196.1  232.18
#Mann= 3 , 0 , 0
  3793.9     .11       0  4965.7     .06       0  5016.9     .11       0
Bank Sta=4965.7,5016.9
XS Rating Curve= 0 ,0
Exp/Cntr=0.3,0.1

Type RM Length L Ch R = 1 ,6092    ,500,500,500
BEGIN DESCRIPTION:
LITTLE CANEY CREEK 9.0
END DESCRIPTION:
XS GIS Cut Line= 3
      3731009.89     10135904.45       3731099.1     10134754.71
      3731537.33     10132614.41
#Sta/Elev= 30
  3846.8  234.42  4040.8  231.35  4274.7  222.77  4570.8  216.56  4669.1  213.34
  4865.7   213.2  4953.5  212.33  4963.5  209.56  4993.6  207.42  5018.9  212.56
  5082.7  212.39  5422.4  210.47  5575.3  211.94    5606  206.93    5614  210.33
  5619.1   206.9  5636.6  212.67  5759.1  210.91  5789.7  207.78  5789.9  206.12
  5891.8   210.8    5962  211.31  6017.6  208.03  6044.9   210.6    6068  208.15
  6113.3  212.57  6146.9  211.21  6365.6  213.39  6859.8  229.19  7184.7  233.29
#Mann= 7 ,-1 , 0
  3846.8     .11       0  4570.8     .15       0  4669.1     .11       0
  4865.7     .15       0  4953.5     .09       0  5018.9     .15       0
  5082.7     .11       0
Bank Sta=4953.5,5018.9
XS Rating Curve= 0 ,0
Exp/Cntr=0.3,0.1