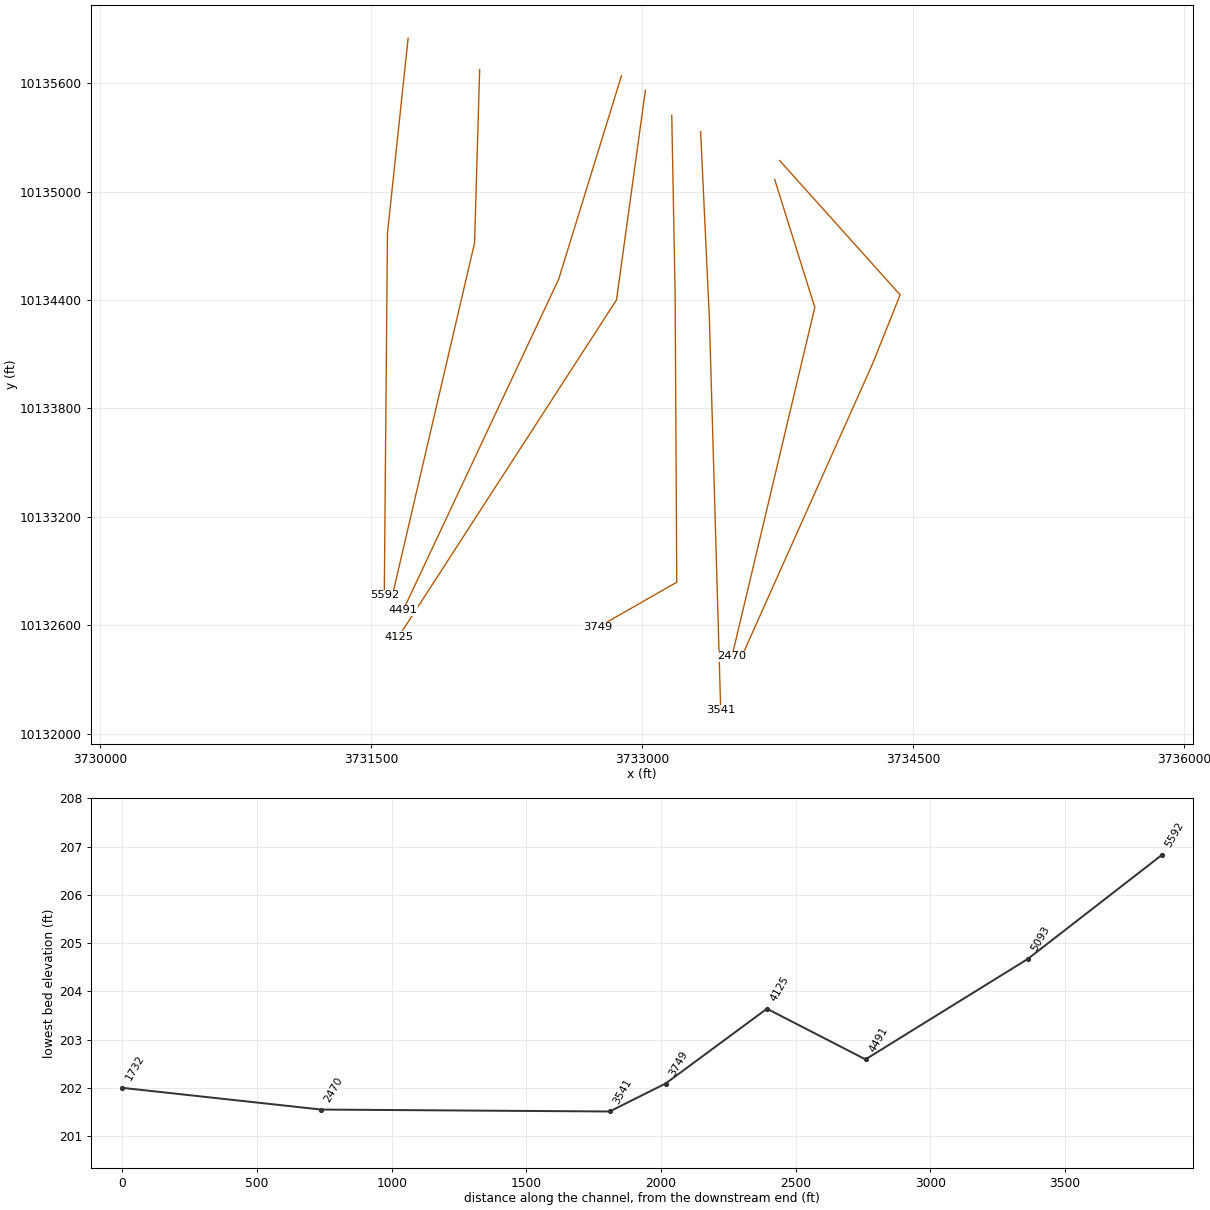
HEC-RAS study LITTLE CANEY CREEK.prj: LITTLE CANEY CREEK Base Level Engineering

--- LITTLE CANEY CREEK.g01 (geometry) --- (continued)

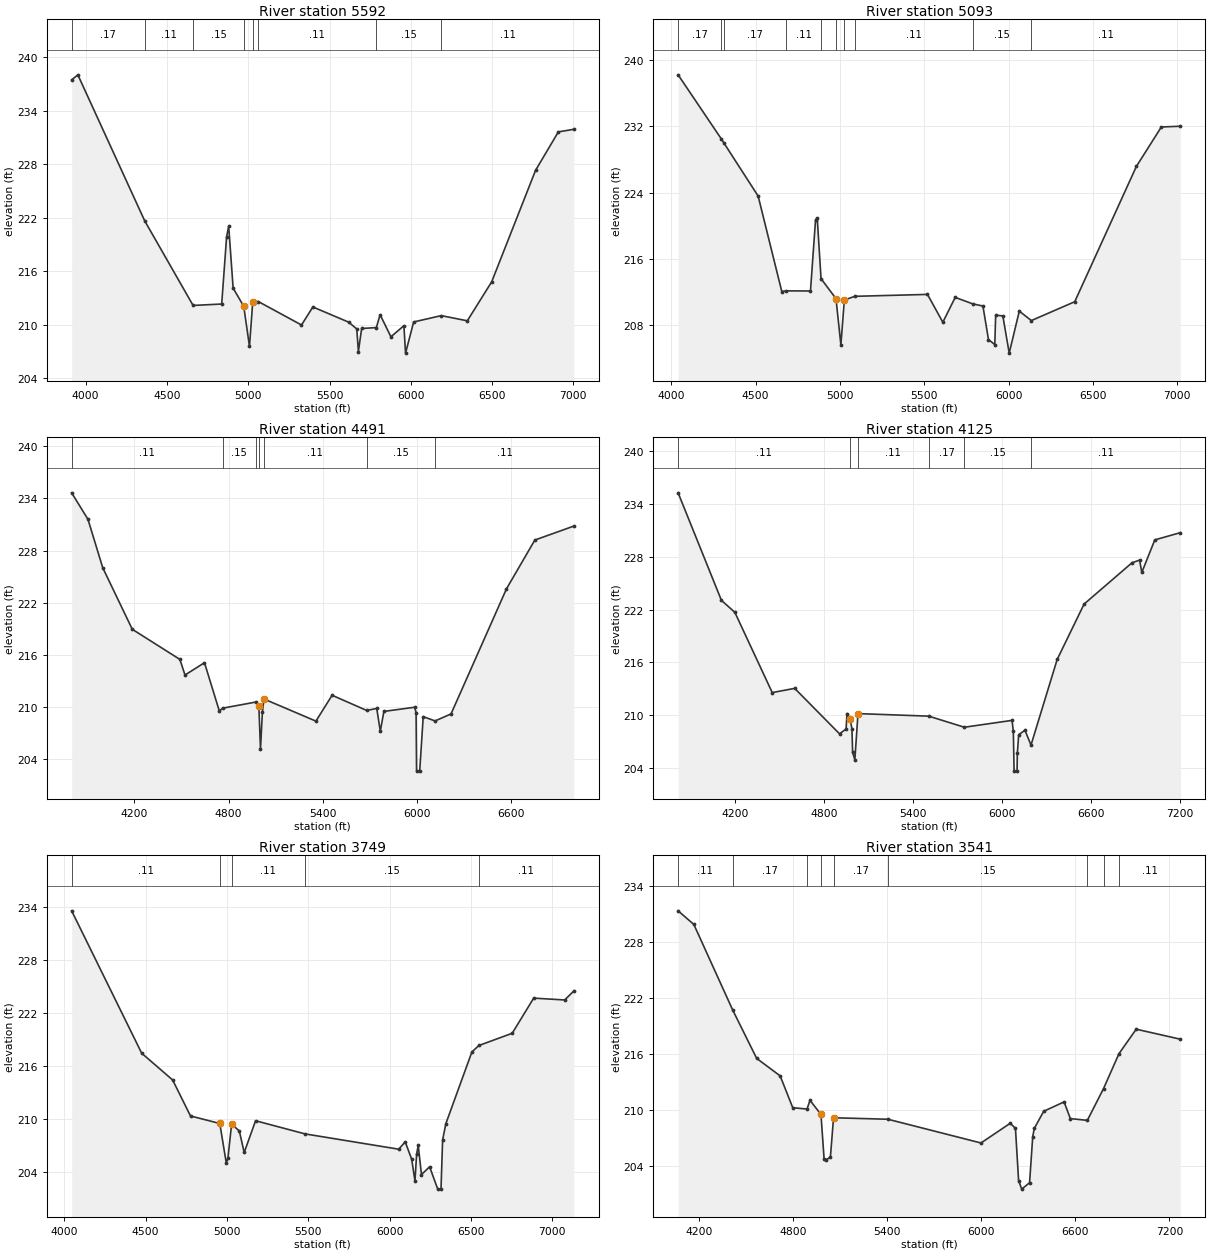
Type RM Length L Ch R = 1 ,5592    ,499,499,499
BEGIN DESCRIPTION:
LITTLE CANEY CREEK 8.0
END DESCRIPTION:
XS GIS Cut Line= 3
      3731704.34     10135848.91      3731589.95     10134768.75
      3731572.39     10132765.83
#Sta/Elev= 30
  3913.8  237.43  3951.9     238  4363.1  221.65  4660.9  212.17  4836.8  212.33
  4866.9  219.84  4879.8  221.05  4907.2  214.11  4972.5  212.07  5007.7  207.58
  5027.7  212.57  5062.8   212.6  5327.7  209.98  5397.7     212  5617.7   210.3
  5667.7  209.54  5677.7  207.01  5697.7  209.59    5788  209.69  5811.4  211.13
  5877.7  208.66  5957.7   209.9  5967.7  206.83  6017.7  210.32  6187.6  211.03
  6347.7  210.45  6497.7  214.82  6767.7  227.31  6907.8  231.61    7003   231.9
#Mann= 8 ,-1 , 0
  3913.8     .17       0  4363.1     .11       0  4660.9     .15       0
  4972.5     .09       0  5027.7     .15       0  5062.8     .11       0
    5788     .15       0  6187.6     .11       0
Bank Sta=4972.5,5027.7
XS Rating Curve= 0 ,0
Exp/Cntr=0.3,0.1

Type RM Length L Ch R = 1 ,5093    ,602,602,602
BEGIN DESCRIPTION:
LITTLE CANEY CREEK 7.0
END DESCRIPTION:
XS GIS Cut Line= 3
      3732100.17     10135675.31      3732072.04     10134716.12
      3731614.05      10132751.6
#Sta/Elev= 30
  4040.4  238.18  4296.9  230.45  4312.9  229.94  4514.8  223.58  4654.9  212.09
  4680.1  212.17    4825  212.15    4855  220.72    4865  220.93  4887.6  213.64
  4976.2  211.23  5005.2  205.67  5025.7  211.06  5087.5  211.51  5518.6  211.74
  5609.5  208.39  5682.9  211.38  5787.2   210.6  5847.2  210.34  5880.2   206.3
  5917.6   205.7  5922.8  209.24  5965.3  209.15    6003  204.67  6062.8  209.73
  6134.2  208.59  6391.4  210.86  6757.1  227.16  6904.8   231.9  7017.2  231.99
#Mann= 10 ,-1 , 0
  4040.4     .17       0  4296.9     .11       0  4312.9     .17       0
  4680.1     .11       0  4887.6     .17       0  4976.2     .09       0
  5025.7     .17       0  5087.5     .11       0  5787.2     .15       0
  6134.2     .11       0
Bank Sta=4976.2,5025.7
XS Rating Curve= 0 ,0
Exp/Cntr=0.3,0.1

Type RM Length L Ch R = 1 ,4491    ,366,366,366
BEGIN DESCRIPTION:
LITTLE CANEY CREEK 6.0
END DESCRIPTION:
XS GIS Cut Line= 3
       3732884.9     10135640.58      3732537.67     10134515.54
      3731676.56     10132682.21
#Sta/Elev= 30
  3799.3  234.65  3903.1  231.61  3997.6  226.02    4186  218.93  4489.6  215.46
  4522.2  213.66  4646.5  215.08  4740.7  209.54  4764.4  209.85  4972.2  210.54
  4993.1  210.15  5003.7  205.12  5015.9  209.41  5025.8   210.9  5357.3  208.35
  5460.4  211.33    5681  209.58  5745.1  209.81  5767.9  207.19  5790.7  209.47
    5987  209.95    5996  209.33  5999.1  202.59  6019.1  202.59  6041.6  208.87
    6117  208.37    6219  209.18  6572.6  223.59  6753.5  229.21  7002.2  230.82
#Mann= 7 ,-1 , 0
  3799.3     .11       0  4764.4     .15       0  4972.2     .11       0
  4993.1     .06       0  5025.8     .11       0    5681     .15       0
    6117     .11       0
Bank Sta=4993.1,5025.8
XS Rating Curve= 0 ,0
Exp/Cntr=0.3,0.1

Type RM Length L Ch R = 1 ,4125    ,376,376,376
BEGIN DESCRIPTION:
LITTLE CANEY CREEK 5.0
END DESCRIPTION:
XS GIS Cut Line= 3
      3733017.42     10135560.58      3732857.69     10134400.81
      3731652.02     10132537.36
#Sta/Elev= 30
  3812.8  235.28    4105  223.06  4195.9  221.69  4448.2  212.57  4599.7  213.05
  4902.5  207.88  4946.8  208.43    4953  210.19  4973.2   209.6  4986.3  208.44
  4990.8  205.77  5005.9  204.93  5027.1  210.18    5505  209.89  5745.2  208.63
  6067.1  209.41  6075.8  208.19  6080.9  203.64  6100.9  203.64  6102.8  205.69
  6112.1  207.78  6154.3  208.29    6195   206.6  6371.9  216.34  6553.3  222.63
    6877  227.33    6928  227.63  6943.1  226.23  7030.8  229.93    7203  230.75
#Mann= 6 ,-1 , 0
  3812.8     .11       0  4973.2     .06       0  5027.1     .11       0
    5505     .17       0  5745.2     .15       0    6195     .11       0
Bank Sta=4973.2,5027.1
XS Rating Curve= 0 ,0
Exp/Cntr=0.3,0.1

Type RM Length L Ch R = 1 ,3749    ,208,208,208
BEGIN DESCRIPTION:
LITTLE CANEY CREEK 4.0
END DESCRIPTION:
XS GIS Cut Line= 4
      3733163.25     10135421.68       3733181.9     10134438.39
      3733191.02     10132838.31      3732753.49     10132588.29
#Sta/Elev= 30
  4045.2  233.59  4475.9  217.47  4665.9  214.45  4775.9  210.37    4956  209.52
    4996  205.04    5006  205.59  5028.7  209.46    5076  208.67    5106  206.24
    5176  209.83  5480.5  208.34    6056  206.61    6096  207.44    6136  205.46
    6156  202.99    6166  206.06    6176  207.03    6196  203.74    6246  204.62
    6296  202.09    6316  202.09    6326  207.66    6346  209.51    6506  217.62
  6549.3  218.35  6753.8  219.73  6885.8  223.71  7076.3   223.5  7132.7  224.52
#Mann= 5 ,-1 , 0
  4045.2     .11       0    4956     .06       0  5028.7     .11       0
  5480.5     .15       0  6549.3     .11       0
Bank Sta=4956,5028.7
XS Rating Curve= 0 ,0
Exp/Cntr=0.3,0.1

Type RM Length L Ch R = 1 ,3541    ,1071,1071,1071
BEGIN DESCRIPTION:
LITTLE CANEY CREEK 3.0
END DESCRIPTION:
XS GIS Cut Line= 3
      3733322.97     10135331.38      3733371.58     10134296.65
      3733434.08     10132130.02
#Sta/Elev= 30
  4065.9   231.3  4166.3  229.84  4413.3  220.71  4566.8  215.51  4716.9  213.63
    4797  210.23  4888.2  210.08  4907.1  211.02  4977.2   209.5  4997.2  204.72
  5007.2  204.63  5037.3  204.92  5057.3  209.15  5404.4  208.99  5997.7  206.45
  6184.5  208.56  6217.8  208.01  6237.8  202.41  6257.8  201.51  6307.8   202.2
  6327.9  207.13  6337.9  208.01  6397.9  209.84  6527.9  210.85    6568  209.06
  6676.2  208.87  6779.8  212.28  6878.1  216.01  6988.1  218.63  7269.3  217.56
#Mann= 9 ,-1 , 0
  4065.9     .11       0  4413.3     .17       0  4888.2     .11       0
  4977.2     .06       0  5057.3     .17       0  5404.4     .15       0
  6676.2     .11       0  6779.8     .17       0  6878.1     .11       0
Bank Sta=4977.2,5057.3
XS Rating Curve= 0 ,0
Exp/Cntr=0.3,0.1

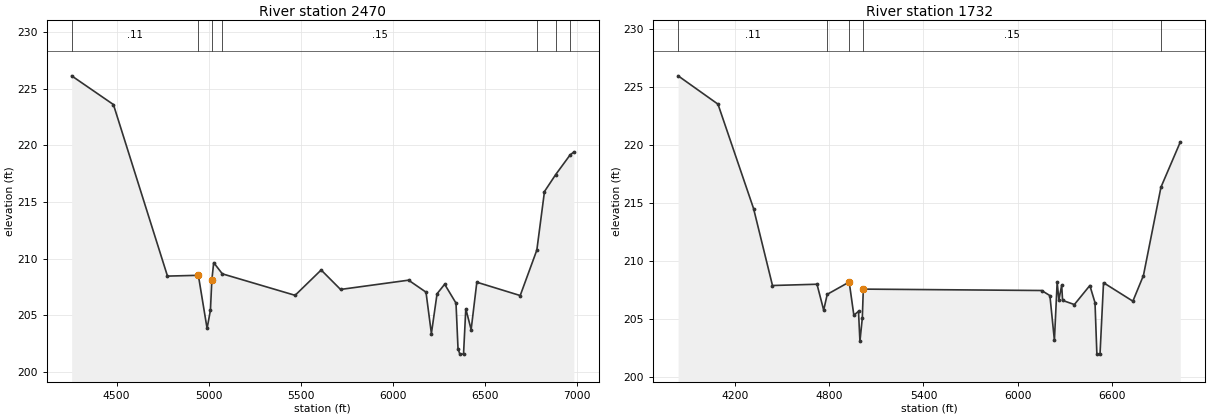
Type RM Length L Ch R = 1 ,2470    ,738,738,738
BEGIN DESCRIPTION:
LITTLE CANEY CREEK 2.0
END DESCRIPTION:
XS GIS Cut Line= 3
      3733732.69     10135067.49      3733954.91     10134359.15
      3733496.58     10132428.59
#Sta/Elev= 30
  4255.5  226.16  4482.3  223.62  4775.8  208.45  4943.5  208.52  4990.8  203.82
  5009.1  205.44  5016.5  208.08  5026.7  209.64  5073.6  208.65  5468.7  206.75
  5610.2  208.99  5715.4  207.27  6084.7  208.09  6179.4  207.03  6208.7  203.37
  6239.5  206.89  6280.7  207.73  6342.3  206.06  6353.3  202.02  6363.2  201.55
  6383.2  201.55  6395.5  205.56  6424.5  203.72  6455.4  207.91  6690.9  206.73
  6781.2  210.75  6822.7  215.93  6883.2  217.42    6962  219.17  6982.1  219.42
#Mann= 7 ,-1 , 0
  4255.5     .11       0  4943.5     .06       0  5016.5     .11       0
  5073.6     .15       0  6781.2     .11       0  6883.2     .17       0
    6962     .11       0
Bank Sta=4943.5,5016.5
XS Rating Curve= 0 ,0
Exp/Cntr=0.3,0.1

Type RM Length L Ch R = 1 ,1732    ,0,0,0
BEGIN DESCRIPTION:
LITTLE CANEY CREEK 1.0
END DESCRIPTION:
XS GIS Cut Line= 4
      3733760.47     10135171.65      3734427.14     10134428.59
      3734274.36     10134046.65      3733545.51     10132415.43
#Sta/Elev= 30
  3838.4  225.97  4092.1  223.53  4318.6  214.54    4439  207.91  4722.3  208.02
  4764.9  205.79  4787.5  207.15  4927.3  208.21  4956.9  205.35  4986.5  205.69
  4995.6   203.1  5010.8  205.11  5017.1   207.6  6152.3  207.48  6204.7  207.04
  6233.4  203.19  6250.9  208.19    6262  206.68  6279.8  207.94  6285.3  206.63
  6360.4  206.27    6459  207.91  6491.8  206.43  6503.7     202  6523.7     202
    6546  208.15  6732.8  206.56    6800  208.77  6911.6  216.38  7034.7  220.27
#Mann= 5 ,-1 , 0
  3838.4     .11       0  4787.5     .15       0  4927.3     .09       0
  5017.1     .15       0  6911.6     .17       0
Bank Sta=4927.3,5017.1
XS Rating Curve= 0 ,0
Exp/Cntr=0.3,0.1

Chan Stop Cuts=-1
Use User Specified Reach Order=0
Composite Channel Slope=5