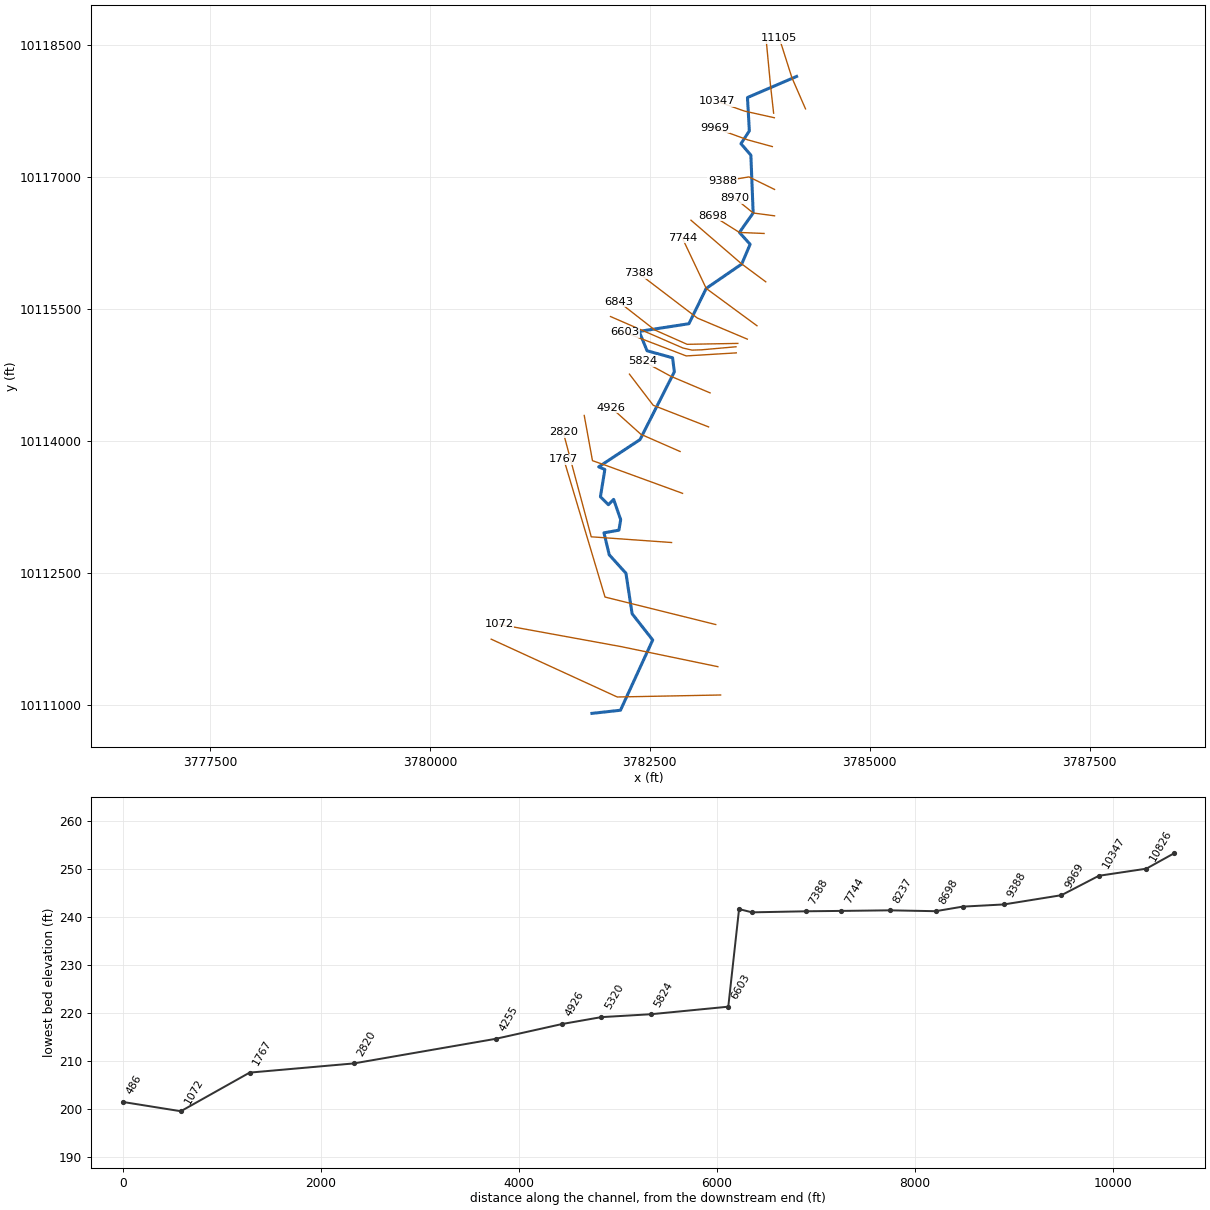
--- MOUND CREEK TRIBUTARY NO 1.prj (project) ---

Proj Title=MOUND CREEK TRIBUTARY NO 1 Base Level Engineering
Current Plan=p01
Default Exp/Contr=0.3,0.1
English Units
Geom File=g01
Flow File=f01
Plan File=p01
Y Axis Title=Elevation
X Axis Title(PF)=Main Channel Distance
X Axis Title(XS)=Station
BEGIN DESCRIPTION:
MOUND CREEK TRIBUTARY NO 1
END DESCRIPTION:
DSS Export Rating Curves= 0
DSS Export Rating Curve Sorted= 0
DSS Export Volume Flow Curves= 0
DXF OffsetX= 0
DXF OffsetY= 0
DXF ScaleX= 1
DXF ScaleY= 10

--- MOUND CREEK TRIBUTARY NO 1.p01 (plan) ---

Plan Title=Multiple Run
Short Identifier=Multiple
Geom File=g01
Flow File=f01
Subcritical Flow
K Sum by GR= 0
Std Step Tol= 0.01
Critical Tol= 0.01
Num of Std Step Trials= 20
Max Error Tol= 0.3
Flow Tol Ratio= 0.001
Split Flow NTrial= 30
Split Flow Tol= 0.02
Split Flow Ratio= 0.02
Log Output Level= 0
Friction Slope Method= 1
Unsteady Friction Slope Method= 2
Unsteady Bridges Friction Slope Method= 1
Parabolic Critical Depth
Global Vel Dist=  1 , 1 , 1
Global Log Level= 0
CheckData=True
Encroach Param= -1, 0, 0, 0
BEGIN DESCRIPTION:
Multiple Run
END DESCRIPTION:

--- MOUND CREEK TRIBUTARY NO 1.f01 (steady flow) ---

Flow Title=Multiple
Program Version=4.10
Number of Profiles= 7
Profile Names=10-year,25-year,50-year,1pct_min,100-year,1pct_plu,500-year
River Rch & RM=MOUND CREEK TRIB,Reach-1         ,11105
     528     707     948     419    1264    3817    2324
River Rch & RM=MOUND CREEK TRIB,Reach-1         ,10826
     528     707     948     419    1264    3817    2324
River Rch & RM=MOUND CREEK TRIB,Reach-1         ,6603
     747    1018    1381     617    1862    5623    3497
River Rch & RM=MOUND CREEK TRIB,Reach-1         ,1072
    3349    4824    6790    3124    9433   28487   18851
Boundary for River Rch & Prof#=MOUND CREEK TRIB,Reach-1         , 1
Up Type= 0
Dn Type= 3
Dn Slope=0.005
Boundary for River Rch & Prof#=MOUND CREEK TRIB,Reach-1         , 2
Up Type= 0
Dn Type= 3
Dn Slope=0.005
Boundary for River Rch & Prof#=MOUND CREEK TRIB,Reach-1         , 3
Up Type= 0
Dn Type= 3
Dn Slope=0.005
Boundary for River Rch & Prof#=MOUND CREEK TRIB,Reach-1         , 4
Up Type= 0
Dn Type= 3
Dn Slope=0.005
Boundary for River Rch & Prof#=MOUND CREEK TRIB,Reach-1         , 5
Up Type= 0
Dn Type= 3
Dn Slope=0.005
Boundary for River Rch & Prof#=MOUND CREEK TRIB,Reach-1         , 6
Up Type= 0
Dn Type= 3
Dn Slope=0.005
Boundary for River Rch & Prof#=MOUND CREEK TRIB,Reach-1         , 7
Up Type= 0
Dn Type= 3
Dn Slope=0.005
DSS Import GetInterval= 0
DSS Import GetPeak= 0
DSS Import FillOption= 0

--- MOUND CREEK TRIBUTARY NO 1.g01 (geometry) ---

Geom Title=Existing Conditions
Program Version=4.10

River Reach=MOUND CREEK TRIB,Reach-1
Reach XY= 30
      3784168.23     10118145.86       3783609.9     10117905.93
      3783631.17     10117526.59      3783535.68     10117381.19
      3783648.53     10117250.98      3783674.57     10116593.43
      3783518.32     10116372.07      3783639.85     10116237.52
      3783545.09     10116013.37      3783140.57     10115735.59
      3782944.39     10115334.55      3782378.23     10115246.84
      3782468.23     10115026.84      3782758.23     10114946.84
      3782778.23     10114786.84      3782388.23     10114016.84
      3781918.23     10113706.84      3781988.23     10113676.84
      3781938.23     10113366.84      3782028.23     10113276.84
      3782088.23     10113336.84      3782168.23     10113106.84
      3782148.23     10112986.84      3781978.23     10112956.84
      3782038.23     10112706.84      3782228.23     10112496.84
      3782298.23     10112036.84      3782532.45     10111738.28
      3782165.87      10110939.5      3781841.78     10110903.92

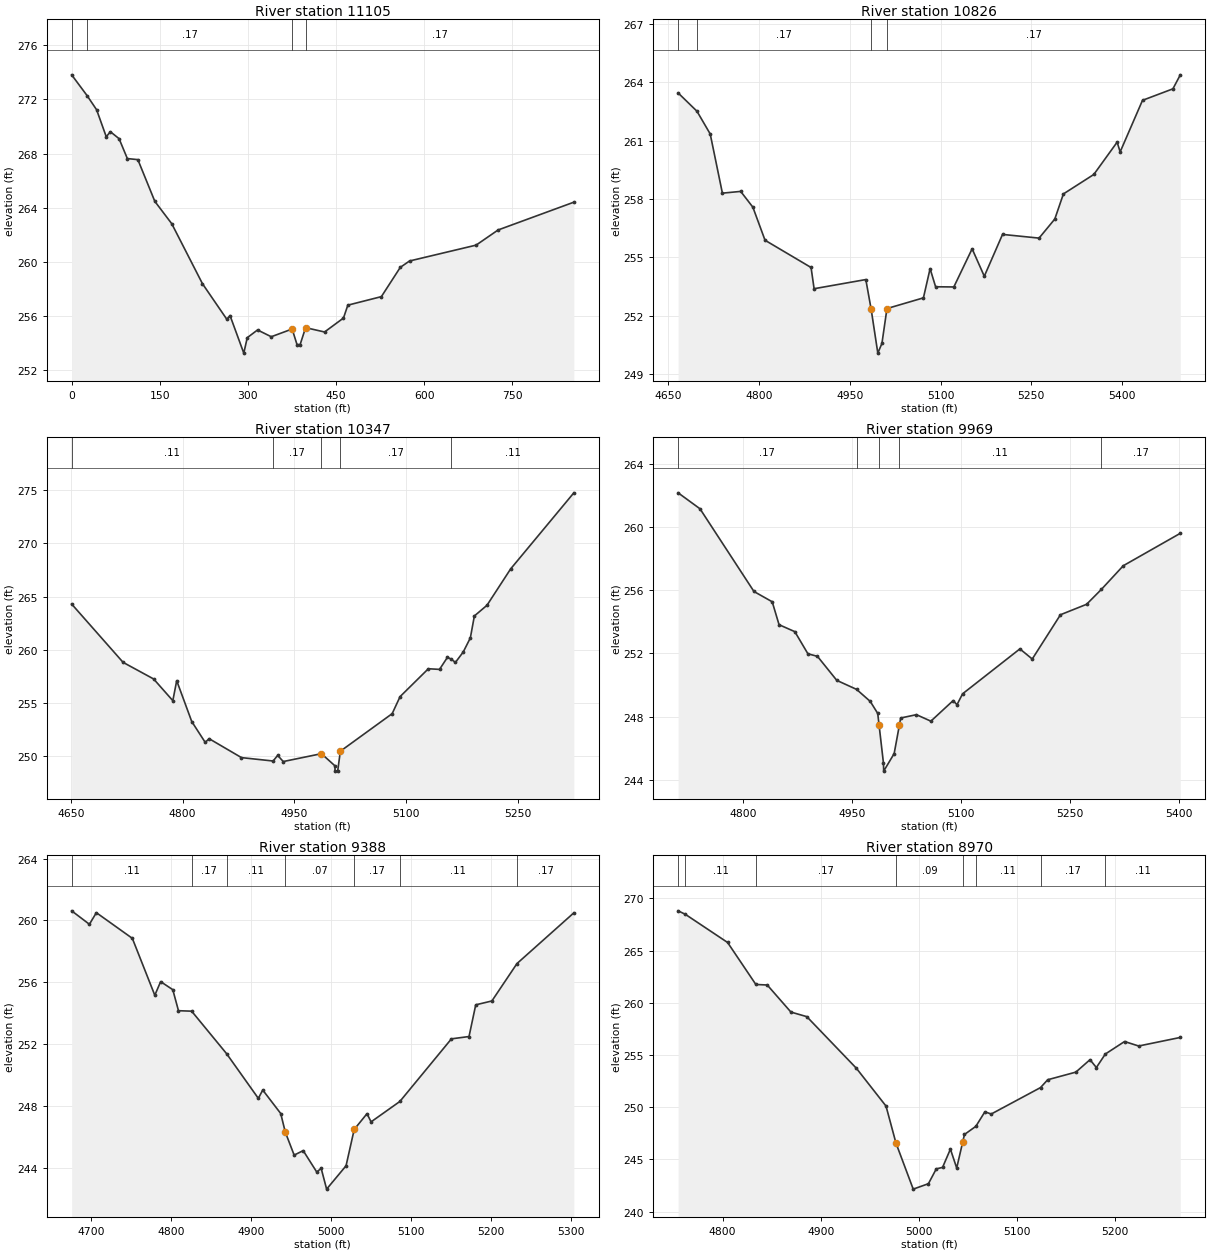
Type RM Length L Ch R = 1 ,11105   ,279,279,279
BEGIN DESCRIPTION:
MOUND CREEK TRIBUTARY NO. 1 15.0
END DESCRIPTION:
XS GIS Cut Line= 3
      3784269.81      10117777.1       3784115.3     10118131.27
      3783972.94     10118579.18
#Sta/Elev= 30
       0  273.81    26.2  272.28    42.5  271.23    58.9  269.24    65.9  269.61
    80.7   269.1    94.8  267.63   112.7  267.55   141.6  264.47   170.4  262.82
   222.7  258.39   264.1  255.77   269.6  256.04     293  253.27   298.9  254.41
   316.4  254.98   339.8  254.48   375.3  255.05   383.6   253.9   388.9   253.9
   398.2  255.15   430.5  254.83   462.7  255.86   470.1  256.81   527.2  257.44
   559.4   259.6   575.1  260.07   688.4  261.24   725.9  262.36   854.8  264.41
#Mann= 4 ,-1 , 0
       0     .11       0    26.2     .17       0   375.3     .09       0
   398.2     .17       0
Bank Sta=375.3,398.2
XS Rating Curve= 0 ,0
Exp/Cntr=0.3,0.1

Type RM Length L Ch R = 1 ,10826   ,479,479,479
BEGIN DESCRIPTION:
MOUND CREEK TRIBUTARY NO. 1 15.0
END DESCRIPTION:
XS GIS Cut Line= 3
      3783907.22     10117728.42      3783870.32     10118059.57
      3783823.28     10118553.24
#Sta/Elev= 30
  4666.8  263.45  4697.9  262.51  4719.8  261.34  4739.9   258.3  4770.1  258.39
  4790.2  257.58  4810.3  255.88  4886.3  254.48  4891.3  253.39  4976.7  253.86
 4985.57252.3222  4996.5  250.08  5003.3  250.58  5011.6  252.37  5071.8  252.92
  5082.8  254.42  5091.9  253.49    5122  253.48  5152.2  255.44  5172.3  254.03
  5202.4  256.18  5262.7  255.99  5288.7  256.97  5302.9  258.26  5353.1  259.26
  5391.6  260.92  5396.6  260.42  5433.5  263.07  5483.7  263.66  5495.9  264.38
#Mann= 4 ,-1 , 0
  4666.8     .11       0  4697.9     .17       0 4985.57     .09       0
  5011.6     .17       0
Bank Sta=4985.57,5011.6
XS Rating Curve= 0 ,0
Exp/Cntr=0.3,0.1

Type RM Length L Ch R = 1 ,10347   ,378,378,378
BEGIN DESCRIPTION:
MOUND CREEK TRIBUTARY NO. 1 14.0
END DESCRIPTION:
XS GIS Cut Line= 3
      3783915.31     10117676.49      3783574.75     10117752.28
      3783267.86     10117861.07
#Sta/Elev= 30
  4651.1   264.3  4720.2  258.82  4761.2  257.26    4787  255.22  4792.2   257.1
  4812.4  253.26  4830.5   251.3  4835.7  251.65  4879.2  249.87  4921.7  249.55
  4927.8  250.08  4935.3   249.5  4986.6  250.24  5004.7   249.1  5004.9   248.6
  5008.4   248.6    5012  250.47  5081.6     254  5092.2   255.6  5130.2  258.22
  5145.2  258.16  5155.8  259.29  5161.1  259.12  5166.5  258.81  5177.1   259.8
  5186.6  261.12    5192  263.18  5208.9  264.18  5240.7   267.6  5325.6  274.75
#Mann= 5 ,-1 , 0
  4651.1     .11       0  4921.7     .17       0  4986.6     .09       0
    5012     .17       0  5161.1     .11       0
Bank Sta=4986.6,5012
XS Rating Curve= 0 ,0
Exp/Cntr=0.3,0.1

Type RM Length L Ch R = 1 ,9969    ,581,581,581
BEGIN DESCRIPTION:
MOUND CREEK TRIBUTARY NO. 1 13.0
END DESCRIPTION:
XS GIS Cut Line= 3
      3783892.68     10117348.38      3783613.81     10117424.59
      3783236.52     10117561.89
#Sta/Elev= 30
  4710.9  262.15    4741  261.14  4815.2  255.91  4840.3  255.26  4849.7  253.81
  4871.4  253.37  4889.4  251.97  4902.5  251.81  4929.1  250.29  4956.3  249.72
  4975.1  248.96  4985.4   248.2 4987.24247.4662  4993.3  245.05  4993.6  244.55
    5008  245.66 5015.12  247.44    5017  247.91  5038.6  248.12  5058.5  247.71
  5089.1  249.01  5094.4  248.75  5102.1  249.44  5180.9  252.28  5197.9  251.64
  5236.7  254.44  5272.6   255.1  5292.9  256.04  5323.1  257.54  5401.5  259.59
#Mann= 5 ,-1 , 0
  4710.9     .17       0  4956.3     .11       0 4987.24     .07       0
 5015.12     .11       0  5292.9     .17       0
Bank Sta=4987.24,5015.12
XS Rating Curve= 0 ,0
Exp/Cntr=0.3,0.1

Type RM Length L Ch R = 1 ,9388    ,418,418,418
BEGIN DESCRIPTION:
MOUND CREEK TRIBUTARY NO. 1 12.0
END DESCRIPTION:
XS GIS Cut Line= 3
      3783917.81     10116861.09      3783626.83     10117003.58
      3783326.75     10116954.27
#Sta/Elev= 30
    4676  260.62  4698.2  259.75  4706.9   260.5  4751.9  258.84    4780  255.16
  4787.3  256.04  4802.5  255.52  4809.6  254.16  4826.1  254.13  4869.8  251.38
  4909.5  248.49    4915  249.03  4937.5  247.51  4943.2  246.31  4954.3  244.82
  4965.6  245.11  4982.5  243.73  4988.1  243.96  4994.9  242.62  5019.2  244.13
  5029.4  246.48  5045.4   247.5  5050.5  246.97  5086.5  248.29    5151  252.34
    5173  252.49  5181.4  254.54  5201.6  254.79    5233  257.21  5304.1  260.49
#Mann= 7 ,-1 , 0
    4676     .11       0  4826.1     .17       0  4869.8     .11       0
  4943.2     .07       0  5029.4     .17       0  5086.5     .11       0
    5233     .17       0
Bank Sta=4943.2,5029.4
XS Rating Curve= 0 ,0
Exp/Cntr=0.3,0.1

Type RM Length L Ch R = 1 ,8970    ,272,272,272
BEGIN DESCRIPTION:
MOUND CREEK TRIBUTARY NO. 1 11.0
END DESCRIPTION:
XS GIS Cut Line= 3
      3783917.83     10116561.07      3783674.57     10116593.43
      3783467.82      10116761.1
#Sta/Elev= 30
  4754.6   268.8  4761.9  268.47    4805  265.77  4833.8  261.75  4845.4   261.7
  4869.5  259.11  4885.7  258.67  4936.2  253.73  4966.4  250.11  4976.5  246.58
  4994.1  242.16  5009.6  242.68  5017.6   244.1    5024  244.24    5032  245.99
  5038.4  244.18 5044.51246.6626  5046.3  247.39  5057.9  248.17  5067.1  249.56
  5073.6  249.35  5123.8  251.88  5131.1  252.63  5159.8  253.36  5174.2  254.55
  5180.7   253.8  5189.8  255.09  5209.4  256.29  5223.8  255.86  5266.2  256.68
#Mann= 8 ,-1 , 0
  4754.6     .17       0  4761.9     .11       0  4833.8     .17       0
  4976.5     .09       0 5044.51     .17       0  5057.9     .11       0
  5123.8     .17       0  5189.8     .11       0
Bank Sta=4976.5,5044.51
XS Rating Curve= 0 ,0
Exp/Cntr=0.3,0.1

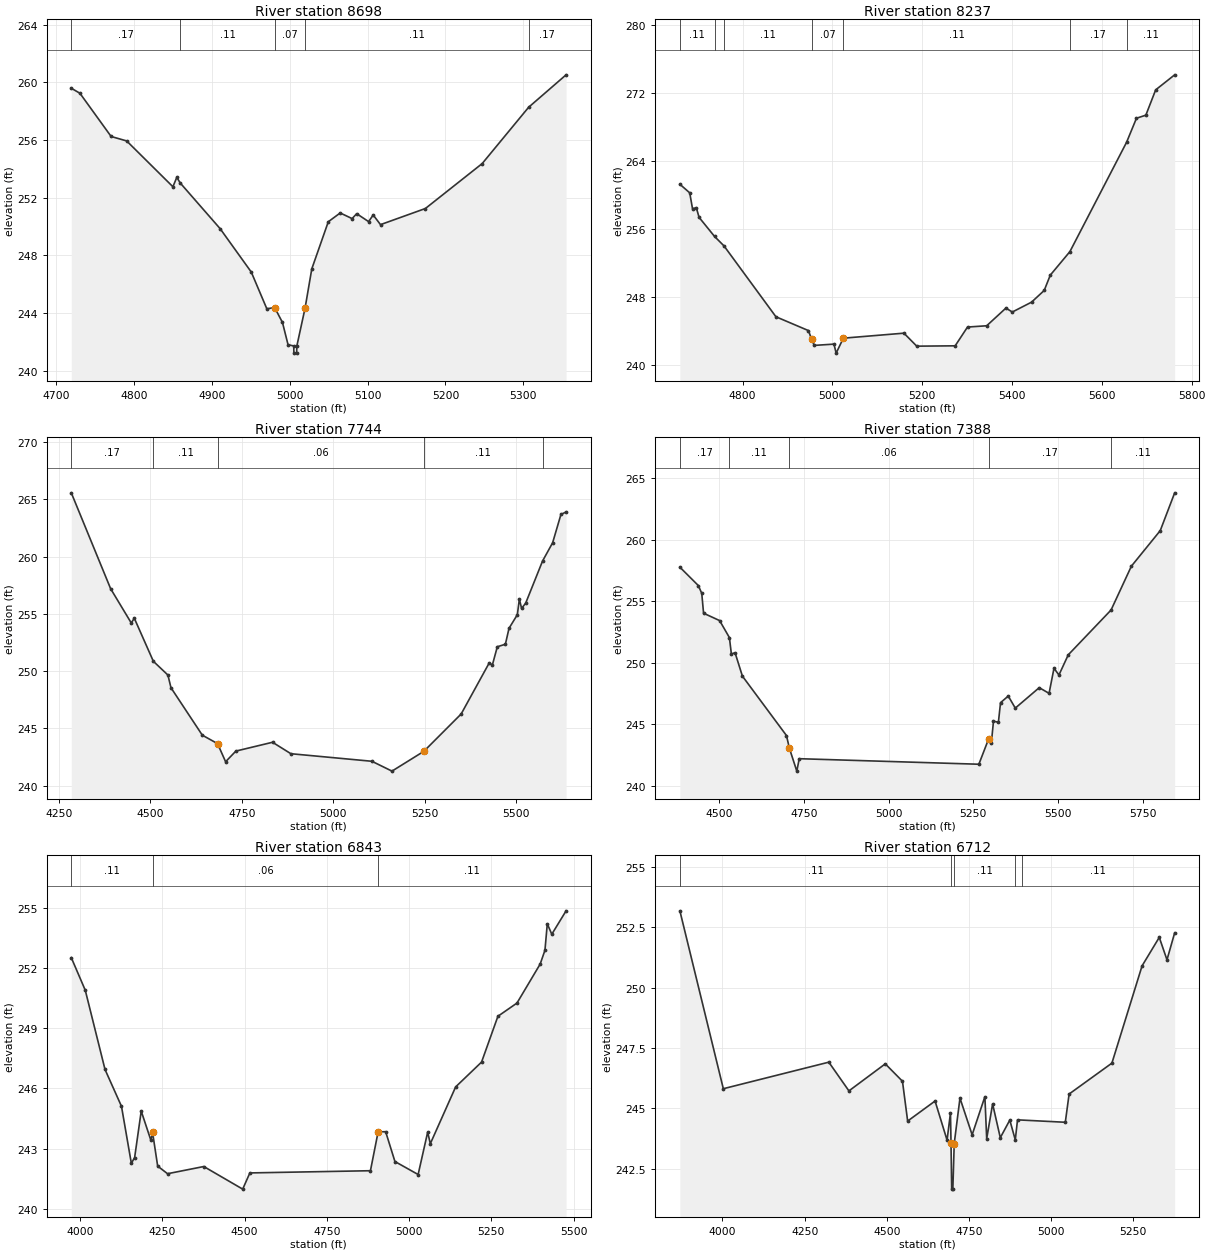
Type RM Length L Ch R = 1 ,8698    ,461,461,461
BEGIN DESCRIPTION:
MOUND CREEK TRIBUTARY NO. 1 10.0
END DESCRIPTION:
XS GIS Cut Line= 3
      3783798.98     10116360.52      3783518.32     10116372.07
      3783217.83     10116561.09
#Sta/Elev= 30
  4719.1   259.6  4730.2  259.25  4770.3  256.25  4790.3  255.94  4849.7  252.76
  4854.7  253.41  4859.3  253.01  4910.4  249.85  4950.4  246.84  4970.4  244.29
  4980.5  244.37  4990.5  243.34  4997.7  241.79    5005  241.71  5005.2  241.21
  5008.7  241.21    5009  241.71 5019.56244.3343  5028.2  247.06  5049.4  250.33
  5064.7  250.94    5080  250.55  5085.9  250.89  5101.2  250.34  5107.1   250.8
  5116.5  250.13  5174.2  251.25  5247.2  254.37  5306.9  258.28    5355  260.53
#Mann= 5 ,-1 , 0
  4719.1     .17       0  4859.3     .11       0  4980.5     .07       0
 5019.56     .11       0  5306.9     .17       0
Bank Sta=4980.5,5019.56
XS Rating Curve= 0 ,0
Exp/Cntr=0.3,0.1

Type RM Length L Ch R = 1 ,8237    ,493,493,493
BEGIN DESCRIPTION:
MOUND CREEK TRIBUTARY NO. 1 9.0
END DESCRIPTION:
XS GIS Cut Line= 3
      3783817.86     10115811.07      3783545.09     10116013.37
      3782967.83     10116511.09
#Sta/Elev= 30
  4660.4  261.27  4682.3  260.26  4688.6  258.38    4697  258.51  4703.2  257.37
  4737.7  255.12  4758.7  254.01  4874.3  245.67  4946.8  244.04  4953.6  243.03
  4959.8   242.3  5003.5  242.45  5008.4  241.39  5024.4  243.15  5159.3  243.74
  5187.9  242.21  5273.4  242.25  5300.9  244.46  5343.6  244.61  5386.4  246.69
  5400.7  246.23  5443.5  247.39  5471.7  248.77  5485.2  250.57  5528.9  253.34
  5655.1  266.21  5677.1  269.04    5698   269.4  5719.9  272.38  5762.2  274.15
#Mann= 7 ,-1 , 0
  4660.4     .11       0  4737.7     .17       0  4758.7     .11       0
  4953.6     .07       0  5024.4     .11       0  5528.9     .17       0
  5655.1     .11       0
Bank Sta=4953.6,5024.4
XS Rating Curve= 0 ,0
Exp/Cntr=0.3,0.1

Type RM Length L Ch R = 1 ,7744    ,356,356,356
BEGIN DESCRIPTION:
MOUND CREEK TRIBUTARY NO. 1 8.0
END DESCRIPTION:
XS GIS Cut Line= 3
      3783717.88     10115311.05      3783140.57     10115735.59
      3782867.87     10116311.04
#Sta/Elev= 30
  4283.4  265.57    4391   257.2  4447.4  254.21  4455.8  254.62  4507.9  250.86
  4547.7  249.66  4556.1  248.55  4641.8  244.41  4683.5  243.67  4705.5  242.09
  4733.6  243.02  4833.9  243.79  4884.1  242.79  5105.7  242.13  5160.6  241.27
  5247.8     243  5349.8  246.26  5426.6  250.72  5435.2  250.54  5448.7  252.13
  5470.8  252.35  5480.7  253.74  5503.5  254.93    5509  256.29  5515.1  255.48
  5526.2  255.93  5572.5  259.62    5600  261.21  5622.7  263.68  5636.8   263.9
#Mann= 5 ,-1 , 0
  4283.4     .17       0  4507.9     .11       0  4683.5     .06       0
  5247.8     .11       0  5572.5     .17       0
Bank Sta=4683.5,5247.8
XS Rating Curve= 0 ,0
Exp/Cntr=0.3,0.1

Type RM Length L Ch R = 1 ,7388    ,545,545,545
BEGIN DESCRIPTION:
MOUND CREEK TRIBUTARY NO. 1 7.0
END DESCRIPTION:
XS GIS Cut Line= 3
        3783608.     10115159.13      3783039.88     10115398.78
      3782367.87     10115911.06
#Sta/Elev= 30
  4383.4  257.76  4437.8  256.27    4448  255.64  4453.4  254.02  4500.8  253.42
  4529.7  252.04  4535.5  250.71  4546.4  250.81  4568.1  248.91  4698.3  244.08
  4706.9  243.05  4728.8  241.19    4736   242.2  5266.6  241.75  5295.2  243.79
  5303.5  243.49  5309.8  245.25  5324.3  245.16  5330.6  246.75  5353.4  247.29
  5374.2  246.31  5444.9  247.97    5474  247.51  5488.5  249.55  5503.1     249
  5530.7  250.64  5657.1  254.28  5717.1  257.84  5802.4  260.73    5845   263.8
#Mann= 5 ,-1 , 0
  4383.4     .17       0  4529.7     .11       0  4706.9     .06       0
  5295.2     .17       0  5657.1     .11       0
Bank Sta=4706.9,5295.2
XS Rating Curve= 0 ,0
Exp/Cntr=0.3,0.1

Type RM Length L Ch R = 1 ,6843    ,131,131,131
BEGIN DESCRIPTION:
MOUND CREEK TRIBUTARY NO. 1 6.0
END DESCRIPTION:
XS GIS Cut Line= 4
      3783500.34     10115110.52      3782923.97      10115100.1
      3782555.92      10115263.3      3782142.85     10115586.07
#Sta/Elev= 30
  3973.7  252.54  4016.2  250.91  4076.2  246.95  4126.2  245.11  4156.2  242.26
  4166.2  242.55  4186.2  244.87  4215.6  243.41  4220.6  243.81  4236.2  242.12
  4266.2  241.74  4376.3   242.1  4494.5  240.97  4516.3  241.78  4882.6  241.89
  4905.9  243.83  4928.8  243.84    4957  242.35  5027.5   241.7  5056.5  243.82
  5064.5  243.24  5141.5  246.08  5220.2  247.32  5269.9  249.61  5327.8  250.27
  5398.3  252.22  5412.8  252.91  5419.9  254.23  5433.6  253.71    5477  254.88
#Mann= 3 , 0 , 0
  3973.7     .11       0  4220.6     .06       0  4905.9     .11       0
Bank Sta=4220.6,4905.9
XS Rating Curve= 0 ,0
Exp/Cntr=0.3,0.1

Type RM Length L Ch R = 1 ,6712    ,109,109,109
BEGIN DESCRIPTION:
Mapping XS a98ea465
END DESCRIPTION:
XS GIS Cut Line= 5
      3783479.54     10115072.33      3783087.17      10115037.6
      3782979.53     10115034.13      3782875.36     10115058.44
      3782052.66     10115415.98
#Sta/Elev= 30
  3870.4  253.18  4002.6  245.81  4323.6  246.91  4384.8  245.72  4495.4  246.84
  4547.7  246.12  4563.5  244.47  4646.9   245.3  4683.4  243.68  4693.8  244.81
 4695.43243.5709  4697.5  241.65    4701  241.65  4705.2  243.54  4722.7  245.42
  4759.7   243.9  4798.5  245.48    4804  243.74    4822  245.18  4845.4  243.78
  4874.3  244.51    4891  243.69  4897.8  244.52  5043.2  244.42  5054.8  245.59
    5185  246.87  5276.8   250.9  5329.1  252.08  5352.6  251.15    5376  252.27
#Mann= 5 ,-1 , 0
  3870.4     .11       0 4695.43     .07       0  4705.2     .11       0
    4891     .15       0  4910.9     .11       0
Bank Sta=4695.43,4705.2
XS Rating Curve= 0 ,0
Exp/Cntr=0.3,0.1

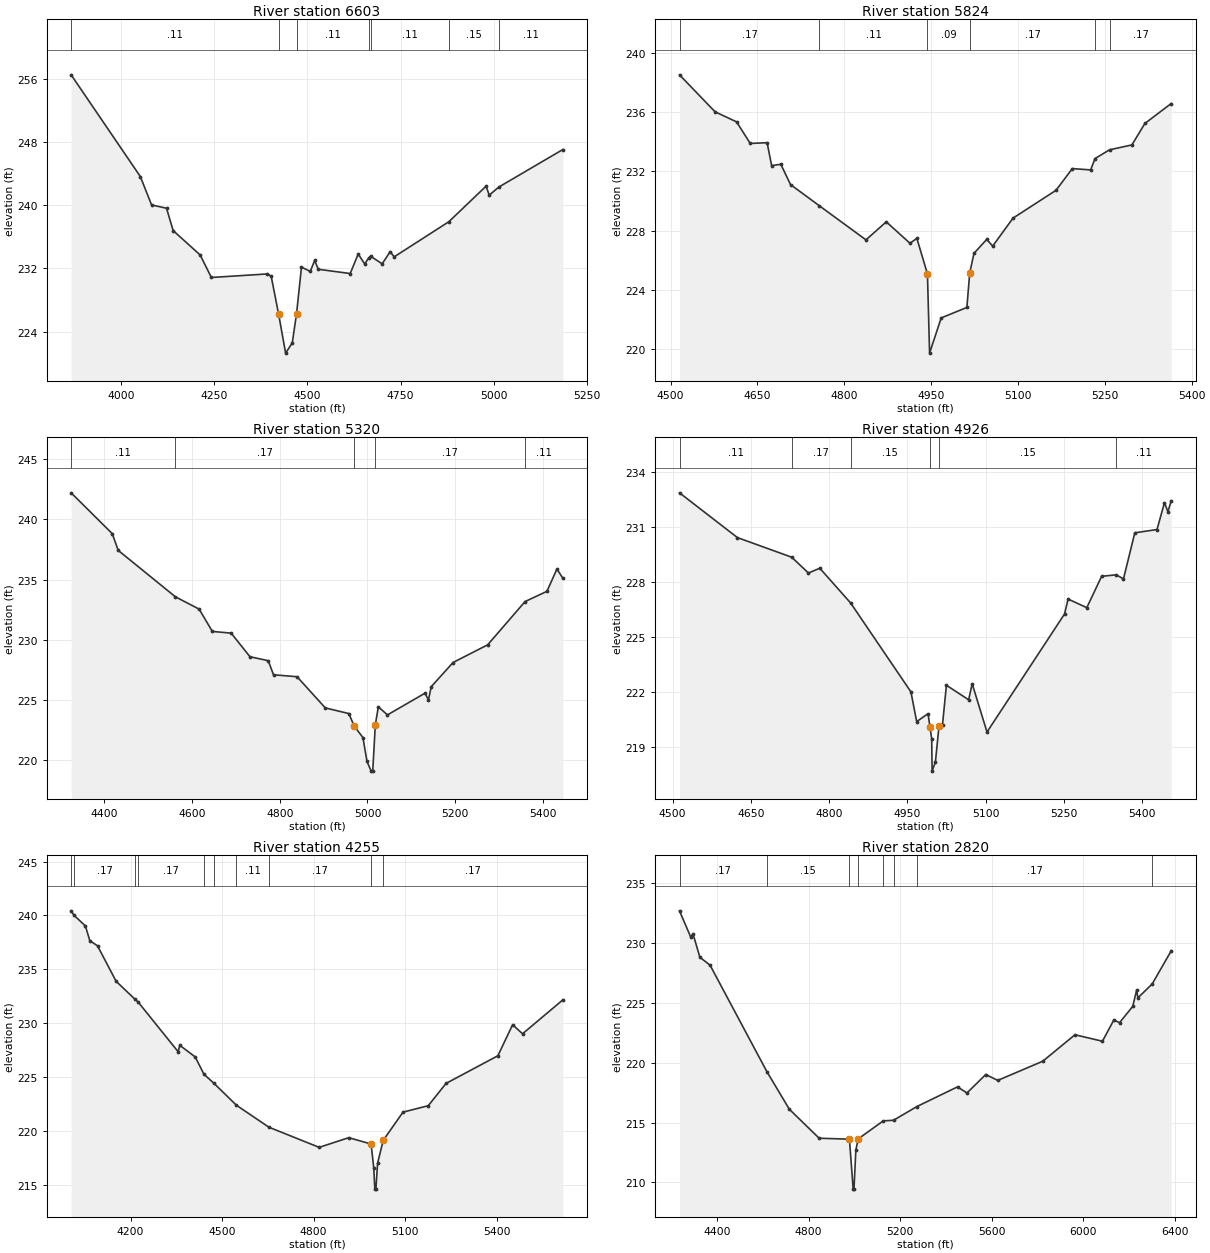
Type RM Length L Ch R = 1 ,6603    ,779,779,779
BEGIN DESCRIPTION:
MOUND CREEK TRIBUTARY NO. 1 5.0
END DESCRIPTION:
XS GIS Cut Line= 3
      3783483.04     10115002.89      3782913.56     10114968.16
      3782215.66     10115235.51
#Sta/Elev= 30
  3866.9  256.49  4052.4  243.62  4082.5  240.03  4122.6  239.61  4140.4  236.78
  4212.7   233.7  4242.8  230.85  4393.1   231.3  4403.1  231.01  4423.1  226.19
  4441.8  221.28  4459.6  222.58 4471.12226.2794  4484.3  232.16  4507.8  231.62
  4519.7  233.01  4529.2  231.89  4614.9  231.35  4636.3  233.82  4653.8  232.56
  4664.6  233.34  4669.5  233.54  4700.6  232.58    4722  234.12  4732.7  233.46
  4879.1   237.9    4979   242.4  4987.5  241.27  5013.5   242.3  5184.8  247.04
#Mann= 7 ,-1 , 0
  3866.9     .11       0  4423.1     .09       0 4471.12     .11       0
  4664.6     .15       0  4669.5     .11       0  4879.1     .15       0
  5013.5     .11       0
Bank Sta=4423.1,4471.12
XS Rating Curve= 0 ,0
Exp/Cntr=0.3,0.1

Type RM Length L Ch R = 1 ,5824    ,504,504,504
BEGIN DESCRIPTION:
MOUND CREEK TRIBUTARY NO. 1 4.0
END DESCRIPTION:
XS GIS Cut Line= 3
      3783184.42     10114548.01      3782738.23     10114736.84
      3782417.84     10114911.08
#Sta/Elev= 30
  4515.5  238.53  4576.9  236.03    4614  235.35  4637.7  233.89  4666.8  233.94
  4674.6  232.39  4690.5  232.48  4707.2  231.11  4757.2  229.67  4837.5  227.37
  4872.6  228.59  4913.5  227.14  4925.4  227.47  4943.7  225.07  4947.4  219.71
  4967.4  222.09  5011.8   222.8 5016.72225.1334  5024.1  226.46    5046   227.4
  5056.4  226.95  5091.5  228.84  5165.7  230.72  5193.9  232.19  5225.5   232.1
  5233.2  232.87  5258.2  233.46  5296.8  233.79  5319.2  235.24  5364.7  236.59
#Mann= 6 ,-1 , 0
  4515.5     .17       0  4757.2     .11       0  4943.7     .09       0
 5016.72     .17       0  5233.2     .11       0  5258.2     .17       0
Bank Sta=4943.7,5016.72
XS Rating Curve= 0 ,0
Exp/Cntr=0.3,0.1

Type RM Length L Ch R = 1 ,5320    ,394,394,394
BEGIN DESCRIPTION:
MOUND CREEK TRIBUTARY NO. 1 3.0
END DESCRIPTION:
XS GIS Cut Line= 3
      3783167.86     10114161.07      3782538.23     10114406.84
      3782267.87     10114761.05
#Sta/Elev= 30
  4324.1  242.21  4417.9  238.82  4431.5  237.43  4561.8  233.58  4616.1  232.55
  4646.2   230.7  4689.1  230.56    4732   228.6  4773.7  228.27  4785.7   227.1
  4839.4  226.94  4903.8  224.35  4957.5  223.88 4969.61 222.851  4989.7  221.88
  4998.9   219.9  5008.5   219.1    5012   219.1  5017.9  222.95  5024.8  224.44
  5045.6  223.77  5131.1  225.57  5139.1  225.02  5145.4  226.11  5195.2  228.12
  5274.2  229.59  5359.4  233.18  5409.3  234.03  5432.1  235.88  5445.6  235.12
#Mann= 5 ,-1 , 0
  4324.1     .11       0  4561.8     .17       0 4969.61     .09       0
  5017.9     .17       0  5359.4     .11       0
Bank Sta=4969.61,5017.9
XS Rating Curve= 0 ,0
Exp/Cntr=0.3,0.1

Type RM Length L Ch R = 1 ,4926    ,671,671,671
BEGIN DESCRIPTION:
MOUND CREEK TRIBUTARY NO. 1 2.0
END DESCRIPTION:
XS GIS Cut Line= 3
      3782844.15     10113881.34      3782398.23     10114076.84
      3782059.36     10114381.38
#Sta/Elev= 30
  4513.1  232.84  4624.1   230.4  4728.2  229.33  4760.2  228.47    4782  228.73
    4841  226.84  4956.7  221.99  4967.7  220.37  4989.5   220.8 4993.07220.1013
  4996.5  219.43  4997.3  217.67  5003.6  218.17  5010.5  220.12  5017.2   220.2
  5024.7  222.35  5067.3  221.56  5074.1  222.43  5102.5   219.8  5251.2  226.24
  5257.9  227.05  5293.8  226.58  5322.2  228.29  5350.2  228.37  5364.1  228.15
  5385.8  230.66  5428.4  230.84  5442.6   232.3  5449.3  231.81  5455.6  232.41
#Mann= 6 ,-1 , 0
  4513.1     .11       0  4728.2     .17       0    4841     .15       0
 4993.07     .09       0  5010.5     .15       0  5350.2     .11       0
Bank Sta=4993.07,5010.5
XS Rating Curve= 0 ,0
Exp/Cntr=0.3,0.1

Type RM Length L Ch R = 1 ,4255    ,1435,1435,1435
BEGIN DESCRIPTION:
Mapping XS ebb74396
END DESCRIPTION:
XS GIS Cut Line= 4
      3782871.93     10113405.65      3781986.47     10113728.58
      3781847.58     10113777.19      3781753.84     10114291.05
#Sta/Elev= 30
  4005.3  240.43  4014.7  240.02  4052.2  239.02  4066.5  237.66  4091.8  237.18
  4152.9  233.88  4214.2  232.23  4224.9  231.96  4356.2  227.34  4361.5  227.94
    4412  226.86  4440.8  225.25  4473.8   224.4  4547.3  222.37  4653.8  220.33
  4818.5  218.46  4915.5  219.36  4988.7  218.77  4997.4  216.55  5000.9  214.58
  5004.4  214.58  5009.9  216.98  5028.4  219.11  5093.3  221.73  5176.1  222.33
  5234.4   224.4  5404.4  226.97  5452.6  229.85  5485.2  229.01  5617.3  232.16
#Mann= 10 ,-1 , 0
  4005.3     .15       0  4014.7     .17       0  4214.2     .15       0
  4224.9     .17       0  4440.8     .11       0  4473.8     .17       0
  4547.3     .11       0  4653.8     .17       0  4988.7     .09       0
  5028.4     .17       0
Bank Sta=4988.7,5028.4
XS Rating Curve= 0 ,0
Exp/Cntr=0.3,0.1

Type RM Length L Ch R = 1 ,2820    ,1053,1053,1053
BEGIN DESCRIPTION:
MOUND CREEK TRIBUTARY NO. 1 1.0
END DESCRIPTION:
XS GIS Cut Line= 3
      3782746.85     10112846.64      3781833.49     10112911.62
      3781514.26     10114103.54
#Sta/Elev= 30
  4235.4  232.68  4284.5  230.49  4294.5  230.75  4324.6   228.8    4369  228.14
  4617.4  219.25  4715.6  216.11  4845.9  213.69 4978.25213.6122  4994.6  209.44
  4998.1  209.44  5006.3  212.69  5016.4  213.63  5126.1  215.14    5171  215.19
  5272.5  216.33  5450.7  217.98  5492.1  217.47  5574.2  219.01  5626.7  218.52
  5823.4  220.12  5964.2  222.33  6084.3  221.79    6134  223.56  6159.2  223.34
  6216.8   224.7  6234.1  226.08  6239.3  225.41    6302  226.58    6385  229.34
#Mann= 8 ,-1 , 0
  4235.4     .17       0  4617.4     .15       0 4978.25     .09       0
  5016.4     .15       0  5126.1     .17       0    5171     .15       0
  5272.5     .17       0    6302     .11       0
Bank Sta=4978.25,5016.4
XS Rating Curve= 0 ,0
Exp/Cntr=0.3,0.1

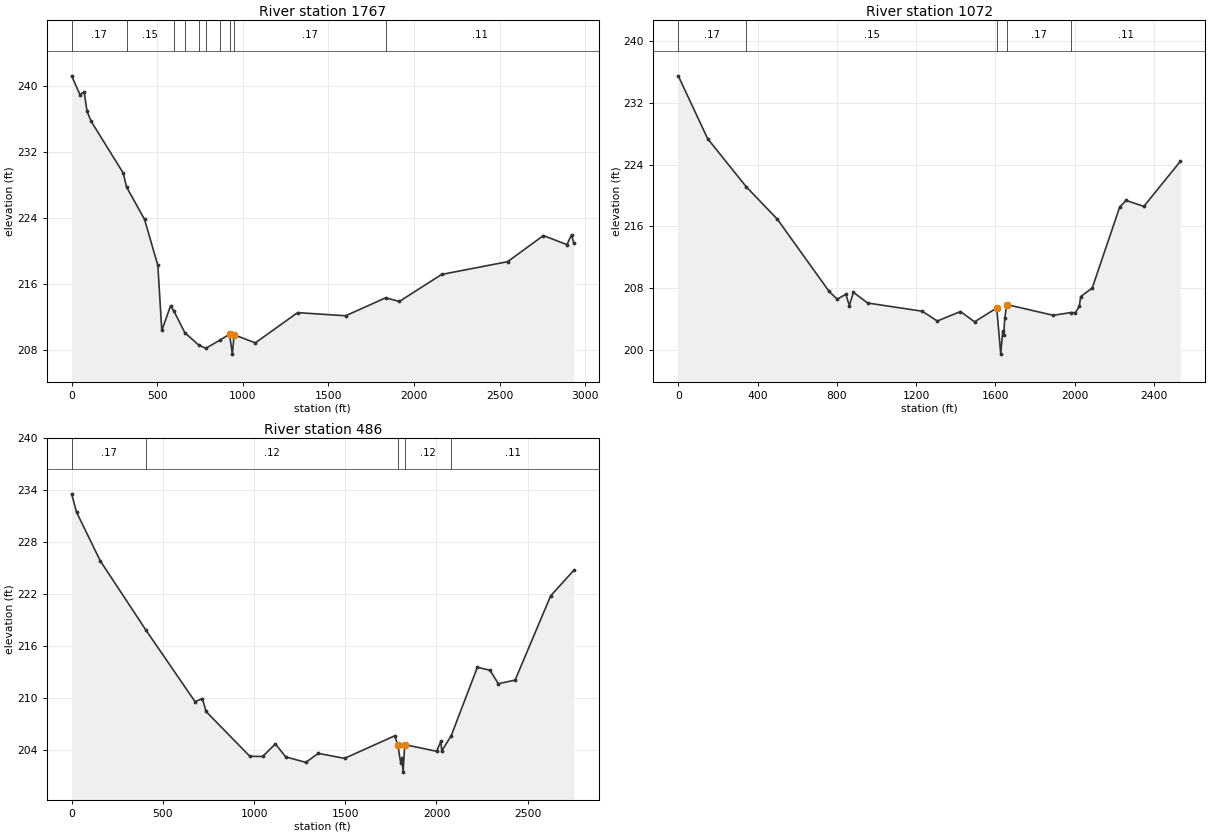
Type RM Length L Ch R = 1 ,1767    ,695,695,695
BEGIN DESCRIPTION:
MOUND CREEK TRIBUTARY NO. 1 0.5
END DESCRIPTION:
XS GIS Cut Line= 3
      3783248.84     10111914.12      3781990.16     10112226.62
      3781521.41     10113793.46
#Sta/Elev= 30
       0  241.18    48.5  238.91    73.1  239.24    89.9  236.89   114.4  235.66
   301.8   229.4   320.4  227.74   425.9  223.81   503.4  218.25   526.5  210.39
     578  213.37   598.6  212.68   660.5  210.13   742.9   208.6   784.1  208.23
   866.5  209.22   922.2  209.93   938.6  207.52     949  209.86  1072.6  208.88
  1319.8  212.54  1600.3  212.16  1833.9  214.33  1913.8  213.89  2161.2  217.16
  2546.2   218.7  2755.3  221.86  2892.9  220.76  2919.4  221.96  2932.3  220.99
#Mann= 10 ,-1 , 0
       0     .17       0   320.4     .15       0   598.6     .12       0
   660.5     .15       0   742.9     .17       0   784.1     .15       0
   866.5     .17       0   922.2     .14       0     949     .17       0
  1833.9     .11       0
#Block Obstruct= 2 , 0
          578.85  213.28
Bank Sta=922.2,949
XS Rating Curve= 0 ,0
Exp/Cntr=0.3,0.1

Type RM Length L Ch R = 1 ,1072    ,586,586,586
BEGIN DESCRIPTION:
MOUND CREEK TRIBUTARY NO. 1 0.4
END DESCRIPTION:
XS GIS Cut Line= 3
      3783273.15     10111434.95      3782171.72     10111663.33
      3780786.73     10111915.94
#Sta/Elev= 30
       0   235.5   148.3  227.36   342.4  221.15   499.4  216.95   761.2  207.58
     802  206.57   845.4  207.21   863.3  205.75   883.7  207.47   955.2  206.08
  1230.4  205.02    1307  203.75  1423.7  204.98  1494.7  203.64  1606.5  205.44
  1626.9  199.46  1636.8  202.48  1641.9  201.96  1647.2  204.13  1657.4  205.88
  1891.2  204.49  1982.6  204.85    2003  204.82  2023.3  205.65  2030.1  206.91
  2088.5  208.03  2226.6  218.48  2258.5  219.37  2348.6  218.59  2532.7  224.42
#Mann= 5 ,-1 , 0
       0     .17       0   342.4     .15       0  1606.5     .06       0
  1657.4     .17       0  1982.6     .11       0
Bank Sta=1606.5,1657.4
XS Rating Curve= 0 ,0
Exp/Cntr=0.3,0.1

Type RM Length L Ch R = 1 ,486     ,0,0,0
BEGIN DESCRIPTION:
MOUND CREEK TRIBUTARY NO. 1 0.3
END DESCRIPTION:
XS GIS Cut Line= 3
      3783304.53     10111112.99      3782129.18      10111090.2
      3780696.02     10111747.75
#Sta/Elev= 30
       0  233.57    26.7  231.46   156.7  225.83   406.8  217.83   676.8  209.54
   716.8  209.91   736.8  208.41   976.9  203.23  1046.9  203.21  1116.9  204.66
  1173.7  203.16  1283.6  202.53  1352.5  203.57    1496  202.99  1771.2   205.6
  1788.4  204.52  1804.2  202.43  1811.4  203.03  1816.9   201.4  1826.2  204.58
  2000.8  203.81  2023.8  204.95  2029.3  203.86  2080.8  205.61  2224.3  213.52
  2293.2  213.18  2339.2  211.62  2431.2  212.04  2626.1  221.78  2752.4  224.72
#Mann= 5 ,-1 , 0
       0     .17       0   406.8     .12       0  1788.4     .06       0
  1826.2     .12       0  2080.8     .11       0
Bank Sta=1788.4,1826.2
XS Rating Curve= 0 ,0
Exp/Cntr=0.3,0.1

Chan Stop Cuts=-1
Use User Specified Reach Order=0
Composite Channel Slope=5