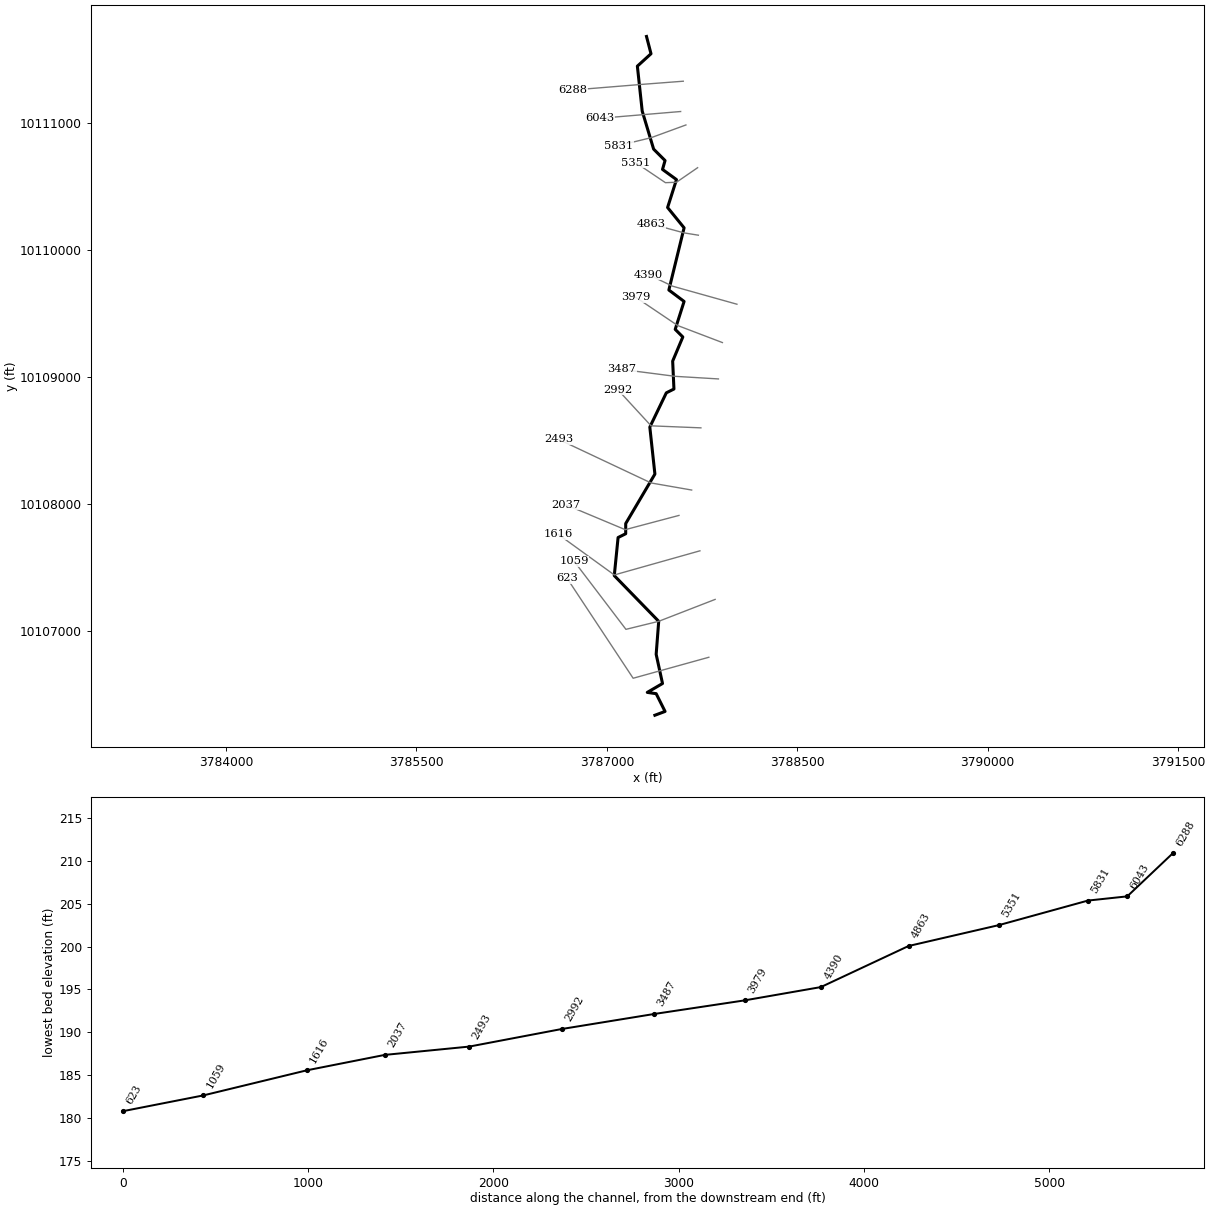
--- MOUND CREEK TRIBUTARY NO 2.prj (project) ---

Proj Title=MOUND CREEK TRIBUTARY NO 2 Base Level Engineering
Current Plan=p01
Default Exp/Contr=0.3,0.1
English Units
Geom File=g01
Flow File=f01
Plan File=p01
Y Axis Title=Elevation
X Axis Title(PF)=Main Channel Distance
X Axis Title(XS)=Station
BEGIN DESCRIPTION:
MOUND CREEK TRIBUTARY NO 2
END DESCRIPTION:
DSS Export Rating Curves= 0
DSS Export Rating Curve Sorted= 0
DSS Export Volume Flow Curves= 0
DXF OffsetX= 0
DXF OffsetY= 0
DXF ScaleX= 1
DXF ScaleY= 10

--- MOUND CREEK TRIBUTARY NO 2.p01 (plan) ---

Plan Title=Multiple Run
Short Identifier=Multiple
Geom File=g01
Flow File=f01
Subcritical Flow
K Sum by GR= 0
Std Step Tol= 0.01
Critical Tol= 0.01
Num of Std Step Trials= 20
Max Error Tol= 0.3
Flow Tol Ratio= 0.001
Split Flow NTrial= 30
Split Flow Tol= 0.02
Split Flow Ratio= 0.02
Log Output Level= 0
Friction Slope Method= 1
Unsteady Friction Slope Method= 2
Unsteady Bridges Friction Slope Method= 1
Parabolic Critical Depth
Global Vel Dist=  1 , 1 , 1
Global Log Level= 0
CheckData=True
Encroach Param= -1, 0, 0, 0
BEGIN DESCRIPTION:
Multiple Run
END DESCRIPTION:

--- MOUND CREEK TRIBUTARY NO 2.f01 (steady flow) ---

Flow Title=Multiple
Program Version=4.10
Number of Profiles= 7
Profile Names=10-year,25-year,50-year,1pct_min,100-year,1pct_plu,500-year
River Rch & RM=MOUND CREEK TRIB,Reach-1         ,6288
     508     678     907     400    1209    3651    2215
River Rch & RM=MOUND CREEK TRIB,Reach-1         ,5831
     821    1130    1544     694    2097    6333    3996
River Rch & RM=MOUND CREEK TRIB,Reach-1         ,2493
     792    1082    1471     657    1985    5995    3736
Boundary for River Rch & Prof#=MOUND CREEK TRIB,Reach-1         , 1
Up Type= 0
Dn Type= 3
Dn Slope=0.005
Boundary for River Rch & Prof#=MOUND CREEK TRIB,Reach-1         , 2
Up Type= 0
Dn Type= 3
Dn Slope=0.005
Boundary for River Rch & Prof#=MOUND CREEK TRIB,Reach-1         , 3
Up Type= 0
Dn Type= 3
Dn Slope=0.005
Boundary for River Rch & Prof#=MOUND CREEK TRIB,Reach-1         , 4
Up Type= 0
Dn Type= 3
Dn Slope=0.005
Boundary for River Rch & Prof#=MOUND CREEK TRIB,Reach-1         , 5
Up Type= 0
Dn Type= 3
Dn Slope=0.005
Boundary for River Rch & Prof#=MOUND CREEK TRIB,Reach-1         , 6
Up Type= 0
Dn Type= 3
Dn Slope=0.005
Boundary for River Rch & Prof#=MOUND CREEK TRIB,Reach-1         , 7
Up Type= 0
Dn Type= 3
Dn Slope=0.005
DSS Import GetInterval= 0
DSS Import GetPeak= 0
DSS Import FillOption= 0

--- MOUND CREEK TRIBUTARY NO 2.g01 (geometry) ---

Geom Title=Existing Conditions
Program Version=4.10

River Reach=MOUND CREEK TRIB,Reach-1
Reach XY= 30
      3787312.14     10111684.38      3787347.55     10111548.26
      3787240.15     10111450.46      3787278.23     10111096.84
      3787368.23     10110796.84      3787458.23     10110706.84
      3787438.23     10110636.84      3787548.23     10110556.84
      3787478.23     10110336.84      3787608.23     10110176.84
      3787488.23     10109686.84      3787608.23     10109596.84
      3787538.23     10109376.84      3787598.23     10109316.84
      3787518.23     10109126.84      3787528.23     10108906.84
      3787468.23     10108876.84      3787338.23     10108606.84
      3787378.23     10108236.84      3787148.23     10107846.84
      3787148.23     10107766.84      3787088.23     10107736.84
      3787058.23     10107436.84      3787408.23     10107076.84
      3787388.23     10106816.84      3787438.23     10106586.84
      3787318.23     10106516.84      3787388.23     10106506.84
      3787458.23     10106366.84      3787378.23     10106336.84

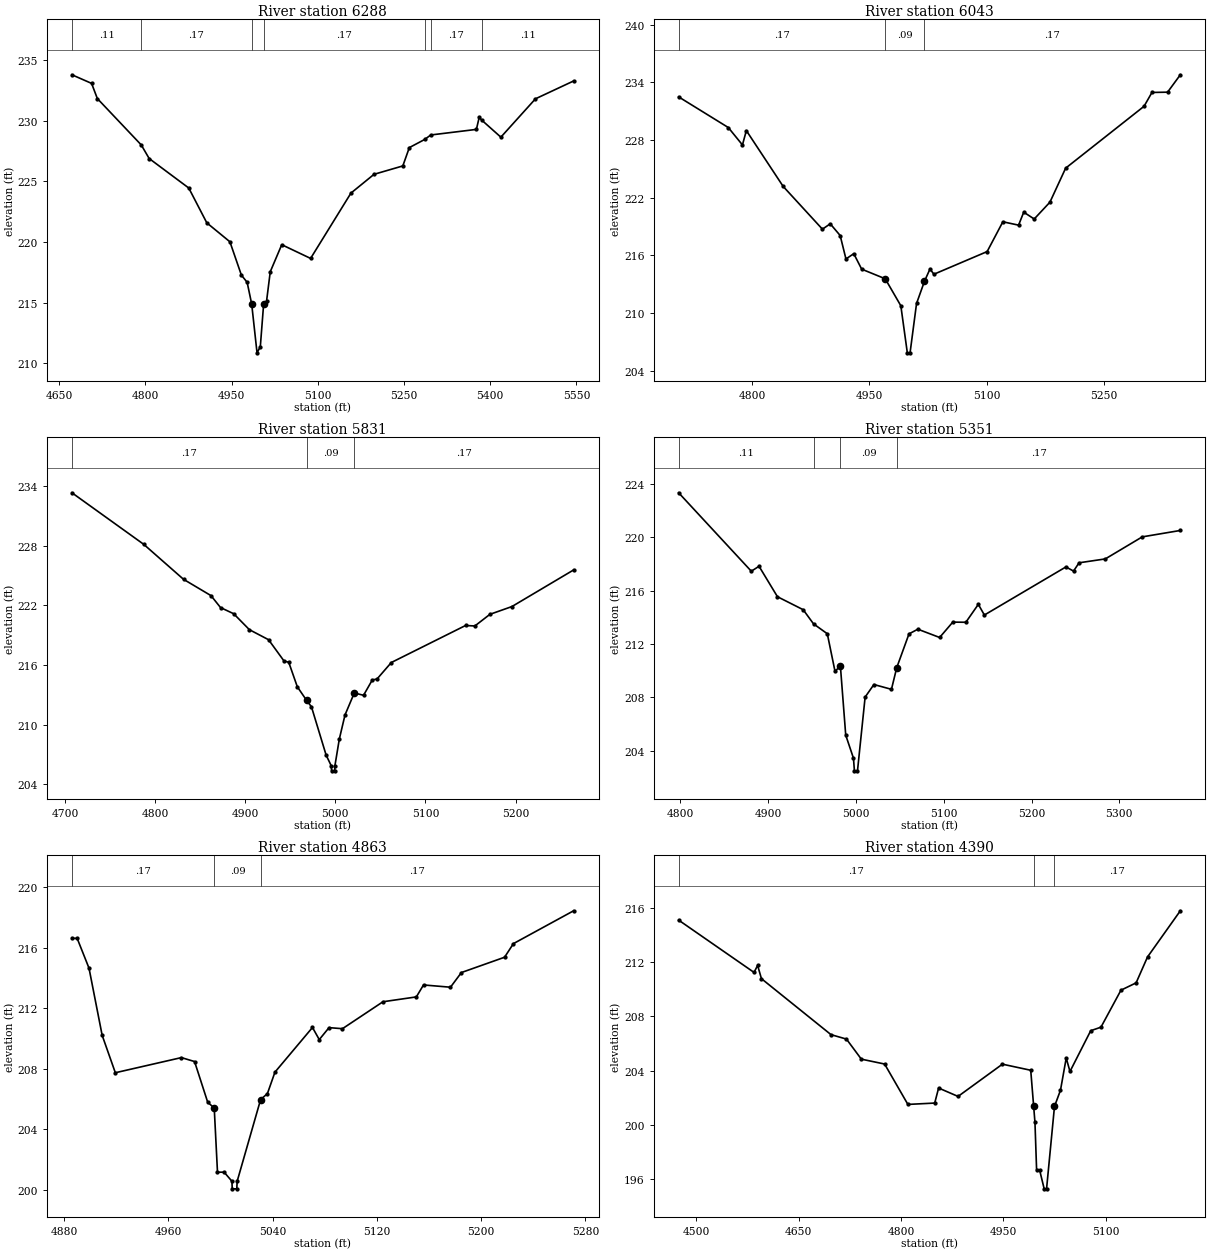
Type RM Length L Ch R = 1 ,6288    ,245,245,245
BEGIN DESCRIPTION:
MOUND CREEK TRIBUTARY NO. 2 13.0
END DESCRIPTION:
XS GIS Cut Line= 3
      3787601.91     10111331.87      3787275.06     10111306.84
      3786731.67     10111262.54
#Sta/Elev= 30
  4672.2  233.78  4706.4  233.07  4716.4  231.82  4792.8     228  4806.6  226.88
  4875.5  224.45  4906.9  221.58  4947.1  220.02  4967.1  217.27  4977.1  216.68
    4985214.8889  4994.3  210.87    5000  211.37  5005.8   214.9  5010.8   215.1
  5017.3  217.55  5037.3  219.78  5087.5  218.65  5157.7  224.03  5197.9  225.58
    5248  226.27  5259.3  227.78    5286  228.45  5296.6  228.82    5376  229.28
    5381  230.29  5384.9  230.06  5418.6  228.64  5478.8   231.8  5545.2  233.27
#Mann= 7 ,-1 , 0
  4672.2     .11       0  4792.8     .17       0    4985     .09       0
  5005.8     .17       0    5286     .11       0  5296.6     .17       0
  5384.9     .11       0
Bank Sta=4985,5005.8
XS Rating Curve= 0 ,0
Exp/Cntr=0.3,0.1

Type RM Length L Ch R = 1 ,6043    ,212,212,212
BEGIN DESCRIPTION:
Mapping XS c156bc15
END DESCRIPTION:
XS GIS Cut Line= 2
       3787581.1     10111093.16      3786941.65     10111039.44
#Sta/Elev= 30
  4706.1   232.5  4769.6  229.31  4787.7   227.5  4792.7  228.99  4839.8  223.18
    4890  218.73    4900  219.29  4912.7  218.07  4920.1  215.63  4930.1  216.18
  4940.2  214.57  4970.3  213.57  4990.3  210.76  4998.6  205.86  5002.1  205.86
  5010.4     211  5020.5   213.3  5027.6  214.59  5032.6  214.04  5100.7   216.4
  5120.8   219.5  5140.9  219.15  5147.5   220.5  5160.9  219.79    5181  221.54
  5201.1  225.08  5301.4  231.52  5311.5  232.96  5331.5  232.99  5347.8   234.8
#Mann= 3 , 0 , 0
  4706.1     .17       0  4970.3     .09       0  5020.5     .17       0
Bank Sta=4970.3,5020.5
XS Rating Curve= 0 ,0
Exp/Cntr=0.3,0.1

Type RM Length L Ch R = 1 ,5831    ,480,480,480
BEGIN DESCRIPTION:
MOUND CREEK TRIBUTARY NO. 2 12.0
END DESCRIPTION:
XS GIS Cut Line= 3
      3787622.74     10110987.25      3787348.23     10110886.84
       3787091.3     10110824.44
#Sta/Elev= 30
  4707.7   233.3  4787.4  228.12  4831.5  224.61    4862  222.97  4872.6  221.77
  4887.2  221.15  4904.6  219.55  4925.9  218.54  4942.9  216.42  4948.3  216.27
  4957.8  213.81  4968.1  212.45  4973.5   211.8  4989.8  206.94  4995.5  205.87
  4995.8  205.37  4999.3  205.37  4999.5  205.87  5004.4  208.56  5010.7  210.98
    5021  213.19  5031.3  212.96    5041   214.5  5046.2  214.59  5062.1  216.25
  5144.5  219.97  5154.8  219.92  5171.5  221.09  5195.9  221.87  5264.4  225.55
#Mann= 3 , 0 , 0
  4707.7     .17       0  4968.1     .09       0    5021     .17       0
Bank Sta=4968.1,5021
XS Rating Curve= 0 ,0
Exp/Cntr=0.3,0.1

Type RM Length L Ch R = 1 ,5351    ,488,488,488
BEGIN DESCRIPTION:
MOUND CREEK TRIBUTARY NO. 2 11.0
END DESCRIPTION:
XS GIS Cut Line= 4
      3787714.77     10110650.45       3787548.1     10110535.87
      3787461.29     10110532.53      3787226.92     10110690.38
#Sta/Elev= 30
  4797.9  223.32  4880.7  217.45  4889.5  217.82  4910.5  215.54  4939.8  214.57
  4951.6  213.51  4967.3  212.77  4976.1  209.95  4982.2  210.37  4988.3  205.18
  4997.1  203.46  4998.2  202.51  5001.7  202.51  5010.4  208.03  5020.4  208.97
  5040.4  208.61 5046.43210.2321  5060.4  212.76  5070.5  213.11  5095.3  212.49
  5110.3  213.64  5125.2  213.63  5139.4  214.97  5146.3  214.17  5239.2  217.77
  5247.9  217.46  5254.2  218.08  5284.1  218.37  5326.2  220.02  5369.6   220.5
#Mann= 4 ,-1 , 0
  4797.9     .11       0  4951.6     .17       0  4982.2     .09       0
 5046.43     .17       0
Bank Sta=4982.2,5046.43
XS Rating Curve= 0 ,0
Exp/Cntr=0.3,0.1

Type RM Length L Ch R = 1 ,4863    ,473,473,473
BEGIN DESCRIPTION:
MOUND CREEK TRIBUTARY NO. 2 10.0
END DESCRIPTION:
XS GIS Cut Line= 3
      3787720.77     10110118.67      3787608.23     10110136.84
      3787346.67     10110207.76
#Sta/Elev= 30
    4886  216.62    4890  216.62  4899.1  214.65  4909.2  210.21  4919.3  207.74
    4970  208.74  4980.1  208.48  4990.2  205.79  4995.2  205.41  4997.7  201.17
  5002.8  201.17  5008.8  200.57    5009  200.07  5012.5  200.07  5012.8  200.57
  5030.8  205.97    5036  206.36  5041.8  207.78  5070.6  210.73  5075.8  209.93
  5083.3  210.72  5093.6  210.65  5124.7  212.43  5150.3  212.75  5155.8  213.54
  5176.5  213.39  5184.9  214.36    5218  215.37  5224.8  216.27    5271  218.44
#Mann= 3 , 0 , 0
    4886     .17       0  4995.2     .09       0  5030.8     .17       0
Bank Sta=4995.2,5030.8
XS Rating Curve= 0 ,0
Exp/Cntr=0.3,0.1

Type RM Length L Ch R = 1 ,4390    ,411,411,411
BEGIN DESCRIPTION:
MOUND CREEK TRIBUTARY NO. 2 9.0
END DESCRIPTION:
XS GIS Cut Line= 3
      3788024.62     10109574.94      3787518.23     10109716.84
      3787329.32     10109806.72
#Sta/Elev= 30
  4474.1  215.11  4584.6  211.25  4589.8  211.77  4595.4  210.79  4697.3  206.66
    4720  206.33  4741.8  204.85  4775.9  204.49    4810  201.51  4849.3  201.61
    4855  202.72  4883.5   202.1  4948.5  204.48    4990  204.03 4994.23201.4034
  4996.2  200.18  4998.6  196.67    5003  196.67  5009.7  195.28  5013.2  195.28
  5024.8  201.36  5033.6  202.56    5042  204.93  5047.5  203.94  5077.9  206.95
  5092.9  207.21  5122.2  209.94  5144.4  210.48  5161.1  212.39  5209.2   215.8
#Mann= 3 , 0 , 0
  4474.1     .17       0 4994.23     .09       0  5024.8     .17       0
Bank Sta=4994.23,5024.8
XS Rating Curve= 0 ,0
Exp/Cntr=0.3,0.1

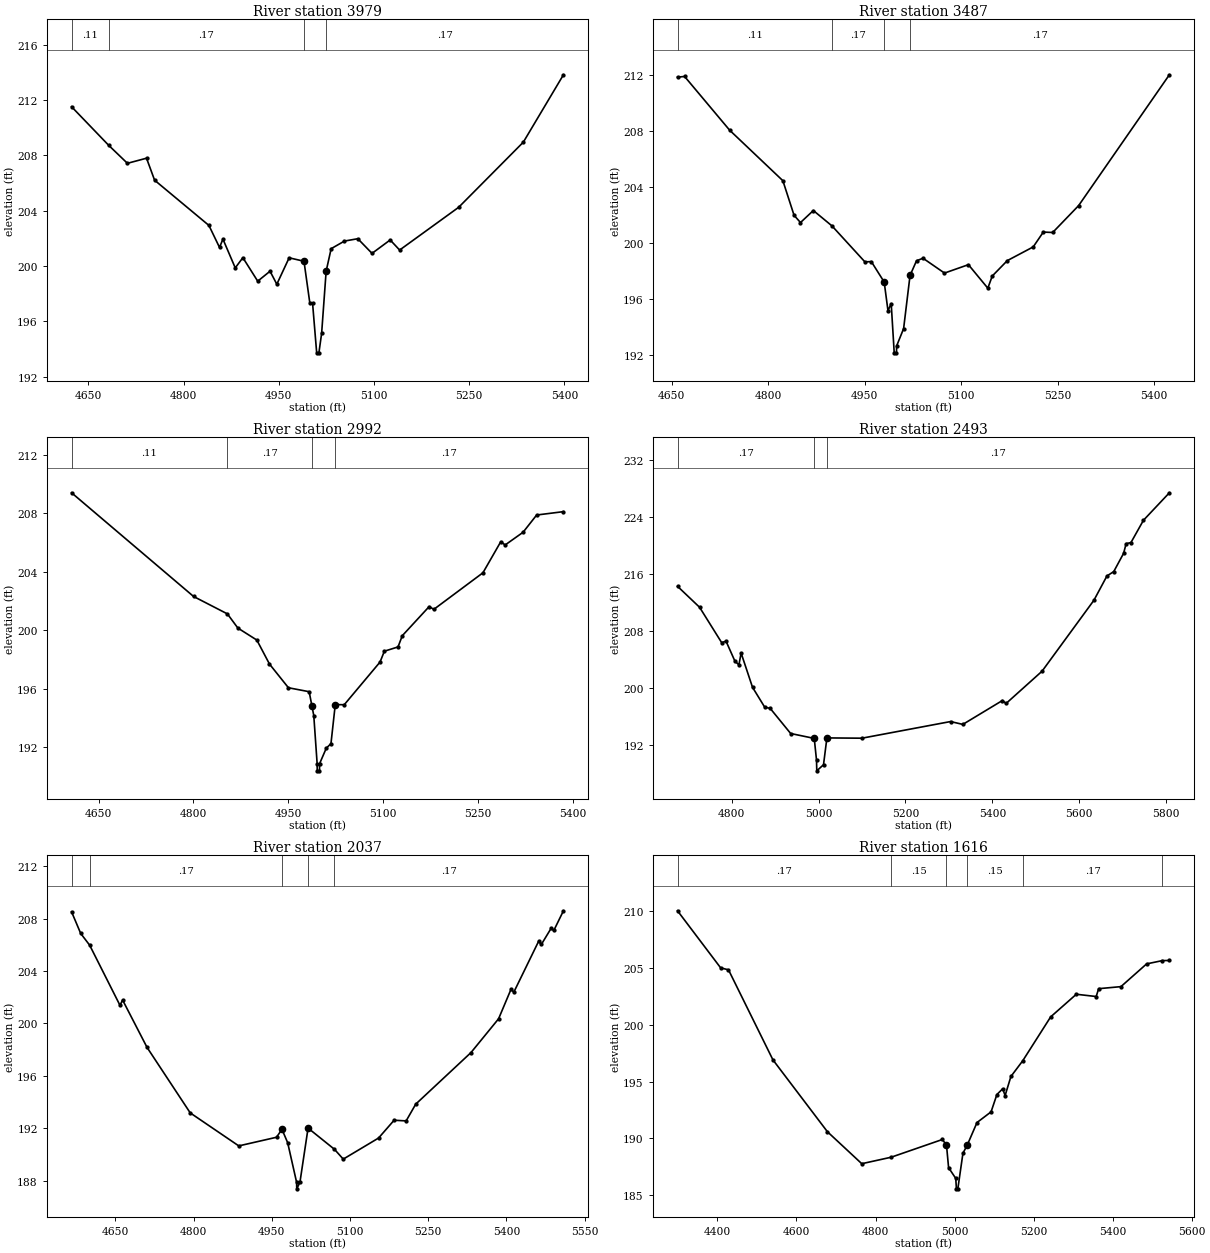
Type RM Length L Ch R = 1 ,3979    ,492,492,492
BEGIN DESCRIPTION:
MOUND CREEK TRIBUTARY NO. 2 8.0
END DESCRIPTION:
XS GIS Cut Line= 3
      3787910.08     10109272.85      3787558.23     10109406.84
      3787227.81     10109629.61
#Sta/Elev= 30
  4623.5  211.52    4682  208.73  4711.5  207.43  4741.6   207.8  4754.3  206.21
  4839.9  202.94  4856.6  201.35    4862  201.95  4881.4  199.87  4893.4  200.61
  4916.8  198.91  4936.2  199.63  4946.9  198.69  4966.3   200.6  4989.7  200.35
  4998.9  197.33  5003.2  197.33  5009.7  193.73  5013.2  193.73  5017.5  195.14
  5024.6  199.63  5032.5  201.26  5053.5  201.81  5074.5  201.98  5096.9  200.92
  5125.5  201.89  5140.4  201.16  5233.4  204.25  5335.3  208.96  5398.5  213.83
#Mann= 4 ,-1 , 0
  4623.5     .11       0    4682     .17       0  4989.7     .09       0
  5024.6     .17       0
Bank Sta=4989.7,5024.6
XS Rating Curve= 0 ,0
Exp/Cntr=0.3,0.1

Type RM Length L Ch R = 1 ,3487    ,495,495,495
BEGIN DESCRIPTION:
MOUND CREEK TRIBUTARY NO. 2 7.0
END DESCRIPTION:
XS GIS Cut Line= 3
      3787878.82     10108986.39      3787538.23     10109006.84
      3787117.81     10109061.08
#Sta/Elev= 30
  4658.8  211.83  4669.8  211.88  4739.9  208.04  4822.7  204.43  4840.1  201.96
  4850.1  201.44  4870.1   202.3  4899.1   201.2  4950.3  198.63  4960.3  198.65
  4980.3  197.19  4986.2  195.14  4991.2  195.65  4995.9  192.13  4999.4  192.13
  4999.7  192.63  5010.5  193.86  5020.5  197.66  5030.6  198.71  5040.7  198.89
  5074.1  197.83  5111.3  198.43  5141.5  196.75  5148.4  197.62  5171.8  198.72
  5212.1   199.7  5227.8  200.76  5242.4  200.73  5282.7  202.65  5423.9     212
#Mann= 4 ,-1 , 0
  4658.8     .11       0  4899.1     .17       0  4980.3     .09       0
  5020.5     .17       0
Bank Sta=4980.3,5020.5
XS Rating Curve= 0 ,0
Exp/Cntr=0.3,0.1

Type RM Length L Ch R = 1 ,2992    ,499,499,499
BEGIN DESCRIPTION:
MOUND CREEK TRIBUTARY NO. 2 6.0
END DESCRIPTION:
XS GIS Cut Line= 3
      3787740.81     10108600.97      3787348.23     10108616.84
      3787087.15     10108900.47
#Sta/Elev= 30
  4607.1   209.4  4800.2  202.31  4853.7  201.12  4870.3  200.15  4900.3  199.33
  4920.3  197.69  4950.3  196.07  4983.1   195.8 4987.43194.8331  4990.4  194.17
  4995.7  190.89  4995.9  190.39  4999.4  190.39  4999.7  190.89  5010.2  191.94
  5017.6  192.25  5024.4  194.92  5038.6  194.91  5095.3  197.83  5102.1  198.57
  5123.7  198.86  5130.5  199.63    5173  201.62  5180.4  201.43  5258.1  203.93
  5286.4  206.06  5293.2  205.83  5321.6   206.7  5343.1  207.88  5385.5  208.11
#Mann= 4 ,-1 , 0
  4607.1     .11       0  4853.7     .17       0 4987.43     .09       0
  5024.4     .17       0
Bank Sta=4987.43,5024.4
XS Rating Curve= 0 ,0
Exp/Cntr=0.3,0.1

Type RM Length L Ch R = 1 ,2493    ,456,456,456
BEGIN DESCRIPTION:
MOUND CREEK TRIBUTARY NO. 2 5.0
END DESCRIPTION:
XS GIS Cut Line= 3
       3787667.9     10108111.06      3787348.23     10108166.84
      3786617.88     10108511.06
#Sta/Elev= 30
  4675.5  214.29  4726.3  211.34  4777.1  206.37  4787.2  206.57  4807.5  203.78
  4816.8  203.24  4821.9   204.9  4848.1  200.09  4876.3  197.28  4888.7  197.13
  4935.9  193.59  4990.2   192.9  4995.4  189.83    4996  188.34  5011.5   189.2
  5019.3  192.97  5099.9  192.93  5303.8  195.27  5332.1  194.87  5423.2  198.23
  5431.6  197.81  5514.4  202.35  5633.8  212.33  5663.7  215.74  5679.4  216.36
  5702.1  218.93  5707.9  220.29    5719  220.44  5747.7  223.57  5807.4  227.44
#Mann= 3 , 0 , 0
  4675.5     .17       0  4990.2     .09       0  5019.3     .17       0
Bank Sta=4990.2,5019.3
XS Rating Curve= 0 ,0
Exp/Cntr=0.3,0.1

Type RM Length L Ch R = 1 ,2037    ,421,421,421
BEGIN DESCRIPTION:
MOUND CREEK TRIBUTARY NO. 2 4.0
END DESCRIPTION:
XS GIS Cut Line= 3
      3787567.85     10107911.07      3787144.46     10107798.89
      3786678.32      10107994.2
#Sta/Elev= 30
  4565.9  208.53  4583.4  206.88  4600.6  205.98  4658.7  201.39  4663.8  201.79
  4710.7  198.17  4793.5  193.17  4886.6  190.65    4959  191.31  4969.4  191.92
  4980.4  190.89  4997.5  187.87  4997.8  187.37  5003.9  187.87  5019.5  192.01
  5070.1  190.39    5087  189.64  5154.7  191.25  5184.5  192.61  5207.6  192.56
    5226  193.84    5332  197.78  5384.9  200.36  5408.7  202.61  5414.1  202.39
  5461.7  206.28  5467.1  206.05  5485.5  207.26  5490.9  207.11  5509.3  208.61
#Mann= 5 ,-1 , 0
  4565.9     .11       0  4600.6     .17       0  4969.4     .09       0
  5019.5     .15       0  5070.1     .17       0
Bank Sta=4969.4,5019.5
XS Rating Curve= 0 ,0
Exp/Cntr=0.3,0.1

Type RM Length L Ch R = 1 ,1616    ,557,557,557
BEGIN DESCRIPTION:
MOUND CREEK TRIBUTARY NO. 2 3.0
END DESCRIPTION:
XS GIS Cut Line= 3
      3787732.98     10107632.22      3787058.52     10107442.12
      3786617.87     10107761.06
#Sta/Elev= 30
  4298.9  210.02  4408.1     205  4427.9  204.83  4540.4  196.91  4678.3  190.59
  4765.2  187.78  4839.6  188.35  4969.2  189.91  4979.6  189.41  4984.9  187.43
    5003  186.49  5004.7  185.57  5008.3  185.57  5021.2   188.7 5031.99189.4085
  5056.8   191.4  5092.4  192.34  5107.1  193.86  5121.8  194.37  5127.9  193.77
  5142.6  195.45  5172.5  196.83  5243.2  200.69  5308.1  202.68  5358.4  202.48
  5364.6  203.17    5421  203.35    5486  205.35  5526.1  205.64  5543.6  205.65
#Mann= 6 ,-1 , 0
  4298.9     .17       0  4839.6     .15       0  4979.6     .09       0
 5031.99     .15       0  5172.5     .17       0  5526.1     .11       0
Bank Sta=4979.6,5031.99
XS Rating Curve= 0 ,0
Exp/Cntr=0.3,0.1

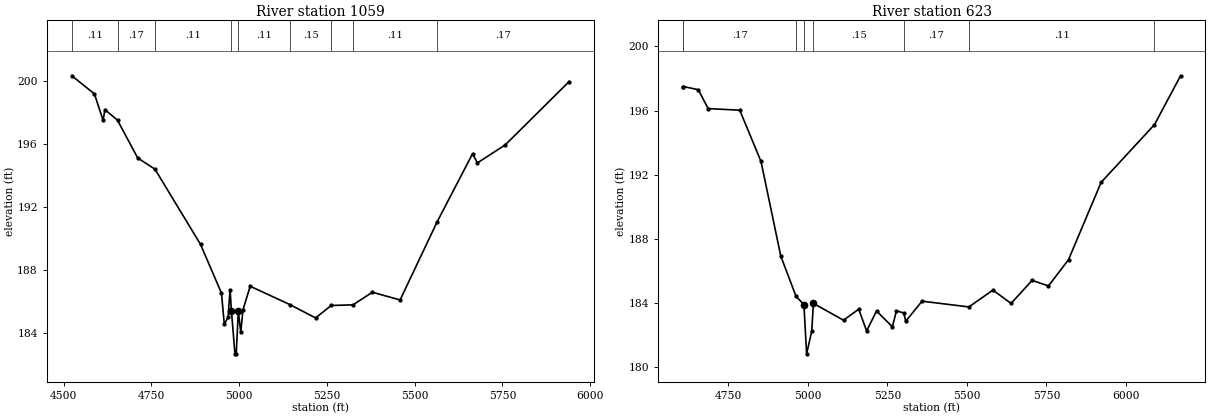
Type RM Length L Ch R = 1 ,1059    ,436,436,436
BEGIN DESCRIPTION:
MOUND CREEK TRIBUTARY NO. 2 2.0
END DESCRIPTION:
XS GIS Cut Line= 4
      3787852.81     10107249.42      3787408.23     10107076.84
      3787150.02     10107013.59      3786741.85     10107550.13
#Sta/Elev= 30
  4523.1   200.3  4587.5  199.15  4612.1  197.47  4617.4  198.15  4653.2  197.48
  4710.8  195.08    4760  194.37  4889.7   189.6  4949.5   186.5  4957.5  184.52
  4968.2  184.98    4974   186.7 4977.95 185.354  4987.8  182.65  4991.5  182.65
  4997.5  185.37  5004.4  184.02  5010.7  185.45  5031.3  186.94    5144  185.78
  5217.6  184.93  5262.2  185.72  5324.2  185.76  5379.4  186.56  5458.4  186.07
  5564.2  191.04  5664.8  195.35  5678.8  194.77  5757.8  195.91    5940  199.93
#Mann= 9 ,-1 , 0
  4523.1     .11       0  4653.2     .17       0    4760     .11       0
 4977.95     .06       0  4997.5     .11       0    5144     .15       0
  5262.2     .17       0  5324.2     .11       0  5564.2     .17       0
Bank Sta=4977.95,4997.5
XS Rating Curve= 0 ,0
Exp/Cntr=0.3,0.1

Type RM Length L Ch R = 1 ,623     ,0,0,0
BEGIN DESCRIPTION:
MOUND CREEK TRIBUTARY NO. 2 1.0
END DESCRIPTION:
XS GIS Cut Line= 3
      3787803.27     10106793.67      3787206.85     10106628.32
      3786686.13     10107416.06
#Sta/Elev= 30
  4608.5  197.49  4608.8   197.5  4655.6   197.3  4686.8  196.12    4786  196.02
  4852.8  192.82  4915.1   186.9    4963  184.39  4987.7  183.88  4996.2   180.8
  5012.4  182.22 5017.44183.9525  5112.2   182.9  5159.9  183.59  5184.9  182.23
    5216  183.48  5265.8  182.49  5278.7  183.49  5301.5  183.35  5307.9  182.84
  5359.1  184.09  5506.3  183.73  5581.8  184.78  5638.9  183.95  5705.2  185.39
  5756.4  185.04  5819.5  186.68  5921.9  191.51  6089.8  195.12  6171.7  198.17
#Mann= 8 ,-1 , 0
  4608.5     .11       0  4608.8     .17       0    4963     .15       0
  4987.7     .09       0 5017.44     .15       0  5301.5     .17       0
  5506.3     .11       0  6089.8     .17       0
Bank Sta=4987.7,5017.44
XS Rating Curve= 0 ,0
Exp/Cntr=0.3,0.1

Chan Stop Cuts=-1
Use User Specified Reach Order=0
Composite Channel Slope=5