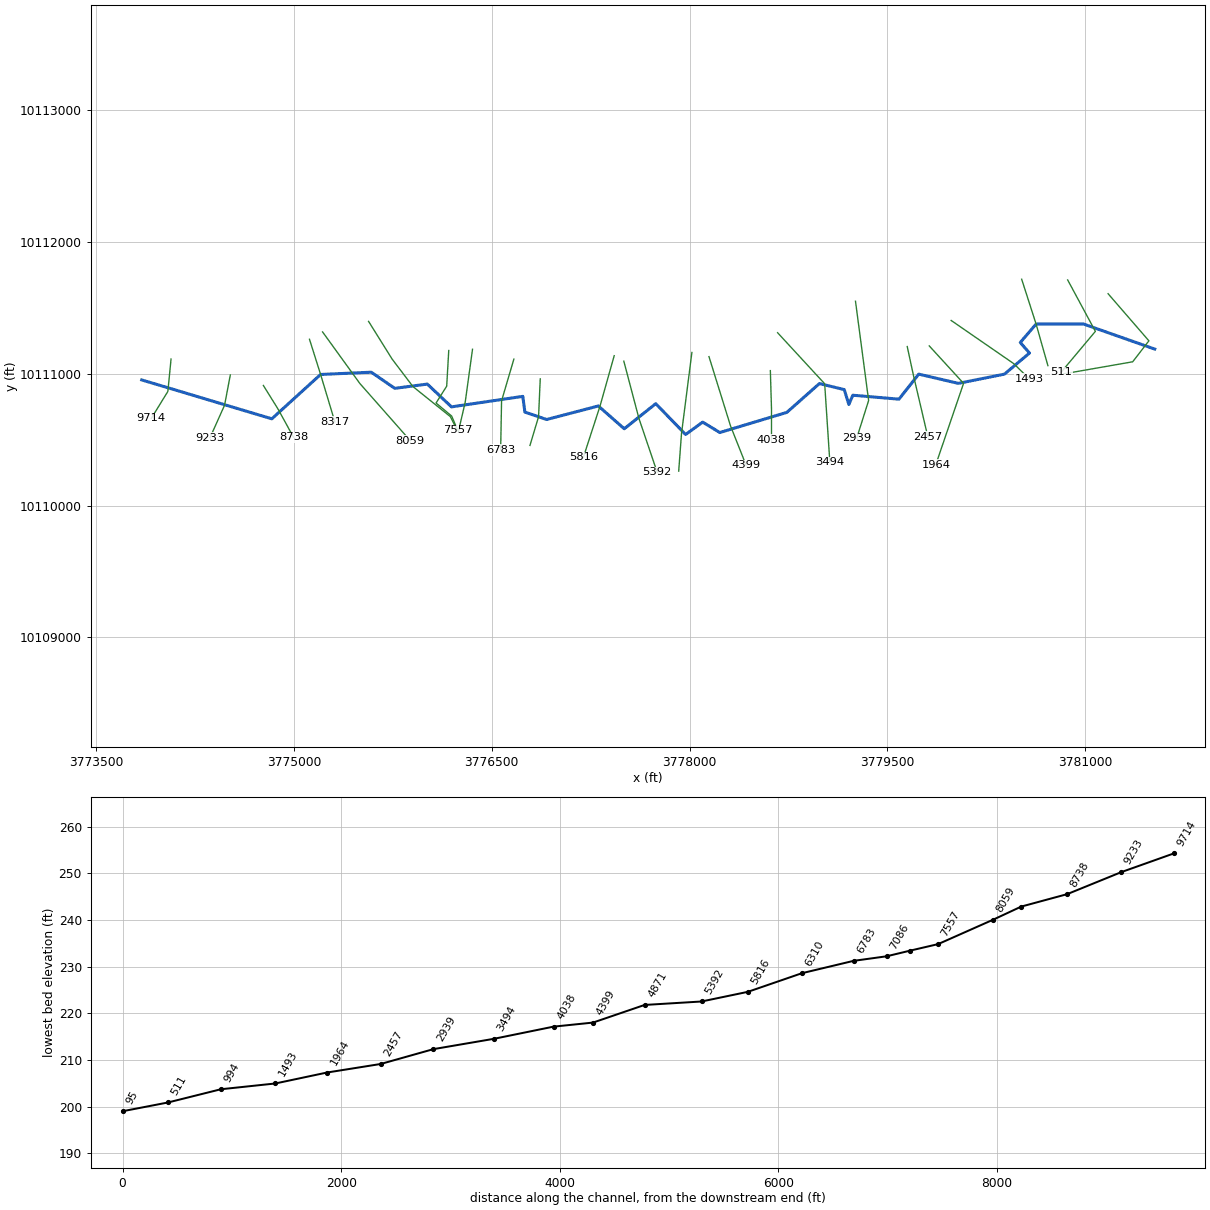
--- MOUND CREEK TRIBUTARY NO 3.prj (project) ---

Proj Title=MOUND CREEK TRIBUTARY NO 3 Base Level Engineering
Current Plan=p01
Default Exp/Contr=0.3,0.1
English Units
Geom File=g01
Flow File=f01
Plan File=p01
Y Axis Title=Elevation
X Axis Title(PF)=Main Channel Distance
X Axis Title(XS)=Station
BEGIN DESCRIPTION:
MOUND CREEK TRIBUTARY NO 3
END DESCRIPTION:
DSS Export Rating Curves= 0
DSS Export Rating Curve Sorted= 0
DSS Export Volume Flow Curves= 0
DXF OffsetX= 0
DXF OffsetY= 0
DXF ScaleX= 1
DXF ScaleY= 10

--- MOUND CREEK TRIBUTARY NO 3.p01 (plan) ---

Plan Title=Multiple Run
Short Identifier=Multiple
Geom File=g01
Flow File=f01
Subcritical Flow
K Sum by GR= 0
Std Step Tol= 0.01
Critical Tol= 0.01
Num of Std Step Trials= 20
Max Error Tol= 0.3
Flow Tol Ratio= 0.001
Split Flow NTrial= 30
Split Flow Tol= 0.02
Split Flow Ratio= 0.02
Log Output Level= 0
Friction Slope Method= 1
Unsteady Friction Slope Method= 2
Unsteady Bridges Friction Slope Method= 1
Parabolic Critical Depth
Global Vel Dist=  1 , 1 , 1
Global Log Level= 0
CheckData=True
Encroach Param= -1, 0, 0, 0
BEGIN DESCRIPTION:
Multiple Run
END DESCRIPTION:

--- MOUND CREEK TRIBUTARY NO 3.f01 (steady flow) ---

Flow Title=Multiple
Program Version=4.10
Number of Profiles= 7
Profile Names=10-year,25-year,50-year,1pct_min,100-year,1pct_plu,500-year
River Rch & RM=MOUND CREEK TRIB,Reach-1         ,9714
     959    1334    1837     831    2510    7580    4849
River Rch & RM=MOUND CREEK TRIB,Reach-1         ,7304
    1380    1960    2737    1255    3790   11446    7515
Boundary for River Rch & Prof#=MOUND CREEK TRIB,Reach-1         , 1
Up Type= 0
Dn Type= 3
Dn Slope=0.005
Boundary for River Rch & Prof#=MOUND CREEK TRIB,Reach-1         , 2
Up Type= 0
Dn Type= 3
Dn Slope=0.005
Boundary for River Rch & Prof#=MOUND CREEK TRIB,Reach-1         , 3
Up Type= 0
Dn Type= 3
Dn Slope=0.005
Boundary for River Rch & Prof#=MOUND CREEK TRIB,Reach-1         , 4
Up Type= 0
Dn Type= 3
Dn Slope=0.005
Boundary for River Rch & Prof#=MOUND CREEK TRIB,Reach-1         , 5
Up Type= 0
Dn Type= 3
Dn Slope=0.005
Boundary for River Rch & Prof#=MOUND CREEK TRIB,Reach-1         , 6
Up Type= 0
Dn Type= 3
Dn Slope=0.005
Boundary for River Rch & Prof#=MOUND CREEK TRIB,Reach-1         , 7
Up Type= 0
Dn Type= 3
Dn Slope=0.005
DSS Import GetInterval= 0
DSS Import GetPeak= 0
DSS Import FillOption= 0

--- MOUND CREEK TRIBUTARY NO 3.g01 (geometry) ---

Geom Title=Existing Conditions
Program Version=4.10

River Reach=MOUND CREEK TRIB,Reach-1
Reach XY= 30
      3773845.25     10110952.97      3774832.23     10110657.83
      3775202.02     10110994.29      3775586.39     10111011.48
      3775764.52     10110889.08      3776011.39     10110921.37
      3776194.73     10110748.45      3776735.35     10110828.14
       3776751.5     10110708.87      3776916.08     10110652.62
      3777308.27     10110755.23      3777504.97     10110582.48
      3777743.68     10110772.59      3777970.25     10110539.08
      3778099.59     10110632.83       3778229.8     10110553.84
      3778738.23     10110706.84        3778985.     10110925.36
      3779173.37     10110879.36      3779208.23     10110766.84
      3779238.23     10110836.84      3779588.23     10110806.84
      3779738.23     10110996.84      3780038.23     10110926.84
      3780388.23     10110996.84      3780578.23     10111156.84
      3780508.23     10111236.84      3780628.23     10111376.84
      3780988.23     10111376.84      3781528.23     10111186.84

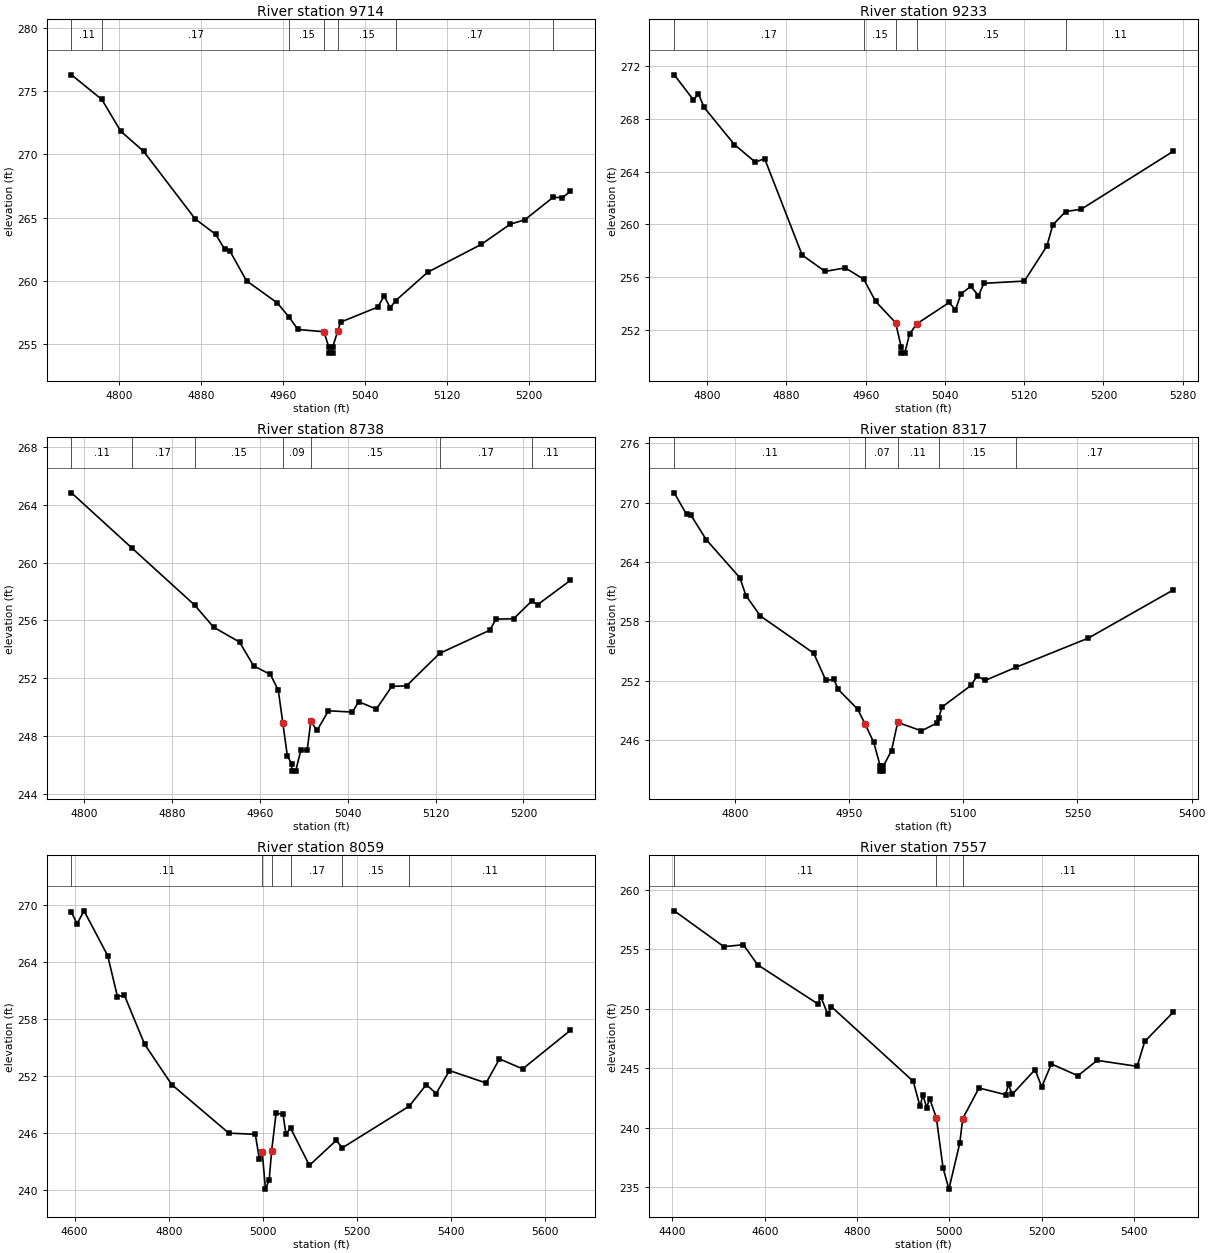
Type RM Length L Ch R = 1 ,9714    ,481,481,481
BEGIN DESCRIPTION:
MOUND CREEK TRIBUTARY NO. 3 20.0
END DESCRIPTION:
XS GIS Cut Line= 3
      3774067.85     10111111.06      3774043.68     10110865.64
      3773917.84     10110661.05
#Sta/Elev= 30
  4753.4  276.28    4783  274.33  4801.5  271.82  4823.7  270.24    4874   264.9
  4894.1  263.67  4902.8  262.51  4907.8  262.38  4924.2     260  4954.4  258.24
  4965.8  257.12  4974.4  256.15  4999.8  255.97  5004.4  254.78  5004.7  254.28
  5008.2  254.28  5008.4  254.78 5013.41256.0655    5016  256.73  5052.3  257.92
  5058.5   258.8  5064.4  257.87  5069.9  258.44  5101.1  260.68  5153.2  262.87
  5181.5  264.47  5195.8  264.82  5223.3  266.59  5232.5  266.58  5240.2  267.06
#Mann= 7 ,-1 , 0
  4753.4     .11       0    4783     .17       0  4965.8     .15       0
  4999.8     .09       0 5013.41     .15       0  5069.9     .17       0
  5223.3     .11       0
Bank Sta=4999.8,5013.41
XS Rating Curve= 0 ,0
Exp/Cntr=0.3,0.1

Type RM Length L Ch R = 1 ,9233    ,495,495,495
BEGIN DESCRIPTION:
MOUND CREEK TRIBUTARY NO. 3 19.0
END DESCRIPTION:
XS GIS Cut Line= 3
      3774517.28      10110990.7      3774473.89     10110761.48
      3774363.43     10110514.77
#Sta/Elev= 30
  4766.7  271.32  4786.1  269.42  4791.1  269.88  4796.9  268.85  4827.4  266.05
  4848.6  264.71  4857.9  264.99  4895.8  257.69    4919  256.45  4939.3  256.72
  4958.1  255.85  4969.9  254.19  4990.2  252.57  4995.7  250.77  4995.9  250.27
  4999.4  250.27  5004.2   251.7  5011.4  252.48  5044.3   254.1  5050.6  253.53
  5056.1  254.75  5066.2  255.32  5073.8  254.61  5079.3  255.55  5120.2  255.72
  5142.9  258.37  5148.9  259.97  5161.8  260.98  5177.5  261.15  5270.3  265.53
#Mann= 5 ,-1 , 0
  4766.7     .17       0  4958.1     .15       0  4990.2     .09       0
  5011.4     .15       0  5161.8     .11       0
Bank Sta=4990.2,5011.4
XS Rating Curve= 0 ,0
Exp/Cntr=0.3,0.1

Type RM Length L Ch R = 1 ,8738    ,421,421,421
BEGIN DESCRIPTION:
MOUND CREEK TRIBUTARY NO. 3 18.0
END DESCRIPTION:
XS GIS Cut Line= 3
      3774767.86     10110911.06      3774879.62     10110731.27
      3774996.44     10110518.53
#Sta/Elev= 30
  4788.3  264.83    4843  261.03  4900.4  257.06  4917.8  255.52  4941.4  254.49
  4954.2  252.84  4969.5  252.25  4976.7  251.15  4980.8248.8901  4984.9  246.63
  4988.8  246.05    4989  245.55  4992.5  245.55  4997.2  246.99    5003  246.99
  5006.3     249    5012  248.37  5022.4  249.73  5044.2  249.64  5049.9  250.36
    5066  249.85  5080.1  251.42  5093.5  251.46  5123.7  253.71  5169.3  255.31
    5175  256.08  5191.1  256.11  5207.8  257.35  5212.9  257.08  5242.7  258.76
#Mann= 7 ,-1 , 0
  4788.3     .11       0    4843     .17       0  4900.4     .15       0
  4980.8     .09       0  5006.3     .15       0  5123.7     .17       0
  5207.8     .11       0
Bank Sta=4980.8,5006.3
XS Rating Curve= 0 ,0
Exp/Cntr=0.3,0.1

Type RM Length L Ch R = 1 ,8317    ,258,258,258
BEGIN DESCRIPTION:
MOUND CREEK TRIBUTARY NO. 3 17.0
END DESCRIPTION:
XS GIS Cut Line= 3
      3775117.87     10111261.03      3775202.02     10110994.29
      3775310.23     10110634.61
#Sta/Elev= 30
  4720.3  270.99  4736.4  268.81  4741.7   268.8  4762.2  266.27  4806.4  262.42
  4814.6  260.59  4833.5  258.55  4903.4   254.8  4919.5  252.04    4930  252.14
  4935.8  251.13  4961.4  249.12  4971.2247.6051  4982.4  245.78  4990.9  243.38
  4991.1  242.88  4994.6  242.88  4994.9  243.38  5005.7  244.95  5013.8   247.8
  5045.1  246.95    5066  247.76  5067.8  248.25  5071.8  249.34    5110  251.53
  5118.2   252.5  5128.7  252.04  5169.3  253.37  5264.4  256.32  5375.6  261.17
#Mann= 5 ,-1 , 0
  4720.3     .11       0  4971.2     .07       0  5013.8     .11       0
  5067.8     .15       0  5169.3     .17       0
Bank Sta=4971.2,5013.8
XS Rating Curve= 0 ,0
Exp/Cntr=0.3,0.1

Type RM Length L Ch R = 1 ,8059    ,502,502,502
BEGIN DESCRIPTION:
Mapping XS bfdc0273
END DESCRIPTION:
XS GIS Cut Line= 3
      3775216.93     10111317.14      3775499.43     10110926.21
      3775881.88     10110492.46
#Sta/Elev= 30
  4593.2  269.28  4605.1  268.06  4619.8  269.43  4670.1  264.71  4690.9  260.38
  4705.7  260.52  4748.7  255.35  4806.2   251.1  4927.7  245.97  4984.1  245.84
  4992.7   243.2  4998.8  243.96  5005.6  240.06  5013.5  241.01 5018.61244.0377
  5028.2  248.06  5042.9  247.98  5049.1  245.88  5058.9  246.51  5099.1  242.57
    5156   245.2  5169.1  244.42  5311.2  248.81  5347.6  251.09  5368.5  250.15
  5396.9  252.57  5474.7  251.26  5503.2   253.8  5552.5  252.75  5653.8  256.81
#Mann= 6 ,-1 , 0
  4593.2     .11       0  4998.8     .07       0 5018.61     .15       0
  5058.9     .17       0  5169.1     .15       0  5311.2     .11       0
Bank Sta=4998.8,5018.61
XS Rating Curve= 0 ,0
Exp/Cntr=0.3,0.1

Type RM Length L Ch R = 1 ,7557    ,253,253,253
BEGIN DESCRIPTION:
MOUND CREEK TRIBUTARY NO. 3 16.0
END DESCRIPTION:
XS GIS Cut Line= 5
      3775565.89     10111396.99      3775744.72     10111110.52
       3775902.7     10110902.19      3776185.69     10110674.76
      3776239.79     10110569.35
#Sta/Elev= 30
  4403.9  258.23  4511.3  255.22  4553.7  255.38  4584.4   253.7  4715.3   250.4
  4721.2  251.02  4736.6  249.53  4744.4  250.17  4921.7   243.9  4936.3   241.8
  4942.6  242.75  4950.8   241.7  4957.1  242.45  4971.7  240.84  4986.2  236.64
  4998.9  234.84  5022.4  238.69  5028.9  240.77  5064.1  243.34  5121.6  242.78
  5128.1  243.64    5136  242.81  5185.6  244.88    5200  243.43  5220.9  245.36
  5278.4  244.37  5320.1  245.66  5406.7  245.16  5423.2  247.25  5484.6   249.7
#Mann= 3 , 0 , 0
  4403.9     .11       0  4971.7     .07       0  5028.9     .11       0
Bank Sta=4971.7,5028.9
XS Rating Curve= 0 ,0
Exp/Cntr=0.3,0.1

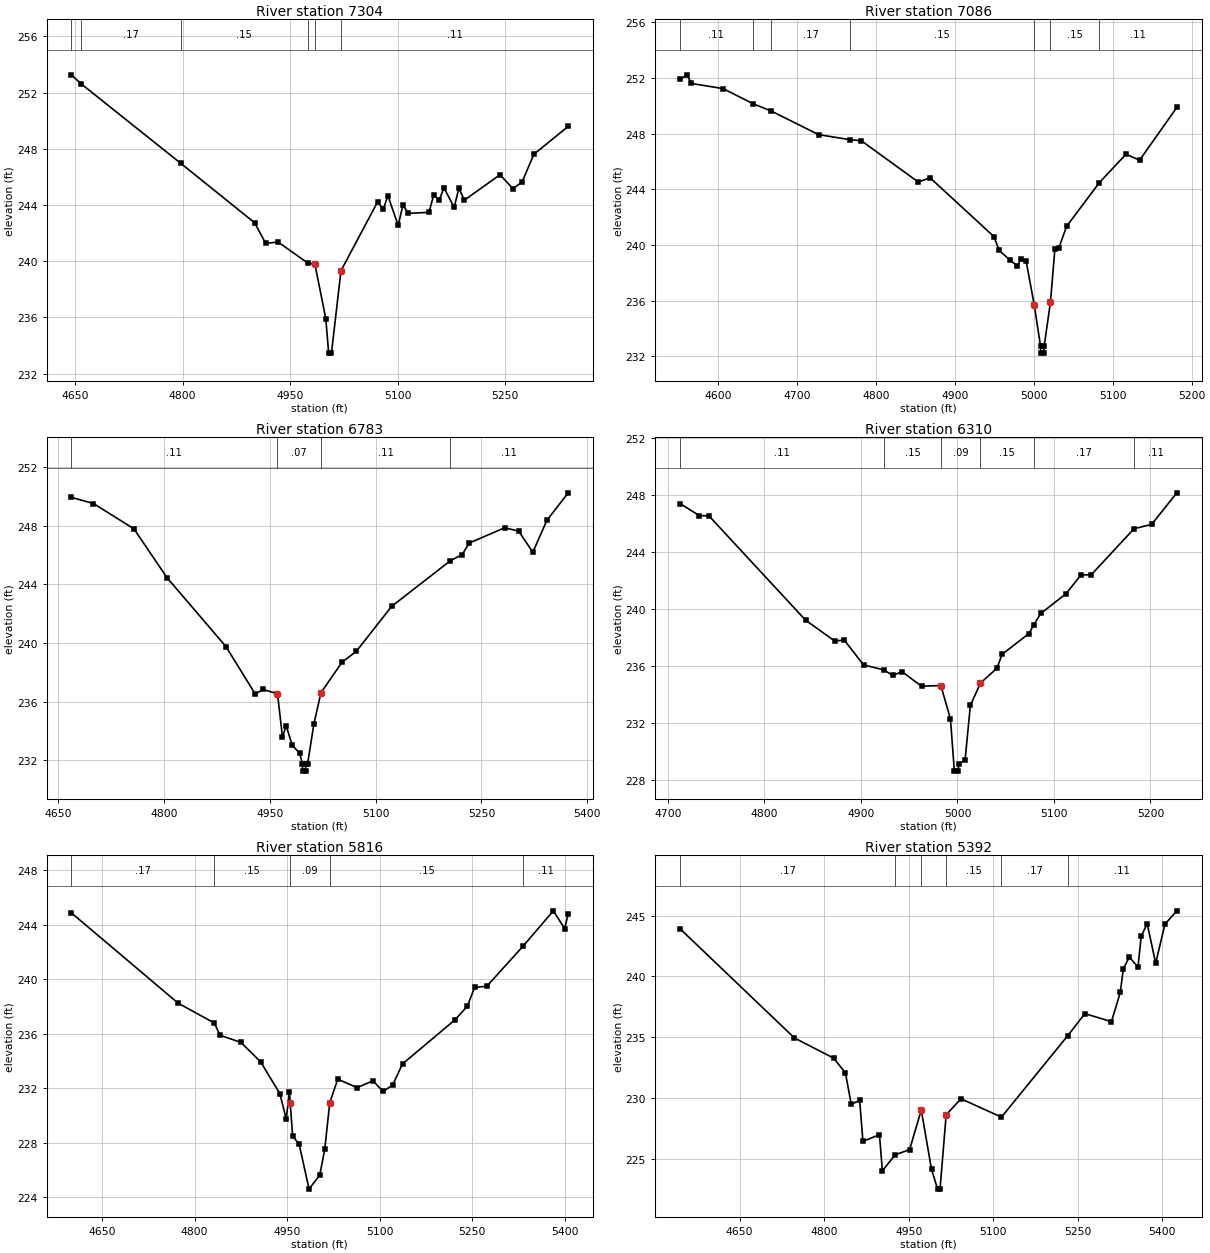
Type RM Length L Ch R = 1 ,7304    ,218,218,218
BEGIN DESCRIPTION:
Mapping XS 159562d5
END DESCRIPTION:
XS GIS Cut Line= 5
      3776173.91     10111176.17      3776158.29     10110905.38
      3776077.56     10110777.78      3776196.05     10110678.82
      3776241.62     10110572.05
#Sta/Elev= 30
    4645  253.27  4658.6  252.63  4797.5  246.97  4900.5  242.74  4915.9  241.27
  4933.2  241.37  4974.3  239.88  4984.5  239.79  4999.7  235.92  5003.7  233.46
  5007.6  233.46  5020.9  239.33    5072  244.23  5079.8  243.69  5086.3  244.67
  5100.6  242.55  5107.2  243.99    5115  243.41  5143.6  243.48  5150.1  244.71
  5157.9  244.36  5164.4  245.23  5178.7  243.83  5185.2  245.19    5193  244.35
  5242.6  246.16  5260.8  245.16  5273.5  245.66  5289.9  247.62  5337.7   249.6
#Mann= 6 ,-1 , 0
    4645     .15       0  4658.6     .17       0  4797.5     .15       0
  4974.3     .11       0  4984.5     .07       0  5020.9     .11       0
Bank Sta=4984.5,5020.9
XS Rating Curve= 0 ,0
Exp/Cntr=0.3,0.1

Type RM Length L Ch R = 1 ,7086    ,303,303,303
BEGIN DESCRIPTION:
MOUND CREEK TRIBUTARY NO. 3 15.0
END DESCRIPTION:
XS GIS Cut Line= 3
      3776354.09     10111185.15      3776298.54      10110782.4
      3776247.85     10110564.99
#Sta/Elev= 30
  4551.4   251.9  4560.5  252.23  4565.6  251.61    4606  251.24  4643.7  250.16
    4667  249.63  4727.1  247.93  4766.8  247.57  4781.3  247.49  4853.3  244.53
  4868.4  244.83  4949.2  240.61  4956.1  239.61  4969.6  238.91  4978.9  238.51
    4984     239  4990.1  238.86  5000.4  235.69  5008.4  232.73  5008.7  232.23
  5012.6  232.23    5013  232.73  5020.9  235.87  5026.6  239.73  5031.7  239.81
  5041.5  241.35  5083.1  244.49  5116.8  246.53  5133.9  246.09  5181.2  249.89
#Mann= 7 ,-1 , 0
  4551.4     .11       0  4643.7     .15       0    4667     .17       0
  4766.8     .15       0  5000.4     .09       0  5020.9     .15       0
  5083.1     .11       0
Bank Sta=5000.4,5020.9
XS Rating Curve= 0 ,0
Exp/Cntr=0.3,0.1

Type RM Length L Ch R = 1 ,6783    ,473,473,473
BEGIN DESCRIPTION:
MOUND CREEK TRIBUTARY NO. 3 14.0
END DESCRIPTION:
XS GIS Cut Line= 3
      3776667.86     10111111.09      3776574.41     10110793.77
      3776567.58     10110420.93
#Sta/Elev= 30
  4669.2  249.95  4700.5  249.53  4757.8   247.8  4804.7  244.46  4888.1  239.76
  4929.7  236.51  4940.3  236.83  4961.1  236.54  4968.2  233.58  4973.4  234.35
    4982  233.02  4992.4  232.48  4996.4  231.75  4996.7  231.25  5000.8  231.25
  5001.2  231.75  5003.8  231.75  5012.7  234.48  5022.7  236.61  5052.7   238.7
  5072.7  239.43  5122.7   242.5  5205.9  245.62  5222.7  246.04  5232.7  246.83
  5282.7  247.87  5302.7  247.65  5322.7   246.2  5342.8  248.39  5372.9  250.26
#Mann= 4 ,-1 , 0
  4669.2     .11       0  4961.1     .07       0  5022.7     .11       0
  5205.9     .11       0
Bank Sta=4961.1,5022.7
XS Rating Curve= 0 ,0
Exp/Cntr=0.3,0.1

Type RM Length L Ch R = 1 ,6310    ,494,494,494
BEGIN DESCRIPTION:
MOUND CREEK TRIBUTARY NO. 3 13.0
END DESCRIPTION:
XS GIS Cut Line= 3
      3776867.85     10110961.08      3776855.08     10110673.87
      3776789.86     10110456.02
#Sta/Elev= 30
  4712.5  247.39  4732.5  246.54  4742.5  246.52  4842.6   239.2  4872.7  237.74
  4882.7   237.8  4902.7  236.06  4924.1   235.7  4932.7  235.32  4942.7  235.58
  4962.8  234.56  4982.8  234.61  4992.8  232.25  4996.8   228.6  5000.9   228.6
  5001.3   229.1  5007.9  229.38  5013.4  233.21  5023.8  234.78    5041  235.83
  5046.3   236.8  5074.1  238.26  5079.2  238.89  5086.4  239.67  5112.4  241.05
  5128.2  242.38  5138.6  242.38    5183  245.62  5201.2  245.92  5227.4  248.14
#Mann= 6 ,-1 , 0
  4712.5     .11       0  4924.1     .15       0  4982.8     .09       0
  5023.8     .15       0  5079.2     .17       0    5183     .11       0
Bank Sta=4982.8,5023.8
XS Rating Curve= 0 ,0
Exp/Cntr=0.3,0.1

Type RM Length L Ch R = 1 ,5816    ,424,424,424
BEGIN DESCRIPTION:
MOUND CREEK TRIBUTARY NO. 3 12.0
END DESCRIPTION:
XS GIS Cut Line= 3
      3777428.75     10111136.58      3777320.25     10110751.58
      3777194.67     10110365.49
#Sta/Elev= 30
    4600  244.86  4773.2  238.24  4831.8  236.79  4841.2  235.89  4875.2  235.36
    4907  233.94  4938.2  231.61  4948.5  229.75  4953.7  231.72 4954.95230.9558
    4959  228.48  4969.4  227.92  4985.6  224.61  5002.9  225.64    5011  227.52
  5019.1 230.938  5032.1  232.67  5063.6  232.05  5089.2  232.55  5105.7  231.77
  5121.2  232.24  5137.2  233.79  5222.3  237.02  5242.4  238.02  5254.2   239.4
  5273.9  239.48  5333.1  242.44  5381.9  245.01  5400.1  243.71    5406  244.77
#Mann= 5 ,-1 , 0
    4600     .17       0  4831.8     .15       0 4954.95     .09       0
  5019.1     .15       0  5333.1     .11       0
Bank Sta=4954.95,5019.1
XS Rating Curve= 0 ,0
Exp/Cntr=0.3,0.1

Type RM Length L Ch R = 1 ,5392    ,521,521,521
BEGIN DESCRIPTION:
MOUND CREEK TRIBUTARY NO. 3 11.0
END DESCRIPTION:
XS GIS Cut Line= 3
      3777501.67     10111094.85      3777616.25     10110660.87
      3777755.14     10110251.12
#Sta/Elev= 30
  4544.4  243.92  4747.4  234.95  4817.2  233.29  4837.9  232.08  4848.2  229.49
  4863.1  229.84  4868.9  226.46  4898.2  227.01  4903.4  224.04  4926.1  225.36
  4951.7  225.78  4972.4  229.04  4990.6  224.16  5001.4  222.54  5005.7  222.54
  5016.6  228.64  5042.8  229.96  5114.7  228.45  5232.3  235.14  5262.7  236.95
  5309.8  236.29  5325.5  238.69  5330.9  240.62  5341.5  241.59  5356.9  240.77
  5362.6  243.29  5373.2  244.34  5388.3  241.09  5404.8   244.3  5425.9  245.39
#Mann= 6 ,-1 , 0
  4544.4     .17       0  4926.1     .15       0  4972.4     .09       0
  5016.6     .15       0  5114.7     .17       0  5232.3     .11       0
Bank Sta=4972.4,5016.6
XS Rating Curve= 0 ,0
Exp/Cntr=0.3,0.1

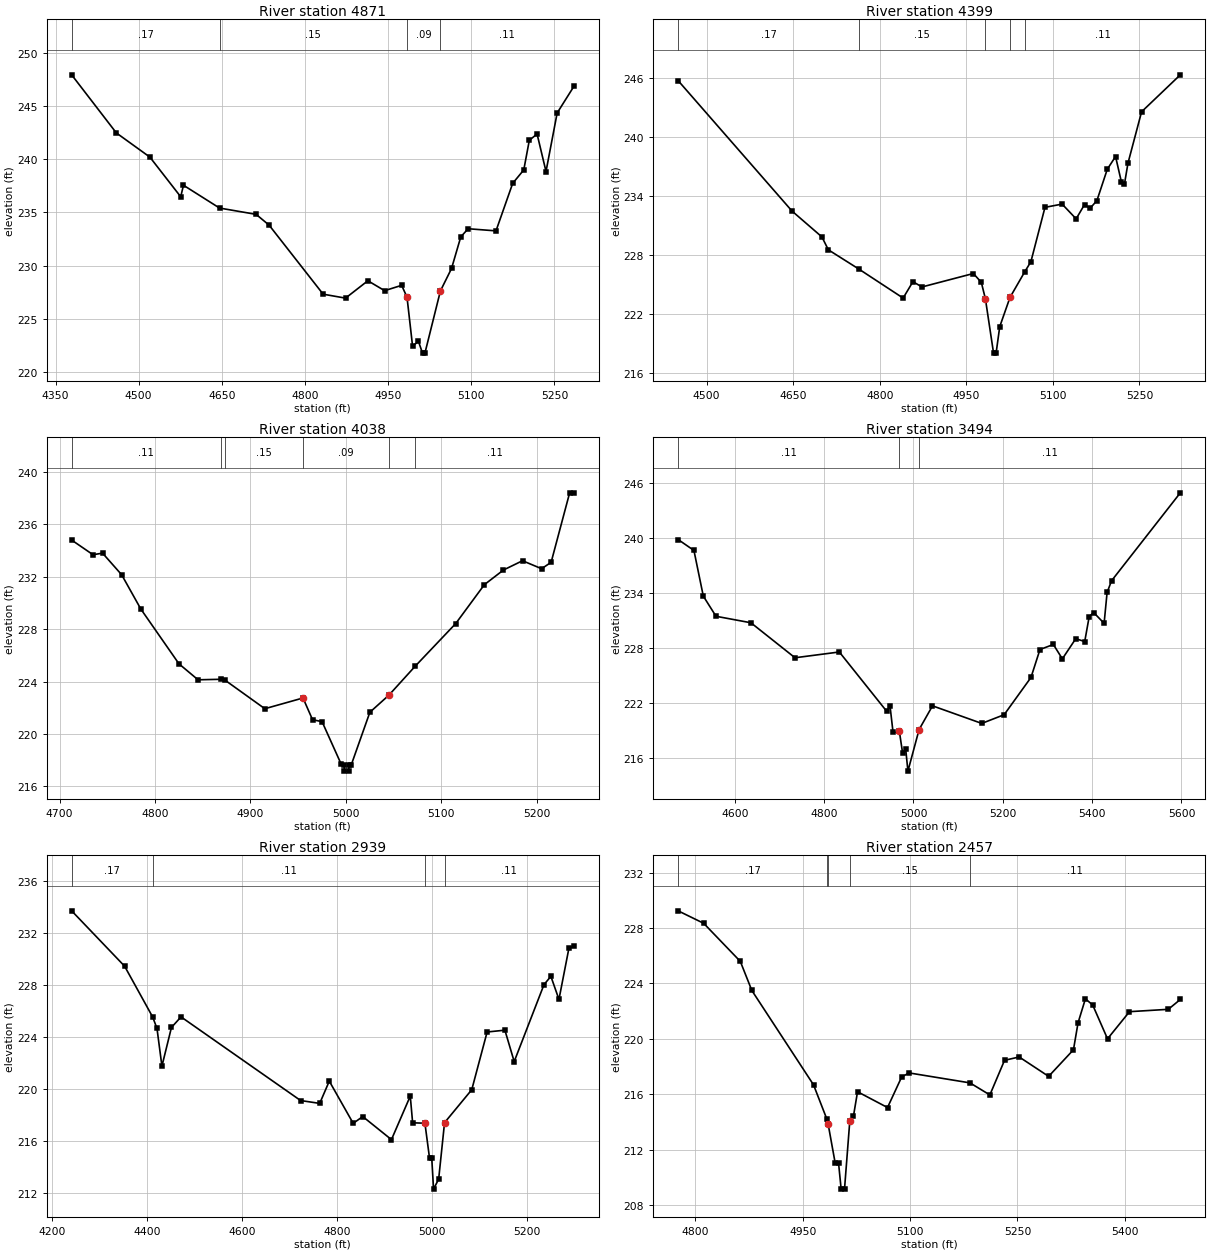
Type RM Length L Ch R = 1 ,4871    ,472,472,472
BEGIN DESCRIPTION:
MOUND CREEK TRIBUTARY NO. 3 10.0
END DESCRIPTION:
XS GIS Cut Line= 3
      3778017.85     10111161.03        3777939.     10110545.16
      3777917.85     10110261.04
#Sta/Elev= 30
  4379.1  247.91  4459.7  242.46  4520.2  240.19  4575.8  236.47  4580.8  237.55
  4645.9  235.41  4711.8  234.82  4735.2  233.81  4832.7  227.33  4873.1  226.96
  4913.4  228.59  4943.6  227.66  4974.3  228.16    4984  227.05    4994  222.46
  5004.6   222.9    5012   221.8  5016.3   221.8  5044.2  227.63  5064.3  229.74
    5081  232.71  5094.3  233.47  5144.5  233.27  5174.6  237.73  5194.6  238.99
  5204.6  241.77  5218.6  242.36  5234.7  238.84  5254.8  244.33  5284.9  246.82
#Mann= 4 ,-1 , 0
  4379.1     .17       0  4645.9     .15       0    4984     .09       0
  5044.2     .11       0
Bank Sta=4984,5044.2
XS Rating Curve= 0 ,0
Exp/Cntr=0.3,0.1

Type RM Length L Ch R = 1 ,4399    ,361,361,361
BEGIN DESCRIPTION:
MOUND CREEK TRIBUTARY NO. 3 9.0
END DESCRIPTION:
XS GIS Cut Line= 3
       3778147.5      10111129.6      3778310.53     10110605.05
      3778428.74     10110306.72
#Sta/Elev= 30
  4450.7  245.74  4648.1  232.47  4699.9  229.84    4711  228.53  4764.2  226.56
  4840.6  223.62  4857.6  225.29  4873.2  224.75  4962.3  226.12  4976.1  225.22
  4983.2  223.53  4997.3  218.02  5001.7  218.02    5008  220.71  5025.8  223.69
  5051.4   226.3    5062  227.32  5086.4  232.85  5116.1  233.18  5140.4  231.68
  5154.9  233.13  5164.7  232.76  5176.4  233.54  5194.4  236.73  5208.7  238.02
  5218.8  235.44  5224.1  235.21  5230.2  237.34  5253.8  242.57  5320.9  246.33
#Mann= 5 ,-1 , 0
  4450.7     .17       0  4764.2     .15       0  4983.2     .09       0
  5025.8     .15       0  5051.4     .11       0
Bank Sta=4983.2,5025.8
XS Rating Curve= 0 ,0
Exp/Cntr=0.3,0.1

Type RM Length L Ch R = 1 ,4038    ,544,544,544
BEGIN DESCRIPTION:
MOUND CREEK TRIBUTARY NO. 3 8.0
END DESCRIPTION:
XS GIS Cut Line= 3
      3778612.88     10111023.49      3778621.56     10110734.87
      3778621.56     10110497.23
#Sta/Elev= 30
  4712.6  234.81    4735  233.69    4745  233.81    4765  232.16  4785.1  229.54
  4825.1  225.35  4845.1  224.13  4869.2  224.17  4873.2  224.11  4915.1  221.92
  4955.1  222.74  4965.1  221.08  4975.1  220.93  4995.2  217.67  4998.1  217.65
  4998.6  217.15    5003  217.15  5003.4  217.65  5005.8  217.65  5025.2  221.65
  5045.2  222.96  5072.6  225.16  5115.2  228.43  5145.2   231.4  5165.2  232.52
  5185.2  233.23  5205.2  232.62  5215.2  233.11  5234.6  238.42    5239  238.42
#Mann= 6 ,-1 , 0
  4712.6     .11       0  4869.2     .17       0  4873.2     .15       0
  4955.1     .09       0  5045.2     .15       0  5072.6     .11       0
Bank Sta=4955.1,5045.2
XS Rating Curve= 0 ,0
Exp/Cntr=0.3,0.1

Type RM Length L Ch R = 1 ,3494    ,555,555,555
BEGIN DESCRIPTION:
MOUND CREEK TRIBUTARY NO. 3 7.0
END DESCRIPTION:
XS GIS Cut Line= 3
      3778667.85     10111311.07      3779024.93     10110923.63
      3779064.16     10110327.52
#Sta/Elev= 30
  4473.1  239.84  4508.5  238.65  4529.5  233.66  4557.9  231.46  4636.1  230.75
  4734.8  226.93    4834  227.56  4940.1  221.08  4947.5  221.67  4954.3  218.78
  4968.4   218.9  4975.8  216.48  4982.6  216.95  4987.6  214.55  5012.6  219.09
  5042.6  221.68  5152.9  219.76    5203  220.71  5263.1  224.78  5283.2  227.83
  5313.2  228.38  5333.3  226.81  5363.3  229.01  5383.4   228.7  5393.4  231.42
  5403.4  231.87  5426.8  230.69  5433.5  234.06  5443.5  235.34  5597.4  244.94
#Mann= 3 ,-1 , 0
  4473.1     .11       0  4968.4     .07       0  5012.6     .11       0
Bank Sta=4968.4,5012.6
XS Rating Curve= 0 ,0
Exp/Cntr=0.3,0.1

Type RM Length L Ch R = 1 ,2939    ,482,482,482
BEGIN DESCRIPTION:
MOUND CREEK TRIBUTARY NO. 3 6.0
END DESCRIPTION:
XS GIS Cut Line= 3
       3779258.6     10111549.78      3779358.23     10110796.84
      3779267.86     10110511.09
#Sta/Elev= 30
  4240.5  233.69  4352.2  229.44  4411.4  225.54  4420.5  224.66  4430.9  221.77
    4451  224.74  4471.2  225.55  4723.4  219.13  4763.7  218.91  4783.9  220.62
  4834.3  217.38  4854.5   217.9    4915  216.13  4954.7  219.47  4959.7  217.42
  4985.6  217.39  4995.3  214.72    5000  214.72  5003.8  212.33  5014.6   213.1
    5027  217.43  5084.4  219.96  5116.8  224.39  5154.3  224.53  5173.9  222.12
  5236.8  228.03  5251.3  228.66  5268.3  226.89  5289.2   230.8  5299.7  230.97
#Mann= 4 ,-1 , 0
  4240.5     .17       0  4411.4     .11       0  4985.6     .06       0
    5027     .11       0
Bank Sta=4985.6,5027
XS Rating Curve= 0 ,0
Exp/Cntr=0.3,0.1

Type RM Length L Ch R = 1 ,2457    ,493,493,493
BEGIN DESCRIPTION:
MOUND CREEK TRIBUTARY NO. 3 5.0
END DESCRIPTION:
XS GIS Cut Line= 3
      3779650.97     10111206.01      3779698.23     10110986.84
      3779807.23     10110521.95
#Sta/Elev= 30
  4775.8  229.24  4811.5  228.34  4862.7  225.59  4878.8  223.49    4965  216.68
  4983.5  214.22  4985.4  213.85  4995.3  211.02    5000  211.02  5003.6  209.15
  5008.3  209.15  5015.7  214.08  5020.8  214.42  5026.5  216.18  5068.4  215.04
  5088.1  217.24  5098.4  217.54  5183.6  216.82  5211.4  215.95  5231.9  218.45
  5252.4  218.69  5293.5  217.29  5328.2  219.21  5334.6  221.15  5344.9  222.89
  5355.1  222.44  5375.8     220  5406.5  221.96  5460.7  222.13  5477.5  222.84
#Mann= 5 ,-1 , 0
  4775.8     .17       0  4983.5     .15       0  4985.4     .09       0
  5015.7     .15       0  5183.6     .11       0
Bank Sta=4985.4,5015.7
XS Rating Curve= 0 ,0
Exp/Cntr=0.3,0.1

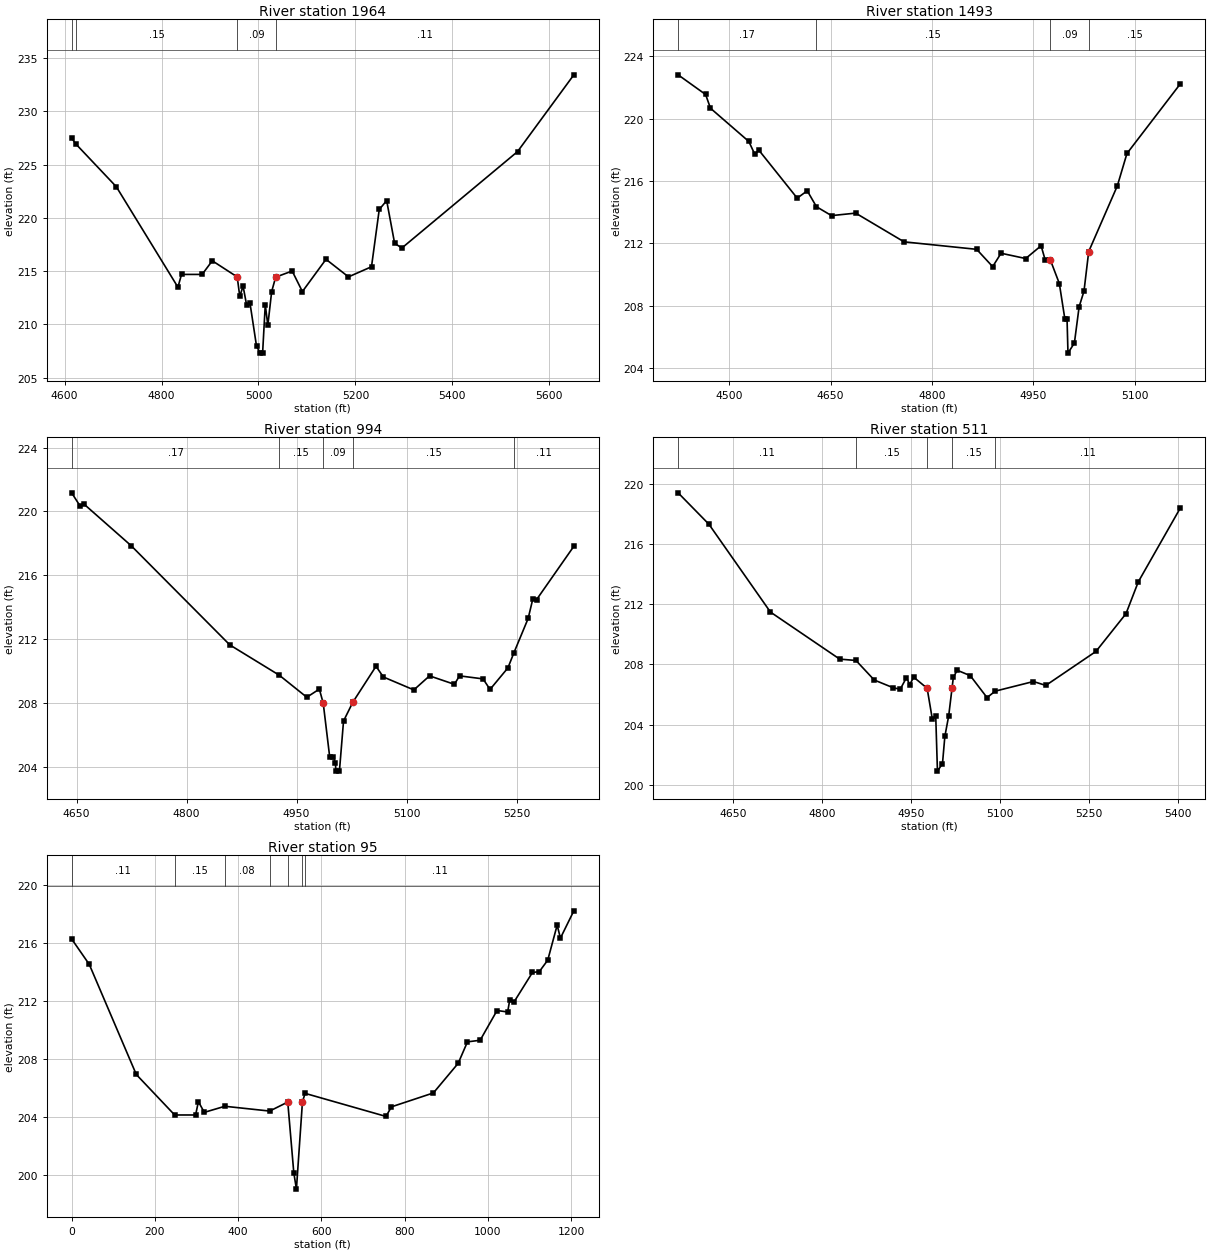
Type RM Length L Ch R = 1 ,1964    ,471,471,471
BEGIN DESCRIPTION:
MOUND CREEK TRIBUTARY NO. 3 4.0
END DESCRIPTION:
XS GIS Cut Line= 3
      3779817.83      10111211.1      3780078.23     10110926.84
      3779867.86     10110311.09
#Sta/Elev= 30
  4614.5   227.5  4623.3  226.94  4706.7  222.93  4833.8   213.5  4841.2   214.7
  4883.7   214.7  4904.7  215.98 4956.14214.4638  4961.4  212.63  4968.2  213.61
  4975.6   211.8  4982.4  212.03    4996  207.95  5003.8  207.31  5008.5  207.31
    5014  211.86  5019.3  209.92  5027.2  213.09 5035.45214.4443  5069.5  215.02
  5090.6  213.09  5139.3  216.12  5185.7  214.47  5233.2  215.42  5249.2   220.8
  5264.5  221.63  5280.9  217.62  5295.9  217.18  5534.5  226.23  5650.7  233.44
#Mann= 4 ,-1 , 0
  4614.5     .17       0  4623.3     .15       0 4956.14     .09       0
 5035.45     .11       0
Bank Sta=4956.14,5035.45
XS Rating Curve= 0 ,0
Exp/Cntr=0.3,0.1

Type RM Length L Ch R = 1 ,1493    ,499,499,499
BEGIN DESCRIPTION:
MOUND CREEK TRIBUTARY NO. 3 3.0
END DESCRIPTION:
XS GIS Cut Line= 3
      3779984.33      10111403.9      3780458.23     10111076.84
      3780578.03      10110959.5
#Sta/Elev= 30
  4424.2   222.8  4464.9  221.54  4472.1  220.66  4528.9  218.53  4537.7  217.71
  4543.8  217.97  4600.5   214.9  4615.4  215.37    4629  214.35  4651.3  213.78
  4687.1  213.94  4758.7   212.1  4866.2  211.62  4889.9  210.51  4902.3  211.37
  4938.8  211.03  4961.6  211.85  4967.7  210.93  4975.2  210.95  4988.6  209.43
  4996.7  207.18    5000  207.18  5001.4  204.97  5010.9  205.62  5017.9  207.94
  5025.1  208.94  5032.1  211.48  5074.5  215.69  5088.7  217.76  5167.7  222.22
#Mann= 4 ,-1 , 0
  4424.2     .17       0    4629     .15       0  4975.2     .09       0
  5032.1     .15       0
Bank Sta=4975.2,5032.1
XS Rating Curve= 0 ,0
Exp/Cntr=0.3,0.1

Type RM Length L Ch R = 1 ,994     ,483,483,483
BEGIN DESCRIPTION:
MOUND CREEK TRIBUTARY NO. 3 2.0
END DESCRIPTION:
XS GIS Cut Line= 3
      3780519.03     10111716.42      3780628.23     10111376.84
      3780717.84     10111061.11
#Sta/Elev= 30
  4643.3  221.17    4655  220.33  4660.2  220.46  4724.4  217.86    4859  211.64
  4926.5  209.74    4964  208.36  4981.1  208.87  4986.4  207.99  4995.2  204.63
    5000  204.63  5003.1  204.23  5003.6  203.73  5008.5  203.73  5014.1  206.87
  5026.8  208.05  5058.4   210.3  5068.4  209.63    5110  208.82  5131.4   209.7
  5165.3  209.17  5172.3   209.7  5204.4  209.51  5213.9  208.85  5238.3   210.2
  5246.5  211.15  5265.9   213.3  5272.2  214.51  5277.4  214.48  5328.2  217.82
#Mann= 5 ,-1 , 0
  4643.3     .17       0  4926.5     .15       0  4986.4     .09       0
  5026.8     .15       0  5246.5     .11       0
Bank Sta=4986.4,5026.8
XS Rating Curve= 0 ,0
Exp/Cntr=0.3,0.1

Type RM Length L Ch R = 1 ,511     ,416,416,416
BEGIN DESCRIPTION:
MOUND CREEK TRIBUTARY NO. 3 1.0
END DESCRIPTION:
XS GIS Cut Line= 3
      3780867.83     10111711.12      3781077.89      10111321.2
      3780817.86     10111011.08
#Sta/Elev= 30
  4557.1  219.41  4609.1  217.32  4712.9  211.48  4829.8  208.35  4857.3  208.26
  4888.1  206.96  4920.5  206.44    4932  206.35  4942.4  207.11  4948.1  206.66
  4954.7  207.15  4977.4  206.41  4986.2  204.35  4991.9  204.57  4994.8   200.9
  5003.3   201.4  5007.3  203.21  5013.8  204.58 5019.36206.3969  5021.6  207.13
  5028.1  207.61  5050.2  207.25  5078.5  205.79  5092.3  206.22  5156.8  206.86
  5177.7   206.6  5262.3  208.86    5313  211.37  5333.8  213.49  5404.7   218.4
#Mann= 5 ,-1 , 0
  4557.1     .11       0  4857.3     .15       0  4977.4     .06       0
 5019.36     .15       0  5092.3     .11       0
Bank Sta=4977.4,5019.36
XS Rating Curve= 0 ,0
Exp/Cntr=0.3,0.1

Type RM Length L Ch R = 1 ,95      ,0,0,0
BEGIN DESCRIPTION:
MOUND CREEK TRIBUTARY NO. 3 1.0
END DESCRIPTION:
XS GIS Cut Line= 4
      3781174.19     10111606.98       3781483.7     10111249.58
      3781360.82     10111090.49      3780836.09     10110998.69
#Sta/Elev= 30
       0  216.26    42.3  214.51   155.3  206.92   247.5  204.13   297.8  204.13
   304.5  205.05   318.7  204.31   368.1  204.73   475.7   204.4   519.2  205.02
   533.7  200.15     540  199.02   554.5  205.04   560.8  205.62   755.2  204.03
   768.2  204.69   869.1  205.65   928.6  207.69   950.9  209.17   981.4  209.28
    1022  211.33  1047.5  211.23  1052.6  212.08  1062.6  211.91    1107  213.95
  1123.5  214.01  1143.8   214.8  1166.4  217.21  1174.3  216.32  1206.5   218.2
#Mann= 7 ,-1 , 0
       0     .11       0   247.5     .15       0   368.1     .08       0
   475.7     .15       0   519.2     .12       0   554.5     .15       0
   560.8     .11       0
Bank Sta=519.2,554.5
XS Rating Curve= 0 ,0
Exp/Cntr=0.3,0.1

Chan Stop Cuts=-1
Use User Specified Reach Order=0
Composite Channel Slope=5