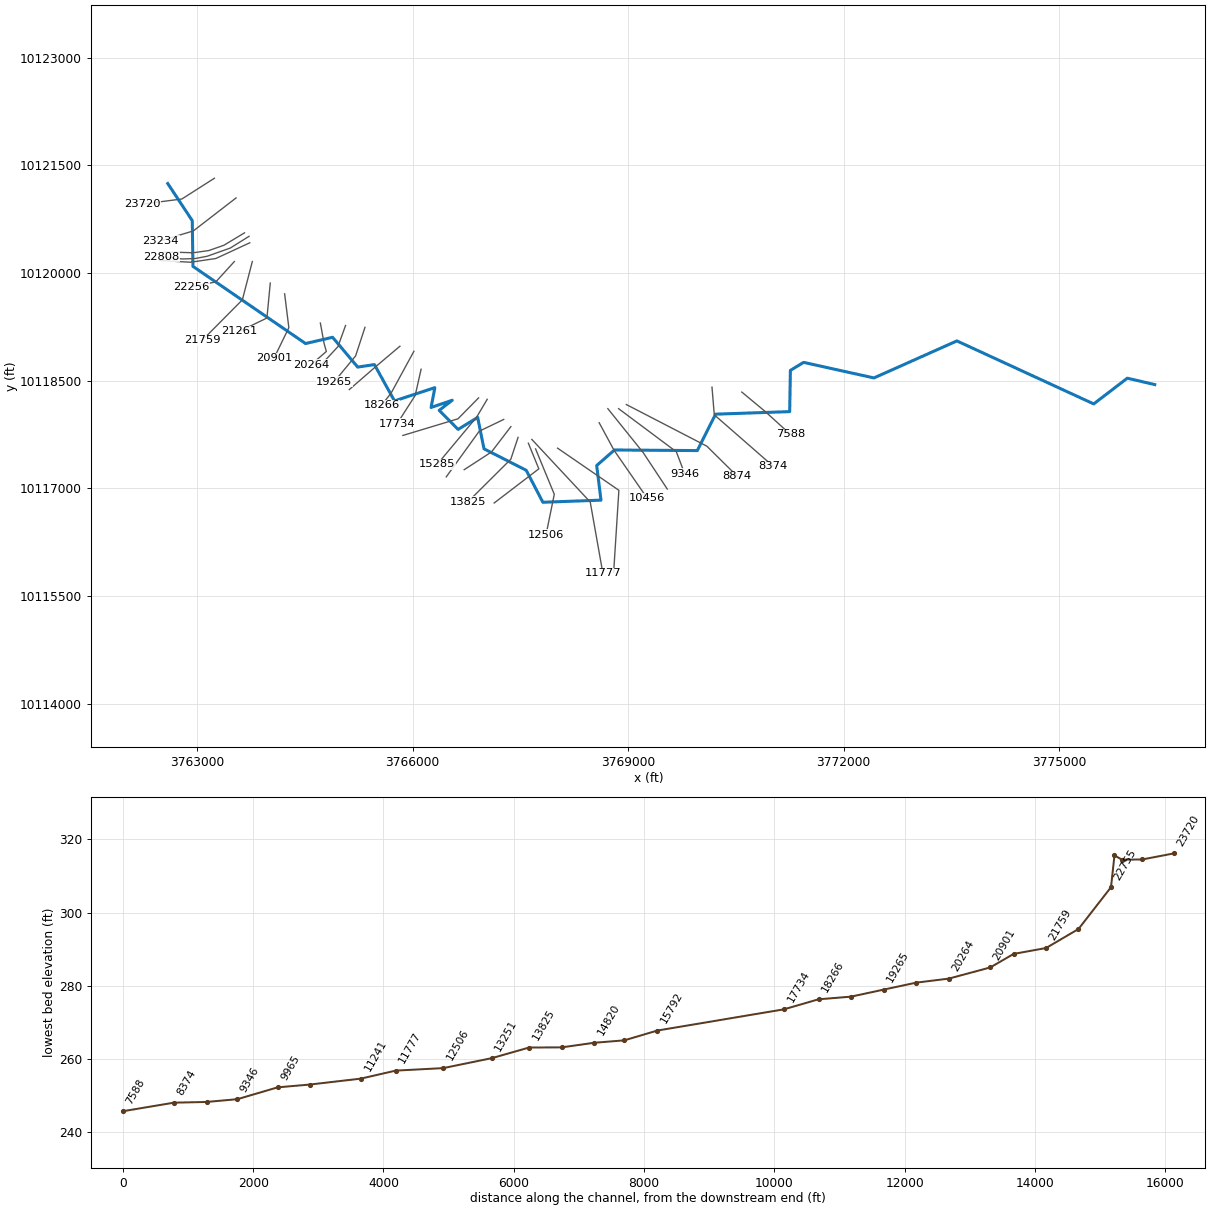
--- MOUND CREEK TRIBUTARY NO 5.prj (project) ---

Proj Title=MOUND CREEK TRIBUTARY NO 5 Base Level Engineering
Current Plan=p01
Default Exp/Contr=0.3,0.1
English Units
Geom File=g01
Flow File=f01
Plan File=p01
Y Axis Title=Elevation
X Axis Title(PF)=Main Channel Distance
X Axis Title(XS)=Station
BEGIN DESCRIPTION:
MOUND CREEK TRIBUTARY NO 5
END DESCRIPTION:
DSS Export Rating Curves= 0
DSS Export Rating Curve Sorted= 0
DSS Export Volume Flow Curves= 0
DXF OffsetX= 0
DXF OffsetY= 0
DXF ScaleX= 1
DXF ScaleY= 10

--- MOUND CREEK TRIBUTARY NO 5.p01 (plan) ---

Plan Title=Multiple Run
Short Identifier=Multiple
Geom File=g01
Flow File=f01
Subcritical Flow
K Sum by GR= 0
Std Step Tol= 0.01
Critical Tol= 0.01
Num of Std Step Trials= 20
Max Error Tol= 0.3
Flow Tol Ratio= 0.001
Split Flow NTrial= 30
Split Flow Tol= 0.02
Split Flow Ratio= 0.02
Log Output Level= 0
Friction Slope Method= 1
Unsteady Friction Slope Method= 2
Unsteady Bridges Friction Slope Method= 1
Parabolic Critical Depth
Global Vel Dist=  1 , 1 , 1
Global Log Level= 0
CheckData=True
Encroach Param= -1, 0, 0, 0
BEGIN DESCRIPTION:
Multiple Run
END DESCRIPTION:

--- MOUND CREEK TRIBUTARY NO 5.f01 (steady flow) ---

Flow Title=Multiple
Program Version=4.10
Number of Profiles= 7
Profile Names=10-year,25-year,50-year,1pct_min,100-year,1pct_plu,500-year
River Rch & RM=MOUND CREEK TRIB,Reach-1         ,23720
     947    1316    1810     818    2471    7462    4764
River Rch & RM=MOUND CREEK TRIB,Reach-1         ,14820
    1126    1560    2140     963    2909    8785    5564
River Rch & RM=MOUND CREEK TRIB,Reach-1         ,8374
    1287    1791    2463    1110    3353   10126    6431
River Rch & RM=MOUND CREEK TRIB,Reach-1         ,2996
    1401    1945    2671    1202    3631   10965    6938
Boundary for River Rch & Prof#=MOUND CREEK TRIB,Reach-1         , 1
Up Type= 0
Dn Type= 3
Dn Slope=0.005
Boundary for River Rch & Prof#=MOUND CREEK TRIB,Reach-1         , 2
Up Type= 0
Dn Type= 3
Dn Slope=0.005
Boundary for River Rch & Prof#=MOUND CREEK TRIB,Reach-1         , 3
Up Type= 0
Dn Type= 3
Dn Slope=0.005
Boundary for River Rch & Prof#=MOUND CREEK TRIB,Reach-1         , 4
Up Type= 0
Dn Type= 3
Dn Slope=0.005
Boundary for River Rch & Prof#=MOUND CREEK TRIB,Reach-1         , 5
Up Type= 0
Dn Type= 3
Dn Slope=0.005
Boundary for River Rch & Prof#=MOUND CREEK TRIB,Reach-1         , 6
Up Type= 0
Dn Type= 3
Dn Slope=0.005
Boundary for River Rch & Prof#=MOUND CREEK TRIB,Reach-1         , 7
Up Type= 0
Dn Type= 3
Dn Slope=0.005
DSS Import GetInterval= 0
DSS Import GetPeak= 0
DSS Import FillOption= 0

--- MOUND CREEK TRIBUTARY NO 5.g01 (geometry) ---

Geom Title=Existing Conditions
Program Version=4.10

River Reach=MOUND CREEK TRIB,Reach-1
Reach XY= 30
      3762590.56     10121247.61      3762931.85      10120730.4
      3762941.09     10120094.13      3764509.05     10119018.68
      3764885.75     10119105.52      3765234.78     10118690.74
       3765468.1     10118724.89      3765747.35     10118219.43
      3766309.31     10118404.18      3766256.78     10118127.61
      3766551.64     10118228.66      3766369.35     10118088.04
      3766633.24     10117822.41      3766905.24     10117989.87
       3766993.4     10117552.15      3767581.52     10117252.43
       3767813.2     10116807.16      3768622.24     10116836.82
      3768562.52     10117319.36      3768809.84     10117535.55
        3769963.     10117527.25      3770218.24     10118034.55
       3771249.8     10118070.02      3771259.34     10118644.45
      3771443.53     10118756.13      3772423.17     10118539.42
      3773577.68     10119055.05      3775482.48     10118177.43
      3775950.64     10118535.75      3776332.72     10118446.73

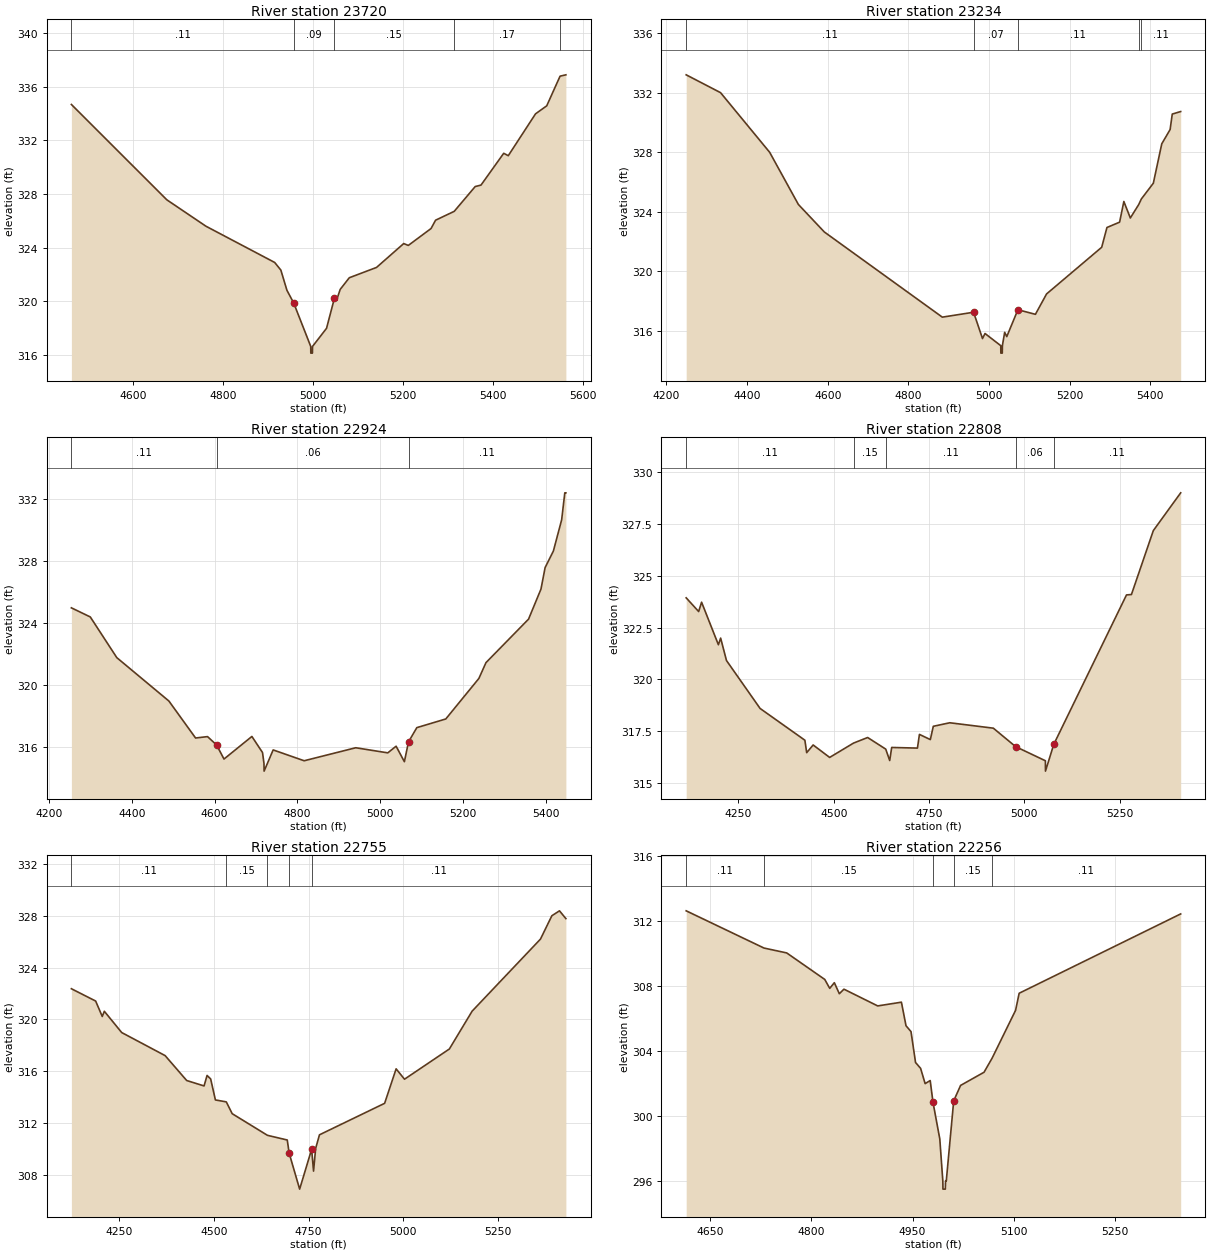
Type RM Length L Ch R = 1 ,23720   ,486,486,486
BEGIN DESCRIPTION:
MOUND CREEK TRIBUTARY NO. 5 38.0
END DESCRIPTION:
XS GIS Cut Line= 3
      3763239.53     10121321.47      3762787.75     10121032.48
      3762230.97     10120960.59
#Sta/Elev= 30
  4463.7  334.67  4675.6  327.56  4762.5  325.59    4915  322.89  4928.7  322.32
  4942.1  320.82  4957.3  319.86    4995  316.63  4995.2  316.13  4998.7  316.13
    4999  316.63  5030.1  317.98  5047.7  320.24  5052.7  320.11  5060.4  320.88
  5080.6  321.75  5141.1  322.52  5201.4   324.3  5211.6  324.16  5262.1  325.42
  5272.1  326.04  5313.5   326.7  5360.1  328.55    5373  328.66  5423.4  331.03
  5433.5  330.85    5494  333.97  5518.9  334.57  5548.5  336.78  5561.4  336.88
#Mann= 5 ,-1 , 0
  4463.7     .11       0  4957.3     .09       0  5047.7     .15       0
  5313.5     .17       0  5548.5     .15       0
Bank Sta=4957.3,5047.7
XS Rating Curve= 0 ,0
Exp/Cntr=0.3,0.1

Type RM Length L Ch R = 1 ,23234   ,310,310,310
BEGIN DESCRIPTION:
MOUND CREEK TRIBUTARY NO. 5 37.0
END DESCRIPTION:
XS GIS Cut Line= 3
      3763541.56     10121047.13      3762947.47     10120588.04
      3762492.99     10120449.93
#Sta/Elev= 30
  4249.2   333.2  4334.4     332  4456.1  327.99  4527.3  324.48  4591.6  322.63
  4884.1   316.9  4961.6  317.23  4983.7  315.46    4990   315.8    5029  314.98
  5029.2  314.48  5032.7  314.48    5033  314.98  5038.7  315.88  5043.9  315.59
  5071.5   317.4  5114.9  317.09  5142.5  318.46  5279.2   321.6  5292.2  322.93
  5323.6  323.29  5334.1  324.68  5350.2  323.57  5371.1  324.48  5377.5  324.85
  5407.2  325.91  5428.1  328.56  5448.8  329.52  5454.1  330.56    5475  330.73
#Mann= 5 ,-1 , 0
  4249.2     .11       0  4961.6     .07       0  5071.5     .11       0
  5371.1     .15       0  5377.5     .11       0
Bank Sta=4961.6,5071.5
XS Rating Curve= 0 ,0
Exp/Cntr=0.3,0.1

Type RM Length L Ch R = 1 ,22924   ,116,116,116
BEGIN DESCRIPTION:
Mapping XS 91eef145
END DESCRIPTION:
XS GIS Cut Line= 6
      3763659.68     10120561.06      3763371.45     10120387.43
      3763163.12     10120314.51      3762947.84     10120283.26
      3762718.68     10120290.21      3762527.69     10120290.21
#Sta/Elev= 30
  4253.9  324.96  4299.6  324.37  4363.7  321.74  4489.5  318.94    4554  316.55
  4582.9  316.64  4604.8   316.1  4622.7  315.19  4690.1  316.65  4715.8  315.61
  4719.3  314.91  4719.6  314.41  4741.5  315.78  4816.4  315.08  4941.1  315.92
  5018.5  315.59  5038.6  316.02  5058.6  315.02  5068.6   316.3  5088.7  317.22
  5158.7  317.78  5238.7   320.4  5255.8  321.42  5358.7  324.23  5388.7  326.17
  5398.7  327.56  5418.7  328.63  5438.7  330.65  5446.3  332.39  5448.9  332.39
#Mann= 3 , 0 , 0
  4253.9     .11       0  4604.8     .06       0  5068.6     .11       0
Bank Sta=4604.8,5068.6
XS Rating Curve= 0 ,0
Exp/Cntr=0.3,0.1

Type RM Length L Ch R = 1 ,22808   ,53,53,53
BEGIN DESCRIPTION:
Mapping XS 19584c8a
END DESCRIPTION:
XS GIS Cut Line= 6
      3763722.12     10120512.41      3763461.73     10120349.24
      3763138.82     10120234.65      3762975.62      10120203.4
      3762798.54     10120196.46       3762496.5      10120227.7
#Sta/Elev= 30
  4112.9  323.93  4145.6  323.27  4153.3  323.72  4197.4  321.67  4203.3  321.99
  4218.6  320.91  4306.8   318.6  4424.3  317.07  4429.1  316.47    4446  316.84
  4489.3  316.24  4551.9  316.93    4589   317.2  4636.5  316.64  4646.9  316.09
  4652.1  316.72  4719.7  316.69  4724.9  317.35  4753.5   317.1  4761.3  317.74
  4804.5  317.91  4918.8  317.65  4977.3  316.76  5055.4  316.08  5055.6  315.58
  5077.4  316.87  5268.2  324.07  5281.2  324.09  5338.6  327.17  5410.4  328.99
#Mann= 5 ,-1 , 0
  4112.9     .11       0  4551.9     .15       0  4636.5     .11       0
  4977.3     .06       0  5077.4     .11       0
Bank Sta=4977.3,5077.4
XS Rating Curve= 0 ,0
Exp/Cntr=0.3,0.1

Type RM Length L Ch R = 1 ,22755   ,499,499,499
BEGIN DESCRIPTION:
MOUND CREEK TRIBUTARY NO. 5 36.0
END DESCRIPTION:
XS GIS Cut Line= 4
      3763732.59     10120422.16      3763260.34      10120203.4
      3762909.16      10120151.2      3762480.95     10120175.52
#Sta/Elev= 30
  4124.5  322.37  4188.5  321.42  4205.9  320.23  4211.4  320.63  4257.2  318.99
  4371.8  317.21  4428.6  315.29  4474.5  314.87  4482.4  315.68  4491.9  315.41
  4504.4  313.79  4533.1  313.64  4548.7  312.73  4641.7  311.06  4693.9   310.7
    4699  309.68  4726.6  306.91  4758.2  309.98  4763.3   308.3  4768.8  310.05
  4778.9   311.1  4950.8  313.53  4981.1  316.19  5003.2  315.39  5121.5  317.72
  5181.6  320.64  5361.9   326.2  5391.9     328    5412  328.38  5428.9  327.78
#Mann= 5 ,-1 , 0
  4124.5     .11       0  4533.1     .15       0  4641.7     .11       0
    4699     .06       0  4758.2     .11       0
Bank Sta=4699,4758.2
XS Rating Curve= 0 ,0
Exp/Cntr=0.3,0.1

Type RM Length L Ch R = 1 ,22256   ,497,497,497
BEGIN DESCRIPTION:
MOUND CREEK TRIBUTARY NO. 5 35.0
END DESCRIPTION:
XS GIS Cut Line= 3
      3763517.86     10120161.09      3763258.64     10119876.43
      3762917.85     10119811.07
#Sta/Elev= 30
    4615  312.62  4730.2  310.33  4763.8  310.03  4820.1   308.4  4827.5  307.85
  4834.3   308.2  4841.7  307.52  4848.5   307.8  4898.5  306.77  4933.6     307
  4940.4  305.55  4947.8  305.19  4954.5  303.29    4962  302.93  4968.7  301.99
  4976.2  302.18 4980.38300.8325  4990.4  298.59  4994.9     296  4995.1   295.5
  4998.6   295.5  4998.9     296    5000     296    5011  300.93  5021.2  301.88
  5055.9  302.69  5067.9  303.56  5102.6   306.5  5107.9  307.55    5347  312.43
#Mann= 5 ,-1 , 0
    4615     .11       0  4730.2     .15       0 4980.38     .09       0
    5011     .15       0  5067.9     .11       0
Bank Sta=4980.38,5011
XS Rating Curve= 0 ,0
Exp/Cntr=0.3,0.1

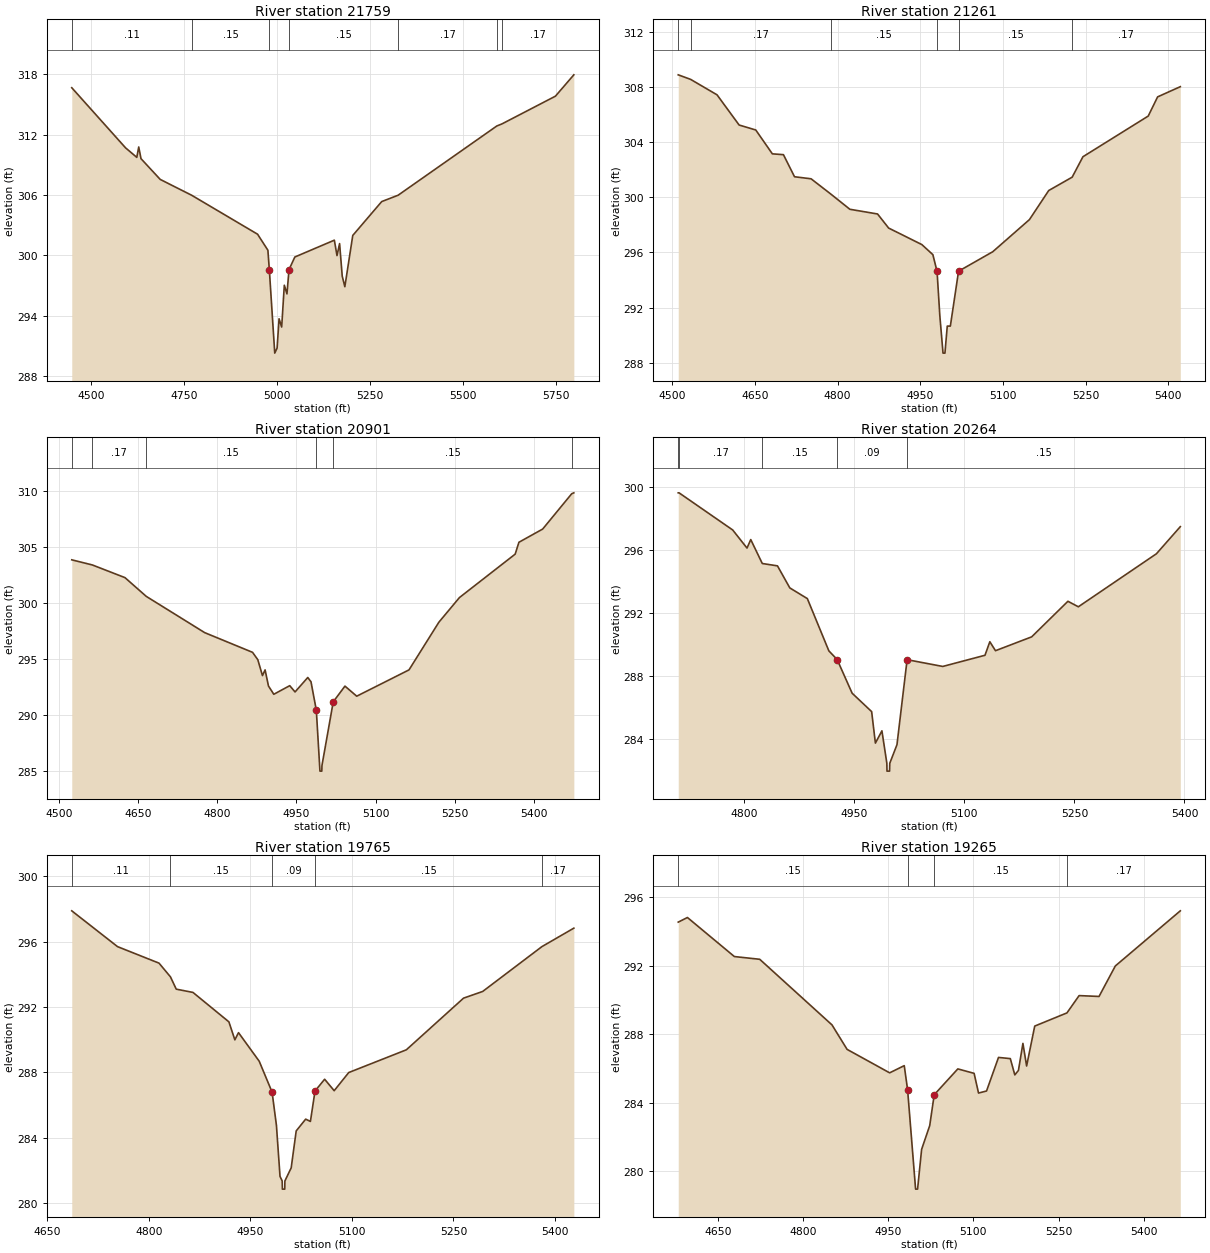
Type RM Length L Ch R = 1 ,21759   ,498,498,498
BEGIN DESCRIPTION:
MOUND CREEK TRIBUTARY NO. 5 34.0
END DESCRIPTION:
XS GIS Cut Line= 3
      3763767.85     10120161.07       3763629.2     10119627.18
      3763067.88      10119061.1
#Sta/Elev= 30
  4448.4  316.65    4593  310.68  4623.1  309.74  4628.3  310.77  4634.4  309.61
    4686  307.55  4770.4  305.98  4947.6  302.11  4975.3  300.52 4979.22298.5507
  4993.7  290.31    5000  290.81  5005.3  293.72  5012.3   292.9  5019.4  297.05
  5026.5  296.19 5032.02298.6001  5047.7  299.85  5153.8  301.52  5160.9  299.99
  5167.9  301.18    5175  297.95    5182   296.9  5203.3  301.99    5281  305.35
  5325.1  305.98  5590.2  312.85  5604.7  313.07  5747.7  315.81  5797.2  317.93
#Mann= 7 ,-1 , 0
  4448.4     .11       0  4770.4     .15       0 4979.22     .09       0
 5032.02     .15       0  5325.1     .17       0  5590.2     .11       0
  5604.7     .17       0
Bank Sta=4979.22,5032.02
XS Rating Curve= 0 ,0
Exp/Cntr=0.3,0.1

Type RM Length L Ch R = 1 ,21261   ,360,360,360
BEGIN DESCRIPTION:
MOUND CREEK TRIBUTARY NO. 5 33.0
END DESCRIPTION:
XS GIS Cut Line= 3
      3764017.86     10119861.11      3763971.23     10119374.24
      3763591.51     10119190.15
#Sta/Elev= 30
  4510.9  308.88  4533.4  308.55  4581.3  307.43  4621.4  305.24  4651.6  304.88
  4681.7  303.15  4701.8  303.09  4721.9  301.49    4752  301.34  4787.6  300.24
  4822.4  299.13  4872.6  298.79  4892.7  297.77    4953  296.57    4973  295.84
  4980.6  294.62  4985.6  291.42  4991.4   288.7  4994.9   288.7  4999.1  290.66
  5004.7  290.66  5019.6  294.64  5081.6  296.05  5148.2  298.38  5183.2  300.49
  5225.8  301.46  5245.3  302.94  5363.8  305.89  5380.8  307.28    5422  308.02
#Mann= 6 ,-1 , 0
  4510.9     .11       0  4533.4     .17       0  4787.6     .15       0
  4980.6     .09       0  5019.6     .15       0  5225.8     .17       0
Bank Sta=4980.6,5019.6
XS Rating Curve= 0 ,0
Exp/Cntr=0.3,0.1

Type RM Length L Ch R = 1 ,20901   ,637,637,637
BEGIN DESCRIPTION:
MOUND CREEK TRIBUTARY NO. 5 32.0
END DESCRIPTION:
XS GIS Cut Line= 3
      3764217.85     10119711.12      3764276.49     10119238.84
      3764067.87     10118811.11
#Sta/Elev= 30
  4524.1  303.89  4563.2  303.43  4624.9   302.3  4665.4  300.62  4776.1  297.38
  4866.8  295.62  4876.8  294.96  4885.6  293.54  4890.6  294.05    4897  292.61
  4907.1  291.87  4937.3  292.64  4947.4  292.08  4971.5  293.37  4977.6  292.99
  4987.7  290.45  4994.6     285  4998.1     285  4998.4   285.5  5019.8   291.2
    5042   292.6  5064.3   291.7  5163.4  294.05    5220  298.31  5259.1  300.52
  5364.7   304.4  5371.8  305.46  5416.8  306.64  5471.9   309.8  5475.9  309.88
#Mann= 6 ,-1 , 0
  4524.1     .15       0  4563.2     .17       0  4665.4     .15       0
  4987.7     .09       0  5019.8     .15       0  5471.9     .17       0
Bank Sta=4987.7,5019.8
XS Rating Curve= 0 ,0
Exp/Cntr=0.3,0.1

Type RM Length L Ch R = 1 ,20264   ,499,499,499
BEGIN DESCRIPTION:
MOUND CREEK TRIBUTARY NO. 5 31.0
END DESCRIPTION:
XS GIS Cut Line= 4
      3764715.21     10119304.08      3764767.35     10119019.11
      3764798.54     10118908.26      3764587.81     10118725.18
#Sta/Elev= 30
  4710.3  299.63  4711.4  299.63  4784.5  297.27    4804  296.12  4809.1  296.66
  4824.8  295.14  4845.5  294.99  4862.3  293.59  4886.2  292.91  4915.5  289.59
  4926.8  289.04  4947.2   286.9  4973.8  285.73  4978.9  283.73  4987.8  284.51
  4994.5  282.45  4994.7  281.95  4998.2  281.95  4998.5  282.45  5008.3  283.63
  5022.1  289.03  5070.7   288.6  5128.2  289.31  5134.8  290.17  5142.5   289.6
  5191.8  290.48  5241.2  292.74  5255.4  292.39  5361.8  295.76  5394.3  297.48
#Mann= 5 ,-1 , 0
  4710.3     .11       0  4711.4     .17       0  4824.8     .15       0
  4926.8     .09       0  5022.1     .15       0
Bank Sta=4926.8,5022.1
XS Rating Curve= 0 ,0
Exp/Cntr=0.3,0.1

Type RM Length L Ch R = 1 ,19765   ,500,500,500
BEGIN DESCRIPTION:
MOUND CREEK TRIBUTARY NO. 5 30.0
END DESCRIPTION:
XS GIS Cut Line= 3
      3765065.91      10119269.4      3764959.27     10118974.28
      3764667.86     10118661.08
#Sta/Elev= 30
  4686.2  297.88  4753.8  295.69  4815.1  294.68    4832  293.84  4840.5  293.09
  4865.2  292.89  4918.3  291.09  4927.1  289.99  4932.5  290.43  4963.1  288.68
  4982.1  286.79  4988.5  284.76  4993.8  281.64    4997  281.36  4997.3  280.86
  5000.8  280.86    5001  281.36  5010.3  282.16  5017.7  284.42  5031.7  285.14
  5038.7     285  5045.5  286.86  5059.7  287.58  5073.8  286.88  5095.3  287.99
  5180.4  289.38  5264.9  292.54  5293.2  292.95  5380.6  295.69  5427.8  296.82
#Mann= 5 ,-1 , 0
  4686.2     .11       0    4832     .15       0  4982.1     .09       0
  5045.5     .15       0  5380.6     .17       0
Bank Sta=4982.1,5045.5
XS Rating Curve= 0 ,0
Exp/Cntr=0.3,0.1

Type RM Length L Ch R = 1 ,19265   ,499,499,499
BEGIN DESCRIPTION:
MOUND CREEK TRIBUTARY NO. 5 29.0
END DESCRIPTION:
XS GIS Cut Line= 3
      3765336.73     10119245.08      3765205.89     10118845.98
      3764909.62      10118488.1
#Sta/Elev= 30
    4580  294.54  4596.2  294.81  4678.9  292.53  4723.6  292.37  4850.9  288.54
  4877.5  287.11  4952.5  285.74  4978.2  286.16  4984.1  284.76  4998.2  278.95
  5001.7  278.95  5008.8  281.27  5023.1  282.66    5031  284.46  5072.6  285.97
  5101.3  285.71  5109.1  284.56  5123.2  284.68  5144.3  286.64  5165.1  286.57
    5173  285.62  5179.4  285.88  5187.3  287.46  5193.8  286.14  5208.1  288.47
  5264.9  289.24  5286.3  290.25  5321.4   290.2  5350.1  291.98  5464.6   295.2
#Mann= 4 ,-1 , 0
    4580     .15       0  4984.1     .09       0    5031     .15       0
  5264.9     .17       0
Bank Sta=4984.1,5031
XS Rating Curve= 0 ,0
Exp/Cntr=0.3,0.1

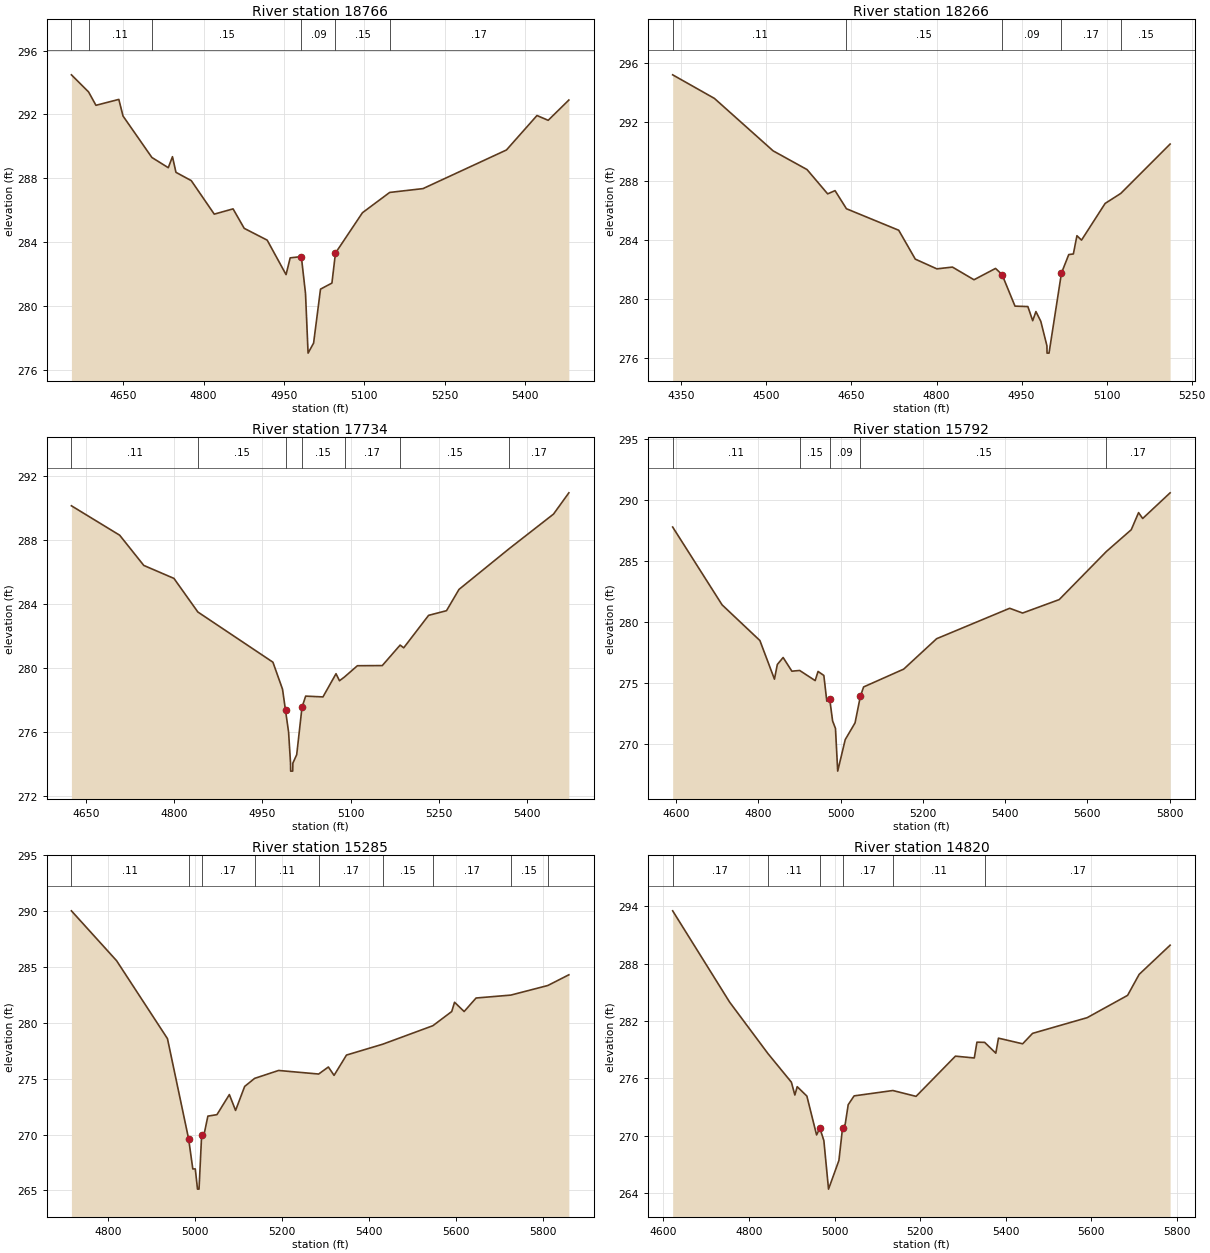
Type RM Length L Ch R = 1 ,18766   ,500,500,500
BEGIN DESCRIPTION:
MOUND CREEK TRIBUTARY NO. 5 28.0
END DESCRIPTION:
XS GIS Cut Line= 3
      3765822.84     10118981.18      3765481.52     10118692.86
      3765117.97       10118377.
#Sta/Elev= 30
  4553.2  294.48  4585.2  293.41    4599  292.57  4641.7  292.94  4649.5   291.9
  4703.4   289.3    4734  288.66  4741.8  289.35  4748.3  288.37  4776.9  287.85
  4819.8  285.75  4854.9  286.08  4875.7  284.86  4918.6  284.12  4953.8  281.96
  4961.5  283.01  4982.3  283.09  4990.1  280.78  4994.9  277.04  5005.2  277.67
  5018.1  281.05  5039.4  281.43    5046  283.31  5096.4  285.84  5147.2  287.11
  5209.4  287.35  5365.1  289.77  5422.1  291.93    5443  291.63  5481.6   292.9
#Mann= 6 ,-1 , 0
  4553.2     .15       0  4585.2     .11       0  4703.4     .15       0
  4982.3     .09       0    5046     .15       0  5147.2     .17       0
Bank Sta=4982.3,5046
XS Rating Curve= 0 ,0
Exp/Cntr=0.3,0.1

Type RM Length L Ch R = 1 ,18266   ,532,532,532
BEGIN DESCRIPTION:
MOUND CREEK TRIBUTARY NO. 5 27.0
END DESCRIPTION:
XS GIS Cut Line= 3
      3766017.86     10118911.09      3765699.66     10118326.93
      3765567.83     10118161.04
#Sta/Elev= 30
  4334.8   295.2  4408.4   293.6  4511.9  290.04  4571.7  288.77  4608.1  287.12
  4621.1  287.34  4641.2  286.11  4733.4  284.65  4762.6  282.69  4800.6  282.03
  4828.1  282.15  4866.1  281.29  4904.1  282.06  4915.6  281.64  4938.4   279.5
  4961.1  279.47  4969.6  278.51  4975.3  279.13  4983.9  278.47  4994.7  276.81
  4994.9  276.31  4998.4  276.31  5020.3  281.74  5033.2     283  5041.3  283.04
  5047.6  284.28  5055.7  283.98  5097.3  286.47  5124.9  287.15  5211.9   290.5
#Mann= 5 ,-1 , 0
  4334.8     .11       0  4641.2     .15       0  4915.6     .09       0
  5020.3     .17       0  5124.9     .15       0
Bank Sta=4915.6,5020.3
XS Rating Curve= 0 ,0
Exp/Cntr=0.3,0.1

Type RM Length L Ch R = 1 ,17734   ,1942,1942,1942
BEGIN DESCRIPTION:
MOUND CREEK TRIBUTARY NO. 5 26.0
END DESCRIPTION:
XS GIS Cut Line= 3
      3766117.84     10118661.04      3766035.61     10118295.68
        3765782.     10117899.14
#Sta/Elev= 30
  4625.5  290.16  4707.5  288.32  4748.5  286.43  4799.7  285.62  4840.3  283.52
  4967.9  280.38  4984.2  278.69 4989.26277.3735  4994.5  276.01  4997.8  274.07
    4998  273.57  5001.5  273.57  5001.8  274.07  5008.3   274.6  5017.3  277.56
  5023.5  278.26  5052.9  278.21  5075.1  279.66    5081  279.22  5089.6  279.46
  5111.4  280.16  5153.7  280.17    5184  281.45  5190.1  281.28  5232.4  283.31
  5262.8   283.6    5284  284.93    5369  287.47  5444.6  289.64  5470.7  290.97
#Mann= 7 ,-1 , 0
  4625.5     .11       0  4840.3     .15       0 4989.26     .09       0
  5017.3     .15       0  5089.6     .17       0    5184     .15       0
    5369     .17       0
Bank Sta=4989.26,5017.3
XS Rating Curve= 0 ,0
Exp/Cntr=0.3,0.1

Type RM Length L Ch R = 1 ,15792   ,507,507,507
BEGIN DESCRIPTION:
MOUND CREEK TRIBUTARY NO. 5 25.0
END DESCRIPTION:
XS GIS Cut Line= 3
      3766917.83     10118261.05       3766631.5     10117969.98
      3765864.48     10117738.12
#Sta/Elev= 30
  4591.7  287.76  4711.9  281.39  4803.8  278.47  4839.2  275.31  4846.2  276.51
  4860.3  277.08  4881.6  275.96  4900.5  276.02  4938.2  275.19  4945.2  275.94
  4959.3  275.61  4966.5  273.51  4973.5   273.7  4980.6  271.89  4987.6  271.27
    4993  267.78  5011.3  270.36  5035.2  271.73 5048.11273.9003    5056  274.67
  5153.5  276.13  5233.6  278.62  5411.2  281.11  5442.6  280.72  5531.6  281.82
  5646.4  285.76  5706.8  287.54  5724.6  288.94  5734.6  288.46  5801.3  290.56
#Mann= 5 ,-1 , 0
  4591.7     .11       0  4900.5     .15       0  4973.5     .09       0
 5048.11     .15       0  5646.4     .17       0
Bank Sta=4973.5,5048.11
XS Rating Curve= 0 ,0
Exp/Cntr=0.3,0.1

Type RM Length L Ch R = 1 ,15285   ,465,465,465
BEGIN DESCRIPTION:
MOUND CREEK TRIBUTARY NO. 5 24.0
END DESCRIPTION:
XS GIS Cut Line= 3
      3767038.15     10118241.64      3766893.05     10117996.34
      3766342.82     10117336.04
#Sta/Elev= 30
    4715  290.04    4819  285.57    4936  278.59  4984.7  269.61  4994.3  266.92
    5000  266.92  5005.1  265.11  5008.6  265.11  5014.6  269.93  5021.2   270.2
    5029  271.65  5049.8  271.78  5078.4  273.58  5092.7  272.16  5113.6  274.31
  5136.5  275.03  5191.7  275.74  5283.8  275.42  5306.2  276.05  5319.3   275.3
  5347.9  277.12  5431.1  278.09  5546.7  279.75    5590  281.02  5596.5  281.85
  5618.6  281.02    5646  282.23  5725.8  282.49  5811.1  283.35  5859.5  284.31
#Mann= 9 ,-1 , 0
    4715     .11       0  4984.7     .07       0  5014.6     .17       0
  5136.5     .11       0  5283.8     .17       0  5431.1     .15       0
  5546.7     .17       0  5725.8     .15       0  5811.1     .17       0
Bank Sta=4984.7,5014.6
XS Rating Curve= 0 ,0
Exp/Cntr=0.3,0.1

Type RM Length L Ch R = 1 ,14820   ,497,497,497
BEGIN DESCRIPTION:
MOUND CREEK TRIBUTARY NO. 5 23.0
END DESCRIPTION:
XS GIS Cut Line= 3
      3767267.87     10117961.08      3766926.85     10117796.85
      3766467.82     10117161.03
#Sta/Elev= 30
  4621.5  293.51  4754.7  283.97  4844.2   278.6    4899  275.61  4907.1  274.27
  4912.6  275.14  4935.2  274.16  4957.9   270.1  4965.6  270.81  4974.9  269.51
  4985.8  264.44  5010.1  267.44  5018.6  270.84  5024.8  271.23  5031.8  273.26
  5045.6  274.18  5136.2  274.74  5190.4  274.13  5282.4  278.33  5326.5  278.14
  5332.7  279.79  5350.7  279.77  5376.8  278.64    5383  280.21  5439.5  279.62
  5462.7  280.71  5590.3  282.35  5684.8  284.68  5711.8  286.87  5784.2  289.92
#Mann= 6 ,-1 , 0
  4621.5     .17       0  4844.2     .11       0  4965.6     .07       0
  5018.6     .17       0  5136.2     .11       0  5350.7     .17       0
Bank Sta=4965.6,5018.6
XS Rating Curve= 0 ,0
Exp/Cntr=0.3,0.1

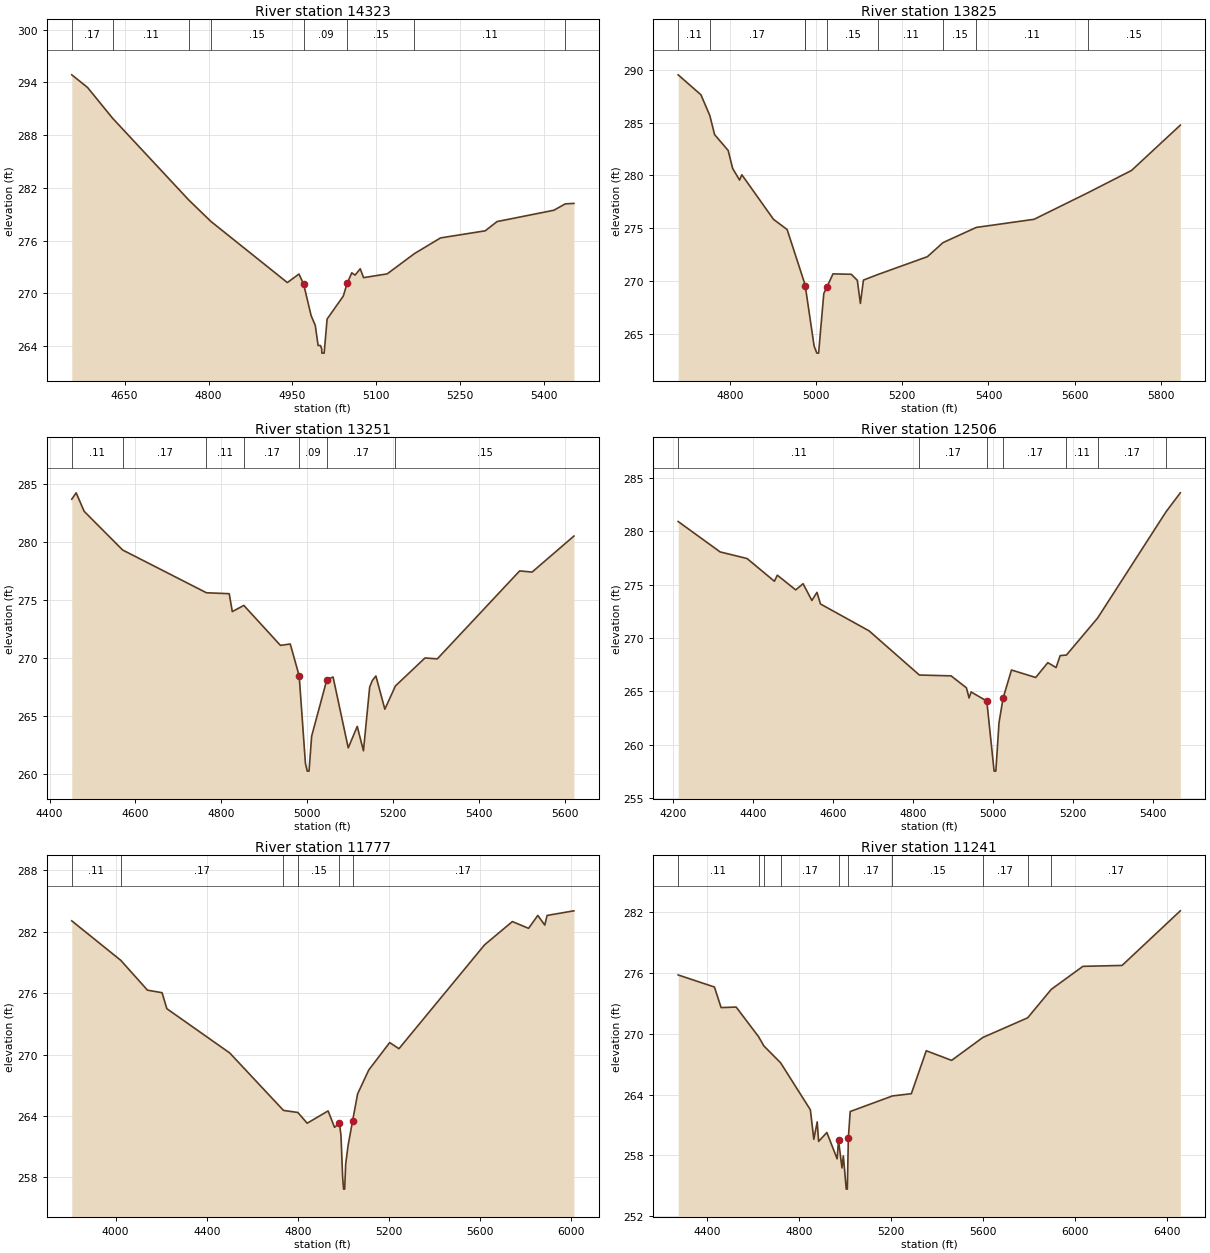
Type RM Length L Ch R = 1 ,14323   ,498,498,498
BEGIN DESCRIPTION:
MOUND CREEK TRIBUTARY NO. 5 22.0
END DESCRIPTION:
XS GIS Cut Line= 3
      3767367.83     10117861.05       3767097.9      10117507.9
      3766717.82     10117261.05
#Sta/Elev= 30
  4555.5  294.86  4583.6  293.43  4628.5  289.92  4764.6  280.62  4804.4  278.17
  4940.9  271.22  4961.7  272.19    4970  271.05  4983.4  267.46  4990.8  266.35
  4995.9  264.06    5000  264.06  5002.3  263.69  5002.6  263.19  5006.7  263.19
    5012  267.07  5040.9  269.68  5047.8  271.14  5056.1  272.33    5062  272.07
  5071.2  272.79  5077.2  271.78  5119.4  272.21    5168  274.51  5214.7   276.3
  5294.7  277.11  5315.8  278.16  5417.4  279.45  5437.6  280.17  5453.2  280.23
#Mann= 8 ,-1 , 0
  4555.5     .17       0  4628.5     .11       0  4764.6     .17       0
  4804.4     .15       0    4970     .09       0  5047.8     .15       0
    5168     .11       0  5437.6     .17       0
Bank Sta=4970,5047.8
XS Rating Curve= 0 ,0
Exp/Cntr=0.3,0.1

Type RM Length L Ch R = 1 ,13825   ,574,574,574
BEGIN DESCRIPTION:
MOUND CREEK TRIBUTARY NO. 5 21.0
END DESCRIPTION:
XS GIS Cut Line= 3
      3767467.85     10117711.06      3767367.01     10117407.15
      3766767.82     10116811.04
#Sta/Elev= 30
  4679.8  289.52  4732.6  287.63  4753.2  285.67  4764.3  283.86  4795.9  282.35
  4806.2  280.65  4822.3  279.55  4827.6  280.05    4901  275.83  4932.7  274.86
  4973.8   269.7  4974.8  269.51  4995.3  263.82  5001.6  263.15  5005.7  263.15
  5017.8  268.81  5024.9   269.4  5039.1  270.66  5081.5  270.62  5095.6  270.05
  5102.7  267.86  5109.8  270.07    5144  270.61  5258.3  272.29  5294.4  273.62
  5371.6  275.06  5505.8  275.83  5630.9  278.35    5732  280.46  5845.2  284.75
#Mann= 9 ,-1 , 0
  4679.8     .11       0  4753.2     .17       0  4973.8     .15       0
  4974.8     .09       0  5024.9     .15       0    5144     .11       0
  5294.4     .15       0  5371.6     .11       0  5630.9     .15       0
Bank Sta=4974.8,5024.9
XS Rating Curve= 0 ,0
Exp/Cntr=0.3,0.1

Type RM Length L Ch R = 1 ,13251   ,745,745,745
BEGIN DESCRIPTION:
MOUND CREEK TRIBUTARY NO. 5 20.0
END DESCRIPTION:
XS GIS Cut Line= 3
      3767611.05     10117630.47      3767756.87     10117272.85
      3767135.33     10116797.14
#Sta/Elev= 30
  4451.7  283.65  4461.9   284.2  4480.5  282.61  4570.1  279.28  4765.2   275.6
  4818.2  275.52  4825.4  273.98  4852.3  274.51  4937.5  271.07  4960.3  271.19
  4981.1  268.45  4995.6  260.92  4999.9  260.25    5004  260.25  5010.1  263.26
  5045.5  268.12    5060  268.35  5095.3  262.25  5116.2   264.1  5130.7     262
  5145.2  267.49  5151.5  268.05  5159.7  268.44  5180.5  265.58  5205.1  267.58
    5274  269.99  5302.6  269.91  5494.3  277.48  5523.3  277.38  5620.6  280.48
#Mann= 7 ,-1 , 0
  4451.7     .11       0  4570.1     .17       0  4765.2     .11       0
  4852.3     .17       0  4981.1     .09       0  5045.5     .17       0
  5205.1     .15       0
Bank Sta=4981.1,5045.5
XS Rating Curve= 0 ,0
Exp/Cntr=0.3,0.1

Type RM Length L Ch R = 1 ,12506   ,729,729,729
BEGIN DESCRIPTION:
MOUND CREEK TRIBUTARY NO. 5 19.0
END DESCRIPTION:
XS GIS Cut Line= 3
      3767711.74     10117550.61      3767972.15     10116918.68
      3767857.57     10116356.22
#Sta/Elev= 30
  4211.9  280.93    4317  278.08  4384.5  277.46  4452.9  275.33  4460.2   275.9
  4506.2  274.52  4524.7   275.1  4546.7  273.53  4559.5  274.29  4568.3   273.2
    4690  270.68  4815.9  266.54  4895.4  266.46  4933.8  265.34  4940.4  264.39
  4945.5  264.95  4984.8   264.1  5003.1  257.53  5007.4  257.53  5015.4  262.08
  5025.6  264.37  5046.6  267.01  5107.3  266.31  5137.6   267.7  5158.3  267.24
  5168.5  268.36  5184.2  268.41  5262.3  271.88  5433.6  281.84  5469.4  283.62
#Mann= 7 ,-1 , 0
  4211.9     .11       0  4815.9     .17       0  4984.8     .09       0
  5025.6     .17       0  5184.2     .11       0  5262.3     .17       0
  5433.6     .11       0
Bank Sta=4984.8,5025.6
XS Rating Curve= 0 ,0
Exp/Cntr=0.3,0.1

Type RM Length L Ch R = 1 ,11777   ,536,536,536
BEGIN DESCRIPTION:
MOUND CREEK TRIBUTARY NO. 5 18.0
END DESCRIPTION:
XS GIS Cut Line= 3
      3767659.67     10117682.54      3768472.69     10116810.43
       3768649.1     10115815.25
#Sta/Elev= 30
  3807.7  283.06  4022.9   279.2  4139.8  276.29  4203.8  276.04  4224.8  274.48
  4500.9  270.15  4736.6  264.54  4799.5  264.34  4840.4  263.29  4932.3  264.49
  4960.6  262.89  4982.1  263.28  4988.9  262.07  4996.1  257.98  5000.3  256.85
    5005  256.85  5009.5  259.32  5019.7  261.08    5040  263.55  5061.8  266.16
  5110.7  268.49  5202.5  271.17  5243.1  270.57  5618.9  280.72  5740.7  282.99
  5811.8  282.33  5852.4  283.59  5882.9  282.65  5893.1  283.59  6010.7  284.04
#Mann= 6 ,-1 , 0
  3807.7     .11       0  4022.9     .17       0  4736.6     .11       0
  4799.5     .15       0  4982.1     .09       0    5040     .17       0
Bank Sta=4982.1,5040
XS Rating Curve= 0 ,0
Exp/Cntr=0.3,0.1

Type RM Length L Ch R = 1 ,11241   ,785,785,785
BEGIN DESCRIPTION:
MOUND CREEK TRIBUTARY NO. 5 17.0
END DESCRIPTION:
XS GIS Cut Line= 3
      3768017.89     10117561.04      3768871.45     10116974.24
      3768798.54     10115828.37
#Sta/Elev= 30
  4273.4   275.8  4431.1  274.61  4460.1  272.58  4525.7  272.63    4623  269.71
    4646   268.8  4718.9  267.13  4848.4  262.49  4863.3  259.58  4878.2   261.3
  4884.3  259.37  4920.1  260.25  4964.8  257.65  4970.9  259.48  4985.8  256.75
  4991.8  257.94  5004.4  254.66  5009.1  254.66  5013.6  259.74  5021.6  262.32
  5205.5  263.86  5287.5  264.08  5352.5  268.32  5462.7  267.37  5598.6  269.63
  5793.5  271.57  5896.2  274.38  6033.8  276.65  6204.2  276.74  6457.4  282.13
#Mann= 10 ,-1 , 0
  4273.4     .11       0    4623     .17       0    4646     .11       0
  4718.9     .17       0  4970.9     .09       0  5013.6     .17       0
  5205.5     .15       0  5598.6     .17       0  5793.5     .15       0
  5896.2     .17       0
Bank Sta=4970.9,5013.6
XS Rating Curve= 0 ,0
Exp/Cntr=0.3,0.1

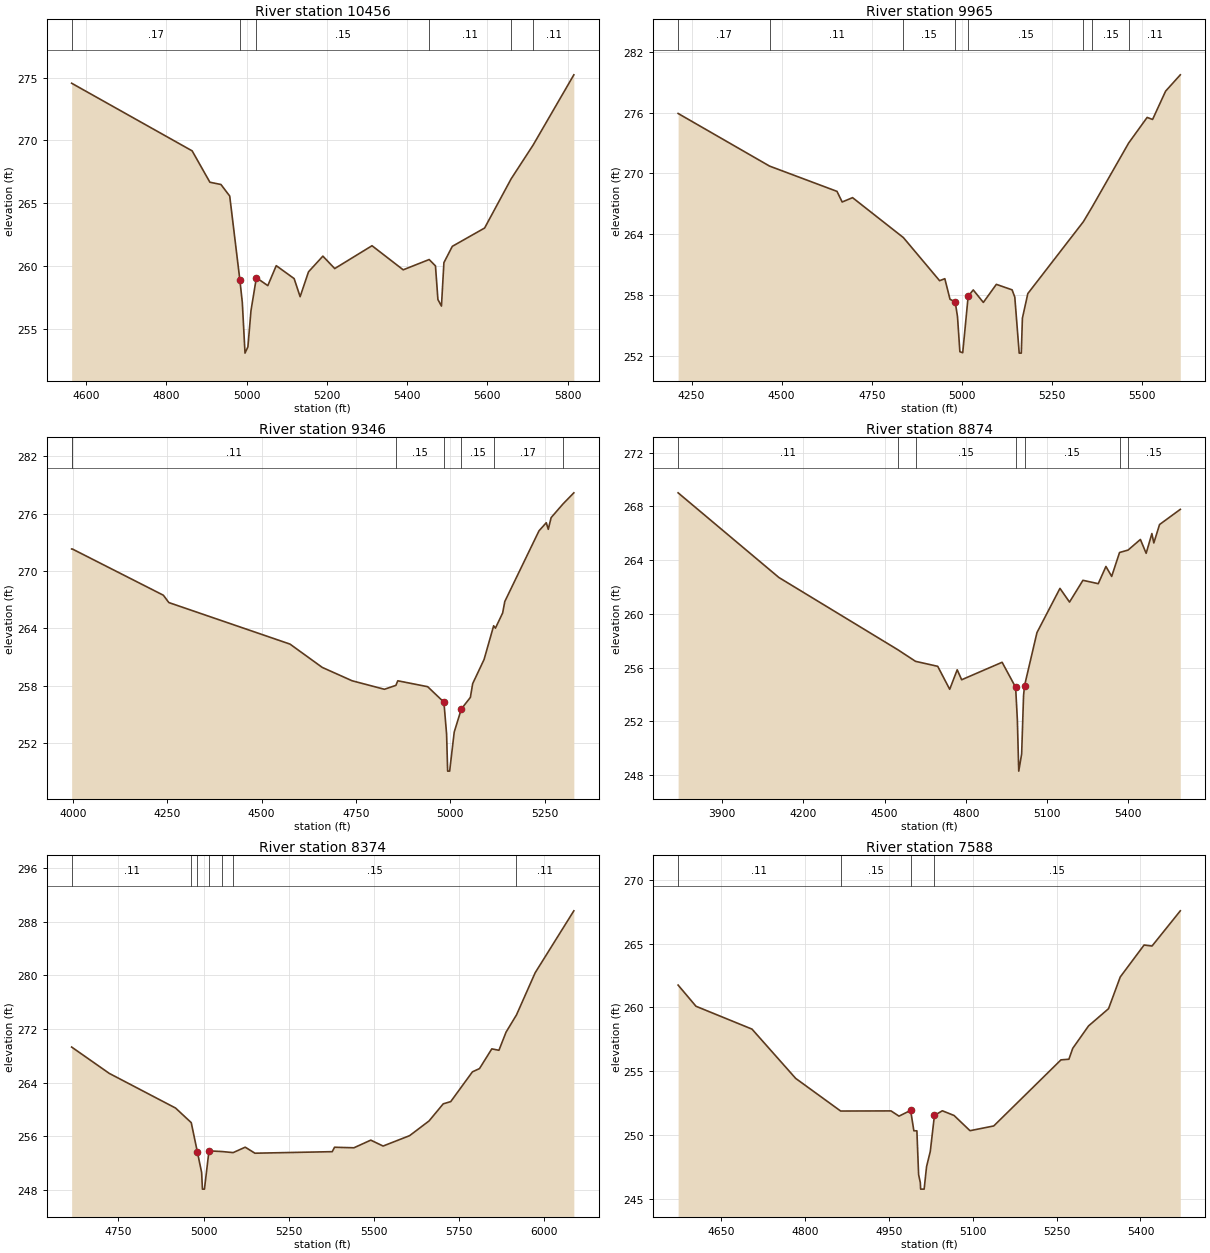
Type RM Length L Ch R = 1 ,10456   ,491,491,491
BEGIN DESCRIPTION:
MOUND CREEK TRIBUTARY NO. 5 16.0
END DESCRIPTION:
XS GIS Cut Line= 3
      3768597.15      10117915.2      3768804.12     10117531.91
      3769267.84     10116861.09
#Sta/Elev= 30
  4564.4  274.55  4864.6  269.16  4908.8  266.66  4936.3  266.48  4958.2  265.56
 4983.62258.8325  4989.6  257.07  4996.3  253.04  5003.5  253.54  5011.2  256.43
  5024.6  259.05  5053.1  258.42  5074.1  260.01  5118.7  258.98  5133.6  257.54
  5154.5  259.52  5190.3  260.77  5219.8  259.78  5312.7   261.6  5390.4  259.68
  5455.1   260.5  5470.8  259.99  5476.9  257.31  5485.7  256.79  5491.8  260.25
  5512.7  261.55  5593.2  263.01  5659.3  266.93    5714  269.62  5815.5  275.22
#Mann= 6 ,-1 , 0
  4564.4     .17       0 4983.62     .09       0  5024.6     .15       0
  5455.1     .11       0  5659.3     .15       0    5714     .11       0
Bank Sta=4983.62,5024.6
XS Rating Curve= 0 ,0
Exp/Cntr=0.3,0.1

Type RM Length L Ch R = 1 ,9965    ,619,619,619
BEGIN DESCRIPTION:
MOUND CREEK TRIBUTARY NO. 5 15.0
END DESCRIPTION:
XS GIS Cut Line= 3
      3768717.85     10118111.07      3769211.11     10117497.44
      3769545.04     10116991.63
#Sta/Elev= 30
  4212.7  275.91  4466.5  270.72  4653.5  268.23  4667.9  267.18  4696.7  267.61
  4837.8  263.67  4938.3  259.42  4952.7  259.62  4967.1  257.59  4981.5  257.33
  4987.9  255.88  4994.5  252.42  5002.4  252.32  5017.5  257.89  5031.6  258.51
  5059.6  257.28  5095.7  259.06  5139.4  258.52  5146.9   257.8  5159.1  252.28
  5164.9  252.28    5168  255.73    5183  258.15  5337.4  265.25  5362.3  266.74
  5462.7  272.99  5514.1  275.52  5529.2  275.32  5565.3  278.11  5606.1  279.72
#Mann= 8 ,-1 , 0
  4212.7     .17       0  4466.5     .11       0  4837.8     .15       0
  4981.5     .09       0  5017.5     .15       0  5337.4     .17       0
  5362.3     .15       0  5462.7     .11       0
Bank Sta=4981.5,5017.5
XS Rating Curve= 0 ,0
Exp/Cntr=0.3,0.1

Type RM Length L Ch R = 1 ,9346    ,472,472,472
BEGIN DESCRIPTION:
MOUND CREEK TRIBUTARY NO. 5 14.0
END DESCRIPTION:
XS GIS Cut Line= 3
      3768867.82      10118111.1      3769671.62      10117510.5
      3769787.61     10117204.76
#Sta/Elev= 30
  3996.6  272.31  3998.4  272.31  4239.5  267.47  4254.1   266.7  4575.1  262.35
  4660.5  259.91  4739.7  258.51  4825.2  257.62  4855.6  258.03  4860.6  258.51
  4939.8  257.89  4982.8  256.27  4989.9  252.93  4992.7  249.05    4998  249.05
  5010.1  253.14  5028.9  255.55  5052.9  256.77    5059  258.21  5089.2  260.74
  5114.6  264.27  5119.3  264.02  5138.4  265.61  5144.1  266.81  5234.7  274.21
    5254  275.06  5259.3  274.37  5266.8  275.59  5298.1  277.02    5327  278.19
#Mann= 7 ,-1 , 0
  3996.6     .17       0  3998.4     .11       0  4855.6     .15       0
  4982.8     .09       0  5028.9     .15       0  5114.6     .17       0
  5298.1     .11       0
Bank Sta=4982.8,5028.9
XS Rating Curve= 0 ,0
Exp/Cntr=0.3,0.1

Type RM Length L Ch R = 1 ,8874    ,500,500,500
BEGIN DESCRIPTION:
MOUND CREEK TRIBUTARY NO. 5 13.0
END DESCRIPTION:
XS GIS Cut Line= 3
      3768975.59      10118168.7      3770096.55     10117588.31
       3770517.3     10117172.14
#Sta/Elev= 30
  3737.7     269  4109.7   262.7  4548.4  257.33  4614.3  256.46  4696.1  256.09
  4740.4  254.38  4768.1  255.83  4784.6  255.09  4933.9  256.39  4983.8  254.53
  4990.2  252.11  4995.3  248.29    5006  249.56  5013.1  253.91 5016.62254.6437
  5062.6   258.6  5147.5  261.89  5182.8  260.87  5232.3  262.49  5288.9  262.24
  5317.2  263.52  5338.4  262.78  5367.5  264.56  5398.9  264.74  5444.5  265.53
  5465.7   264.5  5486.9  265.97    5494  265.27  5515.2  266.64  5591.8  267.77
#Mann= 7 ,-1 , 0
  3737.7     .11       0  4548.4     .17       0  4614.3     .15       0
  4983.8     .09       0 5016.62     .15       0  5367.5     .11       0
  5398.9     .15       0
Bank Sta=4983.8,5016.62
XS Rating Curve= 0 ,0
Exp/Cntr=0.3,0.1

Type RM Length L Ch R = 1 ,8374    ,786,786,786
BEGIN DESCRIPTION:
MOUND CREEK TRIBUTARY NO. 5 12.0
END DESCRIPTION:
XS GIS Cut Line= 3
      3770167.85     10118411.09       3770199.7      10118025.6
      3771017.82      10117311.1
#Sta/Elev= 30
  4613.2   269.3  4723.6  265.37    4918   260.2    4964  258.02 4982.04253.6312
  4994.5  250.57  4996.8   248.1  5002.7   248.1    5016  253.81  5053.9  253.71
    5087  253.55  5122.3  254.36  5150.8  253.46  5377.6  253.69  5384.3  254.35
  5441.2  254.27  5490.6  255.41  5526.7  254.53  5604.5  256.08  5661.4  258.27
  5703.2  260.83  5725.1  261.16  5788.7   265.6  5809.5  266.09  5845.6  269.03
  5866.5  268.82  5887.4  271.53    5918   274.1  5972.8  280.39  6086.2  289.63
#Mann= 7 ,-1 , 0
  4613.2     .11       0    4964     .15       0 4982.04     .09       0
    5016     .15       0  5053.9     .11       0    5087     .15       0
    5918     .11       0
Bank Sta=4982.04,5016
XS Rating Curve= 0 ,0
Exp/Cntr=0.3,0.1

Type RM Length L Ch R = 1 ,7588    ,527,527,527
BEGIN DESCRIPTION:
MOUND CREEK TRIBUTARY NO. 5 11.0
END DESCRIPTION:
XS GIS Cut Line= 3
      3770583.24     10118342.31      3770911.66     10118069.11
      3771260.34     10117752.02
#Sta/Elev= 30
  4572.8  261.75  4604.8  260.09    4705   258.3  4783.1  254.44  4863.6  251.88
  4953.7  251.89    4968  251.48  4988.8  251.93  4994.6  250.33    5000  250.33
  5003.1  246.89  5006.2  246.26  5006.7  245.76    5013  245.76  5017.3  247.52
    5024  248.72  5031.4  251.54  5045.6   251.9  5066.6  251.53    5095  250.34
  5137.5  250.71  5257.8  255.89    5272  255.94  5278.8  256.79  5307.1  258.55
  5342.9   259.9  5363.9  262.39  5406.5  264.89  5420.7  264.81  5471.3  267.57
#Mann= 4 ,-1 , 0
  4572.8     .11       0  4863.6     .15       0  4988.8     .09       0
  5031.4     .15       0
Bank Sta=4988.8,5031.4
XS Rating Curve= 0 ,0
Exp/Cntr=0.3,0.1