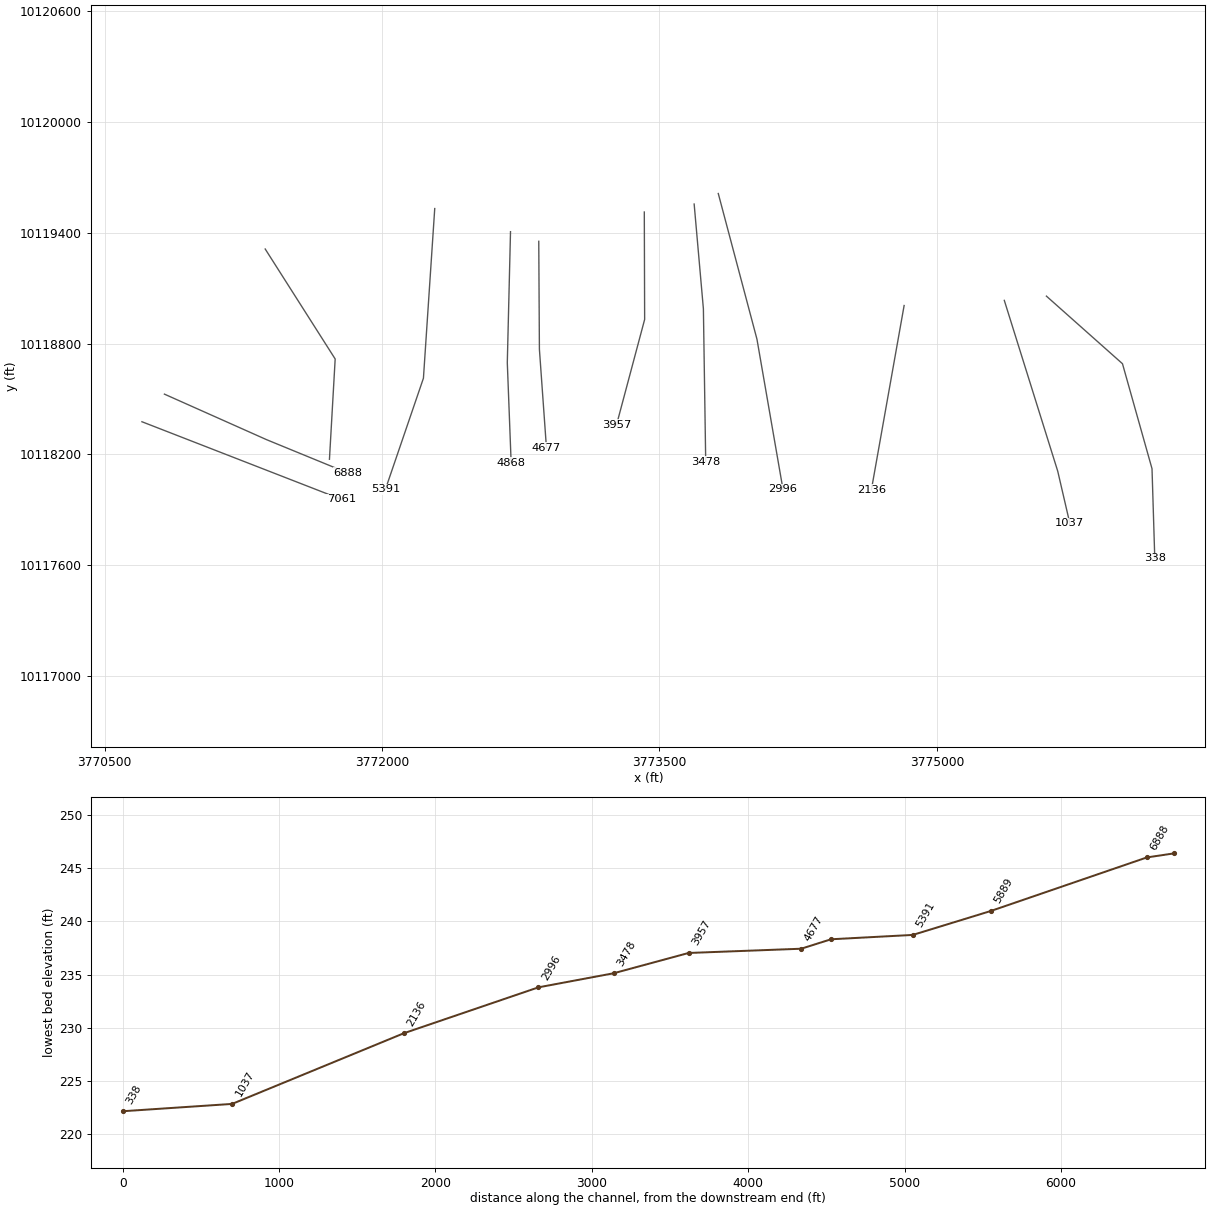
HEC-RAS study MOUND CREEK TRIBUTARY NO 5.prj: MOUND CREEK TRIBUTARY NO 5 Base Level Engineering

--- MOUND CREEK TRIBUTARY NO 5.g01 (geometry) --- (continued)

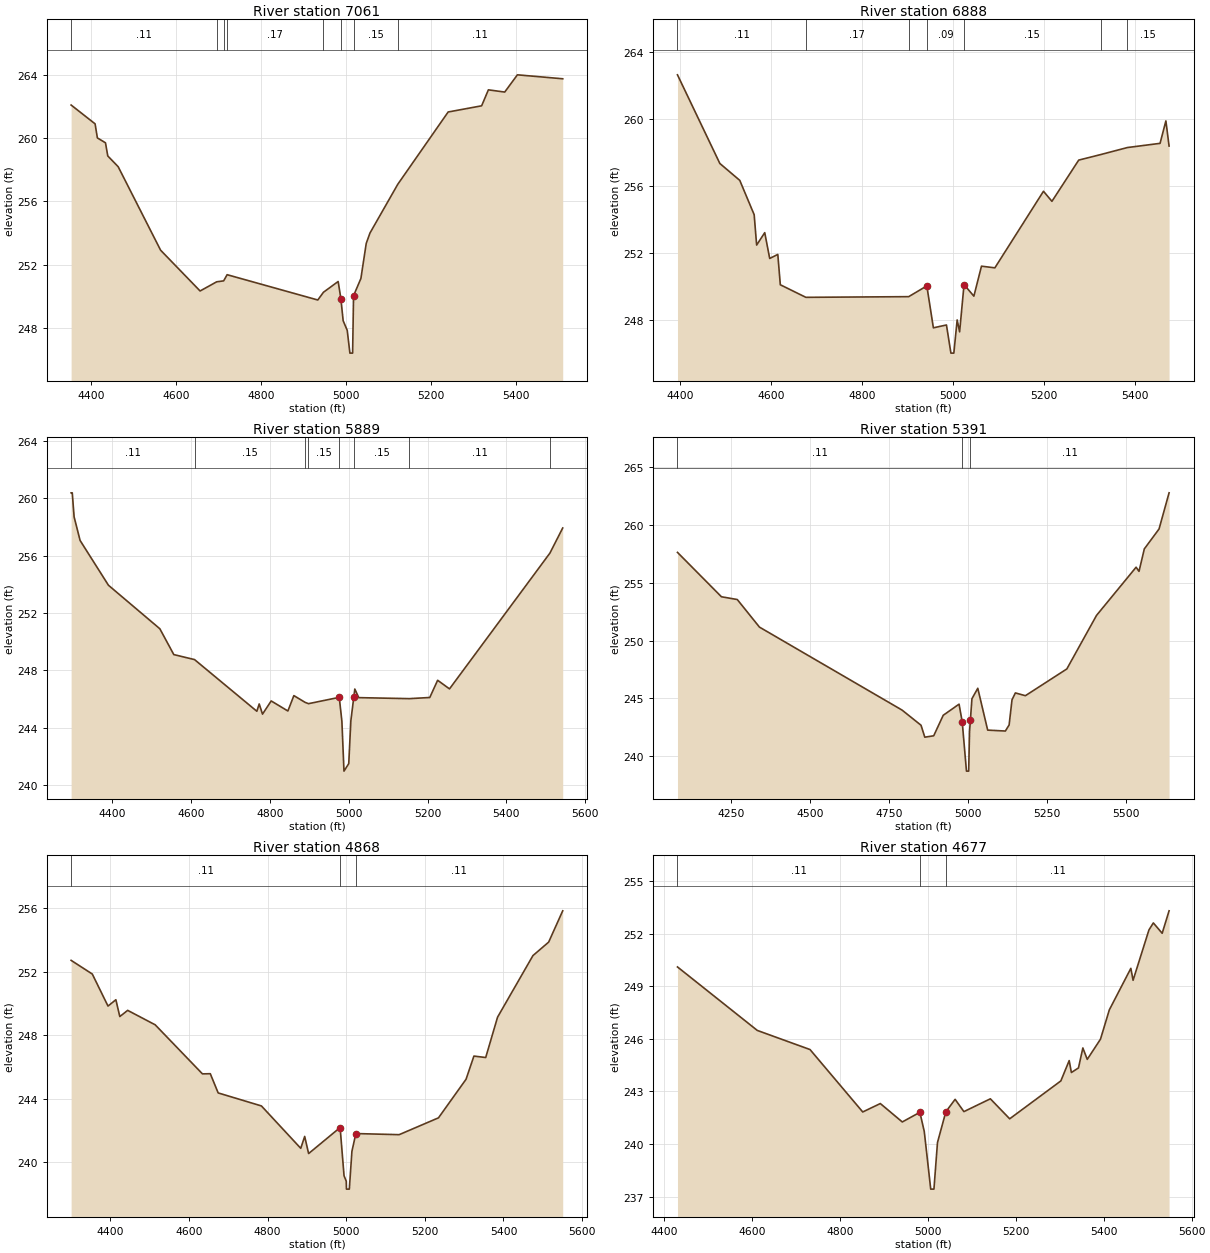
Type RM Length L Ch R = 1 ,7061    ,173,173,173
BEGIN DESCRIPTION:
Mapping XS 6c8ed257
END DESCRIPTION:
XS GIS Cut Line= 2
      3770701.32     10118377.01      3771781.17     10117956.88
#Sta/Elev= 30
  4352.2   262.1  4408.7  260.91  4414.1  260.02  4433.2  259.71  4438.6  258.88
  4463.1   258.2  4563.1  252.92  4656.2  250.34  4695.3  250.92  4711.7  250.98
  4719.9  251.37  4933.6  249.77    4947  250.26  4981.6  250.94    4988  249.86
  4993.4  248.46    5003  247.85  5009.3  246.41  5015.7  246.41  5017.9  250.04
  5035.2  251.13  5047.8  253.35  5056.7  254.01  5122.2  257.09  5240.9  261.66
  5319.8  262.05  5335.7  263.06  5374.2  262.92  5404.1  264.01  5510.9  263.76
#Mann= 8 ,-1 , 0
  4352.2     .11       0  4695.3     .17       0  4711.7     .11       0
  4719.9     .17       0    4947     .15       0    4988     .09       0
  5017.9     .15       0  5122.2     .11       0
Bank Sta=4988,5017.9
XS Rating Curve= 0 ,0
Exp/Cntr=0.3,0.1

Type RM Length L Ch R = 1 ,6888    ,999,999,999
BEGIN DESCRIPTION:
MOUND CREEK TRIBUTARY NO. 5 9.0
END DESCRIPTION:
XS GIS Cut Line= 3
      3770822.88     10118526.31      3771375.55     10118279.94
      3771814.34     10118099.88
#Sta/Elev= 30
  4394.9  262.64  4487.9  257.35  4531.7  256.34  4563.3  254.29  4568.7  252.48
  4586.5  253.22  4597.4  251.68  4615.2  251.92  4620.7  250.11  4676.8  249.36
  4902.6   249.4  4942.4250.0421  4956.8  247.54  4985.5  247.71  4995.3  246.03
  5001.7  246.03    5009  248.01  5014.4   247.3  5024.1  250.12  5045.7  249.43
  5062.4  251.22  5091.8  251.12  5198.5  255.69  5217.1  255.09  5275.9  257.55
  5324.1  257.88  5382.8   258.3  5454.5  258.55  5467.3  259.89  5474.3  258.39
#Mann= 7 ,-1 , 0
  4394.9     .11       0  4676.8     .17       0  4902.6     .15       0
  4942.4     .09       0  5024.1     .15       0  5324.1     .11       0
  5382.8     .15       0
Bank Sta=4942.4,5024.1
XS Rating Curve= 0 ,0
Exp/Cntr=0.3,0.1

Type RM Length L Ch R = 1 ,5889    ,498,498,498
BEGIN DESCRIPTION:
MOUND CREEK TRIBUTARY NO. 5 8.0
END DESCRIPTION:
XS GIS Cut Line= 3
      3771367.87     10119311.04      3771746.26     10118716.43
      3771715.32     10118174.11
#Sta/Elev= 30
  4295.2  260.37  4298.1  260.37  4302.8  258.69    4318  257.05    4390  253.93
  4520.4   250.9  4555.9   249.1  4608.6  248.75  4766.7  245.15  4772.7  245.66
  4781.1  244.95  4803.1  245.87  4845.5  245.17  4860.7  246.24  4889.3  245.77
  4897.8  245.68  4975.9  246.12  4982.6  244.46  4987.9  240.98    5000   241.5
  5005.4   244.5 5013.01246.1742  5015.4   246.7  5025.4   246.1  5153.9  246.03
  5205.7  246.11  5225.7  247.31  5255.8  246.71  5510.7  256.17  5543.2  257.92
#Mann= 8 ,-1 , 0
  4295.2     .11       0  4608.6     .15       0  4889.3     .11       0
  4897.8     .15       0  4975.9     .09       0 5013.01     .15       0
  5153.9     .11       0  5510.7     .15       0
Bank Sta=4975.9,5013.01
XS Rating Curve= 0 ,0
Exp/Cntr=0.3,0.1

Type RM Length L Ch R = 1 ,5391    ,523,523,523
BEGIN DESCRIPTION:
MOUND CREEK TRIBUTARY NO. 5 7.0
END DESCRIPTION:
XS GIS Cut Line= 3
      3772284.65     10119529.81      3772223.51     10118612.34
      3772017.84     10118011.04
#Sta/Elev= 30
  4080.5  257.61  4219.5  253.78  4269.7  253.54  4339.8  251.16  4790.8     244
  4850.9  242.69  4862.8  241.66    4891  241.78  4921.1  243.55  4971.2  244.51
  4981.2  242.98  4994.6  238.73  5001.6  238.73  5004.3  242.11 5007.08243.1599
  5011.9  244.98  5030.4  245.88  5061.7  242.27  5117.6  242.19  5129.5  242.71
  5138.7  244.89  5149.3  245.48    5181  245.24  5312.1  247.55    5406  252.17
  5531.2  256.33  5540.4  255.97  5557.2  257.91  5603.8  259.63  5635.5  262.75
#Mann= 3 , 0 , 0
  4080.5     .11       0  4981.2     .06       0 5007.08     .11       0
Bank Sta=4981.2,5007.08
XS Rating Curve= 0 ,0
Exp/Cntr=0.3,0.1

Type RM Length L Ch R = 1 ,4868    ,191,191,191
BEGIN DESCRIPTION:
MOUND CREEK TRIBUTARY NO. 5 6.0
END DESCRIPTION:
XS GIS Cut Line= 3
      3772694.37     10119404.83      3772677.01     10118696.46
      3772697.82     10118155.45
#Sta/Elev= 30
  4300.6  252.73  4354.4  251.87  4394.4  249.85  4414.4  250.25  4424.4  249.19
  4444.4  249.58  4514.4  248.67  4634.5  245.58  4654.5  245.59  4674.5  244.38
  4784.5  243.56  4884.5  240.89  4894.5  241.64  4904.5  240.56  4984.6   242.2
  4994.6  239.16  5000.2  238.82  5000.7  238.32    5008  238.32  5014.6   240.7
  5024.6  241.82  5134.7  241.75  5234.7  242.81  5304.8  245.24  5324.8   246.7
  5354.8  246.61  5384.9  249.15  5474.9  253.03  5514.9  253.88  5550.6  255.85
#Mann= 3 , 0 , 0
  4300.6     .11       0  4984.6     .06       0  5024.6     .11       0
Bank Sta=4984.6,5024.6
XS Rating Curve= 0 ,0
Exp/Cntr=0.3,0.1

Type RM Length L Ch R = 1 ,4677    ,720,720,720
BEGIN DESCRIPTION:
MOUND CREEK TRIBUTARY NO. 5 5.0
END DESCRIPTION:
XS GIS Cut Line= 3
      3772847.15     10119352.71      3772850.62     10118769.38
      3772888.76     10118235.38
#Sta/Elev= 30
  4429.9   250.1  4611.5  246.48  4731.5  245.39  4851.5  241.83  4891.5  242.31
  4941.5  241.26  4981.5  241.81  4991.5  240.72  5006.2  237.43  5013.5  237.43
  5021.6  240.09  5040.6  241.84  5061.7  242.55  5081.7  241.85  5141.9  242.58
  5185.9  241.44  5302.3   243.6  5321.3  244.76  5326.3  244.08  5342.4  244.34
  5352.4  245.48  5362.4  244.83  5392.5  245.98  5412.6  247.65  5461.6  250.02
  5466.7  249.34  5502.8  252.21  5512.8  252.61  5532.9  252.02  5548.6   253.3
#Mann= 3 , 0 , 0
  4429.9     .11       0  4981.5     .06       0  5040.6     .11       0
Bank Sta=4981.5,5040.6
XS Rating Curve= 0 ,0
Exp/Cntr=0.3,0.1

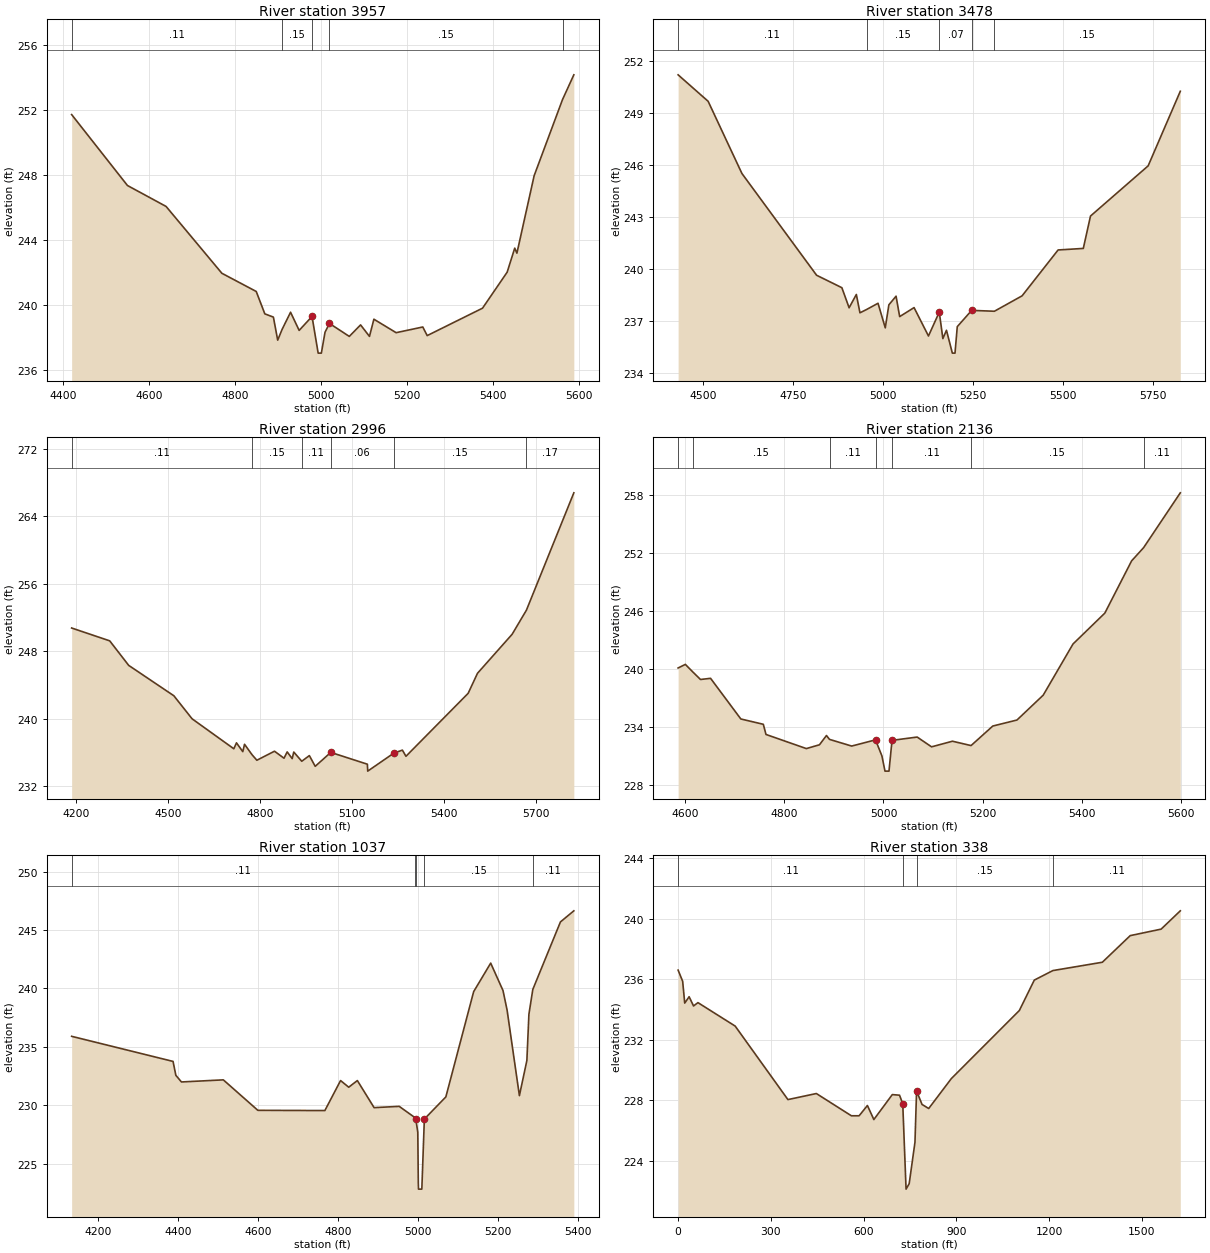
Type RM Length L Ch R = 1 ,3957    ,479,479,479
BEGIN DESCRIPTION:
MOUND CREEK TRIBUTARY NO. 5 4.0
END DESCRIPTION:
XS GIS Cut Line= 3
      3773417.85     10119511.05       3773419.7     10118930.05
      3773267.85     10118361.06
#Sta/Elev= 30
    4419  251.73    4549  247.36    4639  246.07    4769  241.95    4849  240.83
    4869  239.45    4889  239.25    4899  237.83  4909.4   238.5    4929  239.55
    4949  238.43    4979  239.29  4993.3  237.03  5000.7  237.03  5009.3  238.32
  5019.6  238.86  5065.8  238.06  5092.1  238.77  5112.8  238.06  5123.1  239.12
  5174.9  238.29    5237  238.64  5247.3  238.11  5376.2   239.8  5433.6  242.02
  5451.2   243.5  5456.3  243.19  5496.4  247.96  5562.6  252.66  5588.9  254.18
#Mann= 5 ,-1 , 0
    4419     .11       0  4909.4     .15       0    4979     .09       0
  5019.6     .15       0  5562.6     .17       0
Bank Sta=4979,5019.6
XS Rating Curve= 0 ,0
Exp/Cntr=0.3,0.1

Type RM Length L Ch R = 1 ,3478    ,482,482,482
BEGIN DESCRIPTION:
MOUND CREEK TRIBUTARY NO. 5 3.0
END DESCRIPTION:
XS GIS Cut Line= 3
      3773687.42     10119554.14       3773737.4     10118987.34
      3773749.93     10118161.74
#Sta/Elev= 30
    4431   251.2  4514.4  249.67  4608.2   245.5  4815.6  239.62  4885.8   238.9
  4905.9  237.74    4926  238.51    4936  237.45  4954.4  237.64  4986.2     238
  5006.3  236.58  5016.3  237.91  5036.3  238.41  5046.3  237.23  5086.3  237.75
  5126.3  236.11  5156.3  237.49  5166.3  235.96  5176.3  236.44  5192.6  235.12
    5200  235.12  5206.3  236.65  5246.3  237.59  5309.4  237.54  5386.3  238.43
  5486.3  241.08  5556.3  241.17  5576.3  243.04  5736.4  245.94  5825.7  250.25
#Mann= 5 ,-1 , 0
    4431     .11       0  4954.4     .15       0  5156.3     .07       0
  5246.3     .11       0  5309.4     .15       0
Bank Sta=5156.3,5246.3
XS Rating Curve= 0 ,0
Exp/Cntr=0.3,0.1

Type RM Length L Ch R = 1 ,2996    ,860,860,860
BEGIN DESCRIPTION:
MOUND CREEK TRIBUTARY NO. 5 2.0
END DESCRIPTION:
XS GIS Cut Line= 3
      3773817.84      10119611.1      3774026.98      10118823.6
      3774167.84     10118011.12
#Sta/Elev= 30
  4185.2  250.75  4309.4  249.23  4371.5  246.32  4518.9  242.72  4578.4  239.99
  4714.6  236.44  4723.3  237.14  4743.9   236.1  4749.6  236.97  4774.2  235.73
  4789.8  235.08  4847.4  236.15  4878.5  235.32  4888.8  236.07  4905.2  235.27
  4910.3  236.05  4936.4  234.96  4961.2  235.63  4980.3  234.36  5031.2  236.01
  5150.6  234.61  5151.7  233.79    5236   235.9  5264.9  236.28  5276.6  235.55
  5479.6  243.01    5510  245.38  5623.2  250.01  5669.9  252.87  5824.6  266.77
#Mann= 6 ,-1 , 0
  4185.2     .11       0  4774.2     .15       0  4936.4     .11       0
  5031.2     .06       0    5236     .15       0  5669.9     .17       0
Bank Sta=5031.2,5236
XS Rating Curve= 0 ,0
Exp/Cntr=0.3,0.1

Type RM Length L Ch R = 1 ,2136    ,1099,1099,1099
BEGIN DESCRIPTION:
Mapping XS e2c1d408
END DESCRIPTION:
XS GIS Cut Line= 2
      3774822.84     10119005.48      3774645.77     10118008.99
#Sta/Elev= 30
  4586.1  240.13  4600.7   240.5  4615.9  239.71  4631.2  238.94  4651.5  239.06
  4712.5  234.86  4757.8  234.31  4763.2  233.26  4844.5   231.8  4870.9  232.19
  4885.1  233.15  4891.2  232.75  4935.9  232.06  4983.9   232.7  4996.8  231.05
    5003  229.47  5011.1  229.47  5017.2  232.65  5067.9  232.99  5096.9  231.98
    5139  232.56  5176.5  232.11  5220.3  234.13    5269  234.75  5321.9  237.32
    5382  242.61  5446.1   245.8  5500.1   251.2  5524.2  252.56  5598.2  258.23
#Mann= 7 ,-1 , 0
  4586.1     .11       0  4615.9     .15       0  4891.2     .11       0
  4983.9     .06       0  5017.2     .11       0  5176.5     .15       0
  5524.2     .11       0
Bank Sta=4983.9,5017.2
XS Rating Curve= 0 ,0
Exp/Cntr=0.3,0.1

Type RM Length L Ch R = 1 ,1037    ,699,699,699
BEGIN DESCRIPTION:
MOUND CREEK TRIBUTARY NO. 5 1.0
END DESCRIPTION:
XS GIS Cut Line= 3
      3775364.52     10119033.23      3775653.54     10118109.28
      3775718.67     10117828.44
#Sta/Elev= 30
  4134.1   235.9  4387.8  233.75  4394.8  232.56  4408.8  231.99  4513.6  232.17
    4600  229.56  4767.6  229.54  4806.9  232.11  4827.3  231.54  4848.9  232.11
  4890.8  229.79  4953.6   229.9  4992.8  228.94  4994.9  228.86  5000.1  227.68
  5001.4  223.31  5001.9  222.81  5010.2  222.81  5016.5  228.81  5070.3  230.71
  5139.9  239.73  5182.5  242.17  5213.3  239.82  5223.5  238.15  5254.3  230.82
    5273  233.83  5278.1  237.79  5287.9  239.92    5357   245.7  5390.5  246.65
#Mann= 5 ,-1 , 0
  4134.1     .11       0  4992.8     .15       0  4994.9     .06       0
  5016.5     .15       0  5287.9     .11       0
Bank Sta=4994.9,5016.5
XS Rating Curve= 0 ,0
Exp/Cntr=0.3,0.1

Type RM Length L Ch R = 1 ,338     ,0,0,0
BEGIN DESCRIPTION:
MOUND CREEK TRIBUTARY NO. 5 1.0
END DESCRIPTION:
XS GIS Cut Line= 4
      3775592.26     10119056.24      3776003.56     10118690.71
      3776163.28       10118123.       3776178.2     10117639.14
#Sta/Elev= 30
       0   236.6    14.7  235.86    21.4  234.42    35.6  234.84    49.9  234.23
    64.1  234.45   184.5   232.9   355.1  228.04   447.1  228.44   560.3  226.97
   585.4  226.97   612.2  227.65     633  226.72   692.7  228.37   716.1  228.33
   726.5  227.76   737.2  222.12   747.3  222.48     766  225.22   771.2  228.61
   788.8  227.72   810.4  227.45   883.7  229.43  1103.6  233.93  1151.9  235.94
    1212  236.57    1372  237.12  1462.1  238.88  1562.1  239.31  1624.1  240.52
#Mann= 4 ,-1 , 0
       0     .11       0   726.5     .06       0   771.2     .15       0
    1212     .11       0
Bank Sta=726.5,771.2
XS Rating Curve= 0 ,0
Exp/Cntr=0.3,0.1

Chan Stop Cuts=-1
Use User Specified Reach Order=0
Composite Channel Slope=5