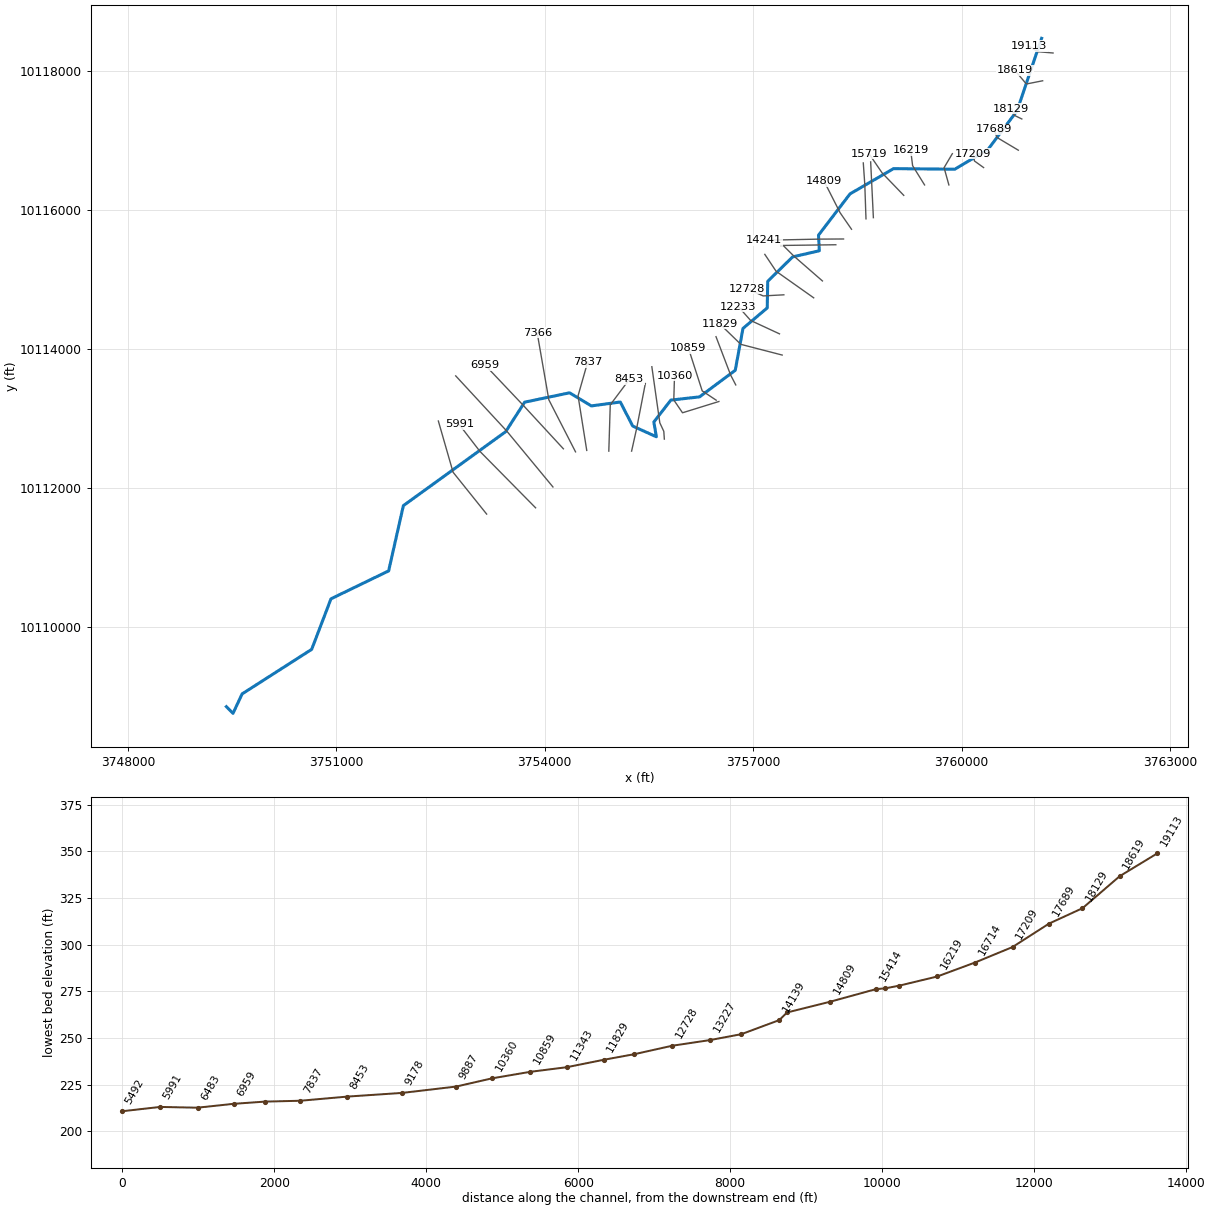
--- SPRING BRANCH NO 2.prj (project) ---

Proj Title=SPRING BRANCH NO 2 Base Level Engineering
Current Plan=p01
Default Exp/Contr=0.3,0.1
English Units
Geom File=g01
Flow File=f01
Plan File=p01
Y Axis Title=Elevation
X Axis Title(PF)=Main Channel Distance
X Axis Title(XS)=Station
BEGIN DESCRIPTION:
SPRING BRANCH NO 2
END DESCRIPTION:
DSS Export Rating Curves= 0
DSS Export Rating Curve Sorted= 0
DSS Export Volume Flow Curves= 0
DXF OffsetX= 0
DXF OffsetY= 0
DXF ScaleX= 1
DXF ScaleY= 10

--- SPRING BRANCH NO 2.p01 (plan) ---

Plan Title=Multiple Run
Short Identifier=Multiple
Geom File=g01
Flow File=f01
Subcritical Flow
K Sum by GR= 0
Std Step Tol= 0.01
Critical Tol= 0.01
Num of Std Step Trials= 20
Max Error Tol= 0.3
Flow Tol Ratio= 0.001
Split Flow NTrial= 30
Split Flow Tol= 0.02
Split Flow Ratio= 0.02
Log Output Level= 0
Friction Slope Method= 1
Unsteady Friction Slope Method= 2
Unsteady Bridges Friction Slope Method= 1
Parabolic Critical Depth
Global Vel Dist=  1 , 1 , 1
Global Log Level= 0
CheckData=True
Encroach Param= -1, 0, 0, 0
BEGIN DESCRIPTION:
Multiple Run
END DESCRIPTION:

--- SPRING BRANCH NO 2.f01 (steady flow) ---

Flow Title=Multiple
Program Version=4.10
Number of Profiles= 7
Profile Names=10-year,25-year,50-year,1pct_min,100-year,1pct_plu,500-year
River Rch & RM=SPRING BRANCH NO,Reach-1         ,19113
     593     808    1097     491    1483    4479    2802
River Rch & RM=SPRING BRANCH NO,Reach-1         ,9887
    1234    1735    2406    1095    3306    9984    6462
Boundary for River Rch & Prof#=SPRING BRANCH NO,Reach-1         , 1
Up Type= 0
Dn Type= 3
Dn Slope=0.005
Boundary for River Rch & Prof#=SPRING BRANCH NO,Reach-1         , 2
Up Type= 0
Dn Type= 3
Dn Slope=0.005
Boundary for River Rch & Prof#=SPRING BRANCH NO,Reach-1         , 3
Up Type= 0
Dn Type= 3
Dn Slope=0.005
Boundary for River Rch & Prof#=SPRING BRANCH NO,Reach-1         , 4
Up Type= 0
Dn Type= 3
Dn Slope=0.005
Boundary for River Rch & Prof#=SPRING BRANCH NO,Reach-1         , 5
Up Type= 0
Dn Type= 3
Dn Slope=0.005
Boundary for River Rch & Prof#=SPRING BRANCH NO,Reach-1         , 6
Up Type= 0
Dn Type= 3
Dn Slope=0.005
Boundary for River Rch & Prof#=SPRING BRANCH NO,Reach-1         , 7
Up Type= 0
Dn Type= 3
Dn Slope=0.005
DSS Import GetInterval= 0
DSS Import GetPeak= 0
DSS Import FillOption= 0

--- SPRING BRANCH NO 2.g01 (geometry) ---

Geom Title=Existing Conditions
Program Version=4.10

River Reach=SPRING BRANCH NO,Reach-1
Reach XY= 30
      3761152.84     10118472.21      3760799.27     10117428.48
      3760379.23     10116869.85      3759903.22     10116587.48
      3759021.38      10116595.8      3758394.74     10116232.21
      3757940.84     10115637.61      3757952.84     10115412.82
      3757568.37     10115324.55      3757209.86     10114973.31
      3757202.78     10114590.05      3756853.46     10114294.47
       3756742.3     10113691.41      3756228.29     10113308.88
      3755814.89     10113262.26      3755570.33     10112946.97
      3755605.97     10112734.49      3755266.08     10112888.44
      3755087.44     10113234.84      3754670.61     10113178.57
       3754357.2     10113367.29      3753710.54     10113232.63
       3753437.1     10112807.28      3751964.12     10111742.28
      3751752.19     10110802.64      3750921.96     10110400.57
      3750644.24     10109672.71      3749642.72     10109031.05
      3749511.44      10108750.7      3749416.27     10108847.62

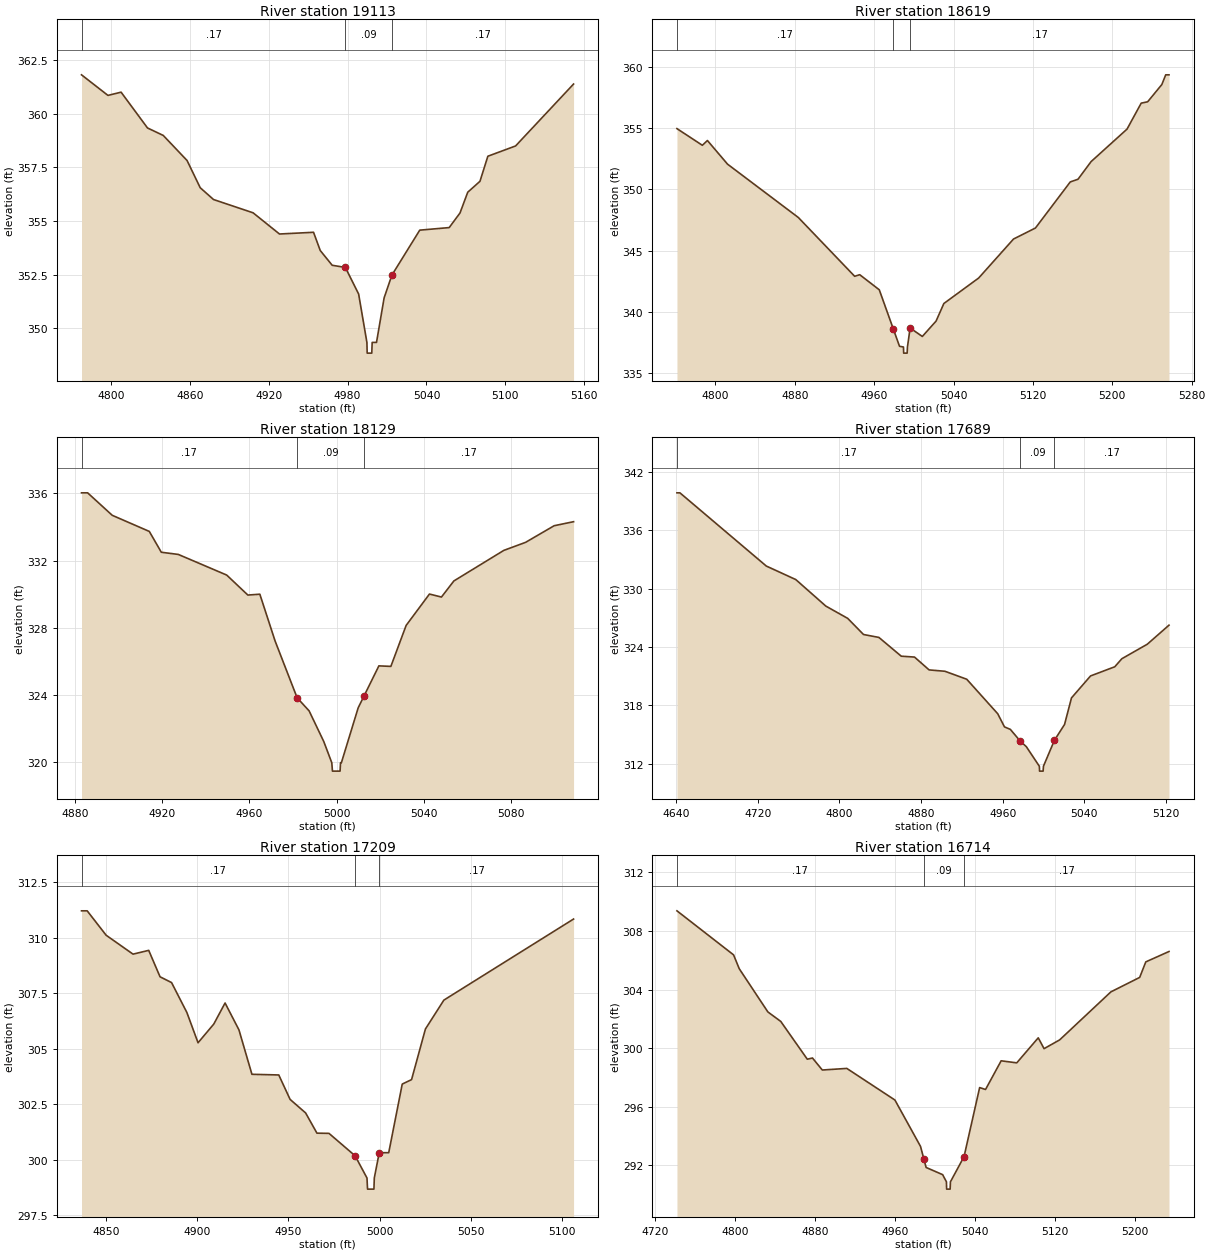
Type RM Length L Ch R = 1 ,19113   ,494,494,494
BEGIN DESCRIPTION:
SPRING BRANCH NO. 2 38.0
END DESCRIPTION:
XS GIS Cut Line= 3
      3761317.87     10118261.07      3761096.27     10118279.87
      3760967.88     10118361.05
#Sta/Elev= 30
  4777.6  361.82  4797.7  360.86  4807.7  361.01  4827.8  359.34  4839.8  358.99
  4857.9  357.82  4867.9  356.55    4878     356  4908.1  355.38  4928.2  354.39
  4954.1  354.47  4959.2  353.62  4968.3  352.93  4978.3  352.83  4988.4  351.59
  4994.7  349.33  4994.9  348.83  4998.4  348.83  4998.7  349.33    5002  349.33
  5007.8  351.41  5013.7  352.47  5034.9  354.57  5057.3  354.69  5065.5  355.37
  5071.4  356.34  5080.7  356.85  5086.7  358.02  5107.8   358.5  5151.9  361.39
#Mann= 3 , 0 , 0
  4777.6     .17       0  4978.3     .09       0  5013.7     .17       0
Bank Sta=4978.3,5013.7
XS Rating Curve= 0 ,0
Exp/Cntr=0.3,0.1

Type RM Length L Ch R = 1 ,18619   ,490,490,490
BEGIN DESCRIPTION:
SPRING BRANCH NO. 2 37.0
END DESCRIPTION:
XS GIS Cut Line= 3
      3761167.86     10117861.07      3760933.62     10117814.58
      3760767.84     10118011.09
#Sta/Elev= 30
  4761.2  354.95  4786.8  353.59  4791.9  353.98  4812.2  352.05  4883.5   347.7
  4940.3   342.9  4945.4  343.03  4965.1   341.8 4979.43338.5617  4985.5  337.19
  4989.5  337.13  4989.7  336.63  4993.2  336.63  4993.5  337.13  4996.2  338.68
  5008.5  337.99  5022.4  339.25  5030.2  340.68  5065.3  342.76  5100.4  345.94
  5122.5  346.84  5157.6   350.6  5165.4  350.82  5178.6  352.26  5214.8  354.91
  5229.1  357.03  5235.6  357.14  5249.9  358.55  5253.8  359.34  5257.1  359.34
#Mann= 3 , 0 , 0
  4761.2     .17       0 4979.43     .09       0  4996.2     .17       0
Bank Sta=4979.43,4996.2
XS Rating Curve= 0 ,0
Exp/Cntr=0.3,0.1

Type RM Length L Ch R = 1 ,18129   ,440,440,440
BEGIN DESCRIPTION:
SPRING BRANCH NO. 2 36.0
END DESCRIPTION:
XS GIS Cut Line= 3
      3760867.83     10117311.08       3760762.5     10117362.01
      3760717.83     10117461.11
#Sta/Elev= 30
    4883  336.04  4885.8  336.04  4897.1   334.7  4914.1  333.74  4919.6   332.5
  4927.4  332.37  4949.6  331.14  4959.3  329.95  4964.8     330  4971.8  327.21
  4981.9  323.83  4987.4  323.05  4994.1  321.23  4997.8  319.96  4998.1  319.46
  5001.6  319.46  5001.8  319.96  5002.2  319.96  5009.9  323.23 5012.65323.9537
  5019.4  325.73  5024.9   325.7  5031.9  328.14  5042.6  330.01  5048.1  329.83
  5053.8  330.79  5076.7  332.61  5086.7  333.09  5099.8  334.08  5108.7  334.32
#Mann= 3 , 0 , 0
    4883     .17       0  4981.9     .09       0 5012.65     .17       0
Bank Sta=4981.9,5012.65
XS Rating Curve= 0 ,0
Exp/Cntr=0.3,0.1

Type RM Length L Ch R = 1 ,17689   ,480,480,480
BEGIN DESCRIPTION:
SPRING BRANCH NO. 2 35.0
END DESCRIPTION:
XS GIS Cut Line= 3
      3760817.86     10116861.06      3760509.34     10117045.22
      3760467.84     10117161.11
#Sta/Elev= 30
  4640.7  339.85  4643.6  339.85  4728.3  332.32  4757.2  330.93  4786.7   328.2
  4808.1  326.94  4823.6  325.28  4838.7  324.98  4860.6  323.05  4873.6  322.96
  4887.9  321.64  4903.4   321.5  4924.8  320.68  4955.2  317.13  4961.8  315.78
  4967.6  315.52  4977.4   314.3  4983.2  313.75    4996  311.73  4996.2  311.23
  4999.7  311.23    5000  311.73 5010.76314.3965  5020.7  316.03  5027.5  318.76
  5046.2  321.02  5069.9  321.96  5076.9  322.79  5101.8  324.28  5123.1  326.24
#Mann= 3 , 0 , 0
  4640.7     .17       0  4977.4     .09       0 5010.76     .17       0
Bank Sta=4977.4,5010.76
XS Rating Curve= 0 ,0
Exp/Cntr=0.3,0.1

Type RM Length L Ch R = 1 ,17209   ,495,495,495
BEGIN DESCRIPTION:
SPRING BRANCH NO. 2 34.0
END DESCRIPTION:
XS GIS Cut Line= 3
      3760317.86     10116611.07      3760185.31     10116706.46
      3760167.85     10116811.11
#Sta/Elev= 30
  4836.7  311.21  4839.8  311.21  4850.2  310.11  4864.9  309.26  4873.5  309.43
  4879.7  308.24    4886  307.98  4894.4  306.63  4900.5  305.27  4909.1  306.11
  4915.3  307.06  4922.9  305.85    4930  303.85  4944.7  303.82  4950.9  302.72
  4959.4  302.11  4965.6   301.2  4972.2  301.19  4986.5  300.18    4993  299.18
  4993.3  298.68  4996.8  298.68    4997  299.18  4999.7  300.32  5004.9  300.32
  5012.3  303.41  5017.4  303.61    5025  305.89  5035.1  307.19  5106.1  310.84
#Mann= 3 , 0 , 0
  4836.7     .17       0  4986.5     .09       0  4999.7     .17       0
Bank Sta=4986.5,4999.7
XS Rating Curve= 0 ,0
Exp/Cntr=0.3,0.1

Type RM Length L Ch R = 1 ,16714   ,495,495,495
BEGIN DESCRIPTION:
SPRING BRANCH NO. 2 33.0
END DESCRIPTION:
XS GIS Cut Line= 3
      3759817.85     10116361.07       3759748.9     10116609.59
      3759867.86     10116811.09
#Sta/Elev= 30
  4742.1  309.38  4798.7  306.37  4804.4  305.42    4833  302.47  4845.9  301.82
  4872.4  299.24  4877.6  299.32  4887.4   298.5  4911.9  298.61    4960  296.45
  4985.6  293.28 4988.85292.4443  4991.2  291.84  5007.7  291.35  5011.5  290.86
  5011.7  290.36  5015.2  290.36  5015.5  290.86  5029.1  292.58  5044.7   297.3
  5050.6  297.17  5066.2  299.13  5081.8  298.99  5103.3   300.7  5109.1  299.96
  5124.7  300.56  5175.9  303.84  5204.7  304.83  5210.8  305.89    5234   306.6
#Mann= 3 , 0 , 0
  4742.1     .17       0 4988.85     .09       0  5029.1     .17       0
Bank Sta=4988.85,5029.1
XS Rating Curve= 0 ,0
Exp/Cntr=0.3,0.1

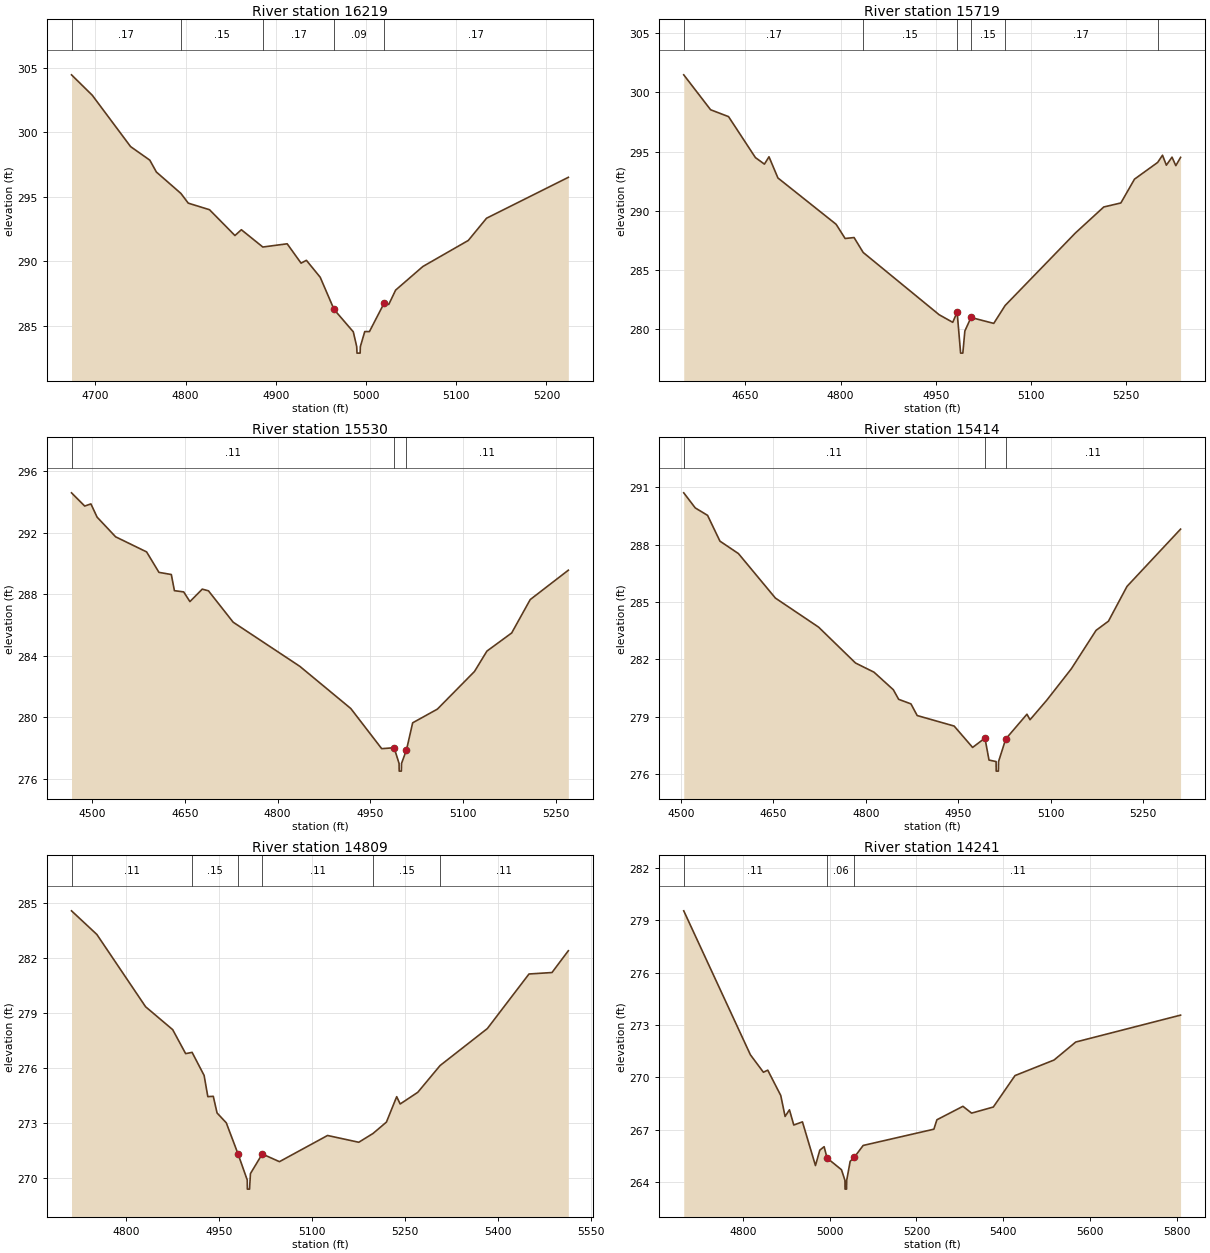
Type RM Length L Ch R = 1 ,16219   ,500,500,500
BEGIN DESCRIPTION:
SPRING BRANCH NO. 2 32.0
END DESCRIPTION:
XS GIS Cut Line= 3
      3759467.83      10116361.1      3759295.66     10116638.52
      3759267.85     10116861.09
#Sta/Elev= 30
  4673.5  304.46  4696.5  302.88    4739   298.9  4760.3  297.85  4767.6  296.93
  4794.8  295.27  4802.9  294.52  4826.5  294.01  4854.7  292.01  4861.8  292.46
  4885.6  291.12  4912.6  291.37    4928  289.87  4933.9  290.09  4949.2  288.78
  4964.6  286.28  4985.9  284.55  4989.7   283.4    4990   282.9  4993.5   282.9
  4993.7   283.4  4998.6  284.57  5003.8  284.57  5020.2  286.79  5025.2  286.67
  5032.8  287.78    5063  289.61  5113.4  291.63  5133.6  293.35  5224.3  296.52
#Mann= 5 ,-1 , 0
  4673.5     .17       0  4794.8     .15       0  4885.6     .17       0
  4964.6     .09       0  5020.2     .17       0
Bank Sta=4964.6,5020.2
XS Rating Curve= 0 ,0
Exp/Cntr=0.3,0.1

Type RM Length L Ch R = 1 ,15719   ,189,189,189
BEGIN DESCRIPTION:
SPRING BRANCH NO. 2 31.0
END DESCRIPTION:
XS GIS Cut Line= 3
      3759167.88     10116211.04      3758857.48     10116533.25
      3758667.83      10116811.1
#Sta/Elev= 30
  4552.6  301.49    4595  298.54  4623.3  297.96  4665.7   294.5  4679.9  293.95
  4687.1  294.57  4701.2  292.78    4793  288.87  4807.2  287.67  4821.3  287.75
  4835.7  286.49  4955.6  281.23    4977  280.59  4983.9  281.46  4989.4  277.99
  4992.9  277.99  4996.1  279.86  5005.8     281  5041.7   280.5  5059.6  282.01
  5170.4  288.13  5215.2  290.33  5242.2  290.67  5263.7  292.68  5300.2  294.09
  5307.9   294.7    5314  293.86  5322.9  294.54  5328.9  293.82  5336.4  294.52
#Mann= 6 ,-1 , 0
  4552.6     .17       0  4835.7     .15       0  4983.9     .09       0
  5005.8     .15       0  5059.6     .17       0  5300.2     .11       0
Bank Sta=4983.9,5005.8
XS Rating Curve= 0 ,0
Exp/Cntr=0.3,0.1

Type RM Length L Ch R = 1 ,15530   ,116,116,116
BEGIN DESCRIPTION:
Mapping XS 2bf80fd3
END DESCRIPTION:
XS GIS Cut Line= 2
      3758730.94     10115889.74      3758691.88     10116692.69
#Sta/Elev= 30
  4466.5   294.6  4487.9  293.74  4497.9  293.88  4507.9  293.02  4537.9  291.74
    4588  290.76    4608  289.43    4628  289.29    4633  288.24    4648  288.16
  4658.1  287.53  4678.1  288.34  4688.1  288.23  4728.1  286.19    4836  283.32
  4918.4  280.58  4968.4  277.97  4988.5  278.03  4996.5  277.01  4996.7  276.51
  5000.2  276.51  5000.5  277.01  5008.5  277.89  5018.5  279.65  5058.5  280.54
  5118.6  282.99  5138.6  284.31  5178.7  285.49  5208.7  287.66  5270.4  289.57
#Mann= 3 , 0 , 0
  4466.5     .11       0  4988.5     .06       0  5008.5     .11       0
Bank Sta=4988.5,5008.5
XS Rating Curve= 0 ,0
Exp/Cntr=0.3,0.1

Type RM Length L Ch R = 1 ,15414   ,605,605,605
BEGIN DESCRIPTION:
SPRING BRANCH NO. 2 30.0
END DESCRIPTION:
XS GIS Cut Line= 3
       3758624.6     10115872.35      3758607.24     10116369.32
      3758585.66     10116677.89
#Sta/Elev= 30
  4504.5  290.72  4523.2  289.93  4543.2  289.54  4563.3  288.19  4593.3  287.54
  4653.3  285.21  4723.4  283.69  4783.4  281.81  4813.4  281.33  4844.8  280.41
  4853.4  279.91  4873.4  279.67  4883.5  279.06  4943.5  278.51  4973.5  277.39
  4993.5  277.88  5000.1  276.73  5011.6  276.65  5011.8  276.15  5015.3  276.15
  5015.6  276.65 5027.28277.8324  5061.7  279.13  5066.7  278.84  5093.8  279.86
  5133.8  281.51  5173.9  283.52    5194     284  5224.1  285.82  5311.1  288.82
#Mann= 3 , 0 , 0
  4504.5     .11       0  4993.5     .06       0 5027.28     .11       0
Bank Sta=4993.5,5027.28
XS Rating Curve= 0 ,0
Exp/Cntr=0.3,0.1

Type RM Length L Ch R = 1 ,14809   ,568,568,568
BEGIN DESCRIPTION:
SPRING BRANCH NO. 2 29.0
END DESCRIPTION:
XS GIS Cut Line= 3
      3758416.26     10115722.64      3758251.34     10115961.33
      3758019.92     10116417.68
#Sta/Elev= 30
  4711.7  284.58  4752.6  283.29  4831.3  279.34    4875  278.09  4895.9  276.78
  4906.3  276.85  4925.7  275.59  4931.7  274.43  4940.5  274.45  4946.6  273.54
  4961.5     273 4980.63271.2846  4995.3  269.88  4995.5  269.38    4999  269.38
  5000.5  270.23  5019.5   271.3  5047.3  270.88  5124.9  272.31  5175.3  271.94
  5198.3  272.42  5219.9  273.04  5236.5  274.43  5242.1  274.03  5270.6  274.67
  5306.5  276.13  5382.8  278.15    5450  281.13  5487.1  281.21  5513.5   282.4
#Mann= 6 ,-1 , 0
  4711.7     .11       0  4906.3     .15       0 4980.63     .09       0
  5019.5     .11       0  5198.3     .15       0  5306.5     .11       0
Bank Sta=4980.63,5019.5
XS Rating Curve= 0 ,0
Exp/Cntr=0.3,0.1

Type RM Length L Ch R = 1 ,14241   ,102,102,102
BEGIN DESCRIPTION:
SPRING BRANCH NO. 2 28.0
END DESCRIPTION:
XS GIS Cut Line= 3
      3758301.52     10115582.59      3757942.83      10115580.6
       3757156.2     10115564.09
#Sta/Elev= 30
  4663.6  279.54  4817.3   271.3  4847.3   270.3  4857.3  270.42  4887.3  268.97
  4897.3  267.77  4907.3  268.15  4917.3  267.28  4937.3  267.46  4967.3  264.96
  4977.3  265.84  4987.3  266.04 4993.97 265.393  5027.3  264.72  5035.3  264.11
  5035.5  263.61    5039  263.61  5039.3  264.11  5047.3   265.2  5057.3  265.45
  5077.3  266.11  5240.3  267.04  5247.3  267.58  5307.3  268.35  5327.3  267.96
  5377.4  268.31  5427.4  270.11  5517.4     271  5567.4  272.03  5809.1  273.57
#Mann= 3 , 0 , 0
  4663.6     .11       0 4993.97     .06       0  5057.3     .11       0
Bank Sta=4993.97,5057.3
XS Rating Curve= 0 ,0
Exp/Cntr=0.3,0.1

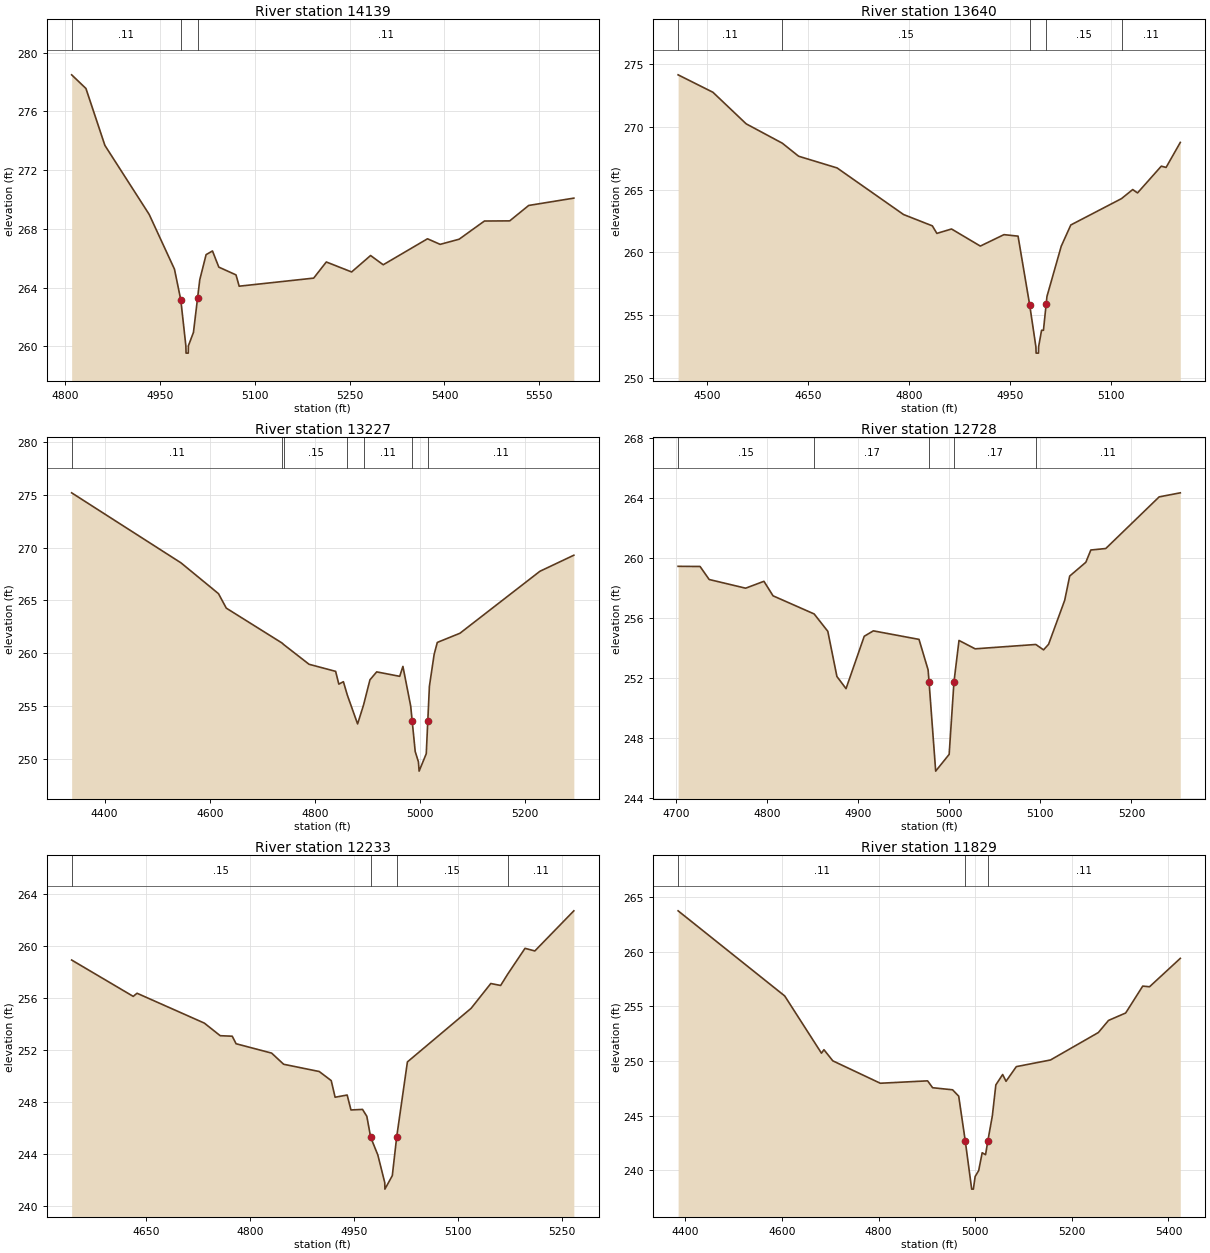
Type RM Length L Ch R = 1 ,14139   ,499,499,499
BEGIN DESCRIPTION:
Mapping XS 404b4bfe
END DESCRIPTION:
XS GIS Cut Line= 2
      3758190.48     10115499.54      3757396.45     10115489.03
#Sta/Elev= 30
  4810.5  278.49  4833.1  277.56  4863.1  273.68  4933.1  268.98  4973.1  265.25
  4983.1  263.15  4991.1  260.03  4991.4  259.53  4994.9  259.53  4995.1  260.03
  5003.1  260.94 5009.54 263.252  5013.1  264.53  5023.1  266.24  5033.2  266.49
  5043.2  265.39  5070.4  264.86  5075.4  264.09  5193.2  264.64  5213.2  265.74
  5253.2  265.06  5283.2  266.18  5303.2  265.55  5373.2  267.32  5393.2  266.94
  5423.2  267.29  5463.2  268.53  5503.2  268.54  5533.2  269.59  5604.6  270.09
#Mann= 3 ,-1 , 0
  4810.5     .11       0  4983.1     .07       0 5009.54     .11       0
Bank Sta=4983.1,5009.54
XS Rating Curve= 0 ,0
Exp/Cntr=0.3,0.1

Type RM Length L Ch R = 1 ,13640   ,413,413,413
BEGIN DESCRIPTION:
SPRING BRANCH NO. 2 27.0
END DESCRIPTION:
XS GIS Cut Line= 3
       3757997.4     10114978.28      3757588.56     10115334.42
       3757444.2     10115477.28
#Sta/Elev= 30
  4457.2  274.14  4508.9  272.75  4558.2  270.24  4611.8   268.7  4636.1  267.66
  4693.1  266.73  4791.8  263.02  4834.5  262.12  4841.2  261.52    4863  261.87
  4905.7  260.51  4940.8  261.42  4961.7   261.3 4978.87255.8562  4988.2  252.49
  4988.5  251.99    4992  251.99  4992.2  252.49  4996.6  253.81  4999.4  253.81
 5003.42255.8895  5004.6   256.5  5025.8   260.5    5040  262.19  5115.3  264.29
  5131.9  265.01    5139  264.74  5174.3  266.87  5181.4  266.77  5202.5  268.76
#Mann= 5 ,-1 , 0
  4457.2     .11       0  4611.8     .15       0 4978.87     .09       0
 5003.42     .15       0  5115.3     .11       0
Bank Sta=4978.87,5003.42
XS Rating Curve= 0 ,0
Exp/Cntr=0.3,0.1

Type RM Length L Ch R = 1 ,13227   ,499,499,499
BEGIN DESCRIPTION:
SPRING BRANCH NO. 2 26.0
END DESCRIPTION:
XS GIS Cut Line= 3
      3757871.53     10114735.23       3757330.6     10115117.89
      3757167.86     10115361.06
#Sta/Elev= 30
  4337.4  275.19  4545.3  268.56  4616.7  265.64  4631.5  264.27  4737.4  260.97
  4741.2   260.8    4789  258.95  4839.5  258.28  4845.6  257.07  4854.3   257.3
  4861.7  256.04  4881.3   253.3  4892.6  255.09  4904.8  257.48  4917.6  258.23
  4961.4  257.81  4967.5  258.75  4982.3  254.99 4985.16253.5565  4990.9  250.68
    4997  249.71  4998.3  248.83  5011.9  250.48 5014.82253.5946  5017.9  256.88
  5026.9  259.89  5032.9  261.02    5076  261.89  5228.1  267.76  5292.6  269.28
#Mann= 7 ,-1 , 0
  4337.4     .11       0  4737.4     .17       0  4741.2     .15       0
  4861.7     .17       0  4892.6     .11       0 4985.16     .06       0
 5014.82     .11       0
Bank Sta=4985.16,5014.82
XS Rating Curve= 0 ,0
Exp/Cntr=0.3,0.1

Type RM Length L Ch R = 1 ,12728   ,495,495,495
BEGIN DESCRIPTION:
SPRING BRANCH NO. 2 25.0
END DESCRIPTION:
XS GIS Cut Line= 3
      3757441.87      10114778.6       3757144.8     10114762.59
      3756913.23     10114866.22
#Sta/Elev= 30
  4702.5  259.46  4726.6  259.45  4736.6  258.58  4776.6     258  4796.7  258.46
  4806.7  257.49  4851.8  256.28  4866.8  255.12  4876.8   252.1  4886.8  251.29
  4906.8  254.79  4916.8  255.15  4966.9  254.58  4976.9  252.54 4977.94251.7262
  4985.2  245.78    5000   246.9  5005.3  251.75  5010.8  254.51  5028.5  253.95
  5095.1  254.24  5103.6  253.88  5109.1  254.25  5126.8  257.19  5132.3  258.81
    5150  259.73  5155.5  260.55  5171.9  260.65  5230.5   264.1  5253.7  264.37
#Mann= 5 ,-1 , 0
  4702.5     .15       0  4851.8     .17       0 4977.94     .09       0
  5005.3     .17       0  5095.1     .11       0
Bank Sta=4977.94,5005.3
XS Rating Curve= 0 ,0
Exp/Cntr=0.3,0.1

Type RM Length L Ch R = 1 ,12233   ,404,404,404
BEGIN DESCRIPTION:
SPRING BRANCH NO. 2 24.0
END DESCRIPTION:
XS GIS Cut Line= 3
      3757378.93     10114216.55      3756963.77     10114409.02
      3756786.49     10114609.34
#Sta/Elev= 30
  4542.4  258.93  4631.3  256.13  4636.8  256.37    4734  254.07  4756.9   253.1
  4774.3  253.06  4779.8  252.48  4831.1  251.76  4848.5   250.9  4899.9  250.34
  4917.2  249.64  4922.8  248.36  4940.2  248.53  4945.7  247.38  4962.4  247.42
  4968.6  246.89  4974.1  245.29  4984.5  243.91  4994.5  241.78  4994.7  241.28
  5005.4  242.32 5011.74245.3042  5027.2  251.08  5119.2  255.21  5147.6  257.12
  5161.8  256.97  5172.1  257.85    5197  259.83  5211.2  259.63  5267.5  262.72
#Mann= 4 ,-1 , 0
  4542.4     .15       0  4974.1     .09       0 5011.74     .15       0
  5172.1     .11       0
Bank Sta=4974.1,5011.74
XS Rating Curve= 0 ,0
Exp/Cntr=0.3,0.1

Type RM Length L Ch R = 1 ,11829   ,486,486,486
BEGIN DESCRIPTION:
SPRING BRANCH NO. 2 23.0
END DESCRIPTION:
XS GIS Cut Line= 3
      3757417.88     10113911.06      3756822.35     10114065.35
      3756517.82      10114361.1
#Sta/Elev= 30
  4384.8  263.75  4605.5  255.96  4681.6  250.72  4686.7  251.04  4705.1  250.02
  4803.4  247.97  4901.3  248.19  4911.7  247.56    4953  247.37  4965.7  246.79
 4979.21 242.718  4992.6  238.28  4996.1  238.28  4999.7  239.43  5007.1  239.98
  5014.3  241.61  5021.3  241.43 5026.17242.7287  5035.4     245  5042.6  247.82
  5056.7  248.77  5063.7  248.15    5085  249.49  5155.8   250.1  5254.8  252.61
  5275.9  253.72  5311.4   254.4  5346.7  256.86  5360.8   256.8  5424.5   259.4
#Mann= 3 , 0 , 0
  4384.8     .11       0 4979.21     .06       0 5026.17     .11       0
Bank Sta=4979.21,5026.17
XS Rating Curve= 0 ,0
Exp/Cntr=0.3,0.1

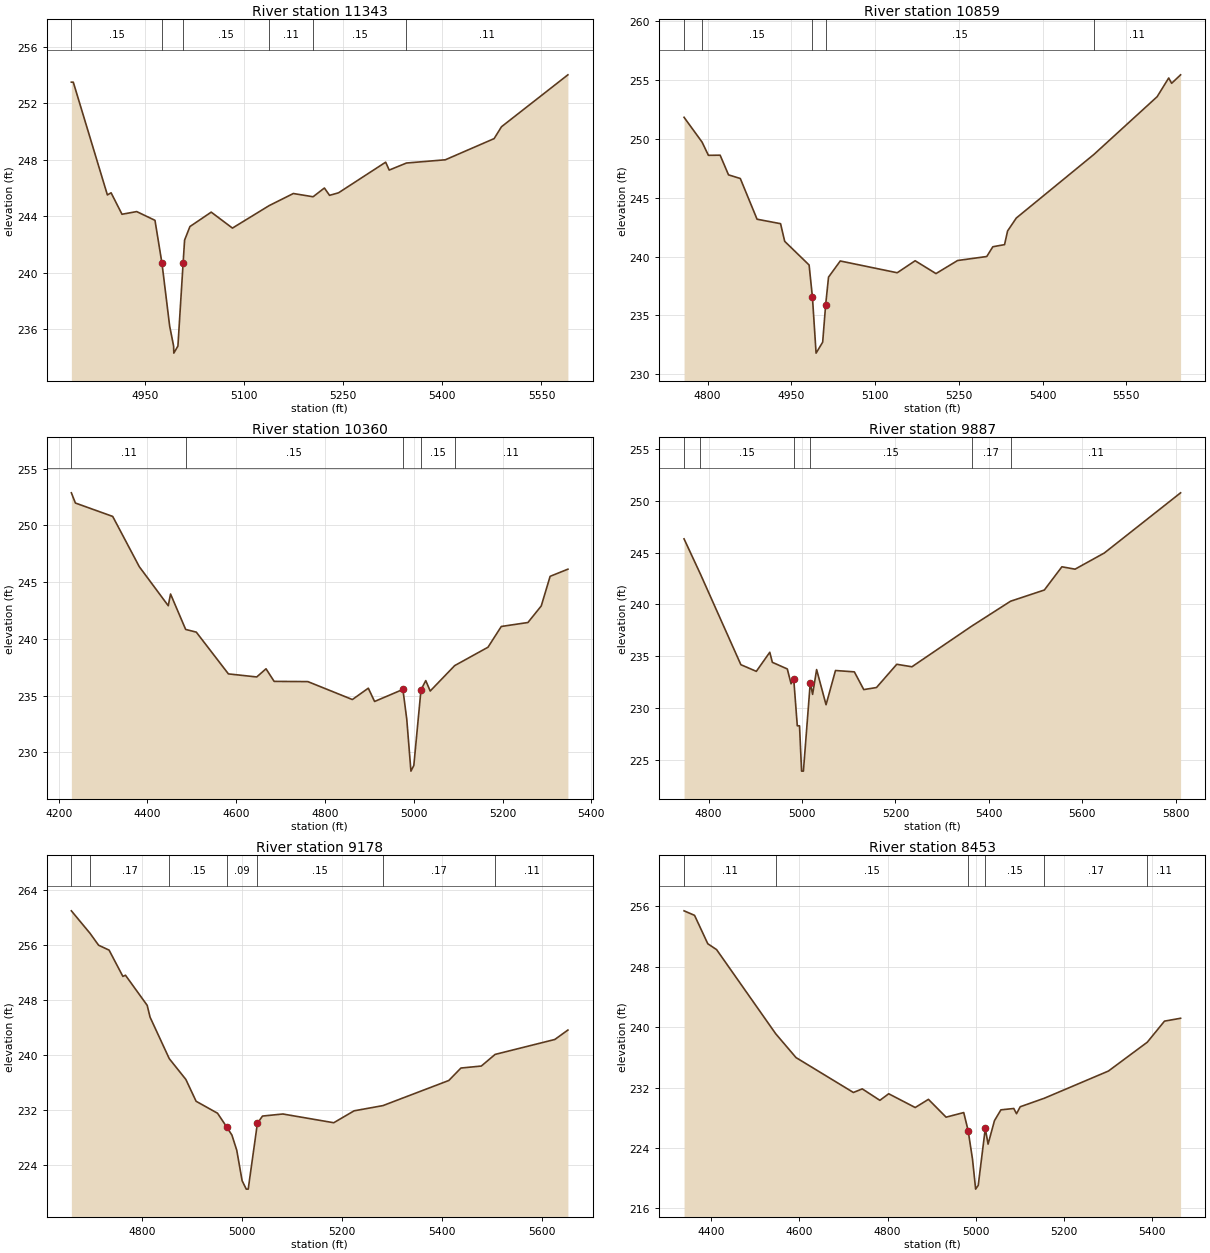
Type RM Length L Ch R = 1 ,11343   ,484,484,484
BEGIN DESCRIPTION:
SPRING BRANCH NO. 2 22.0
END DESCRIPTION:
XS GIS Cut Line= 3
      3756749.59     10113480.89      3756675.44     10113624.02
       3756465.3     10114175.33
#Sta/Elev= 30
  4838.8   253.5  4841.7   253.5  4893.3  245.51  4898.9  245.66  4915.4  244.14
  4937.6  244.33  4965.3  243.71 4975.91240.6556  4987.5  236.22  4993.5   234.8
  4993.8   234.3    5000   234.8 5007.88  240.69  5010.1  242.31  5018.2  243.27
  5050.4  244.29  5082.5  243.16  5138.3  244.76  5174.6  245.61  5204.5  245.38
  5221.6     246  5229.4  245.48    5243  245.66  5314.3  247.83  5319.7  247.27
  5345.7  247.77  5404.6     248  5478.4   249.5  5489.5  250.34    5590  254.02
#Mann= 6 ,-1 , 0
  4838.8     .15       0 4975.91     .09       0 5007.88     .15       0
  5138.3     .11       0  5204.5     .15       0  5345.7     .11       0
Bank Sta=4975.91,5007.88
XS Rating Curve= 0 ,0
Exp/Cntr=0.3,0.1

Type RM Length L Ch R = 1 ,10859   ,499,499,499
BEGIN DESCRIPTION:
SPRING BRANCH NO. 2 21.0
END DESCRIPTION:
XS GIS Cut Line= 3
      3756467.83     10113261.09      3756266.38     10113395.18
      3756067.85     10114011.07
#Sta/Elev= 30
    4758  251.84  4790.3  249.73  4801.6  248.61  4822.6  248.62  4837.6  246.95
  4858.7  246.64  4888.7  243.18  4930.8   242.8  4938.2   241.3  4981.9  239.29
  4987.9  236.54  4994.4   231.8  5006.2  232.73  5011.5  235.88  5016.7  238.26
  5037.7  239.63  5139.7  238.63  5171.8  239.65  5209.1  238.56  5247.8  239.67
    5300  240.01  5310.9  240.84  5331.9  241.02  5337.3  242.18  5352.9  243.28
  5491.8  248.68  5605.1  253.59  5625.8  255.18  5631.1  254.73  5647.1  255.45
#Mann= 5 ,-1 , 0
    4758     .11       0  4790.3     .15       0  4987.9     .09       0
  5011.5     .15       0  5491.8     .11       0
Bank Sta=4987.9,5011.5
XS Rating Curve= 0 ,0
Exp/Cntr=0.3,0.1

Type RM Length L Ch R = 1 ,10360   ,473,473,473
BEGIN DESCRIPTION:
SPRING BRANCH NO. 2 20.0
END DESCRIPTION:
XS GIS Cut Line= 4
      3756506.57     10113242.15      3755983.01     10113079.72
       3755857.5     10113264.19      3755867.85     10113611.04
#Sta/Elev= 30
  4228.7  252.87  4237.8  251.97  4321.8  250.79  4381.7  246.36  4446.9  242.92
  4452.1  243.95  4486.1  240.83  4510.1  240.59  4582.4  236.91  4646.2  236.64
  4667.1  237.36  4685.4  236.25  4761.3  236.23  4861.6  234.65  4897.5  235.65
  4911.6  234.48  4975.4  235.54  4984.1  232.92  4993.5  228.34    5000  228.84
 5016.15235.5075  5026.9  236.32  5036.9   235.4    5092  237.64    5167  239.26
    5197  241.09    5257  241.44    5287   242.9    5307  245.51    5347  246.14
#Mann= 5 ,-1 , 0
  4228.7     .11       0  4486.1     .15       0  4975.4     .09       0
 5016.15     .15       0    5092     .11       0
Bank Sta=4975.4,5016.15
XS Rating Curve= 0 ,0
Exp/Cntr=0.3,0.1

Type RM Length L Ch R = 1 ,9887    ,709,709,709
BEGIN DESCRIPTION:
SPRING BRANCH NO. 2 19.0
END DESCRIPTION:
XS GIS Cut Line= 4
      3755721.39     10112700.53      3755713.58     10112812.46
      3755656.29     10112934.85      3755541.48     10113742.79
#Sta/Elev= 30
  4747.3  246.32    4782  242.96    4869  234.19  4902.1  233.55  4930.9  235.39
  4936.4  234.42  4968.4  233.78  4976.5  232.35  4982.1  232.85  4989.8   228.3
  4994.6   228.3    4999  223.93  5002.9  223.93  5017.6  232.47  5022.6  231.33
  5031.2  233.72  5051.4  230.33  5071.6  233.63    5112   233.5  5132.2  231.79
  5159.4  231.99  5202.9  234.23  5235.3  233.99  5363.4  237.91  5446.6  240.31
  5518.9  241.39  5556.5  243.63  5584.7   243.4  5647.4  244.96  5810.7  250.76
#Mann= 6 ,-1 , 0
  4747.3     .17       0    4782     .15       0  4982.1     .09       0
  5017.6     .15       0  5363.4     .17       0  5446.6     .11       0
Bank Sta=4982.1,5017.6
XS Rating Curve= 0 ,0
Exp/Cntr=0.3,0.1

Type RM Length L Ch R = 1 ,9178    ,725,725,725
BEGIN DESCRIPTION:
SPRING BRANCH NO. 2 18.0
END DESCRIPTION:
XS GIS Cut Line= 3
      3755250.05     10112527.34      3755322.95     10112855.43
      3755447.95     10113501.25
#Sta/Elev= 30
  4658.6  260.98  4696.2  257.69  4713.1  255.98  4734.1  255.27  4761.7  251.45
  4766.9  251.62  4810.4  247.24  4816.1  245.53  4854.6  239.49  4887.8  236.47
  4908.3   233.3  4951.2  231.56  4969.7  229.55    4980  228.38  4989.7  226.17
  5000.4  221.75  5008.7  220.53  5012.6  220.53    5031   230.1  5041.2  231.15
  5081.9  231.45  5183.8  230.18  5224.5  231.91  5282.3  232.67  5414.1  236.32
  5438.4  238.13  5479.2  238.42  5506.8  240.11  5626.3  242.28  5652.5  243.65
#Mann= 7 ,-1 , 0
  4658.6     .11       0  4696.2     .17       0  4854.6     .15       0
  4969.7     .09       0    5031     .15       0  5282.3     .17       0
  5506.8     .11       0
Bank Sta=4969.7,5031
XS Rating Curve= 0 ,0
Exp/Cntr=0.3,0.1

Type RM Length L Ch R = 1 ,8453    ,616,616,616
BEGIN DESCRIPTION:
SPRING BRANCH NO. 2 16.0
END DESCRIPTION:
XS GIS Cut Line= 3
      3754921.91     10112527.27      3754942.75     10113193.97
      3755217.87      10113561.1
#Sta/Elev= 30
  4338.4  255.41  4362.2  254.81  4392.2  251.05  4412.2  250.27  4546.3  239.12
  4592.3  235.97  4722.4  231.35  4742.4  231.83  4782.4  230.31  4802.4  231.18
  4862.5  229.36  4892.5  230.44  4932.5  228.08  4972.5  228.69  4982.5  226.31
  4992.5  222.48  4999.5  218.55  5005.4  219.05  5021.4  226.59  5027.7  224.51
  5042.2  227.62  5056.8  229.05    5086  229.23  5092.2  228.54  5100.6  229.46
  5155.3  230.59  5300.6  234.19  5388.7  238.01  5427.7   240.8  5464.2  241.18
#Mann= 6 ,-1 , 0
  4338.4     .11       0  4546.3     .15       0  4982.5     .09       0
  5021.4     .15       0  5155.3     .17       0  5388.7     .11       0
Bank Sta=4982.5,5021.4
XS Rating Curve= 0 ,0
Exp/Cntr=0.3,0.1

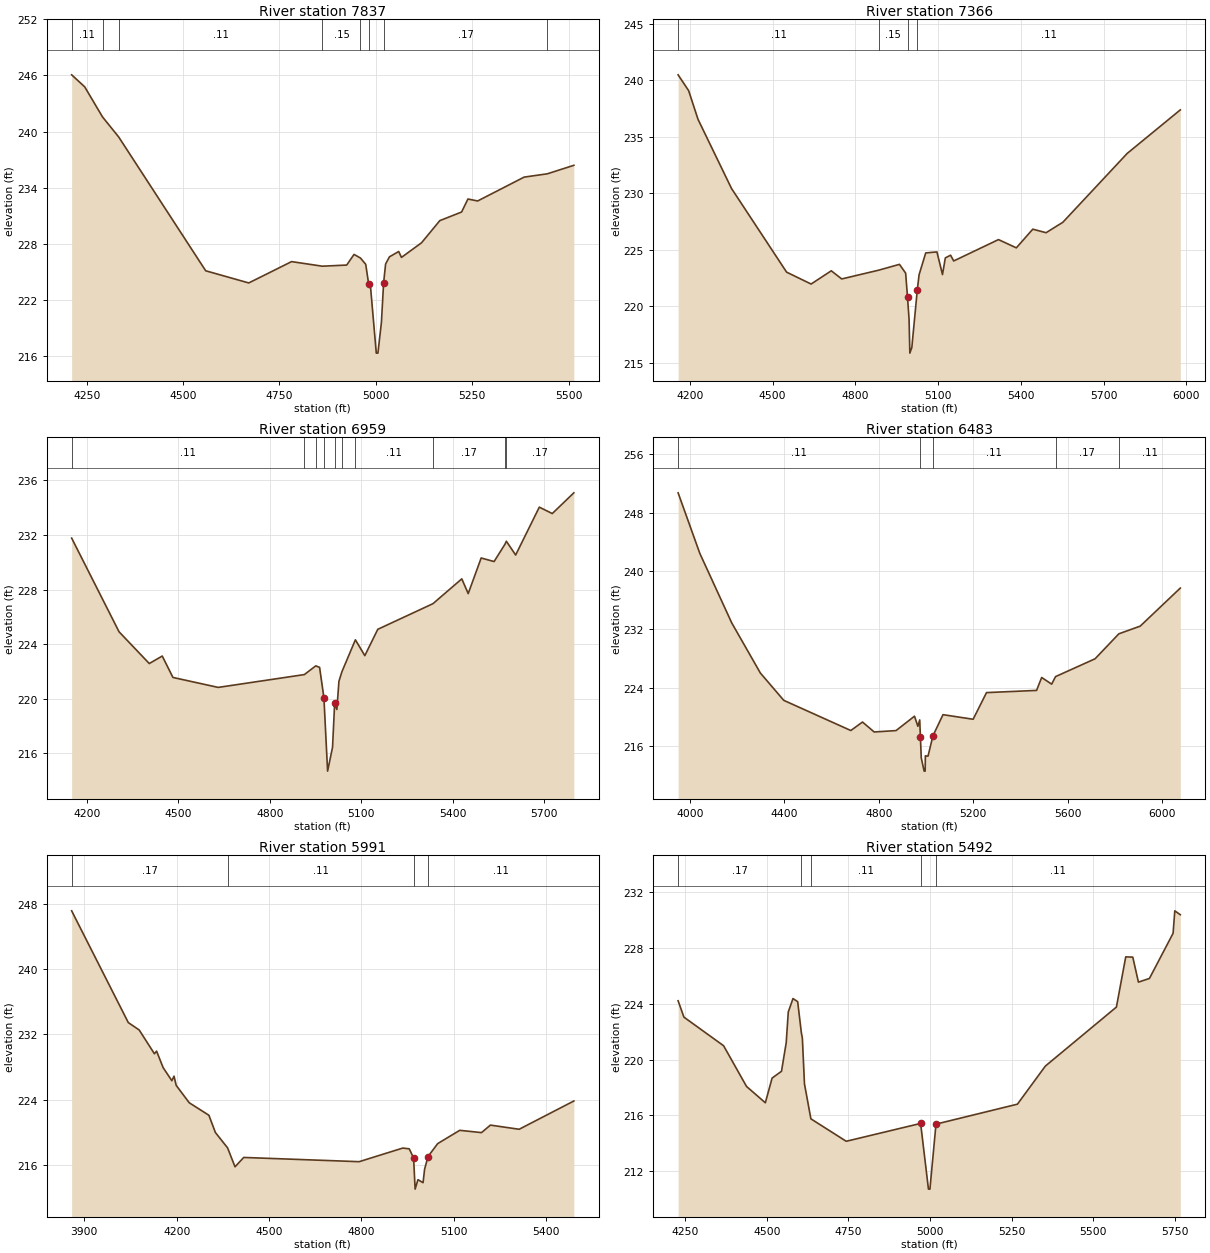
Type RM Length L Ch R = 1 ,7837    ,471,471,471
BEGIN DESCRIPTION:
SPRING BRANCH NO. 2 15.0
END DESCRIPTION:
XS GIS Cut Line= 3
      3754604.21     10112537.68       3754479.2     10113324.18
      3754617.85     10113811.05
#Sta/Elev= 30
  4211.1  246.07  4244.9  244.79  4291.2  241.57  4333.1  239.43  4558.8  225.13
  4670.5  223.83  4781.6  226.11  4861.3  225.62  4924.5  225.74  4943.6  226.88
  4960.3  226.49  4973.9  225.82  4981.6  223.69  4986.7  223.25  5001.3  216.33
  5005.5  216.33  5014.6  219.62  5020.3  223.85  5025.5  225.86  5035.4  226.62
  5059.4  227.19  5066.6  226.56  5118.6  228.12  5166.1  230.49  5222.6  231.41
    5239   232.8  5264.2  232.59  5384.8  235.14  5444.7  235.49  5513.7   236.4
#Mann= 8 ,-1 , 0
  4211.1     .11       0  4291.2     .17       0  4333.1     .11       0
  4861.3     .15       0  4960.3     .17       0  4981.6     .09       0
  5020.3     .17       0  5444.7     .11       0
Bank Sta=4981.6,5020.3
XS Rating Curve= 0 ,0
Exp/Cntr=0.3,0.1

Type RM Length L Ch R = 1 ,7366    ,407,407,407
BEGIN DESCRIPTION:
SPRING BRANCH NO. 2 14.0
END DESCRIPTION:
XS GIS Cut Line= 3
      3754442.74      10112516.9      3754058.42     10113266.86
      3753890.66     10114230.46
#Sta/Elev= 30
  4157.3  240.47  4195.5  239.07  4229.4  236.54  4350.9  230.42  4550.7  223.02
  4639.5  221.97  4712.6  223.14  4750.5  222.42  4885.3   223.2  4959.8  223.71
  4982.3  222.93  4989.1  220.78  4994.7  218.85  4997.5  215.86  5004.7  216.36
  5024.6  221.48    5031  222.79    5055  224.72  5095.7  224.81  5115.9  222.81
  5126.1  224.28  5145.2  224.52  5156.5  224.01  5318.9   225.9  5383.6  225.17
  5443.2  226.82  5491.5  226.51  5552.2  227.43  5785.6  233.52  5978.1  237.37
#Mann= 4 ,-1 , 0
  4157.3     .11       0  4885.3     .15       0  4989.1     .06       0
  5024.6     .11       0
Bank Sta=4989.1,5024.6
XS Rating Curve= 0 ,0
Exp/Cntr=0.3,0.1

Type RM Length L Ch R = 1 ,6959    ,476,476,476
BEGIN DESCRIPTION:
SPRING BRANCH NO. 2 13.0
END DESCRIPTION:
XS GIS Cut Line= 3
      3754267.82      10112561.1      3753691.01     10113185.97
      3753142.11     10113765.35
#Sta/Elev= 30
  4149.6  231.77  4305.2   224.9  4404.4  222.57    4447  223.12  4482.1  221.55
  4630.7  220.82  4913.5  221.76  4950.9   222.4  4963.5  222.29  4977.7  220.06
  4989.8  214.68    5006  216.43  5012.9  219.64  5020.2   219.2    5027  221.27
  5036.6  221.96    5081  224.31    5112  223.15  5154.5  225.08  5335.6  226.96
  5430.3  228.78  5451.4   227.7  5493.9  230.31  5536.3  230.05  5572.3  231.33
  5576.6  231.54  5607.1  230.53  5684.8  234.04  5727.3  233.57  5798.1  235.09
#Mann= 10 ,-1 , 0
  4149.6     .11       0  4913.5     .15       0  4950.9     .11       0
  4977.7     .06       0  5012.9     .11       0  5036.6     .15       0
    5081     .11       0  5335.6     .17       0  5572.3     .11       0
  5576.6     .17       0
Bank Sta=4977.7,5012.9
XS Rating Curve= 0 ,0
Exp/Cntr=0.3,0.1

Type RM Length L Ch R = 1 ,6483    ,492,492,492
BEGIN DESCRIPTION:
SPRING BRANCH NO. 2 12.0
END DESCRIPTION:
XS GIS Cut Line= 3
      3754117.82     10112011.11      3753449.04      10112820.3
      3752717.86     10113611.07
#Sta/Elev= 30
  3950.2  250.71    4042  242.43  4177.5  232.89  4298.6  226.04  4397.6   222.3
  4681.6  218.17  4731.1  219.33  4780.6  217.97  4873.1  218.16  4951.3  220.13
  4965.6  218.75  4973.4  219.62 4976.32217.2885  4979.9  214.43  4992.1  212.61
  4996.5  212.61  4997.3   214.7  5008.5  214.66  5029.5  217.45    5072  220.34
  5199.6  219.71  5256.3  223.36  5468.3  223.66  5489.9  225.43  5532.2  224.52
  5548.7  225.55  5716.1  227.99  5816.8  231.41  5907.2  232.46    6077  237.67
#Mann= 5 ,-1 , 0
  3950.2     .11       0 4976.32     .06       0  5029.5     .11       0
  5548.7     .17       0  5816.8     .11       0
Bank Sta=4976.32,5029.5
XS Rating Curve= 0 ,0
Exp/Cntr=0.3,0.1

Type RM Length L Ch R = 1 ,5991    ,499,499,499
BEGIN DESCRIPTION:
SPRING BRANCH NO. 2 11.0
END DESCRIPTION:
XS GIS Cut Line= 3
      3753867.88     10111711.04      3753066.83     10112523.43
      3752767.88     10112911.03
#Sta/Elev= 30
  3859.1  247.18    4043  233.46  4078.4  232.55  4127.8  229.63  4134.9  229.95
  4156.1  227.93  4184.4  226.32  4191.5  226.88  4198.5  225.75    4241  223.61
  4304.7  222.08  4325.8  219.96  4365.3  218.08  4389.5  215.75  4417.8   216.9
  4792.5  216.38    4934  218.05  4955.1  217.96  4969.3  216.84  4974.2  213.01
  4983.4  214.17    5000   213.8  5004.9  215.44 5016.12 217.014  5047.5   218.6
  5119.1  220.23  5189.7  219.95  5218.7  220.87    5312  220.36  5489.5  223.83
#Mann= 4 ,-1 , 0
  3859.1     .17       0  4365.3     .11       0  4969.3     .06       0
 5016.12     .11       0
Bank Sta=4969.3,5016.12
XS Rating Curve= 0 ,0
Exp/Cntr=0.3,0.1

Type RM Length L Ch R = 1 ,5492    ,498,498,498
BEGIN DESCRIPTION:
SPRING BRANCH NO. 2 10.0
END DESCRIPTION:
XS GIS Cut Line= 3
      3753162.93     10111620.93      3752679.72     10112223.52
      3752467.85     10112961.09
#Sta/Elev= 30
  4227.6  224.21  4245.4  223.04    4367  220.99  4437.4  218.07    4495   216.9
  4515.8  218.67  4544.6  219.16    4559   221.2  4565.4  223.41  4579.8  224.37
  4594.2  224.15  4605.5  221.92  4608.6  221.53    4615  218.26  4634.7  215.75
  4743.1  214.14  4971.2  215.42  4995.2  210.71  4999.7  210.71  5018.3  215.37
    5268   216.8  5353.6  219.53  5571.5  223.76  5600.1  227.36  5621.7  227.34
    5639  225.55  5672.7  225.81  5745.3  229.05  5750.5  230.66  5767.4  230.38
#Mann= 5 ,-1 , 0
  4227.6     .17       0  4605.5     .15       0  4634.7     .11       0
  4971.2     .06       0  5018.3     .11       0
Bank Sta=4971.2,5018.3
XS Rating Curve= 0 ,0
Exp/Cntr=0.3,0.1