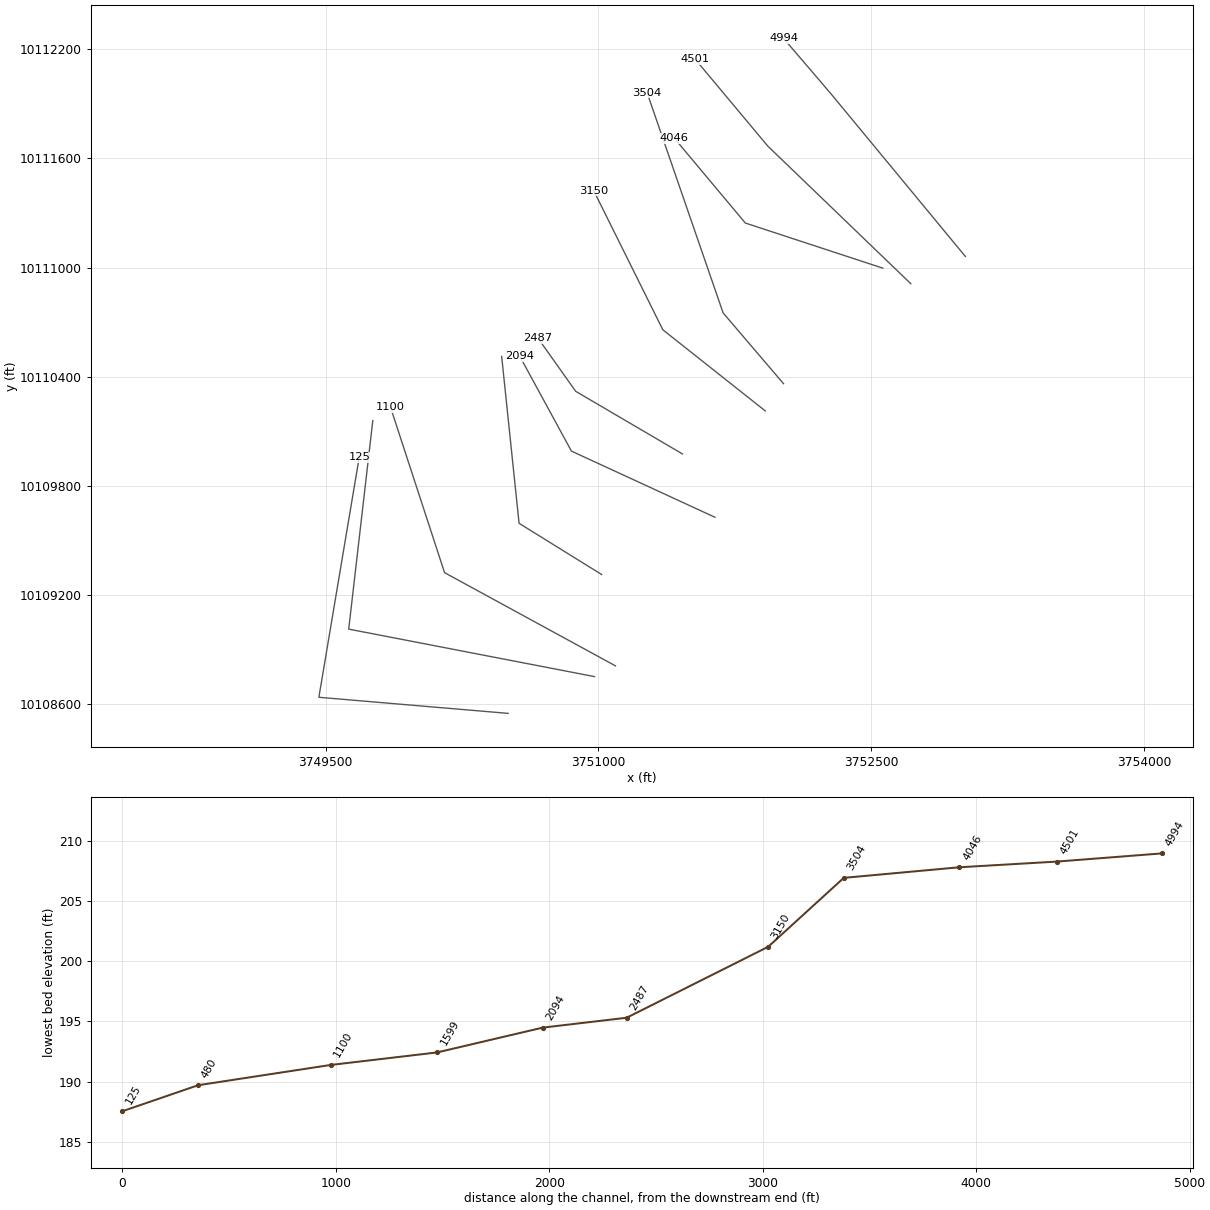
HEC-RAS study SPRING BRANCH NO 2.prj: SPRING BRANCH NO 2 Base Level Engineering

--- SPRING BRANCH NO 2.g01 (geometry) --- (continued)

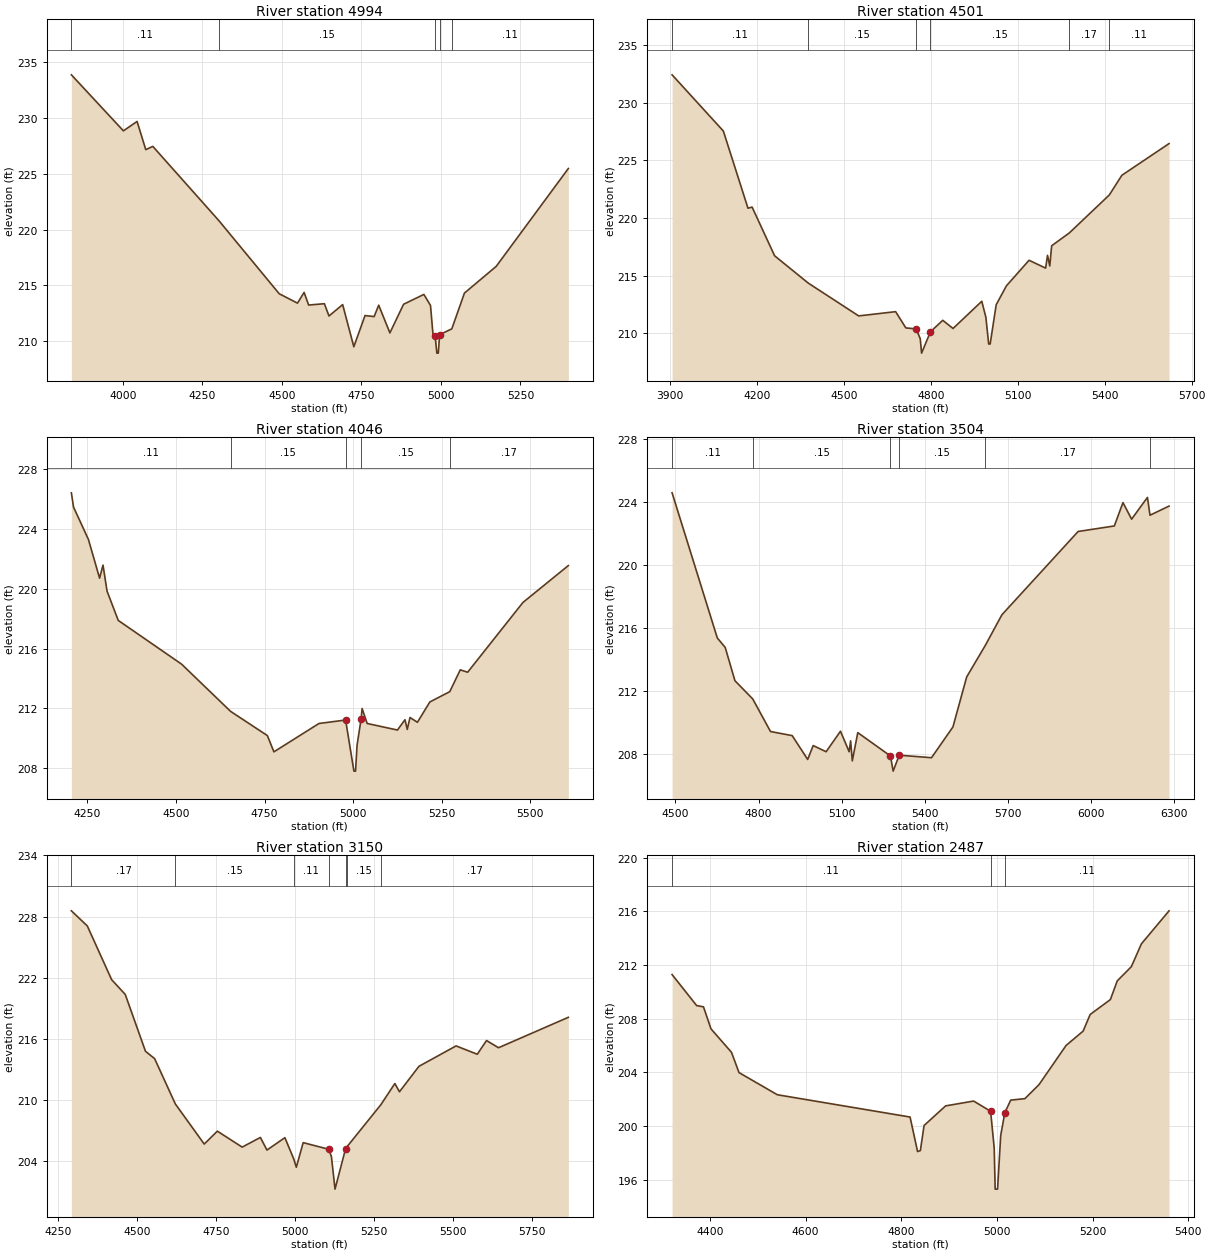
Type RM Length L Ch R = 1 ,4994    ,493,493,493
BEGIN DESCRIPTION:
SPRING BRANCH NO. 2 9.0
END DESCRIPTION:
XS GIS Cut Line= 3
      3753017.86     10111061.06       3752278.1     10111956.78
      3752017.85     10112261.07
#Sta/Elev= 30
  3838.3  233.84  4001.8  228.83  4044.8  229.67  4072.1  227.15  4094.3  227.44
  4301.3  220.82  4491.6  214.26    4549  213.42  4569.8  214.38  4584.1  213.25
  4633.6  213.37    4648  212.27    4691  213.29  4726.1  209.52  4761.3  212.31
    4790  212.22  4804.3  213.24  4839.5  210.76  4882.5  213.32  4946.3   214.2
  4967.1  213.22    4975  210.61  4981.5  210.52  4987.1  208.95  4991.6  208.95
  4995.8   210.6  5034.1  211.12  5073.8  214.32  5173.7  216.71  5400.4  225.46
#Mann= 5 ,-1 , 0
  3838.3     .11       0  4301.3     .15       0  4981.5     .09       0
  4995.8     .15       0  5034.1     .11       0
Bank Sta=4981.5,4995.8
XS Rating Curve= 0 ,0
Exp/Cntr=0.3,0.1

Type RM Length L Ch R = 1 ,4501    ,455,455,455
BEGIN DESCRIPTION:
SPRING BRANCH NO. 2 8.0
END DESCRIPTION:
XS GIS Cut Line= 3
      3752717.82      10110911.1      3751931.28     10111668.32
      3751532.49     10112145.66
#Sta/Elev= 30
  3908.2  232.43    4085  227.55  4169.9  220.85  4184.1  220.95  4261.8  216.72
  4377.8  214.35  4551.7   211.5  4679.1  211.87  4714.3  210.46  4749.8  210.37
    4764  209.52  4768.6  208.27  4799.2  210.12  4841.6  211.12  4877.1  210.41
  4976.2  212.77  4990.3  211.39    5000  209.06  5005.1  209.06  5025.9  212.47
  5061.1  214.11  5139.2  216.33  5196.4  215.65  5202.9  216.76  5210.7  215.84
  5217.2  217.59  5277.9   218.7    5416     222  5459.3  223.71    5622  226.46
#Mann= 6 ,-1 , 0
  3908.2     .11       0  4377.8     .15       0  4749.8     .09       0
  4799.2     .15       0  5277.9     .17       0    5416     .11       0
Bank Sta=4749.8,4799.2
XS Rating Curve= 0 ,0
Exp/Cntr=0.3,0.1

Type RM Length L Ch R = 1 ,4046    ,542,542,542
BEGIN DESCRIPTION:
SPRING BRANCH NO. 2 7.0
END DESCRIPTION:
XS GIS Cut Line= 3
      3752563.51     10110996.83       3751807.9     10111244.93
      3751417.86     10111711.07
#Sta/Elev= 30
  4204.7  226.43  4210.7  225.48  4252.8  223.31  4284.3  220.72    4294  221.59
  4305.4  219.85    4337  217.89  4515.9  214.96  4654.2   211.8    4758  210.18
  4776.5  209.09  4903.8  210.99    4979  211.22  5002.4   207.8    5007   207.8
  5011.2  209.52  5022.9 211.318  5025.5  211.99  5039.8  210.99  5125.4  210.55
  5146.5  211.24    5153  210.59  5160.8  211.39  5181.7  211.07  5216.8  212.43
    5273  213.12  5302.7  214.58  5323.5  214.42  5479.6  219.09  5607.8  221.56
#Mann= 5 ,-1 , 0
  4204.7     .11       0  4654.2     .15       0    4979     .09       0
  5022.9     .15       0    5273     .17       0
Bank Sta=4979,5022.9
XS Rating Curve= 0 ,0
Exp/Cntr=0.3,0.1

Type RM Length L Ch R = 1 ,3504    ,354,354,354
BEGIN DESCRIPTION:
SPRING BRANCH NO. 2 6.0
END DESCRIPTION:
XS GIS Cut Line= 3
      3752017.87     10110361.06      3751685.72     10110750.31
      3751267.87     10111961.03
#Sta/Elev= 30
  4488.3  224.56  4651.4  215.36  4679.9  214.76    4715  212.65  4779.4  211.49
  4843.3  209.43  4921.5  209.17  4977.4  207.66  4997.2  208.54  5043.9  208.15
  5095.7  209.45  5126.9  208.15  5132.2  208.84  5138.3  207.57  5158.1  209.36
  5275.9  207.88  5285.7  206.92  5307.6  207.93    5424  207.77  5501.3  209.72
  5550.9  212.89  5618.1  214.89  5677.9  216.83  5952.9  222.11  6083.4  222.46
  6114.6  223.94  6145.8  222.89  6202.9  224.27  6212.1  223.14  6280.8  223.72
#Mann= 6 ,-1 , 0
  4488.3     .11       0  4779.4     .15       0  5275.9     .09       0
  5307.6     .15       0  5618.1     .17       0  6212.1     .11       0
Bank Sta=5275.9,5307.6
XS Rating Curve= 0 ,0
Exp/Cntr=0.3,0.1

Type RM Length L Ch R = 1 ,3150    ,663,663,663
BEGIN DESCRIPTION:
SPRING BRANCH NO. 2 5.0
END DESCRIPTION:
XS GIS Cut Line= 3
      3751917.83     10110211.09       3751354.2     10110657.51
      3750974.01     10111423.11
#Sta/Elev= 30
  4290.9  228.56  4341.4  227.07  4418.4  221.79  4461.5  220.34  4525.6  214.75
  4554.5  214.03  4620.2  209.57  4711.6  205.63  4753.2   206.9  4831.7  205.33
  4889.4  206.28  4910.3  205.04    4967  206.26  4995.1  204.17  5003.2  203.35
    5025  205.77  5105.8  205.12  5114.4   204.4  5125.8   201.2    5159  205.14
  5162.8  205.33  5270.5  209.48  5315.3  211.58  5329.9  210.77  5391.5  213.27
  5509.1  215.28  5576.4  214.46  5605.6  215.81  5643.6   215.1  5864.7  218.09
#Mann= 7 ,-1 , 0
  4290.9     .17       0  4620.2     .15       0  4995.1     .11       0
  5105.8     .06       0    5159     .11       0  5162.8     .15       0
  5270.5     .17       0
Bank Sta=5105.8,5159
XS Rating Curve= 0 ,0
Exp/Cntr=0.3,0.1

Type RM Length L Ch R = 1 ,2487    ,393,393,393
BEGIN DESCRIPTION:
SPRING BRANCH NO. 2 4.0
END DESCRIPTION:
XS GIS Cut Line= 3
      3751462.22     10109974.51      3750875.04     10110318.97
      3750667.84     10110611.08
#Sta/Elev= 30
  4321.1  211.29  4372.5  208.98  4386.7  208.89  4402.4  207.25  4445.3   205.5
    4461  203.99  4541.1  202.34  4818.6  200.68  4834.3  198.11  4840.1  198.18
  4847.9  200.05  4892.9  201.51  4951.5  201.87    4987  201.11  4994.5  198.37
  4996.5  195.31  5001.5  195.31  5008.1  199.31  5016.7     201    5029  201.94
  5058.6  202.05  5088.1  203.09  5144.7  206.01  5180.4  207.08  5195.1  208.32
  5237.4  209.43  5251.7  210.82  5281.2  211.88  5302.2  213.58    5360  216.04
#Mann= 3 , 0 , 0
  4321.1     .11       0    4987     .06       0  5016.7     .11       0
Bank Sta=4987,5016.7
XS Rating Curve= 0 ,0
Exp/Cntr=0.3,0.1

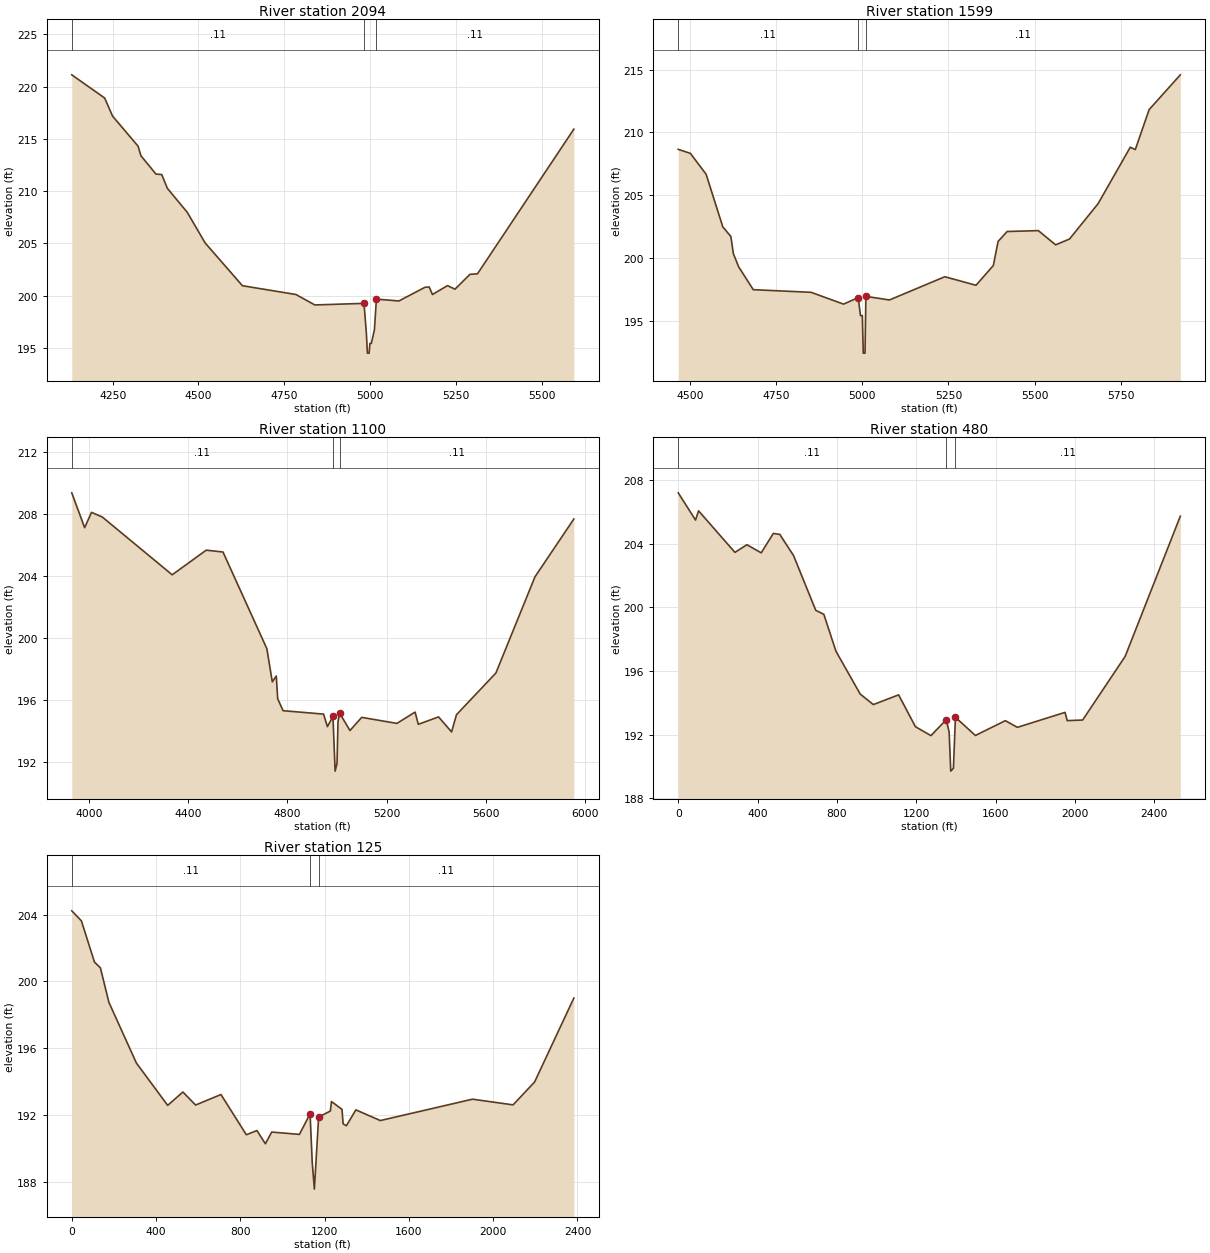
Type RM Length L Ch R = 1 ,2094    ,495,495,495
BEGIN DESCRIPTION:
SPRING BRANCH NO. 2 3.0
END DESCRIPTION:
XS GIS Cut Line= 3
      3751640.62     10109626.28      3750851.48     10109990.17
      3750567.86     10110511.06
#Sta/Elev= 30
    4131  221.12  4226.8   218.9  4249.8  217.17  4324.2  214.29  4332.3  213.38
  4376.3  211.62    4393  211.58  4409.4  210.26  4467.4  207.96  4519.5  205.03
    4628  200.94  4783.8   200.1  4838.8   199.1    4982  199.25  4988.9  196.41
  4991.9  194.49  4996.9  194.49  4999.2  195.42  5003.4  195.42  5012.4  196.73
  5018.1  199.66  5083.6  199.48  5159.6  200.79  5171.8  200.82  5181.4   200.1
  5225.1  200.95    5247  200.61  5290.6  202.03  5312.5  202.08  5593.1  215.92
#Mann= 3 , 0 , 0
    4131     .11       0    4982     .06       0  5018.1     .11       0
Bank Sta=4982,5018.1
XS Rating Curve= 0 ,0
Exp/Cntr=0.3,0.1

Type RM Length L Ch R = 1 ,1599    ,499,499,499
BEGIN DESCRIPTION:
SPRING BRANCH NO. 2 2.0
END DESCRIPTION:
XS GIS Cut Line= 3
      3751017.82     10109311.09      3750563.61     10109592.86
      3750467.85     10110511.08
#Sta/Elev= 30
  4465.5  208.65  4500.8  208.33  4546.4  206.67  4594.9  202.48  4618.4  201.71
  4625.5  200.35  4640.9   199.3  4683.4  197.48  4851.1  197.27  4945.6  196.33
  4988.1  196.85  4994.6  195.42    5000  195.42  5002.7  192.43  5007.8  192.43
  5010.3  196.95  5078.6  196.66  5239.5  198.51    5330  197.83  5380.3   199.4
  5394.2  201.32  5420.5  202.11    5511  202.18  5561.2  201.05  5601.5  201.51
  5684.6  204.33    5778  208.82  5792.5  208.63  5832.7  211.81  5923.2  214.58
#Mann= 3 , 0 , 0
  4465.5     .11       0  4988.1     .06       0  5010.3     .11       0
Bank Sta=4988.1,5010.3
XS Rating Curve= 0 ,0
Exp/Cntr=0.3,0.1

Type RM Length L Ch R = 1 ,1100    ,620,620,620
BEGIN DESCRIPTION:
SPRING BRANCH NO. 2 1.0
END DESCRIPTION:
XS GIS Cut Line= 3
      3751093.77     10108808.56      3750153.78     10109321.42
        3749857.     10110230.19
#Sta/Elev= 30
  3929.2  209.35  3981.2   207.1  4008.8  208.09  4052.4  207.79  4334.6  204.06
    4472  205.65  4539.7  205.53  4716.8  199.29  4738.7  197.15  4754.8  197.53
  4760.5  196.06  4782.3  195.29  4945.6  195.07  4961.2  194.26  4983.6  194.92
  4992.3  191.39    5000  191.89  5003.9  194.58  5010.2  195.14  5052.2  194.01
  5099.6  194.86  5241.6  194.47  5315.2   195.2  5328.1  194.41  5409.9  194.89
  5462.5  193.92  5482.2  195.03  5641.3  197.72  5799.1  203.93    5956  207.66
#Mann= 3 , 0 , 0
  3929.2     .11       0  4983.6     .06       0  5010.2     .11       0
Bank Sta=4983.6,5010.2
XS Rating Curve= 0 ,0
Exp/Cntr=0.3,0.1

Type RM Length L Ch R = 1 ,480     ,355,355,355
BEGIN DESCRIPTION:
SPRING BRANCH NO. 2 0.5
END DESCRIPTION:
XS GIS Cut Line= 3
      3750978.45     10108749.52      3749626.67     10109010.79
       3749759.2     10110158.09
#Sta/Elev= 30
       0  207.19    87.2  205.48   102.5  206.06   285.8  203.45   346.3  203.93
   418.2  203.42   479.3  204.64   511.9  204.58   581.2  203.25   693.2  199.81
   733.9  199.56     795  197.24   917.3  194.55   983.3  193.89  1110.8   194.5
  1195.6   192.5  1273.7  191.94    1351  192.94  1365.4  192.16  1373.6  189.71
  1387.1  189.89  1397.2  193.09  1497.9  191.95  1648.9  192.88  1709.3  192.46
  1949.7   193.4  1960.9  192.88  2038.5  192.92  2252.9  196.92  2530.7  205.72
#Mann= 3 , 0 , 0
       0     .11       0    1351     .06       0  1397.2     .11       0
Bank Sta=1351,1397.2
XS Rating Curve= 0 ,0
Exp/Cntr=0.3,0.1

Type RM Length L Ch R = 1 ,125     ,0,0,0
BEGIN DESCRIPTION:
SPRING BRANCH NO. 2 0.1
END DESCRIPTION:
XS GIS Cut Line= 3
      3750503.35     10108547.22      3749462.61     10108635.79
      3749684.46     10109955.51
#Sta/Elev= 30
       0  204.23    45.7  203.63   107.7  201.16     136  200.81   176.1  198.75
   306.6  195.11   455.2  192.57   527.4  193.37   587.6  192.59     708  193.22
   828.5  190.81   878.7  191.06   918.8  190.27   948.9  190.97  1080.3  190.83
    1131  192.06  1141.1  189.17  1151.3  187.55  1171.6  191.87  1227.1  192.23
  1232.4   192.8  1282.6  192.33  1287.7  191.46  1303.4  191.35  1348.3   192.3
  1464.4  191.66  1901.6  192.94  2094.3   192.6  2196.4  193.97  2382.7     199
#Mann= 3 , 0 , 0
       0     .11       0    1131     .06       0  1171.6     .11       0
Bank Sta=1131,1171.6
XS Rating Curve= 0 ,0
Exp/Cntr=0.3,0.1

Chan Stop Cuts=-1
Use User Specified Reach Order=0
Composite Channel Slope=5