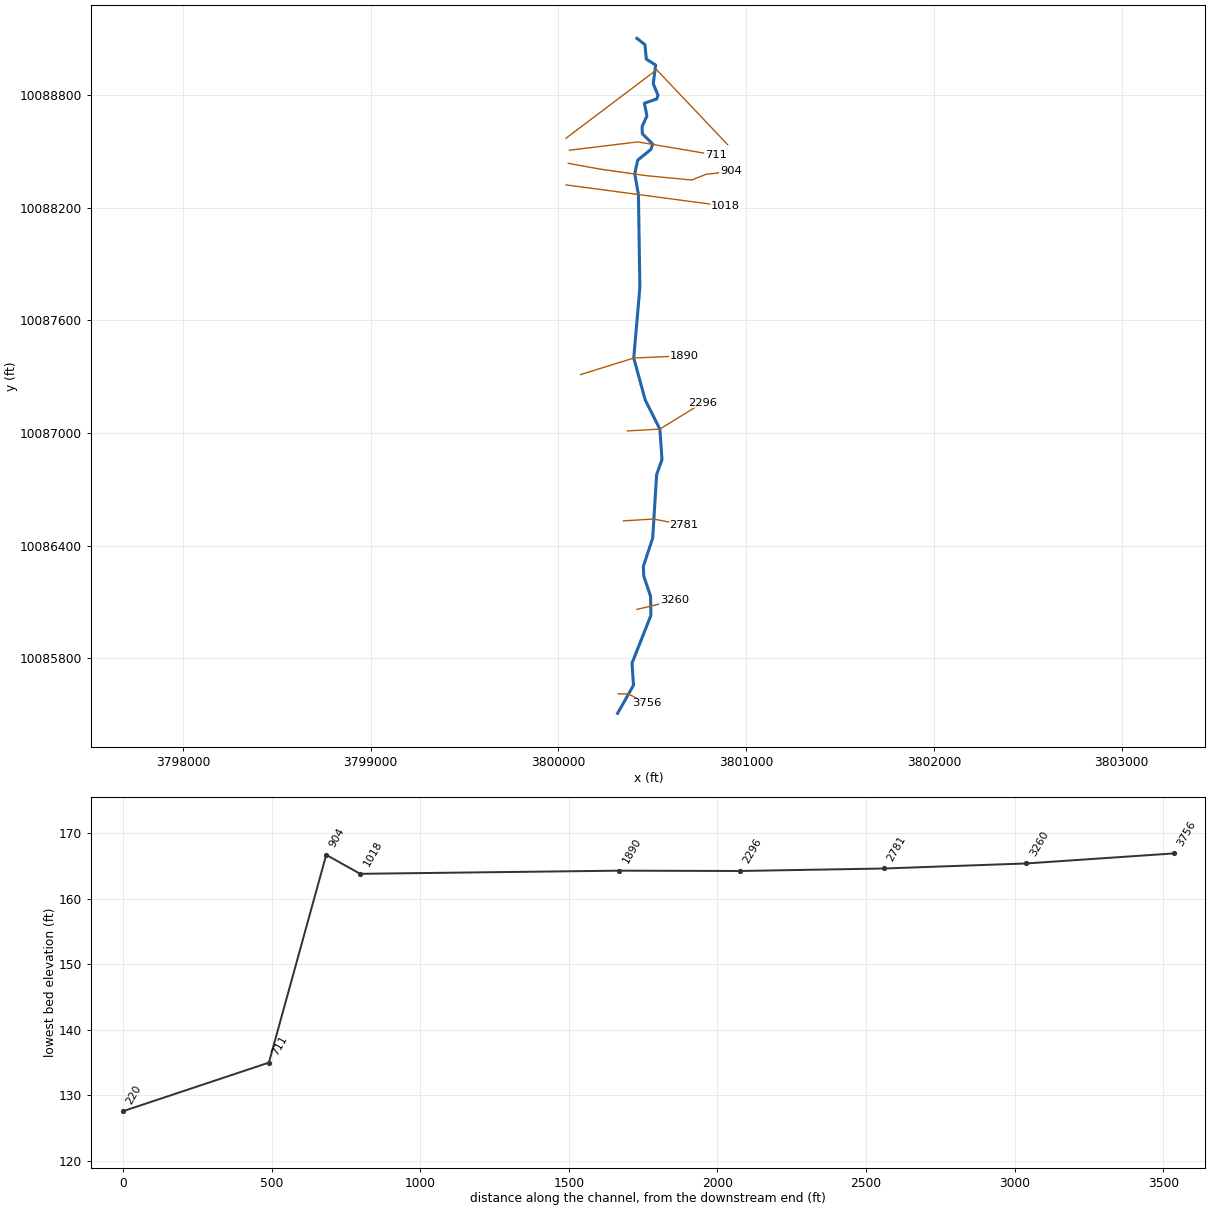
--- STOWE BRANCH.prj (project) ---

Proj Title=STOWE BRANCH Base Level Engineering
Current Plan=p01
Default Exp/Contr=0.3,0.1
English Units
Geom File=g01
Flow File=f01
Plan File=p01
Y Axis Title=Elevation
X Axis Title(PF)=Main Channel Distance
X Axis Title(XS)=Station
BEGIN DESCRIPTION:
STOWE BRANCH
END DESCRIPTION:
DSS Export Rating Curves= 0
DSS Export Rating Curve Sorted= 0
DSS Export Volume Flow Curves= 0
DXF OffsetX= 0
DXF OffsetY= 0
DXF ScaleX= 1
DXF ScaleY= 10

--- STOWE BRANCH.p01 (plan) ---

Plan Title=Multiple Run
Short Identifier=Multiple
Geom File=g01
Flow File=f01
Subcritical Flow
K Sum by GR= 0
Std Step Tol= 0.01
Critical Tol= 0.01
Num of Std Step Trials= 20
Max Error Tol= 0.3
Flow Tol Ratio= 0.001
Split Flow NTrial= 30
Split Flow Tol= 0.02
Split Flow Ratio= 0.02
Log Output Level= 0
Friction Slope Method= 1
Unsteady Friction Slope Method= 2
Unsteady Bridges Friction Slope Method= 1
Parabolic Critical Depth
Global Vel Dist=  1 , 1 , 1
Global Log Level= 0
CheckData=True
Encroach Param= -1, 0, 0, 0
BEGIN DESCRIPTION:
Multiple Run
END DESCRIPTION:

--- STOWE BRANCH.f01 (steady flow) ---

Flow Title=Multiple
Program Version=4.10
Number of Profiles= 7
Profile Names=10-year,25-year,50-year,1pct_min,100-year,1pct_plu,500-year
River Rch & RM=STOWE BRANCH,Reach-1         ,3756
     498     657     873     381    1152    3479    2073
River Rch & RM=STOWE BRANCH,Reach-1         ,711
     462     604     797     346    1045    3156    1854
Boundary for River Rch & Prof#=STOWE BRANCH,Reach-1         , 1
Up Type= 0
Dn Type= 3
Dn Slope=0.005
Boundary for River Rch & Prof#=STOWE BRANCH,Reach-1         , 2
Up Type= 0
Dn Type= 3
Dn Slope=0.005
Boundary for River Rch & Prof#=STOWE BRANCH,Reach-1         , 3
Up Type= 0
Dn Type= 3
Dn Slope=0.005
Boundary for River Rch & Prof#=STOWE BRANCH,Reach-1         , 4
Up Type= 0
Dn Type= 3
Dn Slope=0.005
Boundary for River Rch & Prof#=STOWE BRANCH,Reach-1         , 5
Up Type= 0
Dn Type= 3
Dn Slope=0.005
Boundary for River Rch & Prof#=STOWE BRANCH,Reach-1         , 6
Up Type= 0
Dn Type= 3
Dn Slope=0.005
Boundary for River Rch & Prof#=STOWE BRANCH,Reach-1         , 7
Up Type= 0
Dn Type= 3
Dn Slope=0.005
DSS Import GetInterval= 0
DSS Import GetPeak= 0
DSS Import FillOption= 0

--- STOWE BRANCH.g01 (geometry) ---

Geom Title=Existing Conditions
Program Version=4.10

River Reach=STOWE BRANCH    ,Reach-1
Reach XY= 30
       3800315.2     10085507.08       3800399.9     10085657.17
      3800392.06     10085774.61      3800492.58     10086028.73
      3800490.67     10086131.76      3800454.42     10086238.61
      3800452.51     10086290.13      3800502.12     10086440.86
      3800523.11     10086778.57      3800551.73     10086858.71
      3800540.28     10087020.89      3800462.06     10087176.85
       3800401.3     10087399.29      3800433.85     10087775.81
      3800426.25     10088269.51      3800406.61     10088379.87
      3800422.24     10088453.06      3800492.42      10088510.1
      3800502.37     10088538.54       3800446.9     10088594.02
      3800445.86     10088632.24      3800471.52     10088688.51
      3800457.92     10088756.15      3800523.79     10088779.23
      3800530.31     10088798.98      3800505.03     10088859.83
      3800518.02     10088959.57      3800468.24     10088990.86
      3800461.13     10089067.67      3800418.23     10089101.77

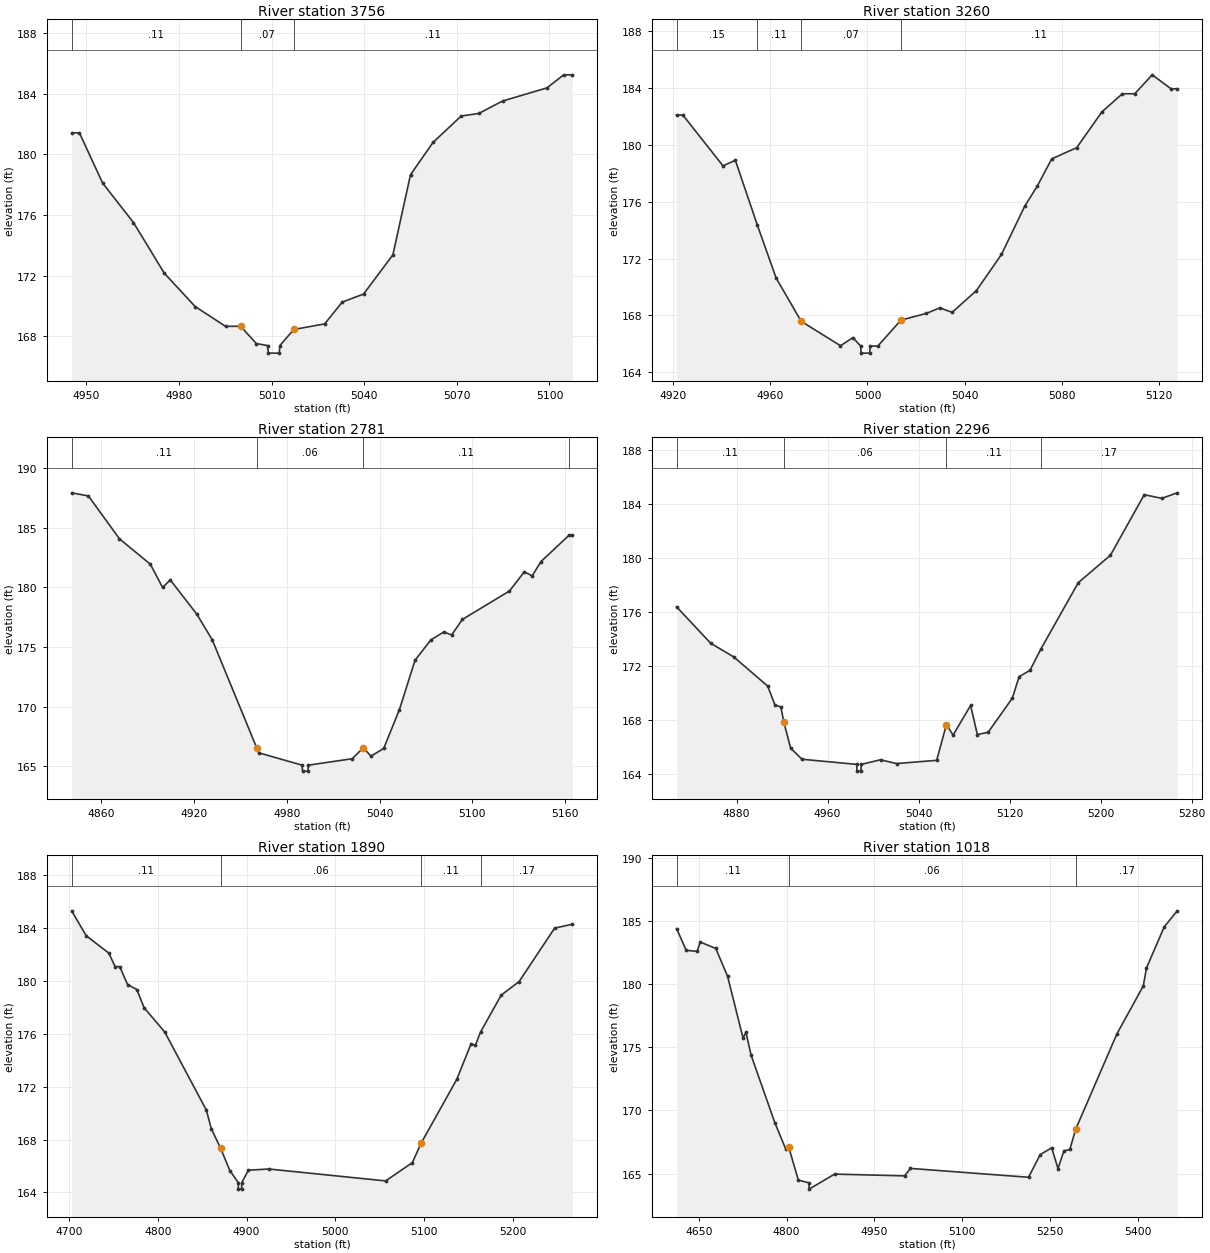
Type RM Length L Ch R = 1 ,3756    ,496,496,496
BEGIN DESCRIPTION:
STOWE BRANCH 6.0
END DESCRIPTION:
XS GIS Cut Line= 3
      3800317.89     10085611.07      3800372.59     10085610.65
      3800467.86     10085561.07
#Sta/Elev= 26
  4945.3  181.42  4947.8  181.42  4955.3  178.11  4965.3   175.5  4975.3  172.15
  4985.3  169.95  4995.1  168.65    5000  168.65  5005.1  167.51  5008.7  167.38
    5009  166.88  5012.5  166.88  5012.7  167.38  5017.2  168.44  5027.2  168.81
  5032.9  170.25  5039.8  170.78  5049.3  173.37    5055  178.66  5062.3  180.79
  5071.4  182.53  5077.1   182.7  5084.8  183.52  5099.2  184.39  5104.6  185.25
  5107.4  185.25
#Mann= 3 ,-1 , 0
  4945.3     .11       0    5000     .07       0  5017.2     .11       0
Bank Sta=5000,5017.2
XS Rating Curve= 0 ,0
Exp/Cntr=0.3,0.1

Type RM Length L Ch R = 1 ,3260    ,479,479,479
BEGIN DESCRIPTION:
STOWE BRANCH 5.0
END DESCRIPTION:
XS GIS Cut Line= 3
      3800417.81     10086061.06      3800494.49     10086078.34
      3800617.82     10086111.06
#Sta/Elev= 30
  4921.4  182.09    4924  182.09  4940.5  178.52  4945.6  178.91  4954.6  174.38
  4962.4  170.63  4972.7  167.59  4988.9  165.87    4994  166.44  4997.2  165.85
  4997.4  165.35  5000.9  165.35  5001.2  165.85  5004.3  165.85  5013.8  167.67
  5024.2  168.14  5029.8  168.53  5034.9  168.22  5044.9  169.75  5055.2  172.29
  5064.8  175.69  5069.9  177.08  5075.9  179.01  5086.2   179.8  5096.6  182.32
    5105  183.59  5110.1  183.59  5117.3  184.92    5125  183.94  5127.6  183.94
#Mann= 4 ,-1 , 0
  4921.4     .15       0  4954.6     .11       0  4972.7     .07       0
  5013.8     .11       0
Bank Sta=4972.7,5013.8
XS Rating Curve= 0 ,0
Exp/Cntr=0.3,0.1

Type RM Length L Ch R = 1 ,2781    ,485,485,485
BEGIN DESCRIPTION:
STOWE BRANCH 4.0
END DESCRIPTION:
XS GIS Cut Line= 3
      3800347.03     10086532.34      3800505.94     10086541.98
      3800667.81     10086511.08
#Sta/Elev= 30
  4840.8  187.94  4851.6  187.68  4871.7  184.08  4891.7  181.95  4899.6     180
  4904.6  180.63  4921.8  177.75  4931.8  175.59  4960.7166.4818  4961.8  166.12
  4989.9  165.08  4990.2  164.58  4993.7  164.58  4993.9  165.08  5022.3  165.62
  5029.5  166.54  5034.5  165.84  5042.7  166.48  5052.9  169.75    5063  173.89
  5073.2  175.59  5081.6  176.26  5086.7  176.01  5093.6  177.31  5124.1   179.7
  5133.7  181.31  5138.8  180.97  5144.5  182.17  5162.9  184.41  5164.8  184.41
#Mann= 4 ,-1 , 0
  4840.8     .11       0  4960.7     .06       0  5029.5     .11       0
  5162.9     .17       0
Bank Sta=4960.7,5029.5
XS Rating Curve= 0 ,0
Exp/Cntr=0.3,0.1

Type RM Length L Ch R = 1 ,2296    ,406,406,406
BEGIN DESCRIPTION:
STOWE BRANCH 3.0
END DESCRIPTION:
XS GIS Cut Line= 3
      3800367.86     10087011.07      3800540.28     10087020.89
      3800767.86     10087161.08
#Sta/Elev= 30
  4827.3  176.37  4857.3  173.67  4877.4  172.67  4907.4   170.5  4913.8  169.08
  4918.9  168.96 4921.51  167.84  4927.5  165.91  4937.5  165.08  4985.6   164.7
  4985.8   164.2  4989.3   164.2  4989.6   164.7  5006.5  165.04  5020.6  164.76
  5055.9     165  5064.4  167.65  5070.3  166.87  5085.7  169.07  5091.6  166.91
  5101.1  167.08  5122.4  169.61  5128.3   171.2  5137.8  171.66  5147.4  173.24
  5180.3  178.16  5208.6   180.2  5238.3  184.68  5253.7  184.41  5267.3  184.82
#Mann= 4 ,-1 , 0
  4827.3     .11       0 4921.51     .06       0  5064.4     .11       0
  5147.4     .17       0
Bank Sta=4921.51,5064.4
XS Rating Curve= 0 ,0
Exp/Cntr=0.3,0.1

Type RM Length L Ch R = 1 ,1890    ,872,872,872
BEGIN DESCRIPTION:
STOWE BRANCH 2.0
END DESCRIPTION:
XS GIS Cut Line= 3
      3800117.81     10087311.06       3800401.3     10087399.29
      3800667.84     10087411.07
#Sta/Elev= 30
  4703.1  185.28  4719.4   183.4    4745  182.08  4751.9  181.07  4757.2  181.06
    4766  179.71  4776.5  179.33  4784.5  177.97  4807.9  176.12  4854.8  170.21
  4860.2  168.83  4870.7  167.35  4881.2  165.65  4890.6  164.75  4890.8  164.25
  4894.3  164.25  4894.6  164.75  4902.1  165.68  4925.1  165.77  5056.6  164.87
  5086.6  166.25  5096.6  167.73  5136.7  172.55  5152.6  175.21  5157.7  175.13
  5163.4  176.12  5186.7  178.91  5206.8  179.93  5246.8  183.97  5266.8  184.27
#Mann= 4 ,-1 , 0
  4703.1     .11       0  4870.7     .06       0  5096.6     .11       0
  5163.4     .17       0
Bank Sta=4870.7,5096.6
XS Rating Curve= 0 ,0
Exp/Cntr=0.3,0.1

Type RM Length L Ch R = 1 ,1018    ,114,114,114
BEGIN DESCRIPTION:
Mapping XS 21cdf204
END DESCRIPTION:
XS GIS Cut Line= 2
      3800041.45     10088321.19      3800889.98     10088208.34
#Sta/Elev= 30
  4611.9   184.4  4628.4  182.68  4647.1   182.6  4652.2  183.34  4678.9  182.83
  4699.1  180.62  4725.4  175.75  4730.5  176.18  4739.4  174.36  4779.8  169.04
  4798.6  166.93  4803.7  167.08  4820.1  164.48  4838.3  164.27  4838.5  163.77
    4882  164.96  5001.7  164.82  5011.8  165.41  5213.6  164.71  5233.7  166.51
  5253.2  167.04    5264   165.4  5274.1   166.8  5284.2  166.91  5294.3  168.52
  5364.9  176.08  5409.8  179.86  5415.3  181.28  5445.6  184.54  5467.9  185.81
#Mann= 3 , 0 , 0
  4611.9     .11       0  4803.7     .06       0  5294.3     .17       0
Bank Sta=4803.7,5294.3
XS Rating Curve= 0 ,0
Exp/Cntr=0.3,0.1

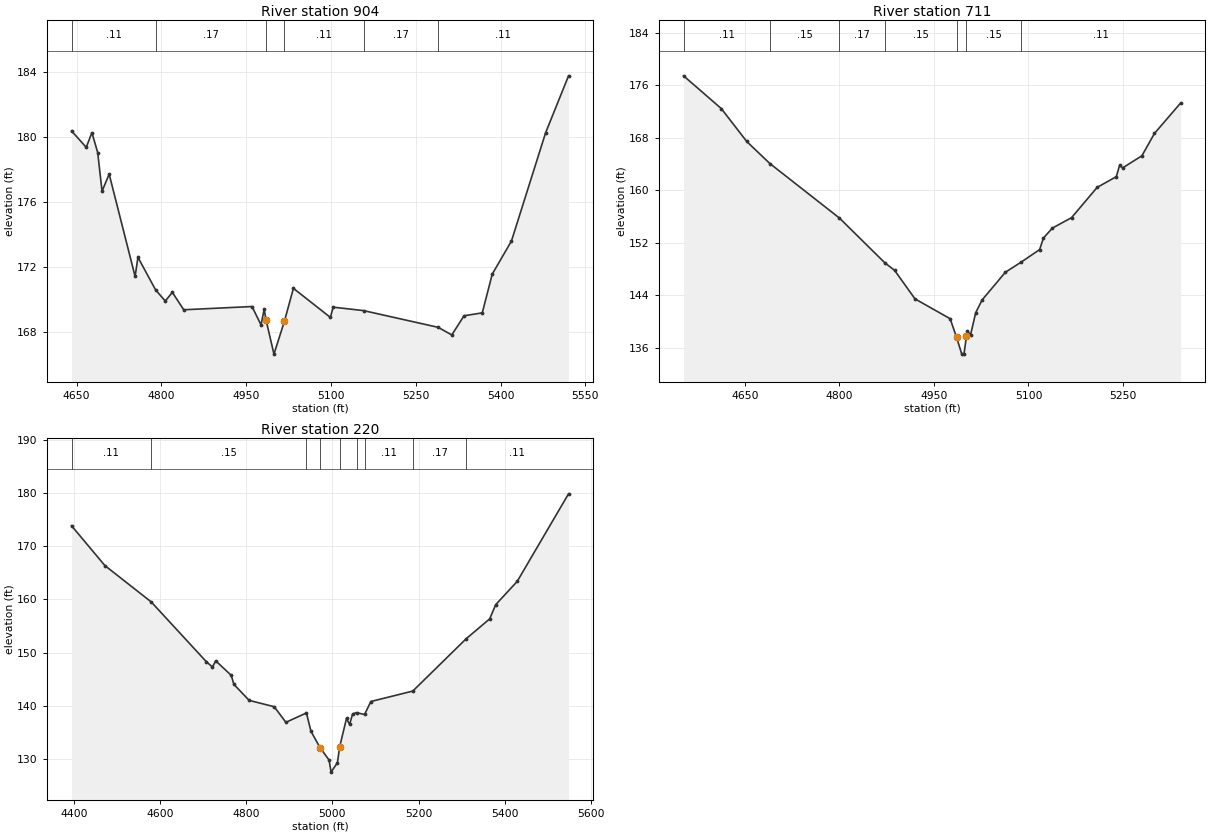
Type RM Length L Ch R = 1 ,904     ,193,193,193
BEGIN DESCRIPTION:
Mapping XS c865e40e
END DESCRIPTION:
XS GIS Cut Line= 6
      3800052.29      10088436.2       3800219.4     10088405.82
      3800462.46      10088371.1      3800709.86     10088347.23
      3800785.81     10088377.61      3800918.22      10088392.8
#Sta/Elev= 30
  4641.1   180.4  4667.1  179.39  4677.2  180.29  4687.4  179.07  4695.1  176.69
  4707.7  177.74  4753.6  171.44  4758.6  172.62  4789.9  170.61  4806.9  169.93
  4819.5  170.46  4839.6  169.39  4960.4  169.59  4976.3  168.46  4981.9  169.41
 4985.28168.7492  4999.2  166.66 5017.73168.6855  5033.6  170.71    5099  168.92
    5104  169.55  5157.6  169.34  5289.6  168.31  5313.8  167.84  5335.4  169.02
  5367.7   169.2  5385.4  171.59  5419.3  173.62  5479.7  180.28  5520.3  183.79
#Mann= 6 ,-1 , 0
  4641.1     .11       0  4789.9     .17       0 4985.28     .06       0
 5017.73     .11       0  5157.6     .17       0  5289.6     .11       0
Bank Sta=4985.28,5017.73
XS Rating Curve= 0 ,0
Exp/Cntr=0.3,0.1

Type RM Length L Ch R = 1 ,711     ,491,491,491
BEGIN DESCRIPTION:
Mapping XS 2a0a99a8
END DESCRIPTION:
XS GIS Cut Line= 3
       3800058.4     10088505.97      3800422.96     10088550.24
      3800838.31     10088479.93
#Sta/Elev= 30
  4552.8   177.4  4612.7  172.41    4653   167.4  4689.8  164.03  4800.2  155.72
  4872.2   148.9  4887.6  147.76    4920  143.41  4975.7  140.39  4985.9  137.56
  4994.2  134.99  4997.7  134.99 5001.61 137.692    5003  138.54  5008.1  137.92
  5016.3   141.3  5026.4  143.24  5063.4  147.47  5088.4  149.01  5117.7  150.92
  5123.8  152.69    5138   154.2  5168.4  155.79    5209   160.4  5239.4  162.04
  5244.5  163.74  5249.6  163.38    5280  165.22  5299.9  168.62  5341.3  173.25
#Mann= 7 ,-1 , 0
  4552.8     .11       0  4689.8     .15       0  4800.2     .17       0
  4872.2     .15       0  4985.9     .09       0 5001.61     .15       0
  5088.4     .11       0
Bank Sta=4985.9,5001.61
XS Rating Curve= 0 ,0
Exp/Cntr=0.3,0.1

Type RM Length L Ch R = 1 ,220     ,0,0,0
BEGIN DESCRIPTION:
STOWE BRANCH 1.0
END DESCRIPTION:
XS GIS Cut Line= 3
      3800040.55     10088569.74      3800523.22     10088934.36
      3800901.23     10088535.54
#Sta/Elev= 30
    4394  173.84  4471.5  166.36  4579.1  159.54  4706.7  148.35  4721.2  147.32
    4729  148.47  4764.9  145.76  4771.2  144.05  4806.6  141.05  4864.8  139.86
  4891.9  136.93  4939.6  138.69  4950.1  135.26    4971   132.2  4992.2  129.85
  4996.9  127.58  5011.6  129.35 5016.68132.2876  5032.7  137.67  5039.9  136.53
  5046.8   138.5    5056  138.75  5074.6   138.4  5089.3  140.84  5186.7   142.8
  5310.6  152.62  5365.2  156.35  5379.3  159.03  5429.1  163.38  5548.4  179.83
#Mann= 9 ,-1 , 0
    4394     .11       0  4579.1     .15       0  4939.6     .17       0
    4971     .09       0 5016.68     .17       0    5056     .15       0
  5074.6     .11       0  5186.7     .17       0  5310.6     .11       0
Bank Sta=4971,5016.68
XS Rating Curve= 0 ,0
Exp/Cntr=0.3,0.1

Chan Stop Cuts=-1
Use User Specified Reach Order=0
Composite Channel Slope=5