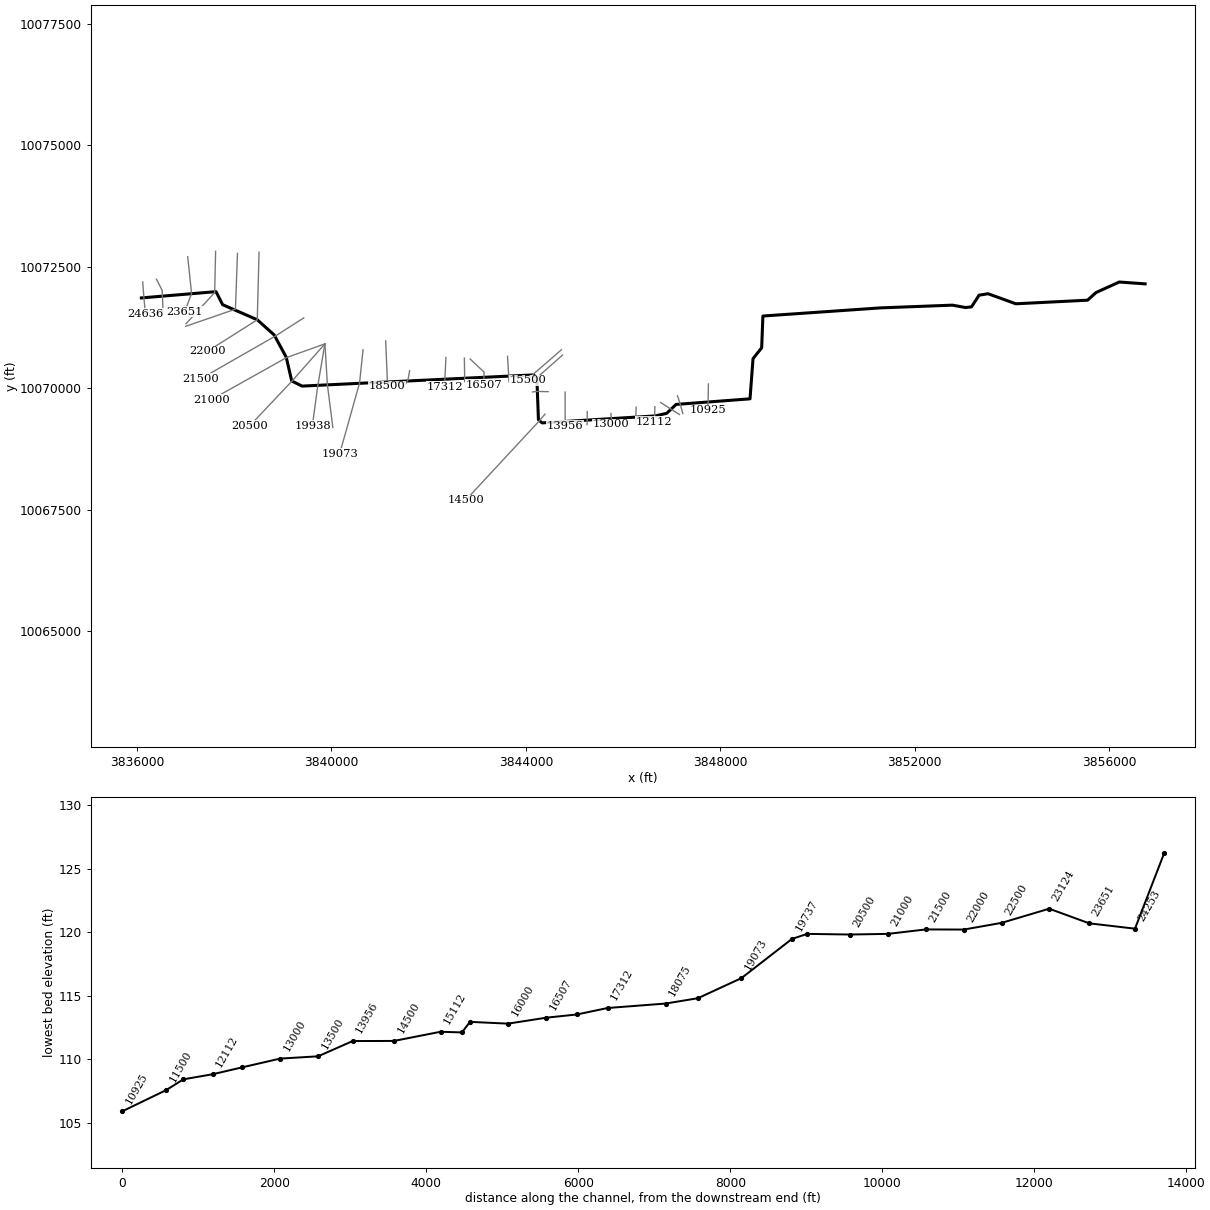
--- CARTERS SLOUGH.prj (project) ---

Proj Title=CARTERS SLOUGH Base Level Engineering
Current Plan=p01
Default Exp/Contr=0.3,0.1
English Units
Geom File=g01
Flow File=f01
Plan File=p01
Y Axis Title=Elevation
X Axis Title(PF)=Main Channel Distance
X Axis Title(XS)=Station
BEGIN DESCRIPTION:
CARTERS SLOUGH
END DESCRIPTION:
DSS Export Rating Curves= 0
DSS Export Rating Curve Sorted= 0
DSS Export Volume Flow Curves= 0
DXF OffsetX= 0
DXF OffsetY= 0
DXF ScaleX= 1
DXF ScaleY= 10

--- CARTERS SLOUGH.p01 (plan) ---

Plan Title=Multiple Run
Short Identifier=Multiple
Geom File=g01
Flow File=f01
Subcritical Flow
K Sum by GR= 0
Std Step Tol= 0.01
Critical Tol= 0.01
Num of Std Step Trials= 20
Max Error Tol= 0.3
Flow Tol Ratio= 0.001
Split Flow NTrial= 30
Split Flow Tol= 0.02
Split Flow Ratio= 0.02
Log Output Level= 0
Friction Slope Method= 1
Unsteady Friction Slope Method= 2
Unsteady Bridges Friction Slope Method= 1
Parabolic Critical Depth
Global Vel Dist=  1 , 1 , 1
Global Log Level= 0
CheckData=True
Encroach Param= -1, 0, 0, 0
BEGIN DESCRIPTION:
Multiple Run
END DESCRIPTION:

--- CARTERS SLOUGH.f01 (steady flow) ---

Flow Title=Multiple
Program Version=4.10
Number of Profiles= 7
Profile Names=10-year,25-year,50-year,1pct_min,100-year,1pct_plu,500-year
River Rch & RM=CARTERS SLOUGH,Reach-1         ,24636
     511     668     881     382    1153    3482    2043
River Rch & RM=CARTERS SLOUGH,Reach-1         ,23651
    1082    1471    1991     883    2668    8057    4954
River Rch & RM=CARTERS SLOUGH,Reach-1         ,18500
    1118    1505    2023     890    2688    8118    4916
River Rch & RM=CARTERS SLOUGH,Reach-1         ,6500
    1335    1813    2452    1085    3277    9896    6056
Boundary for River Rch & Prof#=CARTERS SLOUGH,Reach-1         , 1
Up Type= 0
Dn Type= 3
Dn Slope=0.005
Boundary for River Rch & Prof#=CARTERS SLOUGH,Reach-1         , 2
Up Type= 0
Dn Type= 3
Dn Slope=0.005
Boundary for River Rch & Prof#=CARTERS SLOUGH,Reach-1         , 3
Up Type= 0
Dn Type= 3
Dn Slope=0.005
Boundary for River Rch & Prof#=CARTERS SLOUGH,Reach-1         , 4
Up Type= 0
Dn Type= 3
Dn Slope=0.005
Boundary for River Rch & Prof#=CARTERS SLOUGH,Reach-1         , 5
Up Type= 0
Dn Type= 3
Dn Slope=0.005
Boundary for River Rch & Prof#=CARTERS SLOUGH,Reach-1         , 6
Up Type= 0
Dn Type= 3
Dn Slope=0.005
Boundary for River Rch & Prof#=CARTERS SLOUGH,Reach-1         , 7
Up Type= 0
Dn Type= 3
Dn Slope=0.005
DSS Import GetInterval= 0
DSS Import GetPeak= 0
DSS Import FillOption= 0

--- CARTERS SLOUGH.f02 (steady flow) ---

Flow Title=Orig_BLE_Flow
Program Version=4.10
Number of Profiles= 7
Profile Names=10-year,25-year,50-year,1pct_min,100-year,1pct_plu,500-year
River Rch & RM=CARTERS SLOUGH,Reach-1         ,24636
     511     655     766     294     887    2679    1188
River Rch & RM=CARTERS SLOUGH,Reach-1         ,23651
    1082    1442    1731     679    2052    6196    2880
River Rch & RM=CARTERS SLOUGH,Reach-1         ,18500
    1118    1475    1759     685    2068    6247    2858
River Rch & RM=CARTERS SLOUGH,Reach-1         ,6500
    1335    1777    2132     835    2521    7612    3521
Boundary for River Rch & Prof#=CARTERS SLOUGH,Reach-1         , 1
Up Type= 0
Dn Type= 3
Dn Slope=0.002
Boundary for River Rch & Prof#=CARTERS SLOUGH,Reach-1         , 2
Up Type= 0
Dn Type= 3
Dn Slope=0.002
Boundary for River Rch & Prof#=CARTERS SLOUGH,Reach-1         , 3
Up Type= 0
Dn Type= 3
Dn Slope=0.002
Boundary for River Rch & Prof#=CARTERS SLOUGH,Reach-1         , 4
Up Type= 0
Dn Type= 3
Dn Slope=0.002
Boundary for River Rch & Prof#=CARTERS SLOUGH,Reach-1         , 5
Up Type= 0
Dn Type= 3
Dn Slope=0.002
Boundary for River Rch & Prof#=CARTERS SLOUGH,Reach-1         , 6
Up Type= 0
Dn Type= 3
Dn Slope=0.002
Boundary for River Rch & Prof#=CARTERS SLOUGH,Reach-1         , 7
Up Type= 0
Dn Type= 3
Dn Slope=0.002
DSS Import GetInterval= 0
DSS Import GetPeak= 0
DSS Import FillOption= 0

--- CARTERS SLOUGH.g01 (geometry) ---

Geom Title=Existing Conditions
Program Version=4.10

River Reach=CARTERS SLOUGH  ,Reach-1
Reach XY= 30
      3836089.46     10071860.43      3837625.35     10071989.86
      3837760.57     10071721.43       3838473.4     10071410.87
      3838821.86     10071097.86      3839070.07     10070638.13
      3839182.55     10070150.28      3839395.91     10070044.52
      3844156.67     10070274.77       3844225.7     10070209.57
      3844257.93     10069351.94      3844334.31     10069286.72
      3846663.53     10069430.25      3846897.66     10069484.05
       3847089.5     10069667.11      3848610.13     10069782.03
      3848672.25     10070609.22      3848850.16     10070833.73
       3848875.3     10071487.65      3851297.69     10071655.47
      3852773.63     10071711.58      3853042.85     10071662.59
      3853166.58     10071675.94      3853322.15     10071916.77
      3853507.36     10071946.82      3854077.27     10071739.68
      3855552.82     10071813.71      3855730.12     10071972.33
      3856206.51     10072188.28      3856738.24     10072149.91

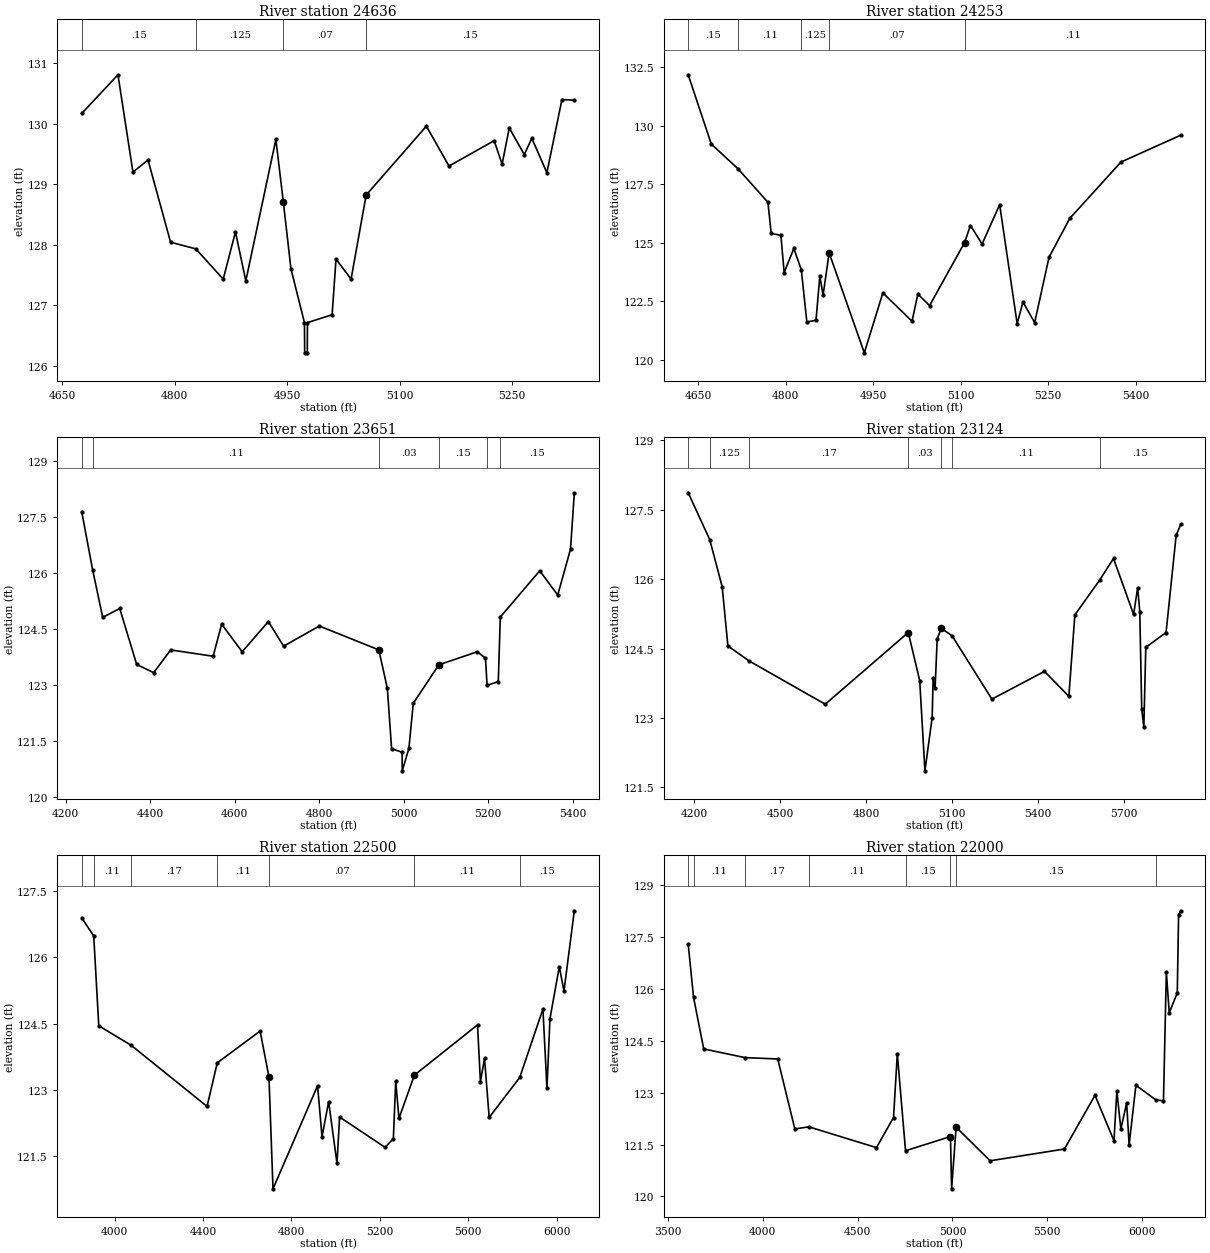
Type RM Length L Ch R = 1 ,24636   ,383,383,383
BEGIN DESCRIPTION:
CARTERS SLOUGH 49.0
END DESCRIPTION:
XS GIS Cut Line= 3
      3836116.83     10072189.18      3836141.99     10071866.16
      3836171.92     10071534.61
#Sta/Elev= 30
    4676  130.17  4724.3  130.81  4744.3   129.2  4764.4   129.4  4794.5  128.04
  4828.1  127.93  4864.7  127.43    4881  128.21  4894.8   127.4  4934.9  129.74
  4944.9   128.7    4955   127.6    4973  126.71  4973.3  126.21  4976.8  126.21
    4977  126.71  5009.9  126.84  5015.1  127.76  5035.2  127.43  5055.3  128.82
  5135.6  129.96  5165.8   129.3    5226  129.72  5236.6  129.33  5246.1  129.93
  5266.2  129.49  5276.2  129.76  5296.3  129.19  5316.4   130.4  5332.9  130.39
#Mann= 4 ,-1 , 0
    4676     .15       0  4828.1    .125       0  4944.9     .07       0
  5055.3     .15       0
Bank Sta=4944.9,5055.3
XS Rating Curve= 0 ,0
Exp/Cntr=0.3,0.1

Type RM Length L Ch R = 1 ,24253   ,602,602,602
BEGIN DESCRIPTION:
CARTERS SLOUGH 48.0
END DESCRIPTION:
XS GIS Cut Line= 4
      3836400.05     10072246.32      3836518.31     10072014.13
      3836535.67      10071587.7      3836393.76     10071520.46
#Sta/Elev= 30
  4632.9  132.17  4672.5  129.21  4718.5  128.15  4769.6  126.72  4775.2  125.39
  4791.8  125.31  4797.4  123.72    4814  124.75  4826.8  123.84  4836.3  121.61
    4852  121.68  4858.5  123.57  4864.1  122.75  4874.5  124.56  4934.8  120.29
  4966.6  122.85  5016.6  121.64  5026.6   122.8  5046.7  122.31  5106.7     125
  5116.7  125.73  5136.7  124.94  5166.8  126.62  5196.8  121.54  5206.8  122.46
  5226.8  121.58  5251.4  124.37  5286.9  126.03  5374.7  128.44  5477.3  129.59
#Mann= 5 ,-1 , 0
  4632.9     .15       0  4718.5     .11       0  4826.8    .125       0
  4874.5     .07       0  5106.7     .11       0
Bank Sta=4874.5,5106.7
XS Rating Curve= 0 ,0
Exp/Cntr=0.3,0.1

Type RM Length L Ch R = 1 ,23651   ,527,527,527
BEGIN DESCRIPTION:
CARTERS SLOUGH 47.0
END DESCRIPTION:
XS GIS Cut Line= 3
      3837042.67     10072710.48      3837122.59     10071952.58
      3836980.91     10071574.35
#Sta/Elev= 30
  4237.9  127.65  4263.6   126.1  4287.6  124.82  4327.8  125.06    4368  123.56
  4408.2  123.34  4448.5  123.95    4549  123.78  4569.1  124.64  4617.7   123.9
  4679.7  124.71  4715.7  124.05  4800.4  124.59  4941.2  123.95  4961.3  122.92
  4971.4   121.3  4996.2  121.21  4996.5  120.71  5012.3  121.31  5022.7  122.52
  5083.2  123.55  5174.1   123.9  5193.6  123.73  5197.4     123  5223.9   123.1
  5228.7  124.83    5322  126.07  5364.6  125.42  5394.9  126.65  5403.9  128.16
#Mann= 6 ,-1 , 0
  4237.9    .125       0  4263.6     .11       0  4941.2     .03       0
  5083.2     .15       0  5197.4     .11       0  5228.7     .15       0
Bank Sta=4941.2,5083.2
XS Rating Curve= 0 ,0
Exp/Cntr=0.3,0.1

Type RM Length L Ch R = 1 ,23124   ,624,624,624
BEGIN DESCRIPTION:
CARTERS SLOUGH 46.0
END DESCRIPTION:
XS GIS Cut Line= 3
      3837617.05     10072819.75      3837597.52     10071970.84
      3837007.94      10071328.4
#Sta/Elev= 30
  4178.1  127.87  4253.2  126.86  4296.8  125.84  4316.8  124.56  4389.7  124.24
  4656.9   123.3    4947  124.85    4987  123.81  5005.2  121.86  5030.5  123.01
  5033.9  123.86  5040.7  123.64  5048.1  124.71  5062.3  124.94  5099.9  124.78
  5239.2  123.41    5423  124.01  5508.1  123.47  5529.1  125.23  5615.4  125.98
  5664.1  126.45  5734.4  125.24  5748.6  125.82  5755.9   125.3  5762.7   123.2
  5770.1   122.8  5776.9  124.53  5847.8  124.85    5883  126.95  5899.2  127.19
#Mann= 7 ,-1 , 0
  4178.1     .15       0  4253.2    .125       0  4389.7     .17       0
    4947     .03       0  5062.3     .17       0  5099.9     .11       0
  5615.4     .15       0
Bank Sta=4947,5062.3
XS Rating Curve= 0 ,0
Exp/Cntr=0.3,0.1

Type RM Length L Ch R = 1 ,22500   ,500,500,500
BEGIN DESCRIPTION:
CARTERS SLOUGH 45.0
END DESCRIPTION:
XS GIS Cut Line= 3
      3838066.92      10072778.1      3838024.72     10071629.27
      3837003.59     10071276.32
#Sta/Elev= 30
  3850.4   126.9  3904.7  126.49  3927.5  124.45  4073.6  124.01  4417.8  122.62
    4464  123.61    4658  124.33    4698  123.29  4716.3  120.75  4918.1  123.09
  4938.2  121.93  4968.2  122.73  5005.9  121.33  5017.8  122.38  5224.1  121.69
  5261.2  121.89  5271.8  123.19  5286.5  122.35  5356.4  123.33  5642.1  124.47
  5655.3  123.18  5673.8  123.71    5695  122.37  5833.6  123.28  5938.3  124.83
  5956.5  123.03  5970.1  124.61  6012.4  125.79  6033.6  125.24  6080.4  127.06
#Mann= 7 ,-1 , 0
  3850.4    .125       0  3904.7     .11       0  4073.6     .17       0
    4464     .11       0    4698     .07       0  5356.4     .11       0
  5833.6     .15       0
Bank Sta=4698,5356.4
XS Rating Curve= 0 ,0
Exp/Cntr=0.3,0.1

Type RM Length L Ch R = 1 ,22000   ,500,500,500
BEGIN DESCRIPTION:
CARTERS SLOUGH 44.0
END DESCRIPTION:
XS GIS Cut Line= 3
       3838510.4     10072802.88      3838473.97     10071410.36
      3837458.05     10070765.68
#Sta/Elev= 30
    3607  127.29  3635.2  125.75  3688.8  124.26  3906.4  124.01    4079  123.97
    4169  121.95  4243.3  122.01  4599.1  121.41  4689.2  122.28  4709.2  124.12
  4752.4  121.32  4989.3  121.73  4995.4  120.22  5019.1     122  5198.6  121.03
    5590  121.37    5751  122.92    5851  121.61  5866.2  123.04  5887.4  121.95
  5917.9   122.7    5931  121.49  5966.6  123.21  6071.4  122.79  6111.9  122.76
  6127.1  126.48  6142.4   125.3  6184.7  125.88  6191.6  128.13  6203.2  128.25
#Mann= 8 ,-1 , 0
    3607     .15       0  3635.2     .11       0  3906.4     .17       0
  4243.3     .11       0  4752.4     .15       0  4989.3     .07       0
  5019.1     .15       0  6071.4     .11       0
Bank Sta=4989.3,5019.1
XS Rating Curve= 0 ,0
Exp/Cntr=0.3,0.1

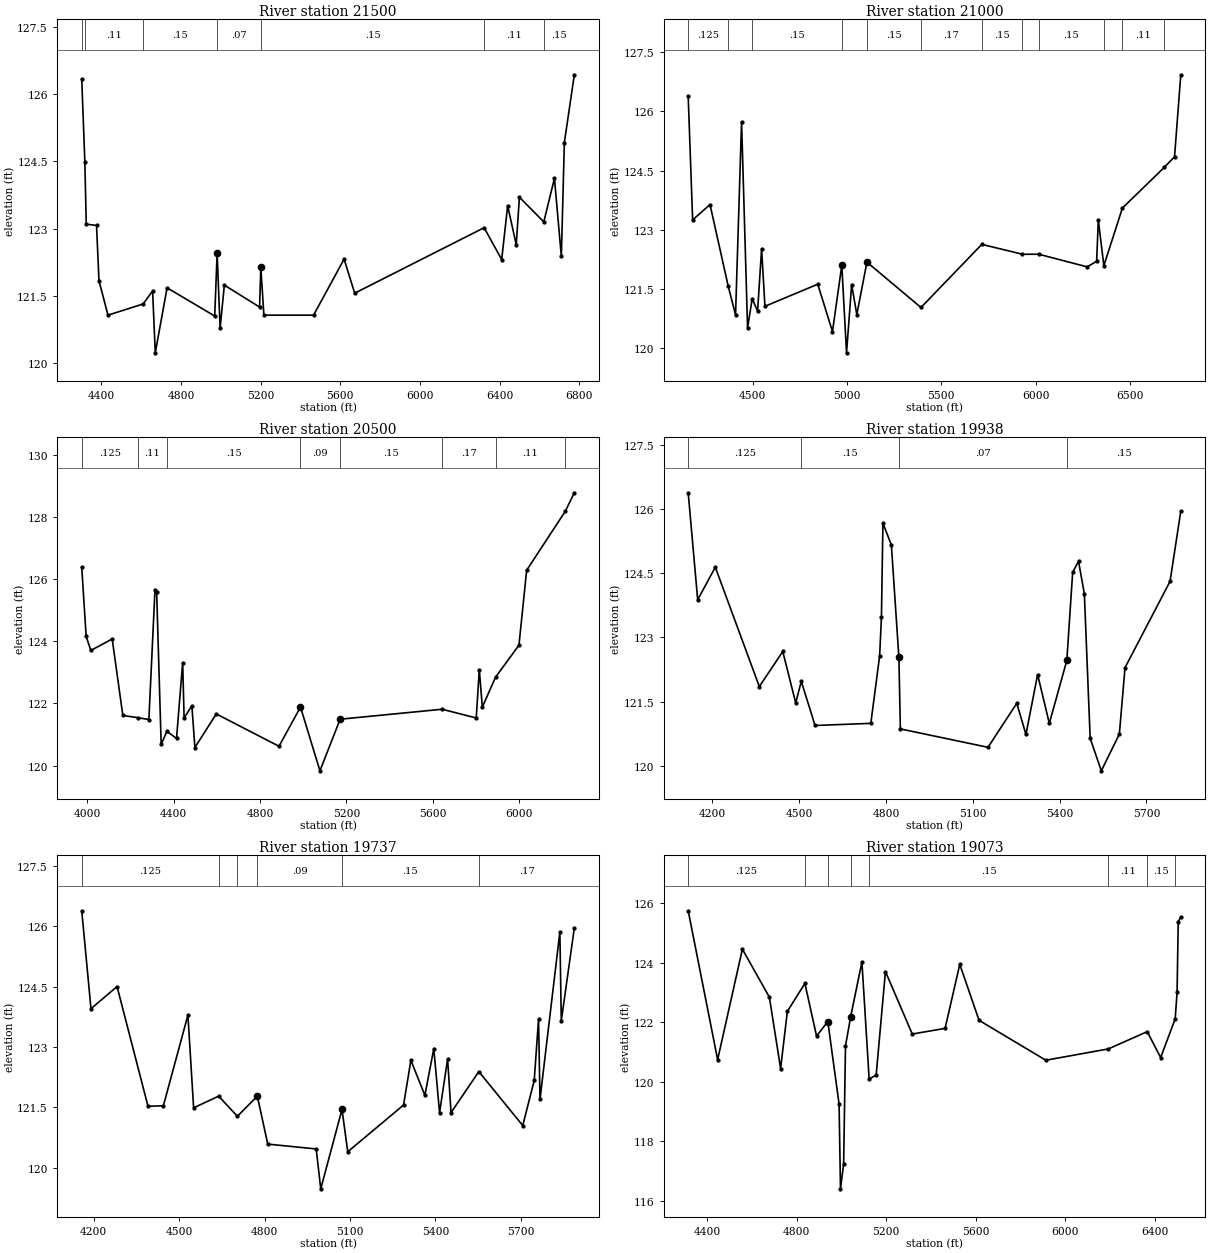
Type RM Length L Ch R = 1 ,21500   ,500,500,500
BEGIN DESCRIPTION:
CARTERS SLOUGH 43.0
END DESCRIPTION:
XS GIS Cut Line= 3
      3839430.82     10071449.06      3838841.92      10071072.5
      3837301.27     10070190.21
#Sta/Elev= 30
    4301  126.34  4316.6  124.49  4323.7   123.1  4375.3  123.07  4387.6  121.84
  4432.8  121.07  4609.6  121.32    4657  121.61  4670.4  120.23  4729.7  121.68
    4969  121.05  4981.1  122.45  4996.1  120.78  5017.4  121.74  5194.4  121.25
  5200.6  122.14    5216  121.07  5465.6  121.07  5618.9  122.32  5672.1  121.56
  6322.2  123.02  6410.6  122.31  6440.5  123.51  6483.7  122.64  6499.5   123.7
  6622.1  123.15  6675.6  124.12  6710.2  122.38  6725.4  124.92  6775.4  126.43
#Mann= 7 ,-1 , 0
    4301     .17       0  4316.6     .11       0  4609.6     .15       0
  4981.1     .07       0  5200.6     .15       0  6322.2     .11       0
  6622.1     .15       0
Bank Sta=4981.1,5200.6
XS Rating Curve= 0 ,0
Exp/Cntr=0.3,0.1

Type RM Length L Ch R = 1 ,21000   ,500,500,500
BEGIN DESCRIPTION:
CARTERS SLOUGH 42.0
END DESCRIPTION:
XS GIS Cut Line= 3
      3839864.04     10070914.32      3839072.36     10070629.67
       3837528.9     10069763.68
#Sta/Elev= 30
  4158.7  126.38  4182.2  123.25  4274.3  123.64  4370.3  121.58  4409.7  120.84
  4441.6  125.74  4473.4  120.51  4497.8  121.25  4526.6  120.94  4547.8  122.52
  4565.5  121.06  4845.4  121.62  4923.5  120.42  4972.9   122.1    4998  119.88
  5025.1  121.61  5052.5  120.85  5106.1  122.18  5392.6  121.03  5715.1  122.63
  5930.7  122.38  6017.2  122.38  6273.3  122.06  6323.8   122.2  6332.6  123.25
    6362  122.09  6460.2  123.55  6681.7  124.58  6736.6  124.85  6769.8  126.93
#Mann= 12 ,-1 , 0
  4158.7    .125       0  4370.3     .11       0  4497.8     .15       0
  4972.9     .09       0  5106.1     .15       0  5392.6     .17       0
  5715.1     .15       0  5930.7     .11       0  6017.2     .15       0
    6362    .125       0  6460.2     .11       0  6681.7     .15       0
Bank Sta=4972.9,5106.1
XS Rating Curve= 0 ,0
Exp/Cntr=0.3,0.1

Type RM Length L Ch R = 1 ,20500   ,562,562,562
BEGIN DESCRIPTION:
CARTERS SLOUGH 41.0
END DESCRIPTION:
XS GIS Cut Line= 3
      3839864.43     10070913.71      3839185.82     10070145.12
      3838324.27     10069232.56
#Sta/Elev= 30
  3974.7  126.38  3995.2  124.15    4017   123.7  4115.7  124.07    4165  121.61
  4233.8  121.54  4285.5  121.48  4313.9  125.66  4321.5  125.58  4342.4  120.68
  4369.2   121.1  4413.5  120.87    4442  123.31  4448.6  121.53  4484.6  121.92
  4498.5  120.58  4597.5  121.66  4887.8  120.62  4987.4  121.88  5077.4  119.83
    5171  121.49    5643  121.81  5800.9  121.53  5815.1  123.08  5829.2  121.88
  5890.3  122.84  5998.7  123.87  6034.4  126.28  6212.8  128.17    6255  128.77
#Mann= 8 ,-1 , 0
  3974.7    .125       0  4233.8     .11       0  4369.2     .15       0
  4987.4     .09       0    5171     .15       0    5643     .17       0
  5890.3     .11       0  6212.8     .15       0
Bank Sta=4987.4,5171
XS Rating Curve= 0 ,0
Exp/Cntr=0.3,0.1

Type RM Length L Ch R = 1 ,19938   ,201,201,201
BEGIN DESCRIPTION:
CARTERS SLOUGH 40.0
END DESCRIPTION:
XS GIS Cut Line= 3
      3839864.89      10070913.4      3839717.16     10070043.61
      3839607.72     10069230.69
#Sta/Elev= 30
  4116.3  126.38  4149.1  123.88    4210  124.64  4362.1  121.85  4443.2  122.67
  4487.8  121.47  4507.2  121.97  4554.8  120.94  4747.5  120.99    4778  122.57
  4784.2  123.48  4789.3  125.67  4818.5  125.16  4844.5  122.53  4849.6  120.86
  5152.5  120.43    5252  121.46  5283.6  120.73    5324  122.13  5364.4  120.99
  5424.9  122.46  5445.1  124.52  5465.3  124.78  5485.5  124.02  5505.6  120.64
  5544.2  119.88  5606.5  120.74    5626  122.29  5781.7  124.31  5818.8  125.95
#Mann= 4 ,-1 , 0
  4116.3    .125       0  4507.2     .15       0  4844.5     .07       0
  5424.9     .15       0
Bank Sta=4844.5,5424.9
XS Rating Curve= 0 ,0
Exp/Cntr=0.3,0.1

Type RM Length L Ch R = 1 ,19737   ,664,664,664
BEGIN DESCRIPTION:
CARTERS SLOUGH 39.0
END DESCRIPTION:
XS GIS Cut Line= 3
      3839865.54     10070913.49      3839916.75     10070070.45
      3840028.72     10069191.35
#Sta/Elev= 30
  4157.6  126.38  4190.1  123.95  4281.7   124.5  4390.4  121.53  4444.4  121.54
  4530.7  123.79  4550.7  121.49  4638.7  121.78  4704.5  121.28  4774.6  121.78
  4811.2  120.59  4981.5  120.47  4997.4  119.48  5072.1  121.45  5092.3   120.4
  5288.4  121.56  5314.1  122.67  5363.3   121.8  5394.7  122.96  5414.9  121.37
  5443.2   122.7  5455.2  121.37  5552.8  122.39  5707.2  121.05  5747.5  122.17
  5762.7  123.69  5767.8   121.7  5837.6  125.85  5842.6  123.65  5888.4  125.95
#Mann= 6 ,-1 , 0
  4157.6    .125       0  4638.7     .11       0  4704.5     .15       0
  4774.6     .09       0  5072.1     .15       0  5552.8     .17       0
Bank Sta=4774.6,5072.1
XS Rating Curve= 0 ,0
Exp/Cntr=0.3,0.1

Type RM Length L Ch R = 1 ,19073   ,573,573,573
BEGIN DESCRIPTION:
CARTERS SLOUGH 38.0
END DESCRIPTION:
XS GIS Cut Line= 3
      3840649.53     10070792.01      3840578.31     10070109.46
      3840168.47     10068649.65
#Sta/Elev= 30
  4314.8  125.74  4446.4  120.74    4557  124.45  4677.7  122.84    4728  120.44
  4758.1  122.36  4836.6   123.3  4888.8  121.53  4939.1  122.02  4989.4  119.25
  4995.7   116.4  5009.8  117.23  5018.1   121.2  5040.9  122.17  5091.5  124.02
  5123.9  120.09  5155.2  120.22  5196.7   123.7  5316.7   121.6  5463.4  121.79
  5529.1  123.94  5615.3  122.06  5913.9  120.72  6193.4   121.1  6367.3  121.68
  6427.3  120.81  6492.3  122.11  6500.7     123  6505.9  125.37  6517.3  125.53
#Mann= 8 ,-1 , 0
  4314.8    .125       0  4836.6     .11       0  4939.1     .03       0
  5040.9     .11       0  5123.9     .15       0  6193.4     .11       0
  6367.3     .15       0  6492.3     .11       0
Bank Sta=4939.1,5040.9
XS Rating Curve= 0 ,0
Exp/Cntr=0.3,0.1

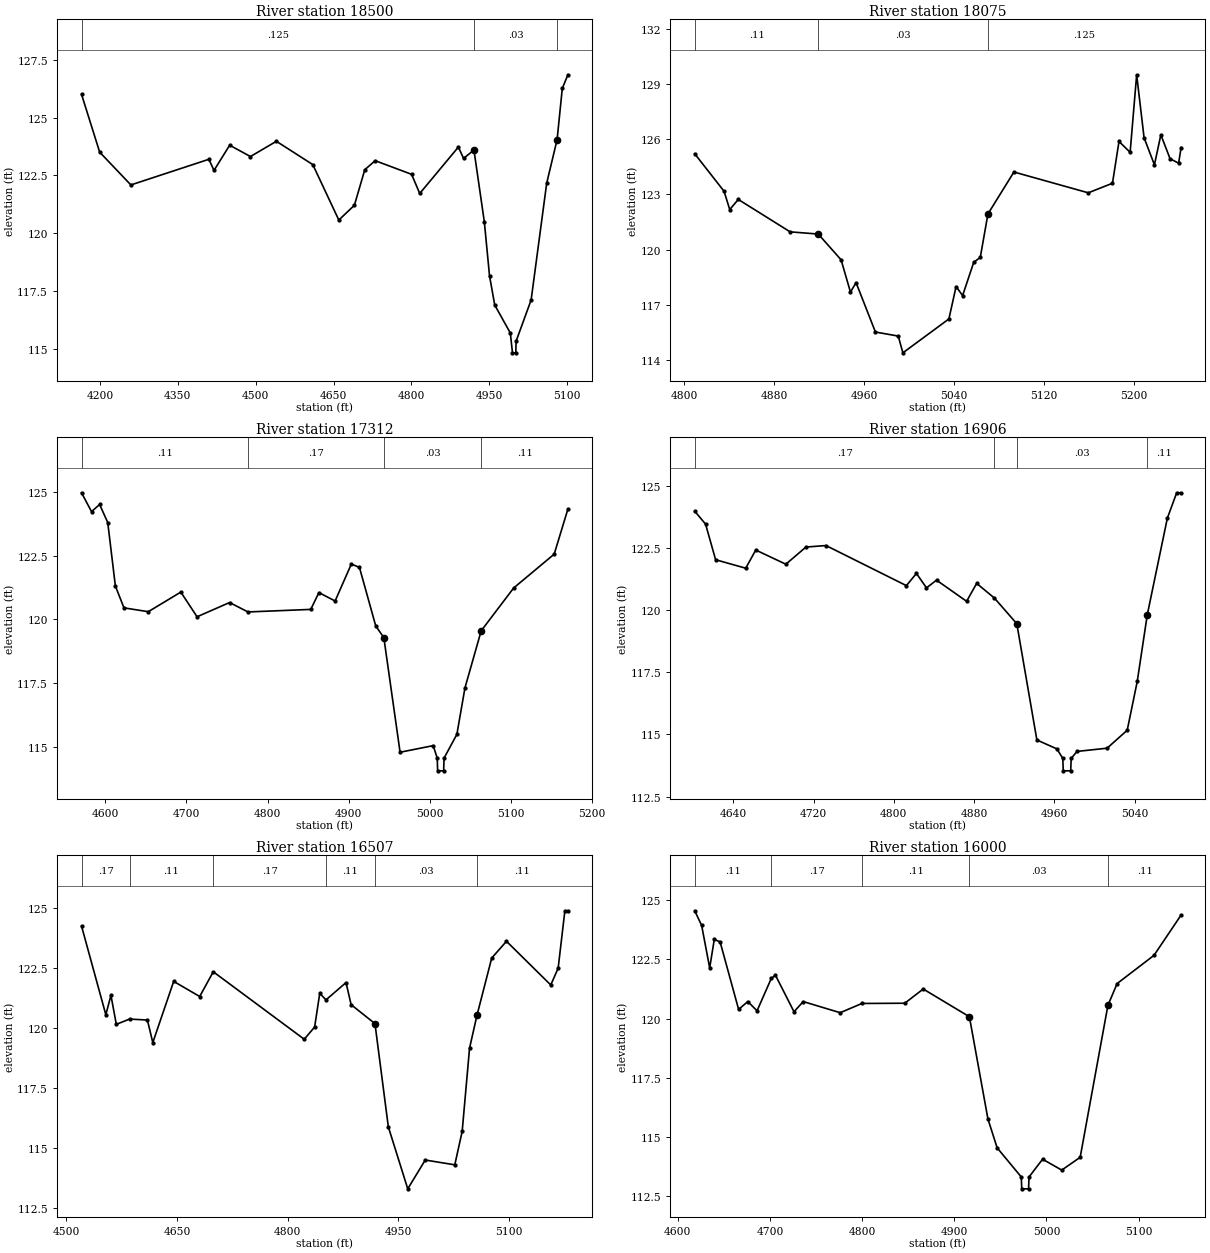
Type RM Length L Ch R = 1 ,18500   ,425,425,425
BEGIN DESCRIPTION:
CARTERS SLOUGH 37.0
END DESCRIPTION:
XS GIS Cut Line= 3
      3841115.54     10070975.99      3841150.53     10070141.42
      3841146.61      10070040.3
#Sta/Elev= 30
  4164.7  126.01  4199.6  123.51  4259.7  122.09  4409.8   123.2  4419.8  122.72
  4449.9  123.81  4489.9  123.32  4539.9  123.98    4610  122.97  4660.1  120.57
  4690.1  121.21  4710.1  122.75  4730.1  123.14  4800.2  122.55  4815.9  121.72
  4890.3  123.73  4900.3  123.24  4920.3   123.6  4940.3  120.49  4950.3  118.15
  4960.3  116.89  4990.3  115.68  4994.5  114.82  5000.9  114.82  5001.4  115.32
  5030.4  117.11  5060.4  122.17  5080.4  124.05  5090.4  126.27  5101.2  126.86
#Mann= 3 ,-1 , 0
  4164.7    .125       0  4920.3     .03       0  5080.4    .125       0
Bank Sta=4920.3,5080.4
XS Rating Curve= 0 ,0
Exp/Cntr=0.3,0.1

Type RM Length L Ch R = 1 ,18075   ,763,763,763
BEGIN DESCRIPTION:
CARTERS SLOUGH 36.0
END DESCRIPTION:
XS GIS Cut Line= 3
      3841607.94     10070359.12      3841574.18     10070171.64
      3841452.62     10069962.61
#Sta/Elev= 30
  4809.5  125.21  4835.6  123.17  4840.6  122.18  4848.2  122.73  4894.3  120.97
  4919.3  120.85  4939.6  119.45  4947.9   117.7  4952.9  118.21  4970.1  115.53
  4990.4  115.31  4994.5   114.4  5035.4  116.24  5041.8     118  5047.6  117.51
  5057.5  119.32  5063.3  119.58  5070.1  121.94  5093.2  124.22  5159.3  123.09
  5180.8  123.61  5186.6  125.88  5196.5  125.29  5202.3   129.5  5208.9  126.08
  5218.1  124.61  5223.8  126.24    5232  124.94  5239.6   124.7  5241.8  125.55
#Mann= 3 , 0 , 0
  4809.5     .11       0  4919.3     .03       0  5070.1    .125       0
Bank Sta=4919.3,5070.1
XS Rating Curve= 0 ,0
Exp/Cntr=0.3,0.1

Type RM Length L Ch R = 1 ,17312   ,406,406,406
BEGIN DESCRIPTION:
CARTERS SLOUGH 35.0
END DESCRIPTION:
XS GIS Cut Line= 3
      3842355.06     10070633.31      3842334.49     10070204.51
      3842335.58     10070034.21
#Sta/Elev= 30
  4570.7  124.97    4583  124.23    4593  124.51    4603   123.8  4612.4  121.31
    4623  120.45    4653   120.3  4693.1  121.07  4713.1   120.1  4753.2  120.66
  4775.9  120.29  4853.3  120.39  4863.3  121.05  4883.3  120.72  4903.3  122.17
  4913.3  122.04  4933.4  119.74  4943.4  119.28  4963.4  114.78  5004.2  115.04
  5009.2  114.55  5009.7  114.05  5017.1  114.05  5017.6  114.55  5033.4  115.48
  5043.4  117.31  5063.4  119.55  5103.4  121.23  5153.4  122.56  5170.3  124.33
#Mann= 4 ,-1 , 0
  4570.7     .11       0  4775.9     .17       0  4943.4     .03       0
  5063.4     .11       0
Bank Sta=4943.4,5063.4
XS Rating Curve= 0 ,0
Exp/Cntr=0.3,0.1

Type RM Length L Ch R = 1 ,16906   ,399,399,399
BEGIN DESCRIPTION:
CARTERS SLOUGH 34.0
END DESCRIPTION:
XS GIS Cut Line= 2
      3842734.06     10070621.91      3842741.35     10070137.36
#Sta/Elev= 30
  4601.6  123.97  4612.4  123.45  4622.4  122.02  4652.4  121.68  4662.4  122.41
  4692.4  121.84  4712.4  122.53  4732.4  122.59  4812.5  120.98  4822.5  121.47
  4832.5  120.89  4842.5   121.2  4872.5  120.35  4882.5  121.07  4900.2  120.48
  4922.5  119.45  4942.5  114.78  4962.5  114.42  4968.3  114.04  4968.8  113.54
  4976.2  113.54  4976.7  114.04  4982.5  114.32  5012.5  114.45  5032.5  115.17
  5042.5  117.13  5052.5  119.81  5072.5  123.69  5081.8  124.71  5086.2  124.71
#Mann= 4 ,-1 , 0
  4601.6     .17       0  4900.2     .11       0  4922.5     .03       0
  5052.5     .11       0
Bank Sta=4922.5,5052.5
XS Rating Curve= 0 ,0
Exp/Cntr=0.3,0.1

Type RM Length L Ch R = 1 ,16507   ,507,507,507
BEGIN DESCRIPTION:
CARTERS SLOUGH 33.0
END DESCRIPTION:
XS GIS Cut Line= 3
      3842852.98     10070602.52      3843140.12     10070332.12
      3843134.14     10070067.91
#Sta/Elev= 30
  4520.8  124.23  4553.7  120.54  4560.6  121.35  4567.9  120.14  4585.8  120.36
    4610  120.32  4617.3  119.38  4645.6  121.93  4680.8   121.3  4699.2  122.33
  4822.4  119.52  4836.5  120.03  4843.4  121.43  4851.9  121.16    4879  121.88
  4885.9  120.96  4918.2  120.17  4936.3  115.87  4962.6  113.29  4986.3  114.49
  5026.3  114.29  5036.3  115.68  5046.3  119.15  5056.3  120.51  5076.3   122.9
  5096.3   123.6  5156.3  121.78  5166.3  122.48  5175.4  124.87  5179.5  124.87
#Mann= 6 ,-1 , 0
  4520.8     .17       0  4585.8     .11       0  4699.2     .17       0
  4851.9     .11       0  4918.2     .03       0  5056.3     .11       0
Bank Sta=4918.2,5056.3
XS Rating Curve= 0 ,0
Exp/Cntr=0.3,0.1

Type RM Length L Ch R = 1 ,16000   ,500,500,500
BEGIN DESCRIPTION:
CARTERS SLOUGH 32.0
END DESCRIPTION:
XS GIS Cut Line= 3
      3843621.67     10070658.56      3843644.52     10070277.64
      3843652.04     10070131.74
#Sta/Elev= 30
  4618.4  124.55  4625.9  123.93  4634.6  122.14  4639.6  123.34  4645.9  123.24
    4666  120.39    4676  120.72    4686  120.33  4701.5   121.7    4706  121.83
  4726.1  120.29  4736.1  120.72  4776.2  120.25  4799.8  120.64  4846.3  120.65
  4866.3  121.25  4916.4  120.08  4936.5  115.77  4946.5  114.55  4972.7  113.32
  4973.2  112.82  4980.6  112.82  4981.1  113.32  4995.8  114.07  5016.6  113.61
  5036.6  114.15  5066.7  120.56  5076.7  121.48  5116.7  122.67  5146.1  124.37
#Mann= 5 ,-1 , 0
  4618.4     .11       0  4701.5     .17       0  4799.8     .11       0
  4916.4     .03       0  5066.7     .11       0
Bank Sta=4916.4,5066.7
XS Rating Curve= 0 ,0
Exp/Cntr=0.3,0.1

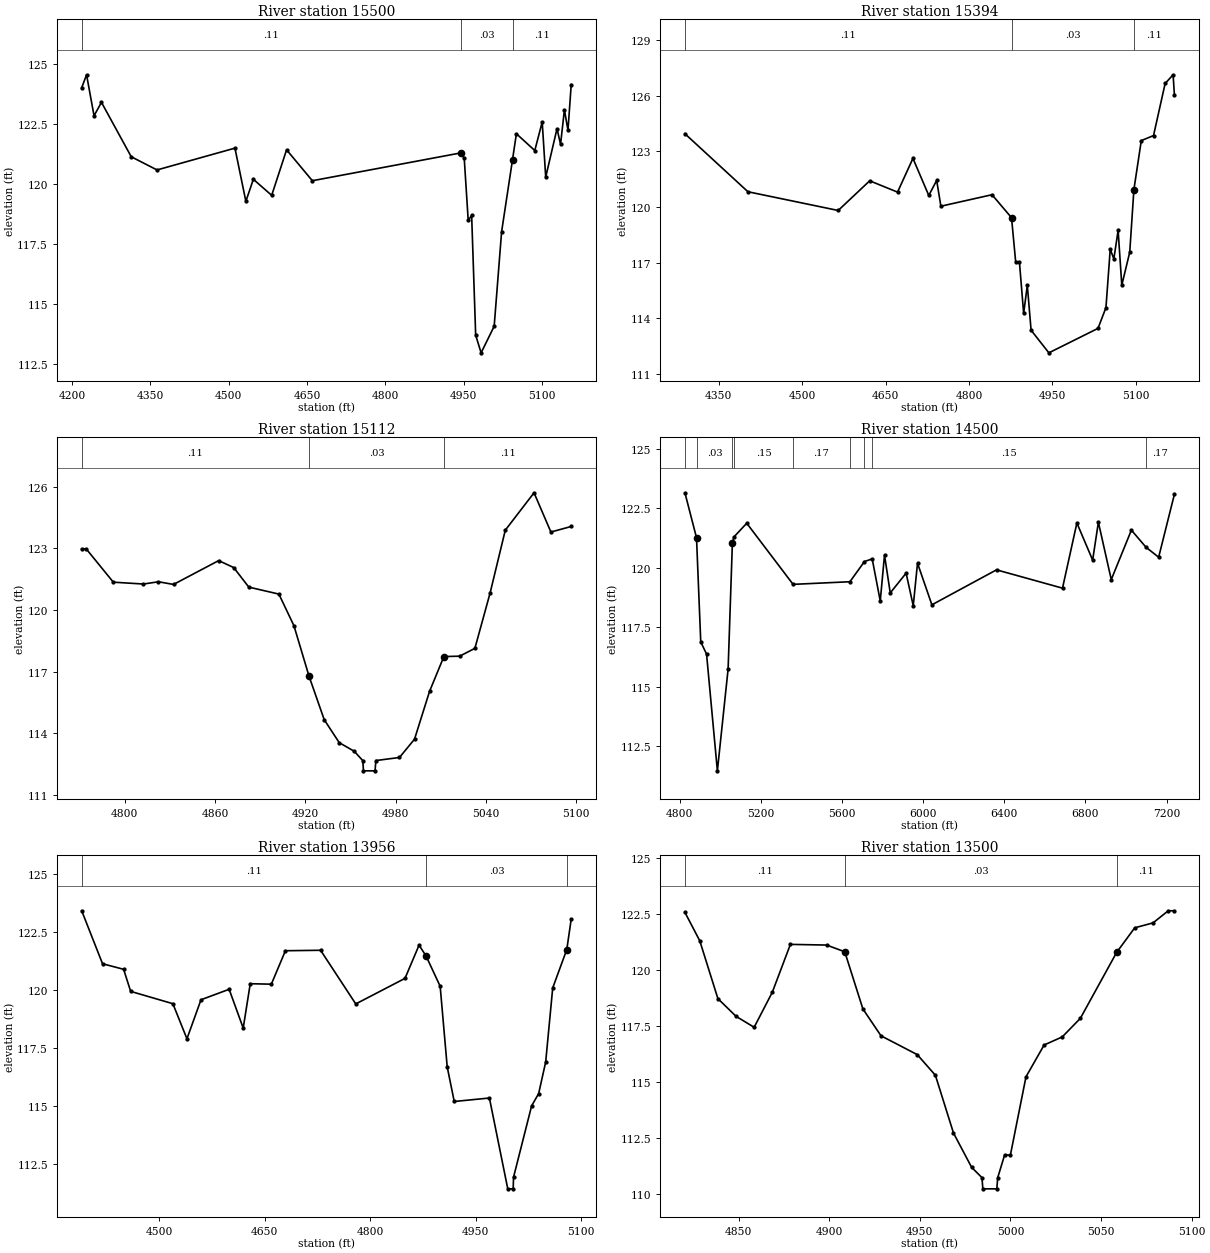
Type RM Length L Ch R = 1 ,15500   ,106,106,106
BEGIN DESCRIPTION:
CARTERS SLOUGH 31.0
END DESCRIPTION:
XS GIS Cut Line= 3
       3844730.1     10070791.98      3844140.43     10070279.57
      3844035.51     10070164.94
#Sta/Elev= 30
  4218.8  124.02  4228.1  124.56  4242.4  122.85  4256.6  123.41  4313.6  121.14
  4362.9  120.59    4512   121.5  4532.9  119.28  4547.2   120.2  4582.3  119.53
  4610.8  121.43  4660.1  120.14  4944.1   121.3  4950.7  121.08  4958.3  118.49
  4964.9  118.69  4972.6   113.7    4983  112.96    5008  114.07  5022.2  118.01
  5043.1  121.02  5050.5   122.1  5085.7   121.4  5099.9  122.59  5106.6  120.29
  5128.2  122.31    5135  121.66  5142.4   123.1  5149.2  122.24  5155.4  124.15
#Mann= 3 , 0 , 0
  4218.8     .11       0  4944.1     .03       0  5043.1     .11       0
Bank Sta=4944.1,5043.1
XS Rating Curve= 0 ,0
Exp/Cntr=0.3,0.1

Type RM Length L Ch R = 1 ,15394   ,282,282,282
BEGIN DESCRIPTION:
Mapping XS 3a0f5833
END DESCRIPTION:
XS GIS Cut Line= 3
      3844754.47     10070684.15      3844235.11     10070224.94
      3844092.33     10070103.35
#Sta/Elev= 30
    4289  123.95  4402.4  120.82  4564.8  119.81  4621.5  121.41  4671.6   120.8
  4699.3  122.62  4727.8  120.62    4742  121.43  4749.6  120.04  4841.6  120.66
  4876.7  119.42  4884.2  117.02  4890.9  117.03  4898.5  114.26  4905.1  115.77
  4911.9  113.35  4943.9  112.13  5032.3  113.45  5046.6  114.57  5054.3  117.72
  5060.8   117.2  5068.5  118.73  5075.1  115.78  5089.4  117.56  5096.9  120.94
  5110.2  123.58  5132.2  123.85  5153.1  126.66  5167.4  127.13  5169.8  126.03
#Mann= 3 , 0 , 0
    4289     .11       0  4876.7     .03       0  5096.9     .11       0
Bank Sta=4876.7,5096.9
XS Rating Curve= 0 ,0
Exp/Cntr=0.3,0.1

Type RM Length L Ch R = 1 ,15112   ,612,612,612
BEGIN DESCRIPTION:
CARTERS SLOUGH 30.0
END DESCRIPTION:
XS GIS Cut Line= 3
      3844458.88     10069929.87      3844213.76     10069934.03
      3844134.44     10069923.29
#Sta/Elev= 30
  4771.4  122.98  4774.4  122.98  4792.4  121.36  4812.4  121.27  4822.4  121.38
  4832.4  121.25  4862.4  122.41  4872.4  122.07  4882.4  121.12  4902.4  120.78
  4912.4  119.24  4922.4  116.79  4932.5  114.67  4942.5  113.55  4952.5  113.13
  4958.1  112.68  4958.6  112.18  4966.3  112.18  4966.8  112.68  4982.5  112.83
  4992.5  113.72  5002.5  116.05    5012  117.74  5022.5  117.76  5032.6  118.14
  5042.7  120.83  5052.8  123.89  5071.9  125.71  5083.1   123.8  5096.6  124.07
#Mann= 3 , 0 , 0
  4771.4     .11       0  4922.4     .03       0    5012     .11       0
Bank Sta=4922.4,5012
XS Rating Curve= 0 ,0
Exp/Cntr=0.3,0.1

Type RM Length L Ch R = 1 ,14500   ,544,544,544
BEGIN DESCRIPTION:
CARTERS SLOUGH 29.0
END DESCRIPTION:
XS GIS Cut Line= 3
      3844392.25     10069466.83      3844279.98     10069333.11
      3842758.21     10067690.89
#Sta/Elev= 30
  4825.4  123.15  4882.6  121.26  4903.5  116.88  4932.1  116.37  4985.5  111.46
  5038.4  115.74  5059.4  121.02  5066.8  121.29  5130.2  121.87  5358.7   119.3
  5638.9  119.41  5710.7  120.26  5748.8  120.37  5788.5   118.6  5809.5  120.53
  5837.8  118.94    5916  119.77  5951.2   118.4  5972.2  120.19  6043.1  118.44
  6361.7  119.91  6687.1  119.14    6758  121.88  6835.7  120.32    6864  121.91
  6927.5   119.5  7026.7  121.58  7098.8  120.86  7161.1  120.44  7238.9  123.09
#Mann= 9 ,-1 , 0
  4825.4     .11       0  4882.6     .03       0  5059.4     .11       0
  5066.8     .15       0  5358.7     .17       0  5638.9     .15       0
  5710.7     .17       0  5748.8     .15       0  7098.8     .17       0
Bank Sta=4882.6,5059.4
XS Rating Curve= 0 ,0
Exp/Cntr=0.3,0.1

Type RM Length L Ch R = 1 ,13956   ,456,456,456
BEGIN DESCRIPTION:
CARTERS SLOUGH 28.0
END DESCRIPTION:
XS GIS Cut Line= 2
       3844806.6     10069920.67      3844807.67     10069224.77
#Sta/Elev= 30
  4389.7  123.42  4419.3  121.14  4449.3   120.9  4459.3  119.95  4519.3  119.42
  4539.3  117.91  4559.3  119.59  4599.3  120.04  4619.3  118.37  4629.3  120.28
  4659.3  120.26  4679.3   121.7  4729.3  121.72  4779.3  119.41  4849.3  120.51
  4869.3  121.94  4879.3  121.47  4899.3  120.17  4909.3   116.7  4919.3  115.21
  4969.3  115.36  4995.4  111.45  5003.1  111.45  5003.6  111.95  5029.3  115.02
  5039.3  115.55  5049.3  116.91  5059.3   120.1  5079.3  121.75  5085.6  123.06
#Mann= 3 , 0 , 0
  4389.7     .11       0  4879.3     .03       0  5079.3     .11       0
Bank Sta=4879.3,5079.3
XS Rating Curve= 0 ,0
Exp/Cntr=0.3,0.1

Type RM Length L Ch R = 1 ,13500   ,500,500,500
BEGIN DESCRIPTION:
CARTERS SLOUGH 27.0
END DESCRIPTION:
XS GIS Cut Line= 3
      3845261.61     10069519.28       3845261.3     10069339.68
      3845258.24     10069249.23
#Sta/Elev= 30
  4820.4  122.59  4828.6  121.32  4838.6  118.74  4848.6  117.95  4858.6  117.46
  4868.6  119.02  4878.6  121.16  4898.6  121.13  4908.6  120.83  4918.6  118.28
  4928.6  117.08  4948.6  116.24  4958.6  115.32  4968.6  112.74  4978.6  111.21
  4984.3  110.75  4984.8  110.25  4992.5  110.25    4993  110.75  4996.8  111.76
    5000  111.76  5008.6  115.25  5018.6  116.67  5028.6  117.03  5038.6  117.86
  5058.6   120.8  5068.6   121.9  5078.7  122.12  5087.1  122.66  5090.5  122.66
#Mann= 3 , 0 , 0
  4820.4     .11       0  4908.6     .03       0  5058.6     .11       0
Bank Sta=4908.6,5058.6
XS Rating Curve= 0 ,0
Exp/Cntr=0.3,0.1

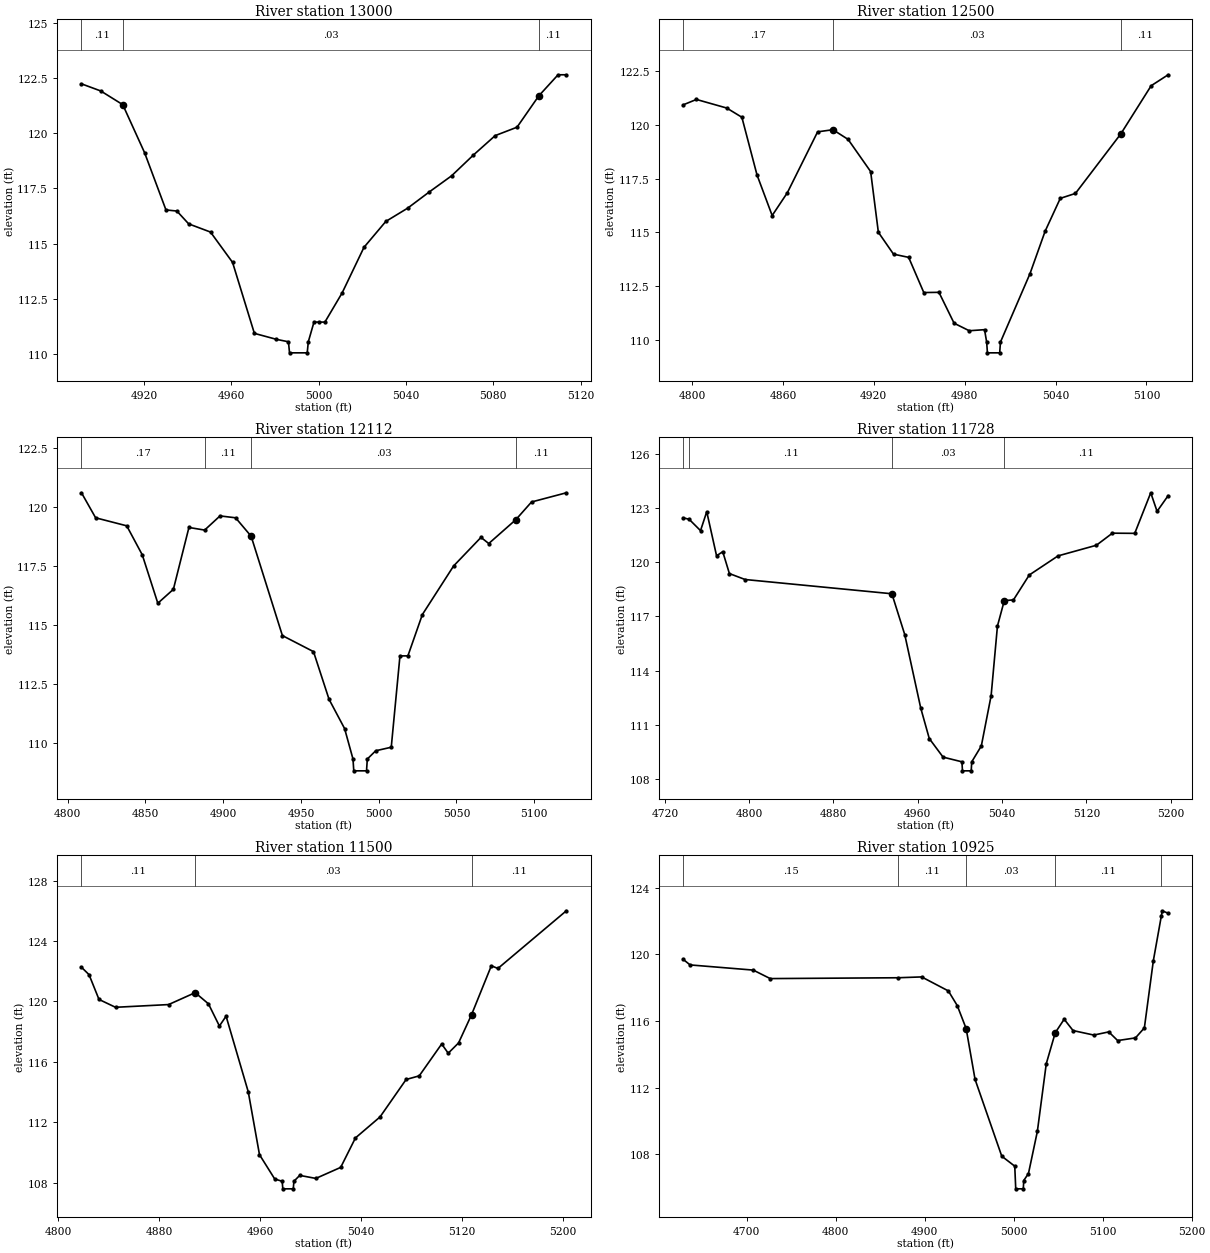
Type RM Length L Ch R = 1 ,13000   ,500,500,500
BEGIN DESCRIPTION:
CARTERS SLOUGH 26.0
END DESCRIPTION:
XS GIS Cut Line= 3
      3845747.92      10069479.8      3845760.26     10069371.91
      3845757.69     10069258.44
#Sta/Elev= 30
  4891.4  122.23  4900.2  121.91  4910.3  121.29  4920.3  119.12  4930.1  116.53
  4935.1  116.48  4940.5   115.9  4950.5  115.53  4960.6  114.16  4970.6  110.95
  4980.7  110.68  4986.2  110.57  4986.7  110.07  4994.8  110.07  4995.3  110.57
  4997.9  111.46    5000  111.46  5002.9  111.46  5010.8  112.78  5020.8  114.84
  5030.8  116.01  5040.8  116.61  5050.8  117.35  5060.9  118.07  5070.9  119.01
  5080.9  119.89  5090.9  120.27  5100.9  121.69  5109.7  122.64  5113.5  122.64
#Mann= 3 , 0 , 0
  4891.4     .11       0  4910.3     .03       0  5100.9     .11       0
Bank Sta=4910.3,5100.9
XS Rating Curve= 0 ,0
Exp/Cntr=0.3,0.1

Type RM Length L Ch R = 1 ,12500   ,388,388,388
BEGIN DESCRIPTION:
CARTERS SLOUGH 25.0
END DESCRIPTION:
XS GIS Cut Line= 3
      3846268.31     10069609.73      3846259.22     10069404.13
      3846260.08     10069289.84
#Sta/Elev= 30
  4794.2  120.94  4802.9  121.19  4822.9  120.79  4832.9  120.36  4842.9  117.67
  4852.9  115.78  4862.9  116.84  4882.9  119.68    4893  119.78    4903  119.33
  4917.9  117.83    4923     115    4933  113.98    4943  113.83    4953  112.19
    4963   112.2    4973  110.76    4983  110.41  4993.1  110.46  4994.5  109.88
    4995  109.38  5003.1  109.38  5003.6  109.88  5023.1  113.07  5033.1  115.05
  5043.1  116.58  5053.1  116.81  5083.1  119.59  5103.1  121.83  5114.3  122.34
#Mann= 3 , 0 , 0
  4794.2     .17       0    4893     .03       0  5083.1     .11       0
Bank Sta=4893,5083.1
XS Rating Curve= 0 ,0
Exp/Cntr=0.3,0.1

Type RM Length L Ch R = 1 ,12112   ,384,384,384
BEGIN DESCRIPTION:
CARTERS SLOUGH 24.0
END DESCRIPTION:
XS GIS Cut Line= 3
      3846653.73     10069620.14      3846646.19     10069414.79
      3846639.62     10069308.68
#Sta/Elev= 30
  4808.9  120.62    4818  119.56    4838  119.22    4848  117.99    4858  115.94
    4868  116.53    4878  119.15  4888.1  119.04    4898  119.64    4908  119.56
    4918  118.78  4938.1  114.57  4958.1  113.89  4968.1  111.87  4978.1  110.63
  4983.5  109.34    4984  108.84  4992.2  108.84  4992.7  109.34  4998.1  109.69
  5008.1  109.84  5013.7  113.71  5018.8  113.71  5028.1  115.46  5048.2  117.52
  5065.8  118.73  5070.8  118.47  5088.2  119.48  5098.3  120.23  5120.7  120.62
#Mann= 4 ,-1 , 0
  4808.9     .17       0  4888.1     .11       0    4918     .03       0
  5088.2     .11       0
Bank Sta=4918,5088.2
XS Rating Curve= 0 ,0
Exp/Cntr=0.3,0.1

Type RM Length L Ch R = 1 ,11728   ,228,228,228
BEGIN DESCRIPTION:
Mapping XS 2941ad7d
END DESCRIPTION:
XS GIS Cut Line= 2
      3846770.93     10069706.05      3847158.97     10069458.64
#Sta/Elev= 30
  4737.4  122.47    4743  122.39  4753.8  121.76  4759.7  122.81    4769  120.37
  4774.9  120.59  4781.2  119.38  4796.1  119.05  4935.4  118.26  4947.6     116
  4962.8  111.92  4970.9  110.23    4984   109.2  5001.9  108.94  5002.4  108.44
  5010.7  108.44  5011.2  108.94  5020.3  109.82  5029.6  112.61  5035.6  116.47
  5042.1  117.88  5050.8  117.92  5065.8   119.3  5093.1  120.36  5129.5  120.95
  5144.7  121.62  5165.9  121.61  5181.1  123.86  5187.1  122.83  5197.6   123.7
#Mann= 4 ,-1 , 0
  4737.4     .17       0    4743     .11       0  4935.4     .03       0
  5042.1     .11       0
Bank Sta=4935.4,5042.1
XS Rating Curve= 0 ,0
Exp/Cntr=0.3,0.1

Type RM Length L Ch R = 1 ,11500   ,575,575,575
BEGIN DESCRIPTION:
CARTERS SLOUGH 23.0
END DESCRIPTION:
XS GIS Cut Line= 3
      3847117.71     10069846.77      3847174.31     10069674.11
      3847228.83     10069478.68
#Sta/Elev= 30
  4818.3  122.26  4824.3  121.77  4832.2  120.13  4845.3  119.61  4887.4  119.79
  4908.5  120.58    4919  119.84  4927.7  118.37    4933  119.02  4950.6  114.01
  4959.5  109.85  4971.6  108.24  4977.5  108.09    4978  107.59  4986.3  107.59
  4986.8  108.09  4991.4  108.48  5004.2  108.28  5023.9  109.01  5035.6  110.96
  5055.1  112.35  5075.8  114.83  5086.2  115.07    5104  117.18  5109.2  116.57
  5117.4  117.25  5127.7  119.12  5143.4  122.36  5148.6  122.18  5202.9     126
#Mann= 3 , 0 , 0
  4818.3     .11       0  4908.5     .03       0  5127.7     .11       0
Bank Sta=4908.5,5127.7
XS Rating Curve= 0 ,0
Exp/Cntr=0.3,0.1

Type RM Length L Ch R = 1 ,10925   ,425,425,425
BEGIN DESCRIPTION:
CARTERS SLOUGH 22.0
END DESCRIPTION:
XS GIS Cut Line= 3
      3847754.05      10070088.8      3847748.07     10069716.43
      3847737.75     10069544.46
#Sta/Elev= 30
  4628.8   119.7  4636.5  119.37  4707.4  119.06  4726.5  118.55    4870   118.6
  4896.6  118.65  4926.6  117.81  4936.6  116.93  4946.6  115.55  4956.6   112.5
  4986.6  107.89  5001.2  107.29  5002.3  105.93  5010.8  105.93  5011.3  106.43
  5016.6  106.85  5026.6  109.38  5036.6  113.44  5046.7   115.3  5056.7  116.11
  5066.7  115.43    5090  115.16  5106.8  115.35  5116.8  114.83  5136.8  114.99
  5146.8  115.59  5156.9  119.63  5165.8  122.29  5166.9  122.62  5173.5  122.47
#Mann= 5 ,-1 , 0
  4628.8     .15       0    4870     .11       0  4946.6     .03       0
  5046.7     .11       0  5165.8     .15       0
Bank Sta=4946.6,5046.7
XS Rating Curve= 0 ,0
Exp/Cntr=0.3,0.1