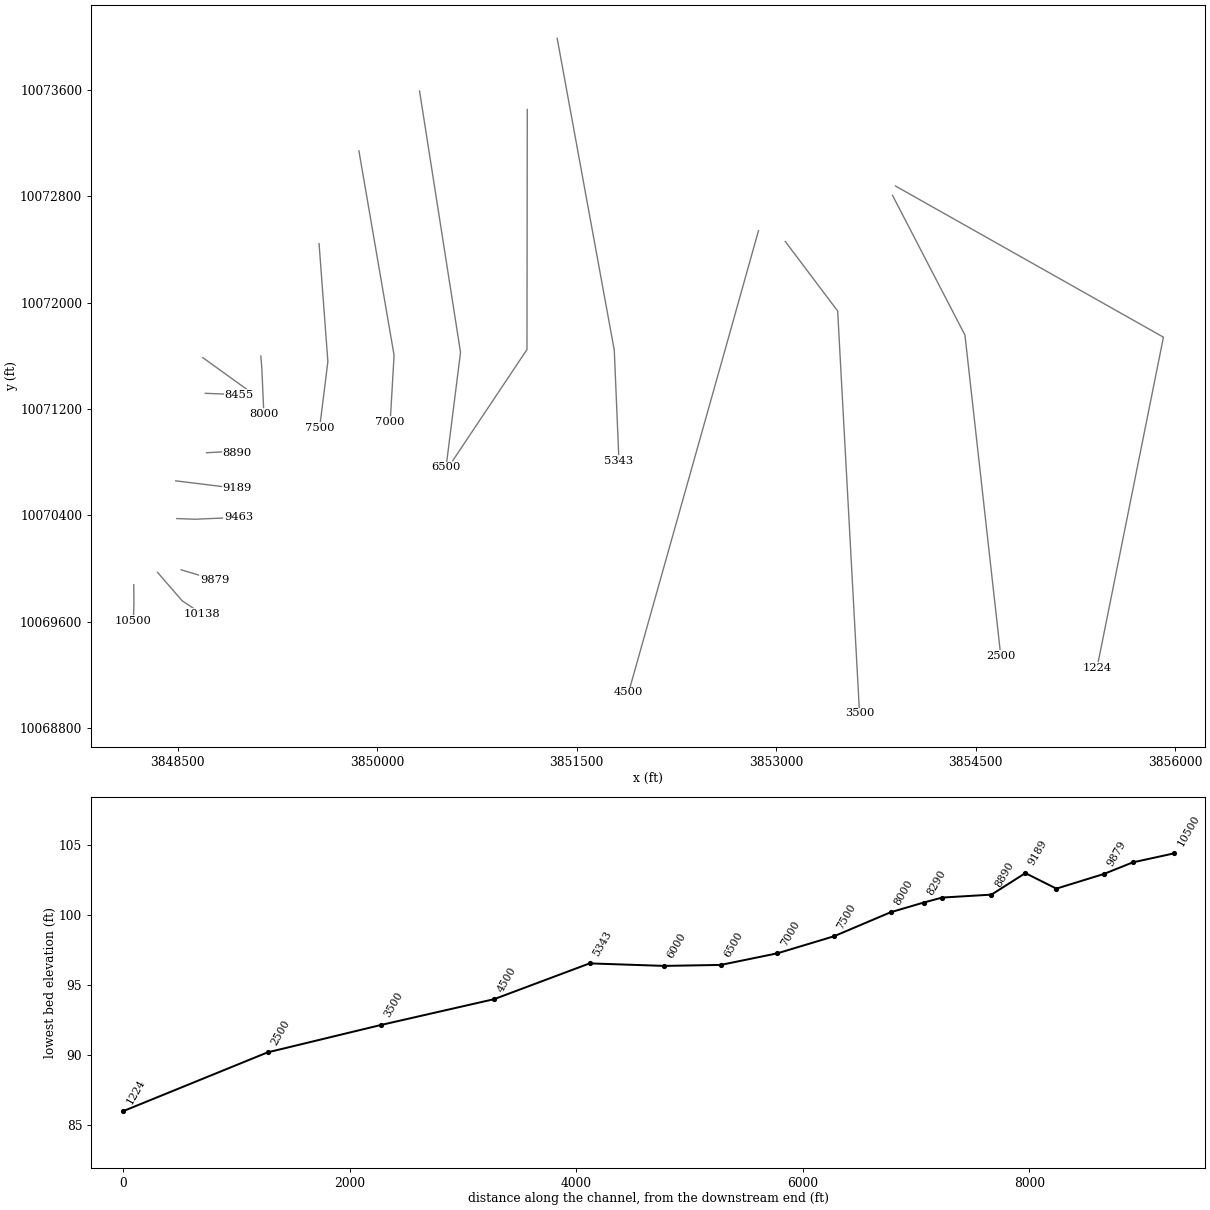
HEC-RAS study CARTERS SLOUGH.prj: CARTERS SLOUGH Base Level Engineering

--- CARTERS SLOUGH.g01 (geometry) --- (continued)

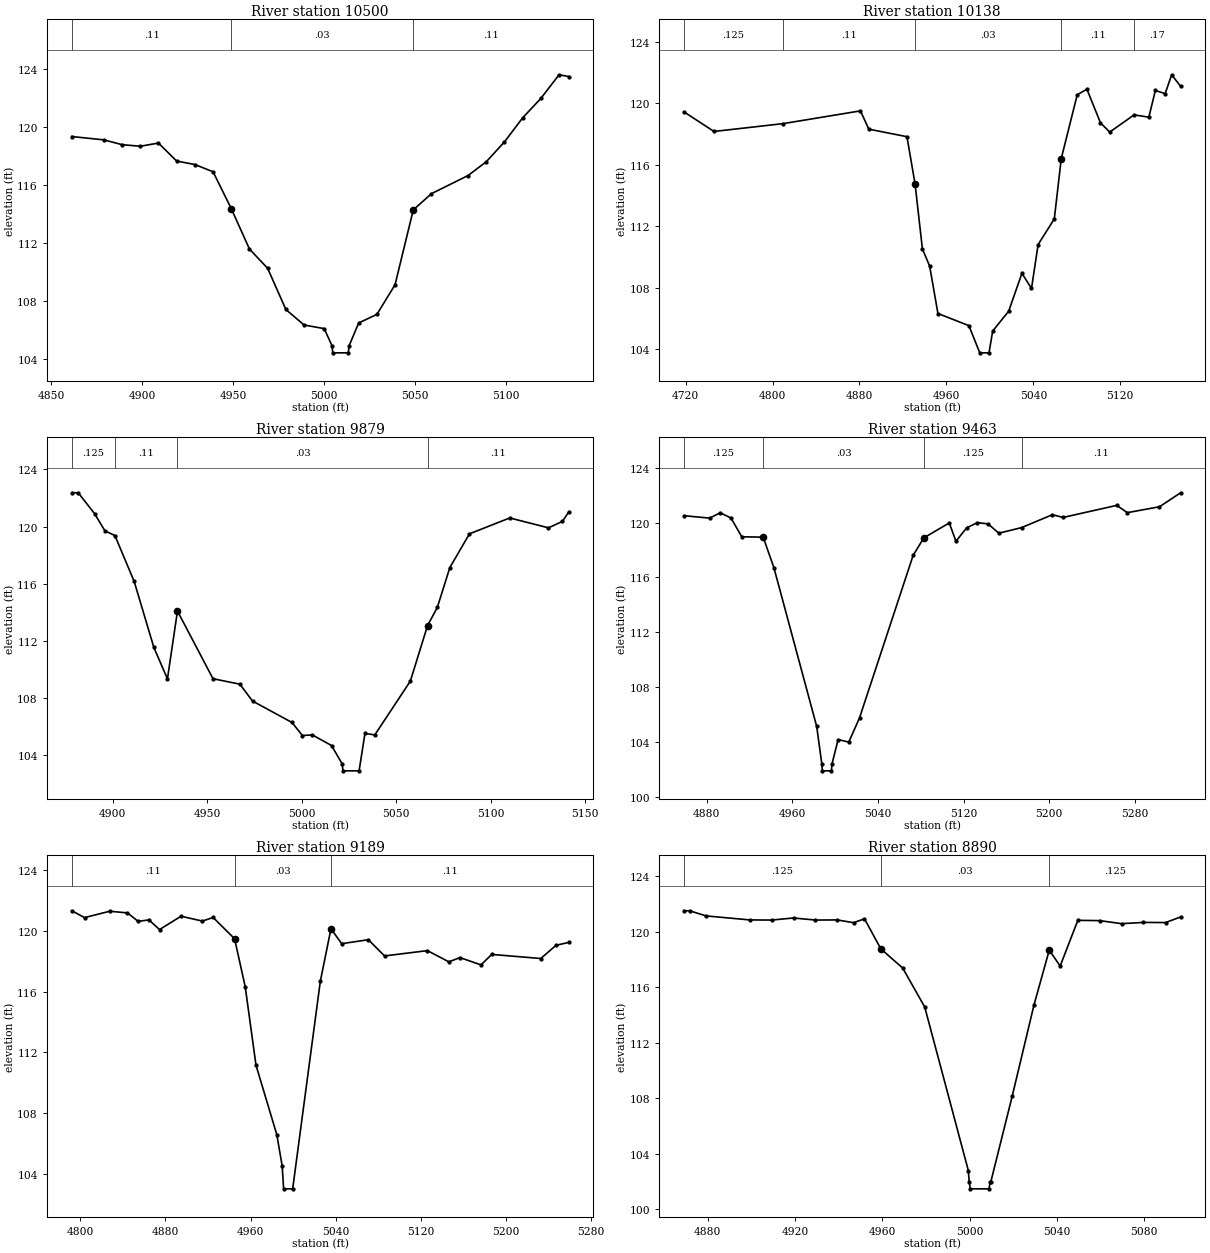
Type RM Length L Ch R = 1 ,10500   ,362,362,362
BEGIN DESCRIPTION:
CARTERS SLOUGH 21.0
END DESCRIPTION:
XS GIS Cut Line= 3
      3848170.72     10069878.68      3848172.07     10069739.99
      3848167.78     10069605.86
#Sta/Elev= 30
  4861.3  119.32  4878.9  119.09  4888.9  118.76  4898.9  118.65  4908.9  118.87
  4918.9  117.63  4928.9  117.39  4938.9  116.89  4948.9  114.35  4958.9  111.56
  4968.9  110.23  4978.9  107.39  4988.9  106.32    5000  106.07  5004.2   104.9
  5004.7   104.4  5013.2   104.4  5013.7   104.9  5018.9  106.46  5028.9  107.05
  5038.9   109.1  5048.9  114.26  5058.9  115.38    5079  116.63    5089  117.58
    5099  118.95    5109  120.61    5119  121.95    5129  123.58  5134.2  123.46
#Mann= 3 , 0 , 0
  4861.3     .11       0  4948.9     .03       0  5048.9     .11       0
Bank Sta=4948.9,5048.9
XS Rating Curve= 0 ,0
Exp/Cntr=0.3,0.1

Type RM Length L Ch R = 1 ,10138   ,259,259,259
BEGIN DESCRIPTION:
Mapping XS 565e170c
END DESCRIPTION:
XS GIS Cut Line= 3
      3848349.12       10069972.      3848533.36     10069759.03
      3848678.97     10069661.07
#Sta/Elev= 30
  4718.4  119.45  4746.1  118.17  4809.7  118.68  4880.9  119.51  4888.6  118.32
  4923.7  117.83  4931.2  114.73  4937.9  110.53  4944.6   109.4  4952.2  106.32
  4980.7  105.53  4990.7  103.76  4999.2  103.76  5002.6  105.18  5017.3  106.47
  5029.5  108.94  5038.3  107.95  5044.4  110.81  5059.3  112.48  5065.7  116.41
  5080.4  120.56  5089.3  120.92  5101.8  118.73  5110.3  118.13  5132.7  119.25
  5146.3   119.1  5152.3  120.84  5161.3  120.63  5167.3  121.86  5175.5  121.11
#Mann= 5 ,-1 , 0
  4718.4    .125       0  4809.7     .11       0  4931.2     .03       0
  5065.7     .11       0  5132.7     .17       0
Bank Sta=4931.2,5065.7
XS Rating Curve= 0 ,0
Exp/Cntr=0.3,0.1

Type RM Length L Ch R = 1 ,9879    ,416,416,416
BEGIN DESCRIPTION:
CARTERS SLOUGH 20.0
END DESCRIPTION:
XS GIS Cut Line= 2
      3848526.27     10069991.17      3848778.02     10069915.79
#Sta/Elev= 30
  4878.4  122.36  4881.8  122.36  4890.5  120.89  4895.9   119.7  4901.2  119.37
  4911.4  116.16  4921.8  111.55    4929  109.35  4934.3  114.09  4953.1  109.36
  4967.3  108.98    4974   107.8  4994.9   106.3  5000.4  105.39  5005.7  105.43
  5015.8  104.69  5021.4  103.42  5021.9  102.92  5030.4  102.92  5033.5  105.54
  5038.7  105.43  5057.5  109.19  5066.6  113.07  5071.8  114.35  5078.4  117.13
  5088.8  119.49  5110.1   120.6  5130.6  119.91    5138  120.36  5141.2     121
#Mann= 4 ,-1 , 0
  4878.4    .125       0  4901.2     .11       0  4934.3     .03       0
  5066.6     .11       0
Bank Sta=4934.3,5066.6
XS Rating Curve= 0 ,0
Exp/Cntr=0.3,0.1

Type RM Length L Ch R = 1 ,9463    ,274,274,274
BEGIN DESCRIPTION:
CARTERS SLOUGH 19.0
END DESCRIPTION:
XS GIS Cut Line= 3
      3848493.83     10070376.41      3848631.99     10070371.37
      3848957.53     10070385.48
#Sta/Elev= 30
  4858.7   120.5  4882.7  120.32  4892.7  120.71  4902.7  120.33  4912.8  118.96
  4932.8  118.93  4942.8  116.71  4982.8  105.12  4987.6  102.38  4988.1  101.88
  4996.6  101.88  4997.1  102.38  5002.8  104.16  5012.8  103.98  5022.8  105.74
  5072.9   117.6  5082.9  118.88  5106.7  119.97  5112.9  118.63  5122.9  119.61
  5132.9  119.99  5142.9   119.9    5153  119.22  5174.3  119.63    5203  120.57
    5213  120.37  5263.1  121.25  5273.1  120.72  5303.1  121.15  5322.8  122.17
#Mann= 4 ,-1 , 0
  4858.7    .125       0  4932.8     .03       0  5082.9    .125       0
  5174.3     .11       0
Bank Sta=4932.8,5082.9
XS Rating Curve= 0 ,0
Exp/Cntr=0.3,0.1

Type RM Length L Ch R = 1 ,9189    ,299,299,299
BEGIN DESCRIPTION:
Mapping XS 0f23be42
END DESCRIPTION:
XS GIS Cut Line= 2
      3848485.95     10070660.27      3848949.52     10070602.98
#Sta/Elev= 30
  4791.9  121.34  4803.9  120.89  4827.6  121.31  4844.2   121.2  4854.3  120.64
  4864.4  120.74  4874.4   120.1  4894.6  120.98  4914.7  120.66  4924.8   120.9
    4945  119.49    4955  116.31  4965.1  111.15  4984.7  106.56  4989.7  104.51
  4991.1  102.99  4999.6  102.99  5025.6  116.69  5035.6  120.15  5045.7  119.17
  5070.8  119.43    5086  118.36  5126.3  118.71  5146.5  117.97  5156.9  118.25
  5176.7  117.77  5186.8  118.46  5232.9  118.19  5247.2  119.06    5259  119.25
#Mann= 3 , 0 , 0
  4791.9     .11       0    4945     .03       0  5035.6     .11       0
Bank Sta=4945,5035.6
XS Rating Curve= 0 ,0
Exp/Cntr=0.3,0.1

Type RM Length L Ch R = 1 ,8890    ,435,435,435
BEGIN DESCRIPTION:
CARTERS SLOUGH 18.0
END DESCRIPTION:
XS GIS Cut Line= 3
      3848717.67     10070871.59      3848853.35     10070879.18
      3848944.76     10070870.68
#Sta/Elev= 29
    4869  121.52  4871.6  121.52  4879.2  121.15  4899.2  120.86  4909.2  120.85
  4919.3     121  4929.3  120.85  4939.3  120.86  4946.8  120.66  4951.8  120.94
  4959.3  118.77  4969.3  117.39  4979.4  114.58  4999.4  102.77  4999.8  101.95
  5000.3  101.45  5008.9  101.45  5009.4  101.95  5009.7  101.95  5019.5  108.13
  5029.5  114.72  5036.5  118.68  5041.5  117.53  5049.6  120.83  5059.6  120.81
  5069.7  120.59  5079.7  120.68  5089.8  120.67  5096.7  121.07
#Mann= 3 , 0 , 0
    4869    .125       0  4959.3     .03       0  5036.5    .125       0
Bank Sta=4959.3,5036.5
XS Rating Curve= 0 ,0
Exp/Cntr=0.3,0.1

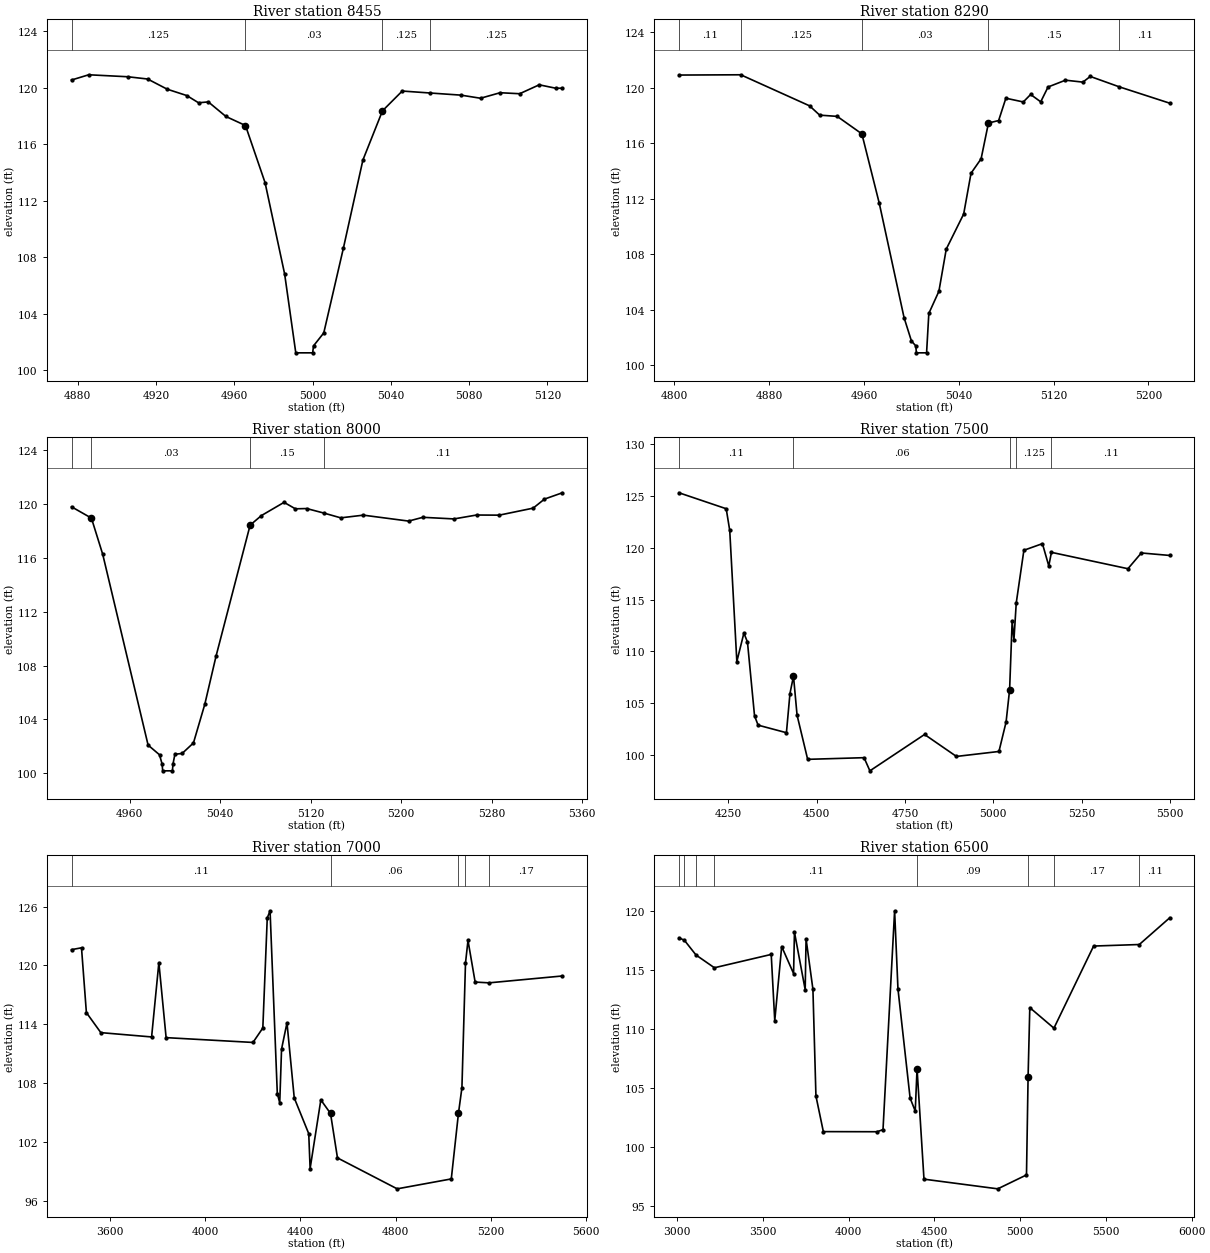
Type RM Length L Ch R = 1 ,8455    ,165,165,165
BEGIN DESCRIPTION:
CARTERS SLOUGH 17.0
END DESCRIPTION:
XS GIS Cut Line= 2
      3848709.03     10071318.64      3848959.64     10071308.87
#Sta/Elev= 28
  4876.8  120.54  4885.6  120.91  4905.6  120.77  4915.7  120.61  4925.7  119.89
  4935.7  119.44  4941.7  118.93  4946.7  118.99  4955.7  117.96  4965.7  117.32
  4975.7  113.28  4985.7  106.82  4991.4  101.24    5000  101.24  5000.5  101.74
  5005.7  102.65  5015.7  108.63  5025.7  114.88  5035.7  118.36  5045.8  119.76
  5060.1  119.62  5075.8  119.47  5085.8  119.25  5095.8  119.64  5105.8  119.57
  5115.8   120.2  5124.2  119.96  5127.6  119.96
#Mann= 4 ,-1 , 0
  4876.8    .125       0  4965.7     .03       0  5035.7    .125       0
  5060.1    .125       0
Bank Sta=4965.7,5035.7
XS Rating Curve= 0 ,0
Exp/Cntr=0.3,0.1

Type RM Length L Ch R = 1 ,8290    ,290,290,290
BEGIN DESCRIPTION:
Mapping XS 7cdbc3eb
END DESCRIPTION:
XS GIS Cut Line= 2
       3848689.1     10071587.36      3849025.01     10071345.19
#Sta/Elev= 30
  4803.9  120.91    4856  120.93  4914.1  118.69  4922.6  118.02  4937.4  117.93
  4958.2  116.67  4972.9  111.66  4993.8  103.42    5000  101.74  5003.7  101.38
  5004.2  100.88  5012.8  100.88  5014.7  103.72  5023.2  105.32  5029.4  108.36
  5044.1  110.89  5050.3  113.83  5058.8  114.87    5065  117.45  5073.6  117.63
  5079.7  119.24  5094.4  118.97  5100.6  119.51  5109.1  118.98  5115.3  120.05
    5130  120.54  5144.7   120.4  5150.9  120.81  5175.4  120.06    5218  118.88
#Mann= 5 ,-1 , 0
  4803.9     .11       0    4856    .125       0  4958.2     .03       0
    5065     .15       0  5175.4     .11       0
Bank Sta=4958.2,5065
XS Rating Curve= 0 ,0
Exp/Cntr=0.3,0.1

Type RM Length L Ch R = 1 ,8000    ,500,500,500
BEGIN DESCRIPTION:
CARTERS SLOUGH 16.0
END DESCRIPTION:
XS GIS Cut Line= 3
       3849125.7     10071598.57      3849133.21     10071507.48
      3849148.45     10071165.32
#Sta/Elev= 30
  4908.6  119.78  4926.2  118.94  4936.2  116.25  4976.3   102.1  4986.4  101.38
  4988.7  100.69  4989.2  100.19  4997.8  100.19  4998.3  100.69    5000  101.42
  5006.4  101.48  5016.4  102.26  5026.4  105.12  5036.4  108.71  5066.5  118.42
  5076.5  119.13  5096.5  120.11  5106.5  119.63  5116.5  119.65  5131.9  119.31
  5146.6  118.96  5166.6  119.16  5206.6  118.72  5219.2     119  5246.7  118.88
  5266.7  119.17  5286.7  119.16  5316.7  119.68  5326.7  120.35  5342.5  120.82
#Mann= 4 ,-1 , 0
  4908.6     .11       0  4926.2     .03       0  5066.5     .15       0
  5131.9     .11       0
Bank Sta=4926.2,5066.5
XS Rating Curve= 0 ,0
Exp/Cntr=0.3,0.1

Type RM Length L Ch R = 1 ,7500    ,500,500,500
BEGIN DESCRIPTION:
CARTERS SLOUGH 15.0
END DESCRIPTION:
XS GIS Cut Line= 3
      3849563.63     10072444.41      3849629.71     10071556.96
      3849567.86     10071061.11
#Sta/Elev= 30
  4110.1  125.31  4243.8  123.77  4253.8  121.67  4273.9  109.02  4293.9  111.77
    4304   110.9    4324  103.78  4334.1  102.88  4414.3  102.15  4424.3  105.93
  4434.3  107.61  4444.4  103.85  4474.4   99.58  4634.1   99.74  4650.6   98.47
  4805.4  101.98  4895.6   99.86    5016  100.34  5036.2  103.18  5046.2   106.3
  5053.4  112.94  5058.4   111.1    5065  114.68  5086.6  119.76  5139.1   120.4
  5157.1  118.25  5164.6  119.56  5381.2  117.98  5419.1   119.5  5499.7  119.26
#Mann= 5 ,-1 , 0
  4110.1     .11       0  4434.3     .06       0  5046.2     .11       0
    5065    .125       0  5164.6     .11       0
Bank Sta=4434.3,5046.2
XS Rating Curve= 0 ,0
Exp/Cntr=0.3,0.1

Type RM Length L Ch R = 1 ,7000    ,500,500,500
BEGIN DESCRIPTION:
CARTERS SLOUGH 14.0
END DESCRIPTION:
XS GIS Cut Line= 3
      3849863.11     10073142.33      3850127.38     10071604.78
      3850098.37     10071105.82
#Sta/Elev= 30
  3439.9  121.61  3481.8   121.8  3502.3   115.2  3562.9  113.16    3776  112.72
  3806.5  120.29  3836.9  112.65  4201.5  112.16  4242.8  113.63  4261.4  124.84
  4273.2  125.57  4303.6  106.96  4313.8  106.01  4321.4  111.48  4344.2  114.16
  4374.7  106.51  4435.5  102.87  4441.3   99.32  4486.3  106.31  4526.9  104.93
  4556.1   100.4  4806.7   97.25  5033.8   98.26  5063.8  104.93  5078.4  107.54
  5093.4  120.24  5103.9  122.55  5133.9  118.31  5192.1  118.23  5499.8  118.93
#Mann= 5 ,-1 , 0
  3439.9     .11       0  4526.9     .06       0  5063.8     .11       0
  5093.4    .125       0  5192.1     .17       0
Bank Sta=4526.9,5063.8
XS Rating Curve= 0 ,0
Exp/Cntr=0.3,0.1

Type RM Length L Ch R = 1 ,6500    ,500,500,500
BEGIN DESCRIPTION:
CARTERS SLOUGH 13.0
END DESCRIPTION:
XS GIS Cut Line= 3
      3850318.84     10073592.89      3850626.91     10071626.58
      3850517.85     10070761.02
#Sta/Elev= 30
  3009.7  117.69  3040.6   117.5  3109.1  116.24  3216.2  115.16  3547.7  116.29
  3568.3  110.67  3608.7  116.96  3678.1  114.67  3683.2  118.18  3745.8   113.3
  3750.9  117.61  3790.9  113.34  3808.5  104.29  3851.7  101.27  4165.4  101.26
  4199.7  101.44  4267.4  119.99  4286.9  113.37  4357.8  104.11  4387.7  103.01
  4398.3   106.6  4438.7   97.24    4869   96.42  5036.6    97.6  5045.9   105.9
  5055.9  111.78  5196.6  110.04  5428.1     117  5694.6  117.13  5872.4   119.4
#Mann= 8 ,-1 , 0
  3009.7    .125       0  3040.6     .11       0  3109.1    .125       0
  3216.2     .11       0  4398.3     .09       0  5045.9     .11       0
  5196.6     .17       0  5694.6     .11       0
Bank Sta=4398.3,5045.9
XS Rating Curve= 0 ,0
Exp/Cntr=0.3,0.1

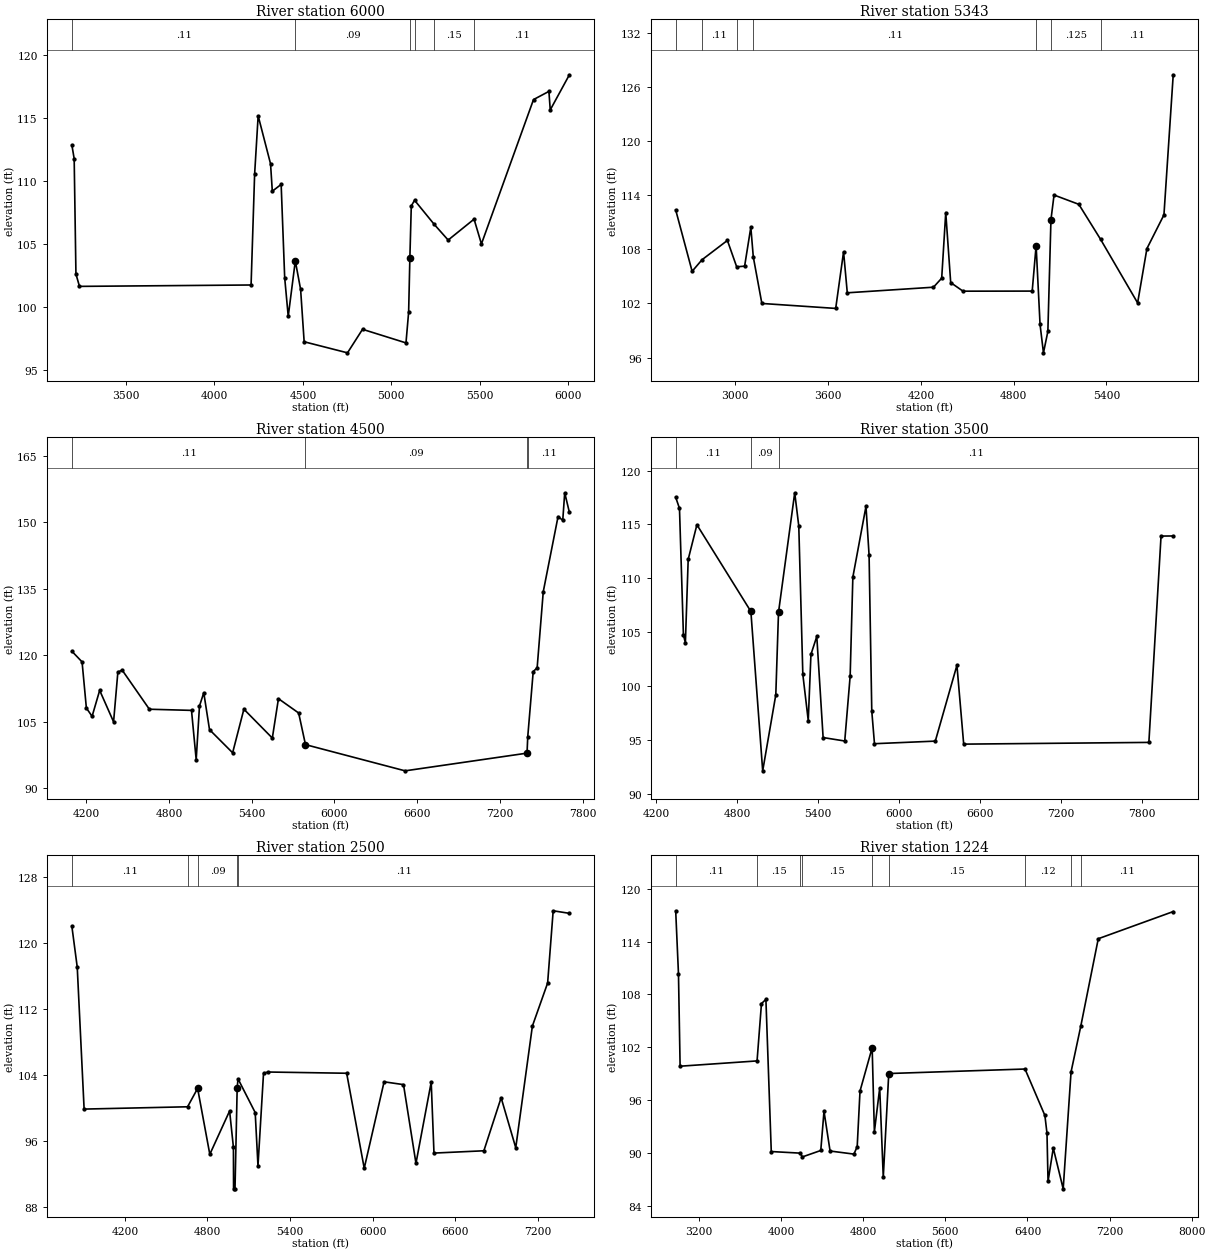
Type RM Length L Ch R = 1 ,6000    ,657,657,657
BEGIN DESCRIPTION:
CARTERS SLOUGH 12.0
END DESCRIPTION:
XS GIS Cut Line= 3
      3851128.62      10073454.2      3851126.44      10071648.1
      3850567.85     10070811.07
#Sta/Elev= 30
  3193.9  112.86    3207  111.78    3217  102.61    3237  101.63    4207  101.74
    4227  110.53    4247  115.18    4317  111.37    4327  109.19    4377  109.73
    4397  102.31    4417   99.25    4457  103.65    4487  101.39    4507   97.23
    4752   96.35    4837   98.22  5082.6   97.14  5097.6   99.58  5104.6  103.89
  5112.6  108.02  5131.2  108.47  5242.6  106.55    5321  105.31  5467.5  106.97
  5509.1     105  5803.5  116.47  5890.6  117.12  5898.1  115.65  6006.3  118.44
#Mann= 6 ,-1 , 0
  3193.9     .11       0    4457     .09       0  5104.6    .125       0
  5131.2     .11       0  5242.6     .15       0  5467.5     .11       0
Bank Sta=4457,5104.6
XS Rating Curve= 0 ,0
Exp/Cntr=0.3,0.1

Type RM Length L Ch R = 1 ,5343    ,843,843,843
BEGIN DESCRIPTION:
CARTERS SLOUGH 11.0
END DESCRIPTION:
XS GIS Cut Line= 3
      3851353.43     10073989.02      3851782.67     10071642.66
      3851817.85     10070811.11
#Sta/Elev= 30
  2614.7  112.36    2721  105.56  2784.9  106.84  2949.1  108.98  3009.1  106.06
  3060.5  106.13  3100.6  110.44  3116.6  107.15    3172     102  3649.5  101.45
  3700.4  107.72  3724.4  103.18  4281.8   103.8    4335   104.8  4361.2  112.07
  4393.2  104.31    4473  103.36  4920.3  103.37  4945.6   108.4  4971.1   99.67
  4993.1   96.53  5021.6    98.9  5041.6  111.29  5061.6  114.01  5221.8  112.98
  5362.6   109.1  5602.1  102.06  5662.2  108.08  5772.3  111.81  5832.3  127.33
#Mann= 7 ,-1 , 0
  2614.7    .125       0  2784.9     .11       0  3009.1    .125       0
  3116.6     .11       0  4945.6     .03       0  5041.6    .125       0
  5362.6     .11       0
Bank Sta=4945.6,5041.6
XS Rating Curve= 0 ,0
Exp/Cntr=0.3,0.1

Type RM Length L Ch R = 1 ,4500    ,1000,1000,1000
BEGIN DESCRIPTION:
CARTERS SLOUGH 9.0
END DESCRIPTION:
XS GIS Cut Line= 3
      3852866.72     10072542.42       3852622.9     10071672.03
      3851890.16     10069068.47
#Sta/Elev= 30
  4096.1  120.94  4170.2  118.53  4201.4  108.12  4242.9  106.26  4297.9  112.11
  4398.7  105.02  4429.8  116.24    4461  116.68  4658.3  107.86  4963.9   107.6
  4997.9   96.48  5021.8  108.59  5052.9  111.58  5094.5  103.26  5262.2   98.04
  5343.8  107.87  5550.1  101.36  5594.5  110.24  5741.1  107.01  5790.5   99.88
  6513.1   93.97  7397.5   97.96  7402.7  101.65  7442.3  116.35  7470.8  117.19
  7515.2  134.36  7622.5   151.3  7656.6  150.46  7670.8  156.66  7704.7  152.25
#Mann= 4 ,-1 , 0
  4096.1     .11       0  5790.5     .09       0  7397.5     .08       0
  7402.7     .11       0
Bank Sta=5790.5,7397.5
XS Rating Curve= 0 ,0
Exp/Cntr=0.3,0.1

Type RM Length L Ch R = 1 ,3500    ,1000,1000,1000
BEGIN DESCRIPTION:
CARTERS SLOUGH 7.0
END DESCRIPTION:
XS GIS Cut Line= 3
      3853067.87     10072461.04      3853461.76     10071937.59
      3853626.28     10068910.95
#Sta/Elev= 30
  4344.9  117.52    4373  116.49  4402.1  104.74  4416.7  104.01  4437.5  111.75
  4502.1  114.97  4901.9  106.92  4989.5   92.12  5086.6   99.18  5106.7  106.84
  5226.8  117.94  5256.9  114.85  5286.9  101.07    5327   96.79    5347  102.93
  5390.3   104.6  5437.2   95.21  5597.4   94.89  5637.5  100.92  5657.5  110.11
  5754.8  116.68  5777.7  112.15  5797.7   97.67  5817.7   94.64  6268.4   94.88
  6428.6  101.92  6478.7    94.6  7850.7   94.76  7940.9  113.92  8031.1  113.93
#Mann= 3 , 0 , 0
  4344.9     .11       0  4901.9     .09       0  5106.7     .11       0
Bank Sta=4901.9,5106.7
XS Rating Curve= 0 ,0
Exp/Cntr=0.3,0.1

Type RM Length L Ch R = 1 ,2500    ,1276,1276,1276
BEGIN DESCRIPTION:
CARTERS SLOUGH 5.0
END DESCRIPTION:
XS GIS Cut Line= 3
      3853873.67     10072808.51      3854418.61      10071756.8
      3854687.89     10069344.08
#Sta/Elev= 30
  3815.5  122.04  3854.6  117.07  3904.5   99.84  4655.7  100.12  4728.6  102.35
  4817.1   94.35  4960.8   99.61  4988.5    95.2  4989.6   90.16    5000   90.16
  5015.8  102.43  5021.8  103.51  5146.6   99.42  5166.8   92.95    5207  104.16
  5237.2  104.34  5810.7  104.19  5938.2   92.66  6082.4  103.15  6223.3  102.81
  6313.8   93.26  6424.5  103.11  6444.6    94.5  6806.9   94.78  6932.1  101.22
  7038.3   95.15  7159.1  109.92  7269.7  115.14    7310  123.91  7427.7   123.6
#Mann= 5 ,-1 , 0
  3815.5     .11       0  4655.7     .15       0  4728.6     .09       0
  5015.8     .15       0  5021.8     .11       0
Bank Sta=4728.6,5015.8
XS Rating Curve= 0 ,0
Exp/Cntr=0.3,0.1

Type RM Length L Ch R = 1 ,1224    ,0,0,0
BEGIN DESCRIPTION:
CARTERS SLOUGH 3.0
END DESCRIPTION:
XS GIS Cut Line= 3
      3853896.78     10072877.98      3855910.71      10071740.8
      3855411.81     10069254.98
#Sta/Elev= 30
  2972.3  117.49  2999.4  110.34  3015.3   99.86  3765.2  100.46  3808.1  106.96
  3851.4  107.44  3903.7   90.18  4185.8      90  4206.4   89.57  4386.1    90.3
  4417.5   94.75  4476.7   90.24  4709.1   89.89    4741   90.74  4768.4   97.04
  4886.8  101.96  4908.4   92.42  4960.3   97.38  4995.1   87.27  5048.5   99.03
  6376.2   99.54    6570   94.27  6590.4   92.26  6600.6   86.79  6651.6   90.57
  6748.3   85.95  6824.9   99.21  6920.4  104.44  7090.1  114.32  7820.5   117.4
#Mann= 9 ,-1 , 0
  2972.3     .11       0  3765.2     .15       0  4185.8     .11       0
  4206.4     .15       0  4886.8     .07       0  5048.5     .15       0
  6376.2     .12       0  6824.9     .17       0  6920.4     .11       0
Bank Sta=4886.8,5048.5
XS Rating Curve= 0 ,0
Exp/Cntr=0.3,0.1

Chan Stop Cuts=-1
Use User Specified Reach Order=0
Composite Channel Slope=5