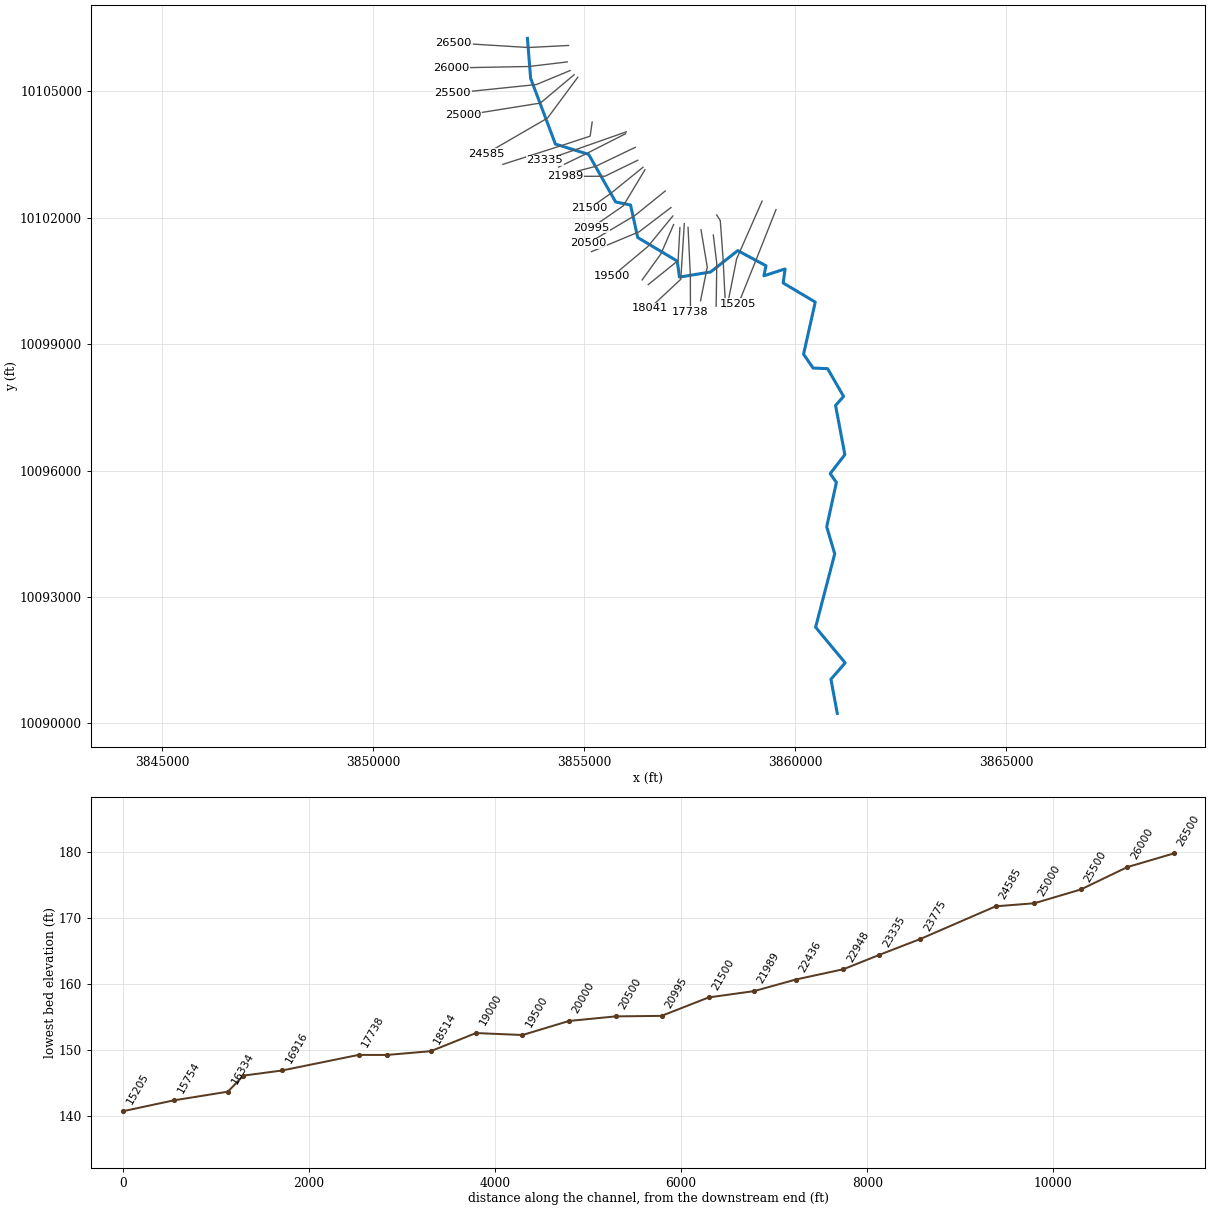
--- CRYSTAL CREEK TRIBUTARY NO 1.prj (project) ---

Proj Title=CRYSTAL CREEK TRIBUTARY NO 1 Base Level Engineering
Current Plan=p01
Default Exp/Contr=0.3,0.1
English Units
Geom File=g01
Flow File=f01
Plan File=p01
Y Axis Title=Elevation
X Axis Title(PF)=Main Channel Distance
X Axis Title(XS)=Station
BEGIN DESCRIPTION:
CRYSTAL CREEK TRIBUTARY NO 1
END DESCRIPTION:
DSS File=dss
DSS Export Rating Curves= 0
DSS Export Rating Curve Sorted= 0
DSS Export Volume Flow Curves= 0
DXF OffsetX= 0
DXF OffsetY= 0
DXF ScaleX= 1
DXF ScaleY= 10

--- CRYSTAL CREEK TRIBUTARY NO 1.p01 (plan) ---

Plan Title=Multiple Run
Program Version=4.10
Short Identifier=Multiple Run
Geom File=g01
Flow File=f01
Subcritical Flow
K Sum by GR= 0
Std Step Tol= 0.01
Critical Tol= 0.01
Num of Std Step Trials= 20
Max Error Tol= 0.3
Flow Tol Ratio= 0.001
Split Flow NTrial= 30
Split Flow Tol= 0.02
Split Flow Ratio= 0.02
Log Output Level= 0
Friction Slope Method= 1
Unsteady Friction Slope Method= 2
Unsteady Bridges Friction Slope Method= 1
Parabolic Critical Depth
Global Vel Dist= 1 , 1 , 1
Global Log Level= 0
CheckData=True
Encroach Param=-1 ,0,0, 0
BEGIN DESCRIPTION:
Multiple Run
END DESCRIPTION:
Computation Interval=1HOUR
Output Interval=1HOUR
Run HTab= 0
Run UNet= 0
Run PostProcess= 0
Run WQNet= 0
UNET Theta= 1
UNET Theta Warmup= 1
UNET ZTol= 0.02
UNET ZSATol= 0.05
UNET MxIter= 20
UNET MaxInSteps= 0
UNET DtIC= 0
UNET DtMin= 0
UNET MaxCRTS= 20
UNET WFStab= 2
UNET SFStab= 1
UNET WFX= 1
UNET SFX= 1
UNET DSS MLevel= 4
UNET DZMax Abort= 100
UNET Convert EG Bridges= 0
UNET Use Existing IB Tables=-1
UNET Froude Reduction=False
UNET Froude Limit= 1
UNET Froude Power= 10
UNET Time Slicing=0,0, 5
UNET Junction Losses=0
Instantaneous Interval=1HOUR
DSS File=dss
Write IC File= 0
Write IC File at Sim End=0
Echo Input=False
Echo Parameters=False
Echo Output=False
Write Detailed= 0
WQ AD Non Conservative
WQ ULTIMATE=-1
WQ Max Comp Step=1HOUR
WQ Output Interval=15MIN
WQ Output Selected Increments= 0
WQ Output face flow=0
WQ Output face velocity=0
WQ Output face area=0
WQ Output face dispersion=0
WQ Output cell volume=0
WQ Output cell surface area=0
WQ Output cell continuity=0
WQ Output cumulative cell continuity=0
WQ Output face conc=0
WQ Output face dconc_dx=0
WQ Output face courant=0
WQ Output face peclet=0
WQ Output face adv mass=0
WQ Output face disp mass=0
WQ Output cell mass=0
WQ Output cell source sink temp=0
WQ Output cell source sink nsm=0
WQ Output MaxMinRange=-1
WQ Daily Max Min Mean=-1
WQ Daily Range=0
WQ Daily Time=0
WQ Create Restart=0
WQ Fixed Restart=0
WQ System Summary=0
WQ Use Fixed Temperature=0
Sorting and Armoring Iterations= 10
XS Update Threshold= 0.02
Hydraulics Update Threshold= 0.02
Energy Slope Method= 1
Volume Change Method= 0
XS Weighting Method= 0
Number of US Weighted Cross Sections= 1
Number of DS Weighted Cross Sections= 1
Upstream XS Weight=0.25
Main XS Weight=0.5
Downstream XS Weight=0.25
Number of DS XS's Weighted with US Boundary= 1
Upstream Boundary Weight= 1
Weight of XSs Associated with US Boundary= 0
Number of US XS's Weighted with DS Boundary= 1
Downstream Boundary Weight= 0.5
Weight of XSs Associated with DS Boundary= 0.5
Sediment Output Level= 4
Mass or Volume Output= 0
Output Increment Type= 1
Profile and TS Output Increment= 10
XS Output Flag= 0
XS Output Increment= 10
Disregard all LS=0
Disregard all Conn=0
Disregard all Breaches=0
Disregard all Pumps=0

--- CRYSTAL CREEK TRIBUTARY NO 1.f01 (steady flow) ---

Flow Title=Multiple
Program Version=4.10
Number of Profiles= 7
Profile Names=10-year,25-year,50-year,1pct_min,100-year,1pct_plu,500-year
River Rch & RM=CRYSTAL CREEK TR,Reach-1         ,26500
     691     921    1231     540    1630    4923    2960
River Rch & RM=CRYSTAL CREEK TR,Reach-1         ,22436
    1057    1443    1960     873    2636    7961    4936
River Rch & RM=CRYSTAL CREEK TR,Reach-1         ,15754
    1386    1918    2628    1180    3565   10766    6784
River Rch & RM=CRYSTAL CREEK TR,Reach-1         ,10940
    1573    2187    3005    1353    4087   12343    7817
River Rch & RM=CRYSTAL CREEK TR,Reach-1         ,3500
    1750    2444    3370    1521    4594   13874    8839
Boundary for River Rch & Prof#=CRYSTAL CREEK TR,Reach-1         , 1
Up Type= 0
Dn Type= 3
Dn Slope=0.01
Boundary for River Rch & Prof#=CRYSTAL CREEK TR,Reach-1         , 2
Up Type= 0
Dn Type= 3
Dn Slope=0.01
Boundary for River Rch & Prof#=CRYSTAL CREEK TR,Reach-1         , 3
Up Type= 0
Dn Type= 3
Dn Slope=0.01
Boundary for River Rch & Prof#=CRYSTAL CREEK TR,Reach-1         , 4
Up Type= 0
Dn Type= 3
Dn Slope=0.01
Boundary for River Rch & Prof#=CRYSTAL CREEK TR,Reach-1         , 5
Up Type= 0
Dn Type= 3
Dn Slope=0.01
Boundary for River Rch & Prof#=CRYSTAL CREEK TR,Reach-1         , 6
Up Type= 0
Dn Type= 3
Dn Slope=0.01
Boundary for River Rch & Prof#=CRYSTAL CREEK TR,Reach-1         , 7
Up Type= 0
Dn Type= 3
Dn Slope=0.01
DSS Import GetInterval= 0
DSS Import GetPeak= 0
DSS Import FillOption= 0

--- CRYSTAL CREEK TRIBUTARY NO 1.g01 (geometry) ---

Geom Title=Existing Conditions
Program Version=4.10

River Reach=CRYSTAL CREEK TR,Reach-1
Reach XY= 30
       3853652.8     10106253.04      3853728.24     10105306.86
      3854315.37     10103744.71      3855103.97     10103499.53
      3855744.38     10102370.48       3856098.1     10102297.99
      3856267.55     10101527.02      3857204.57     10100967.85
       3857257.1      10100588.3      3857995.88      10100710.3
      3858638.24     10101216.86      3859308.15     10100857.64
      3859258.62      10100618.9      3859761.44       10100783.
       3859716.2     10100448.95      3860476.51     10099996.02
      3860199.47     10098759.35      3860425.84     10098430.42
      3860769.28     10098415.97      3861148.03     10097758.31
        3860958.     10097544.51      3861178.13     10096374.97
      3860830.07     10095925.97      3860978.08      10095717.3
      3860747.93     10094664.12      3860937.89     10094022.94
      3860484.74     10092282.36      3861185.26     10091436.01
      3860848.33     10091047.09      3860998.24     10090237.84

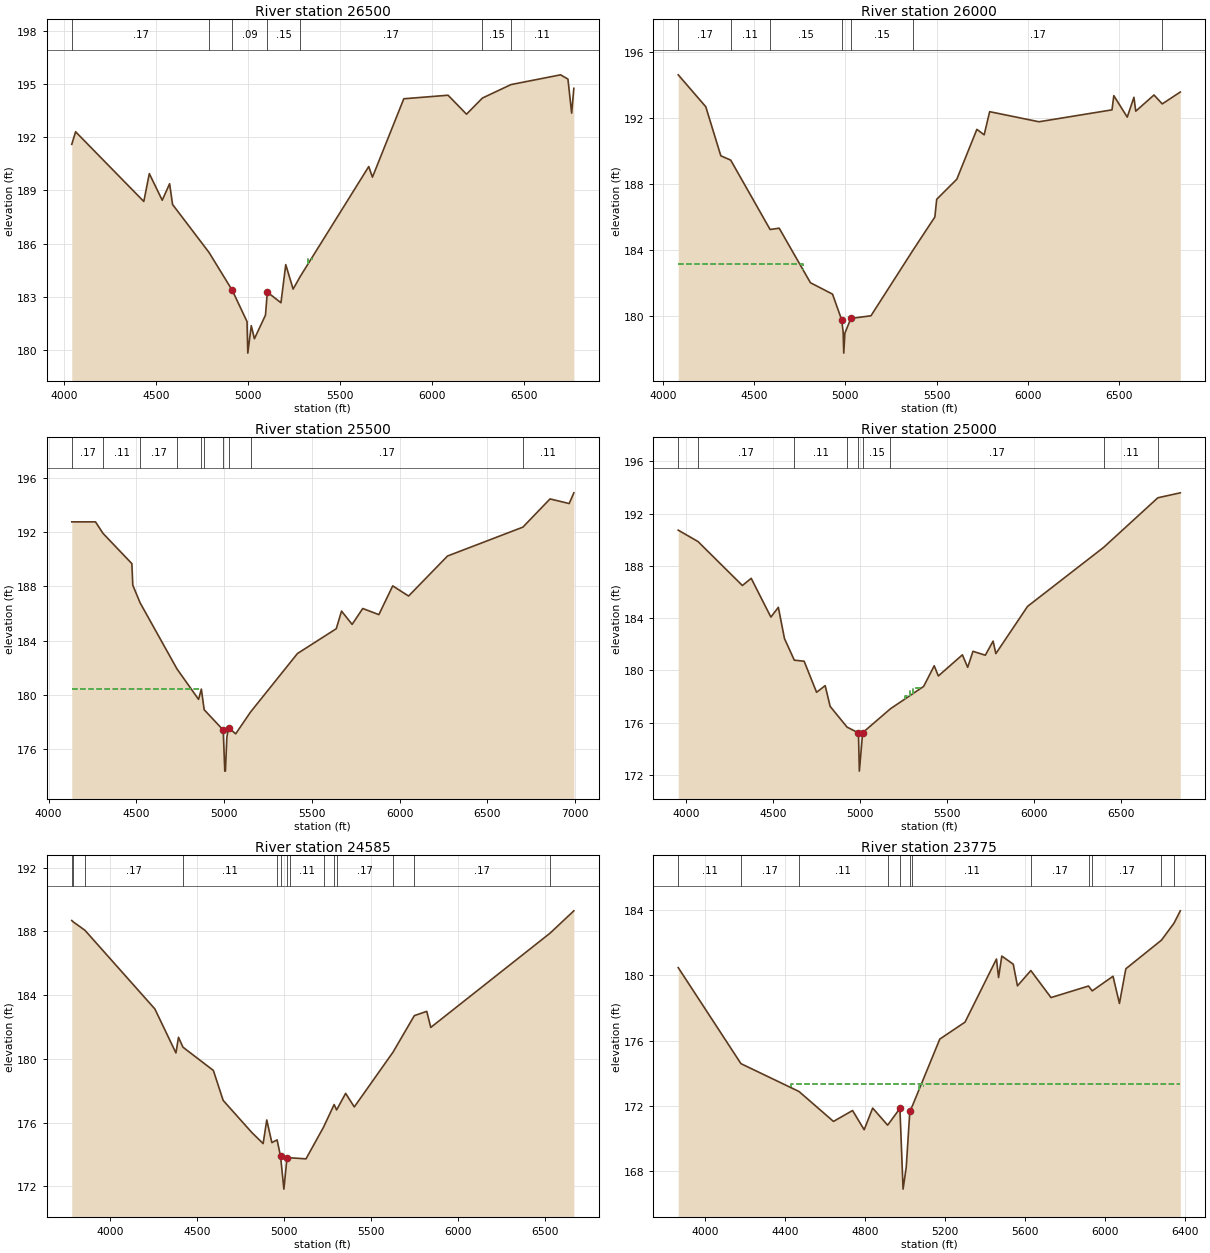
Type RM Length L Ch R = 1 ,26500   ,500,500,500
BEGIN DESCRIPTION:
CRYSTAL CREEK TRIBUTARY NO 1 53.0
END DESCRIPTION:
XS GIS Cut Line= 3
      3854628.64     10106084.02      3853671.08     10106035.18
      3851905.96     10106144.34
#Sta/Elev= 30
  4041.2   191.6    4062  192.31  4432.5  188.38  4462.5  189.95  4532.6  188.45
  4572.7  189.38  4588.8  188.21  4786.6  185.51  4913.1  183.37  4993.2  181.61
  4997.4  179.83  5016.3  181.38  5033.3  180.64  5093.4  181.97  5103.4  183.27
  5177.5  182.67  5203.6  184.82  5243.7  183.44  5280.9  184.13  5654.5  190.35
  5674.5  189.75  5844.8  194.17  6085.3  194.37  6185.5   193.3  6271.7  194.21
  6427.2  194.97  6696.5  195.52  6736.5  195.28  6756.6  193.36  6768.5  194.76
#Mann= 7 ,-1 , 0
  4041.2     .17       0  4786.6     .15       0  4913.1     .09       0
  5103.4     .15       0  5280.9     .17       0  6271.7     .15       0
  6427.2     .11       0
#XS Ineff= 2 ,-1
  5203.6  5323.9  184.82  5323.9  5353.9  185.11
Permanent Ineff=
       F       F
Bank Sta=4913.1,5103.4
XS Rating Curve= 0 ,0
Exp/Cntr=0.3,0.1

Type RM Length L Ch R = 1 ,26000   ,500,500,500
BEGIN DESCRIPTION:
CRYSTAL CREEK TRIBUTARY NO 1 52.0
END DESCRIPTION:
XS GIS Cut Line= 3
      3854596.89     10105693.44      3853688.24     10105584.99
      3851853.86     10105550.59
#Sta/Elev= 30
  4084.9   194.6  4235.7  192.67  4318.2   189.7  4372.2  189.44  4588.1  185.24
  4637.8  185.32    4809  182.02  4929.9  181.33  4980.2  179.77  4988.1  179.04
  4991.4  177.76  4997.7  178.97  5030.4  179.86  5140.4  180.02    5369  183.96
  5490.5     186  5500.5  187.07  5610.5  188.28  5720.5   191.3  5760.5  190.97
  5790.5  192.37  6060.6  191.76  6460.6  192.48  6470.6  193.34    6544  192.04
  6580.7  193.24  6590.7   192.4  6690.7  193.38  6735.7  192.84  6834.7  193.56
#Mann= 7 ,-1 , 0
  4084.9     .17       0  4372.2     .11       0  4588.1     .15       0
  4980.2     .09       0  5030.4     .15       0    5369     .17       0
  6735.7     .11       0
#XS Ineff= 2 , 0
       0  4768.8  183.13               0
Permanent Ineff=
       F       F
Bank Sta=4980.2,5030.4
XS Rating Curve= 0 ,0
Exp/Cntr=0.3,0.1

Type RM Length L Ch R = 1 ,25500   ,500,500,500
BEGIN DESCRIPTION:
CRYSTAL CREEK TRIBUTARY NO 1 51.0
END DESCRIPTION:
XS GIS Cut Line= 3
      3854664.96     10105489.05      3853863.55     10105156.17
      3851881.36     10104951.78
#Sta/Elev= 30
  4132.2  192.75  4267.4  192.75  4310.2   191.9  4474.5  189.67  4479.9  188.08
  4521.2  186.79  4731.5  181.91  4854.6  179.66  4870.5  180.42  4886.5   178.9
    4995   177.4  5004.1  174.37  5007.6  174.37  5015.8  176.87  5025.8  177.57
    5066  177.12  5150.9  178.73  5417.9  183.04  5639.1  184.87  5669.2  186.17
  5729.5  185.19  5789.9  186.36  5881.9  185.91  5960.8  188.03  6051.2  187.28
  6272.9  190.23  6702.4  192.36  6856.9  194.44  6966.1   194.1  6992.7  194.89
#Mann= 10 ,-1 , 0
  4132.2     .17       0  4310.2     .11       0  4521.2     .17       0
  4731.5     .15       0  4870.5     .11       0  4886.5     .15       0
    4995     .09       0  5025.8     .15       0  5150.9     .17       0
  6702.4     .11       0
#XS Ineff= 2 , 0
       0  4870.4  180.44               0
Permanent Ineff=
       F       F
Bank Sta=4995,5025.8
XS Rating Curve= 0 ,0
Exp/Cntr=0.3,0.1

Type RM Length L Ch R = 1 ,25000   ,415,415,415
BEGIN DESCRIPTION:
CRYSTAL CREEK TRIBUTARY NO 1 50.0
END DESCRIPTION:
XS GIS Cut Line= 3
      3854760.33     10105389.11      3853958.24     10104716.95
      3852140.34     10104425.59
#Sta/Elev= 30
  3953.5  190.74    4067  189.87  4322.5   186.5  4373.2  187.05  4486.4  184.08
  4529.3  184.83  4564.4  182.44  4621.1  180.78  4677.6   180.7  4749.2  178.32
  4798.6  178.83  4827.2  177.24  4924.6  175.65  4989.9  175.21  4995.2  172.28
 5014.05175.2219  5174.2  177.06    5365  178.77  5425.7  180.35  5449.5  179.57
  5587.8  181.19  5618.2  180.23  5648.6  181.46  5719.5  181.16  5764.4  182.24
  5780.2  181.28  5962.5   184.9  6400.9  189.43  6711.9  193.22  6841.1   193.6
#Mann= 9 ,-1 , 0
  3953.5     .11       0    4067     .17       0  4621.1     .11       0
  4924.6     .15       0  4989.9     .09       0 5014.05     .15       0
  5174.2     .17       0  6400.9     .11       0  6711.9     .17       0
#XS Ineff= 4 ,-1
  4798.6  4713.5  178.83  5258.5    5284  178.06    5284  5304.2  178.39
  5304.2  5354.9  178.68
Permanent Ineff=
       F       F       F       F
Bank Sta=4989.9,5014.05
XS Rating Curve= 0 ,0
Exp/Cntr=0.3,0.1

Type RM Length L Ch R = 1 ,24585   ,810,810,810
BEGIN DESCRIPTION:
CRYSTAL CREEK TRIBUTARY NO 1 49.0
END DESCRIPTION:
XS GIS Cut Line= 3
      3854846.64     10105330.08      3854130.26     10104362.41
      3852676.86     10103519.36
#Sta/Elev= 30
  3779.5  188.68  3788.8  188.59  3855.1  188.07  4256.9  183.13  4377.9  180.37
  4392.5  181.35  4418.3  180.73  4592.9  179.27  4649.2  177.39  4814.1  175.37
  4878.8  174.68  4899.7  176.16  4928.9  174.74    4959  174.91    4979  173.87
  4998.1  171.82  5015.6  173.75  5030.5  173.79    5125  173.72  5225.8  175.71
  5286.7  177.13  5300.9  176.79  5352.7  177.83  5402.5  176.98    5625  180.42
  5747.3  182.71  5818.8  182.98  5841.8  181.97  6528.4   187.9  6663.7  189.29
#Mann= 14 ,-1 , 0
  3779.5     .17       0  3788.8     .11       0  3855.1     .17       0
  4418.3     .11       0    4959     .15       0    4979     .09       0
  5015.6     .15       0  5030.5     .11       0  5225.8     .15       0
  5286.7     .11       0  5300.9     .17       0    5625     .11       0
  5747.3     .17       0  6528.4     .11       0
#XS Ineff= 2 , 0
       0  4899.7  176.16               0
Permanent Ineff=
       F       F
Bank Sta=4979,5015.6
XS Rating Curve= 0 ,0
Exp/Cntr=0.3,0.1

Type RM Length L Ch R = 1 ,23775   ,440,440,440
BEGIN DESCRIPTION:
CRYSTAL CREEK TRIBUTARY NO 1 48.0
END DESCRIPTION:
XS GIS Cut Line= 4
      3855187.73     10104268.19      3855139.27     10103931.82
      3854385.64     10103684.81      3853071.71     10103263.31
#Sta/Elev= 30
  3866.2  180.48  4180.1  174.58  4470.5  172.87  4643.1  171.03  4738.6   171.7
  4796.8  170.52  4839.4  171.85  4914.2   170.8  4975.7  171.83  4991.5  166.87
  5007.3  168.22  5025.4  171.68  5037.9  171.98  5175.3  176.09  5301.4  177.13
  5458.9  181.01  5469.4  179.87  5485.6  181.19  5542.9  180.69  5563.9  179.36
  5630.9   180.3  5731.9  178.64  5919.6  179.35    5938  179.05  6042.2  179.95
  6074.3  178.28  6106.4  180.41  6284.8  182.17  6347.4  183.21    6379  183.97
#Mann= 12 ,-1 , 0
  3866.2     .11       0  4180.1     .17       0  4470.5     .11       0
  4914.2     .15       0  4975.7     .09       0  5025.4     .15       0
  5037.9     .11       0  5630.9     .17       0  5919.6     .11       0
    5938     .17       0  6284.8     .11       0  6347.4     .17       0
#XS Ineff= 3 ,-1
  4428.5  4333.8  173.36  4333.8  4312.8  173.43  5070.3  5094.9  173.23
Permanent Ineff=
       F       F       F
Bank Sta=4975.7,5025.4
XS Rating Curve= 0 ,0
Exp/Cntr=0.3,0.1

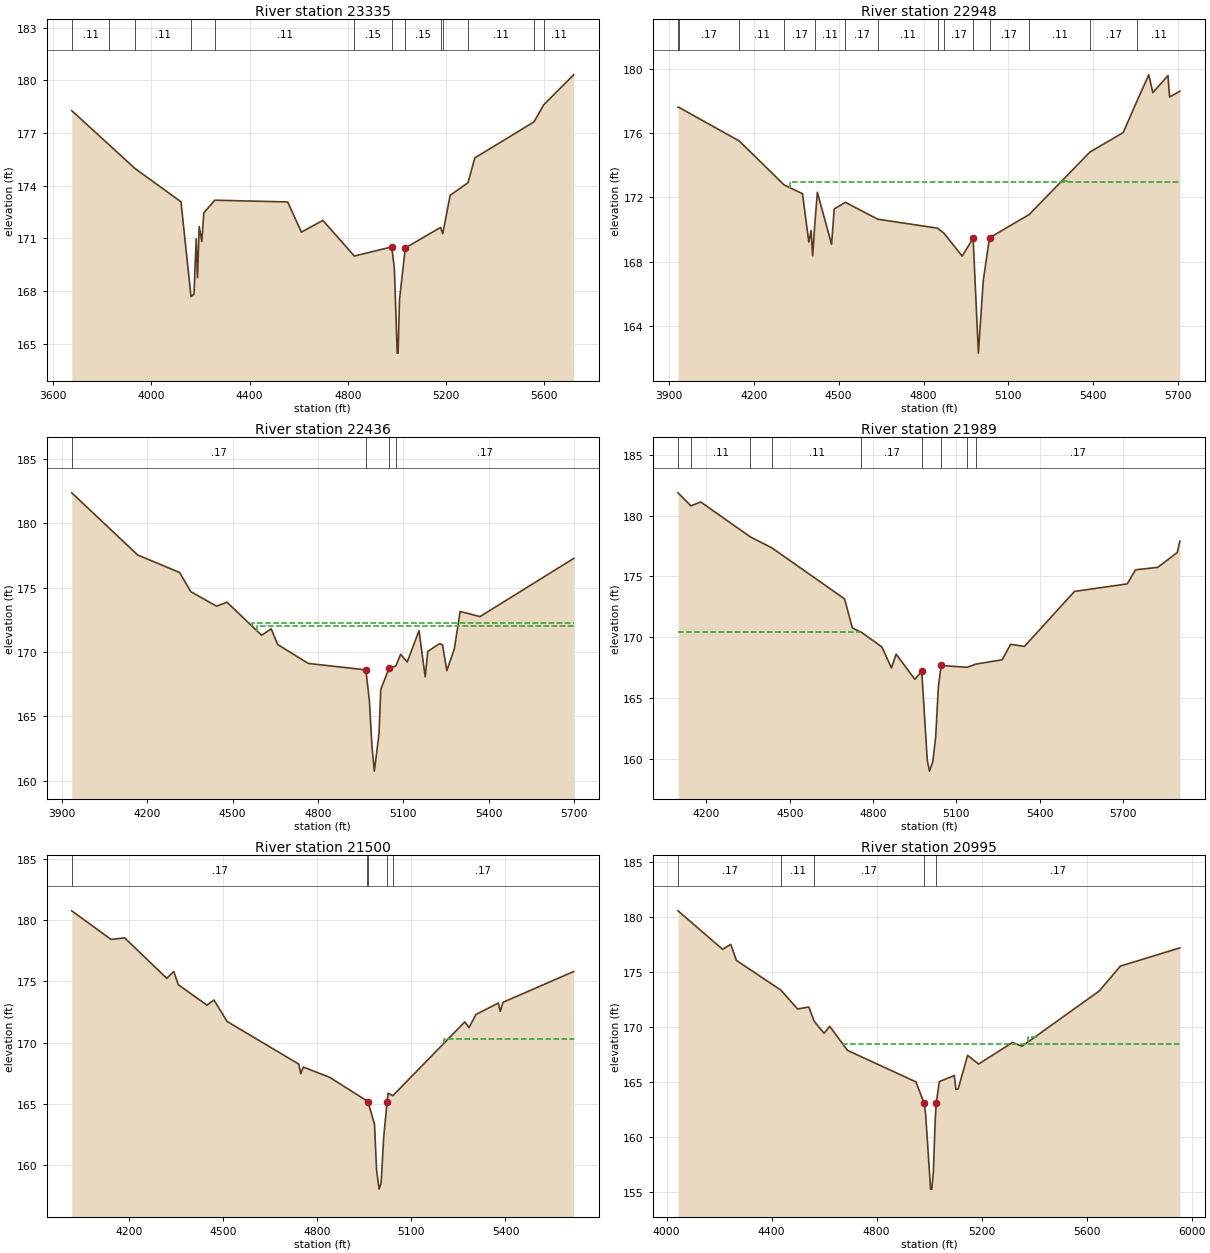
Type RM Length L Ch R = 1 ,23335   ,387,387,387
BEGIN DESCRIPTION:
CRYSTAL CREEK TRIBUTARY NO 1 47.0
END DESCRIPTION:
XS GIS Cut Line= 3
       3855997.6     10104035.32      3854733.73     10103591.06
      3854067.04     10103363.62
#Sta/Elev= 30
  3676.1  178.28  3829.3  176.32  3933.2  174.99  4120.9  173.09  4161.8  167.69
    4174  167.83  4182.9  170.98  4188.2  168.77  4195.2  171.68  4205.8  170.83
  4213.9  172.46  4258.8  173.18  4555.6  173.08  4611.3  171.36  4698.9  172.03
  4826.9     170  4979.6  170.52  4990.2  169.25  5001.6  164.47  5005.1  164.47
  5010.9  167.51  5034.5  170.46  5178.3  171.63    5187  171.27  5217.3  173.46
    5290  174.18  5317.8  175.59  5558.7  177.64  5598.7  178.62  5720.2  180.32
#Mann= 13 ,-1 , 0
  3676.1     .11       0  3829.3     .17       0  3933.2     .11       0
  4161.8     .17       0  4258.8     .11       0  4826.9     .15       0
  4979.6     .09       0  5034.5     .15       0  5178.3     .11       0
    5187     .17       0    5290     .11       0  5558.7     .17       0
  5598.7     .11       0
#XS Ineff= 2 , 0
       0  4555.6  173.08  5217.3       0  173.46
Permanent Ineff=
       F       F
Bank Sta=4979.6,5034.5
XS Rating Curve= 0 ,0
Exp/Cntr=0.3,0.1

Type RM Length L Ch R = 1 ,22948   ,512,512,512
BEGIN DESCRIPTION:
CRYSTAL CREEK TRIBUTARY NO 1 46.0
END DESCRIPTION:
XS GIS Cut Line= 3
      3855980.25     10103990.36      3855030.61     10103507.73
      3854391.44      10103199.4
#Sta/Elev= 30
  3931.9  177.62  3934.3  177.62  4148.9  175.51  4306.8  172.78  4372.1  172.23
  4394.5  169.21  4402.5  169.93  4408.1  168.36  4415.4  170.28  4424.7  172.32
  4474.9  169.07  4484.2  171.28  4523.9  171.69  4638.1  170.64  4849.7  170.08
  4872.7  169.76  4936.6  168.34  4975.5  169.45  4994.1  162.29  5011.3  166.81
  5033.5  169.48  5173.7  170.93  5388.8  174.83  5506.3  176.04  5556.3  178.06
  5596.8  179.64  5610.9  178.53  5664.6  179.59  5670.2  178.26  5706.8  178.62
#Mann= 14 ,-1 , 0
  3931.9     .11       0  3934.3     .17       0  4148.9     .11       0
  4306.8     .17       0  4415.4     .11       0  4523.9     .17       0
  4638.1     .11       0  4849.7     .15       0  4872.7     .17       0
  4975.5     .09       0  5033.5     .17       0  5173.7     .11       0
  5388.8     .17       0  5556.3     .11       0
#XS Ineff= 3 ,-1
  4424.7  4327.2  172.32  4327.2  4274.6  172.94  5288.9  5311.1  173.02
Permanent Ineff=
       F       F       F
Bank Sta=4975.5,5033.5
XS Rating Curve= 0 ,0
Exp/Cntr=0.3,0.1

Type RM Length L Ch R = 1 ,22436   ,447,447,447
BEGIN DESCRIPTION:
CRYSTAL CREEK TRIBUTARY NO 1 45.0
END DESCRIPTION:
XS GIS Cut Line= 3
      3856209.46     10103667.47      3855266.72     10103214.32
      3854571.71     10103034.07
#Sta/Elev= 30
  3934.5  182.36  4166.1  177.53  4313.5  176.17  4352.8  174.68  4443.3  173.55
    4480  173.86  4601.8  171.29  4635.5  171.79  4658.2  170.57  4765.8   169.1
  4968.1   168.6  4980.5  166.24  4989.7  162.63    4998  160.73  5014.4  163.64
  5020.6  167.08  5049.8  168.74  5073.5   168.9  5090.4  169.81  5113.6  169.21
    5155  171.65  5176.7  168.06  5185.9  170.04  5227.3  170.64  5237.6  170.55
  5252.7  168.54  5278.9  170.21  5299.6  173.14  5369.3  172.74  5698.5  177.26
#Mann= 4 ,-1 , 0
  3934.5     .17       0  4968.1     .09       0  5049.8     .15       0
  5073.5     .17       0
#XS Ineff= 4 ,-1
    5155  5299.6  171.65  4635.5  4584.7  171.79  4584.7  4568.7  172.03
  4568.7  4556.5  172.21
Permanent Ineff=
       F       F       F       F
Bank Sta=4968.1,5049.8
XS Rating Curve= 0 ,0
Exp/Cntr=0.3,0.1

Type RM Length L Ch R = 1 ,21989   ,489,489,489
BEGIN DESCRIPTION:
CRYSTAL CREEK TRIBUTARY NO 1 44.0
END DESCRIPTION:
XS GIS Cut Line= 3
      3856267.85     10103361.07      3855490.68     10102981.69
      3854548.02     10102976.48
#Sta/Elev= 30
  4097.5  181.87  4143.9   180.8  4179.1  181.12  4358.3  178.24  4434.4  177.36
  4697.2  173.15  4725.3  170.76  4757.8   170.4  4831.9  169.19    4866  167.47
    4883   168.6  4950.6  166.53  4975.2   167.2  4995.2  159.86  5003.2  158.98
  5015.2  159.79  5025.2  161.73  5035.2  165.92  5045.2  167.67    5139  167.52
  5169.7  167.78  5265.2  168.14  5295.2  169.41  5345.2  169.24  5525.2  173.76
  5715.2  174.38  5745.2  175.54  5825.2  175.74  5895.2  176.96    5905   177.9
#Mann= 9 ,-1 , 0
  4097.5     .17       0  4143.9     .11       0  4358.3     .17       0
  4434.4     .11       0  4757.8     .17       0  4975.2     .09       0
  5045.2     .17       0    5139     .15       0  5169.7     .17       0
#XS Ineff= 2 , 0
       0    4754  170.46               0
Permanent Ineff=
       F       F
Bank Sta=4975.2,5045.2
XS Rating Curve= 0 ,0
Exp/Cntr=0.3,0.1

Type RM Length L Ch R = 1 ,21500   ,505,505,505
BEGIN DESCRIPTION:
CRYSTAL CREEK TRIBUTARY NO 1 43.0
END DESCRIPTION:
XS GIS Cut Line= 3
      3856392.45     10103193.17      3855629.23     10102575.58
      3855126.24     10102217.73
#Sta/Elev= 30
  4018.2  180.77  4143.5  178.43  4186.7  178.56    4321  175.25  4343.4  175.81
  4357.7  174.73  4448.9  173.06  4471.3  173.48  4512.9  171.73  4741.5  168.24
  4747.9  167.45  4755.8     168  4840.6  167.15  4960.3  165.21  4962.1  165.16
  4982.9  163.31  4989.3  159.61  4997.4  158.02  5003.9  158.52  5012.1  162.27
 5022.94165.1468  5026.2  165.86  5041.3  165.66  5270.4  171.69    5284  171.23
    5306   172.3  5377.3  173.23  5383.5  172.56  5392.1  173.29  5617.3  175.81
#Mann= 5 ,-1 , 0
  4018.2     .17       0  4960.3     .15       0  4962.1     .09       0
 5022.94     .15       0  5041.3     .17       0
#XS Ineff= 2 , 0
       0  4605.6   170.3  5205.2       0  170.26
Permanent Ineff=
       F       F
Bank Sta=4962.1,5022.94
XS Rating Curve= 0 ,0
Exp/Cntr=0.3,0.1

Type RM Length L Ch R = 1 ,20995   ,495,495,495
BEGIN DESCRIPTION:
CRYSTAL CREEK TRIBUTARY NO 1 42.0
END DESCRIPTION:
XS GIS Cut Line= 3
      3856438.73     10103134.41      3855923.09     10102277.61
      3855173.11      10101759.4
#Sta/Elev= 30
  4043.8  180.55  4213.6  177.05  4244.7   177.5  4266.1  176.04  4435.9  173.33
  4499.1  171.62  4541.9   171.8  4562.5   170.5  4600.2  169.41  4621.5  170.04
  4689.5  167.85  4949.8  164.99  4980.8  163.07  4986.7  162.11  5005.8  155.23
  5010.3  155.23  5016.4  156.83  5023.6  161.65 5027.39163.0615  5038.9  165.01
    5096  165.57  5102.1   164.3  5110.9  164.35  5146.7   167.4  5188.6  166.61
  5317.6  168.57    5354  168.23  5648.2  173.26  5728.7  175.52  5955.4  177.18
#Mann= 5 ,-1 , 0
  4043.8     .17       0  4435.9     .11       0  4562.5     .17       0
  4980.8     .09       0 5027.39     .17       0
#XS Ineff= 3 ,-1
    4674  4642.9  168.41  5317.6  5376.5  168.57  5376.5  5412.3  169.06
Permanent Ineff=
       F       F       F
Bank Sta=4980.8,5027.39
XS Rating Curve= 0 ,0
Exp/Cntr=0.3,0.1

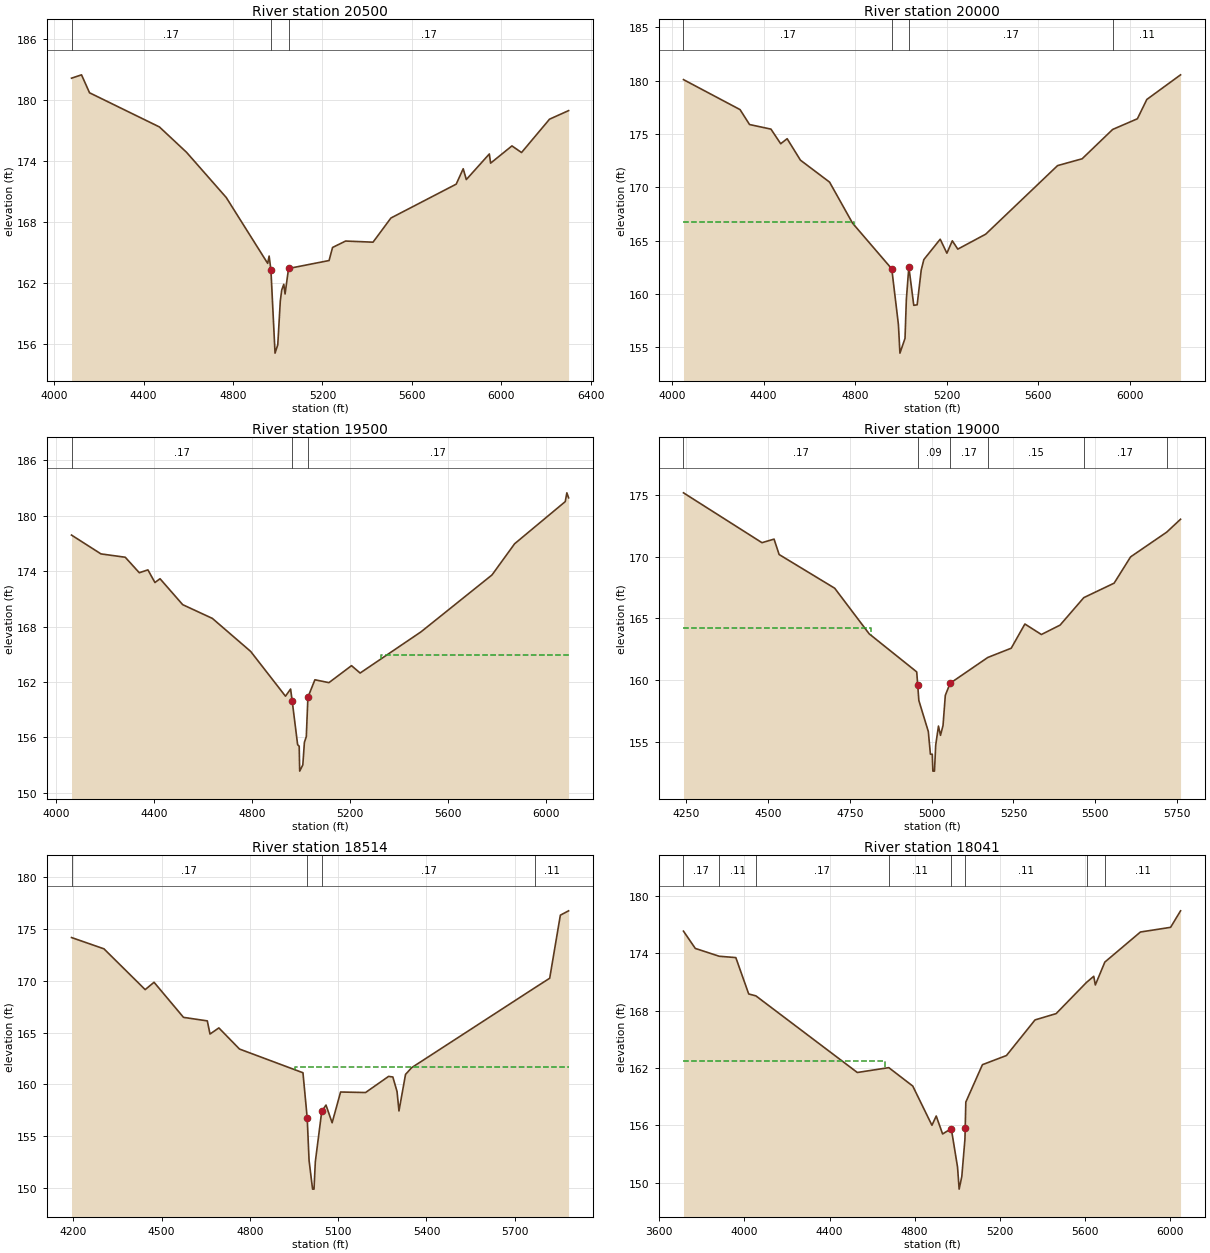
Type RM Length L Ch R = 1 ,20500   ,500,500,500
BEGIN DESCRIPTION:
CRYSTAL CREEK TRIBUTARY NO 1 41.0
END DESCRIPTION:
XS GIS Cut Line= 3
      3856920.51     10102631.79      3856203.11     10102051.52
      3855084.52     10101386.97
#Sta/Elev= 30
  4077.3  182.11    4122  182.44  4157.9  180.68  4470.5  177.33    4592  174.84
  4769.5  170.41  4954.9  163.95  4961.4  164.67 4969.48 163.275  4987.8  155.15
    5000  155.96  5011.3  160.25  5017.7  161.34  5026.9   161.9  5032.7  160.95
  5048.3  163.45  5229.5  164.23  5245.1  165.51  5303.5  166.14  5426.2  166.03
  5506.3   168.4  5798.3  171.72  5829.6  173.23  5843.6  172.17  5946.5  174.68
  5952.3  173.78  6047.7  175.47  6090.6  174.82  6215.8  178.09  6301.1  178.93
#Mann= 3 , 0 , 0
  4077.3     .17       0 4969.48     .09       0  5048.3     .17       0
#XS Ineff= 2 , 0
       0                  5494.5       0  167.92
Permanent Ineff=
       F       F
Bank Sta=4969.48,5048.3
XS Rating Curve= 0 ,0
Exp/Cntr=0.3,0.1

Type RM Length L Ch R = 1 ,20000   ,500,500,500
BEGIN DESCRIPTION:
CRYSTAL CREEK TRIBUTARY NO 1 40.0
END DESCRIPTION:
XS GIS Cut Line= 3
      3857055.92     10102238.56      3856299.74     10101662.83
      3855171.69     10101192.17
#Sta/Elev= 30
  4049.6   180.1  4296.8  177.29  4338.4  175.89  4431.9  175.46  4474.5  174.09
  4502.7  174.56  4560.8  172.55  4688.2  170.49  4788.7  166.64    4960  162.36
  4989.1  157.13  4995.7  154.46  5017.9  155.84  5023.7  159.47  5034.6  162.55
  5056.2  158.94    5071  158.99  5088.7  162.25  5100.2  163.23  5171.7  165.14
  5200.9  163.83  5224.7  164.99  5248.6  164.21  5370.5  165.61  5684.7  172.04
  5792.1  172.68  5925.5  175.43  6033.6  176.43  6074.8  178.24  6222.3  180.55
#Mann= 4 ,-1 , 0
  4049.6     .17       0    4960     .09       0  5034.6     .17       0
  5925.5     .11       0
#XS Ineff= 2 , 0
       0  4795.8  166.79               0
Permanent Ineff=
       F       F
Bank Sta=4960,5034.6
XS Rating Curve= 0 ,0
Exp/Cntr=0.3,0.1

Type RM Length L Ch R = 1 ,19500   ,500,500,500
BEGIN DESCRIPTION:
CRYSTAL CREEK TRIBUTARY NO 1 39.0
END DESCRIPTION:
XS GIS Cut Line= 3
      3857100.17     10102038.02      3856507.16     10101313.32
      3855667.88      10100611.1
#Sta/Elev= 30
  4063.6  177.91    4184  175.87  4283.1  175.51  4340.5  173.83  4375.7  174.14
  4404.4  172.77  4425.2  173.18  4517.8  170.37  4639.1  168.88  4795.6   165.3
  4937.7  160.45  4958.6  161.23    4965  159.96  4987.3   155.2  4993.7  155.03
  4995.8  152.33  5008.5     153    5015  155.45  5022.8  156.07  5029.3  160.33
  5057.9  162.23  5115.2  161.92  5207.5  163.76  5242.7  162.96  5491.2  167.42
  5781.4  173.59  5873.8  176.97  6080.7  181.54  6087.2  182.49  6094.3  181.95
#Mann= 3 , 0 , 0
  4063.6     .17       0    4965     .09       0  5029.3     .17       0
#XS Ineff= 2 , 0
       0                  5327.3       0  164.88
Permanent Ineff=
       F       F
Bank Sta=4965,5029.3
XS Rating Curve= 0 ,0
Exp/Cntr=0.3,0.1

Type RM Length L Ch R = 1 ,19000   ,486,486,486
BEGIN DESCRIPTION:
CRYSTAL CREEK TRIBUTARY NO 1 38.0
END DESCRIPTION:
XS GIS Cut Line= 3
      3857118.42     10101834.94      3856817.77     10101139.33
       3856373.6     10100522.39
#Sta/Elev= 30
  4242.2  175.18  4481.9  171.14  4518.8  171.43  4534.3  170.18    4704  167.45
  4809.1  163.76  4954.5  160.67  4957.4159.6349    4961  158.35  4989.9  155.84
  4996.3     154    5002     154  5003.8  152.63  5008.7  152.63  5012.4  154.73
  5020.9  156.28  5027.1  155.53  5034.8  156.33  5041.8  158.77  5056.5  159.75
  5171.5  161.84  5243.1  162.59  5284.8  164.55  5335.2   163.7  5392.2  164.46
  5464.8  166.69  5557.3  167.86  5607.6  169.99  5717.7  171.99  5760.2  173.04
#Mann= 6 ,-1 , 0
  4242.2     .17       0  4957.4     .09       0  5056.5     .17       0
  5171.5     .15       0  5464.8     .17       0  5717.7     .11       0
#XS Ineff= 2 , 0
       0  4814.5  164.21  5284.8       0  164.55
Permanent Ineff=
       F       F
Bank Sta=4957.4,5056.5
XS Rating Curve= 0 ,0
Exp/Cntr=0.3,0.1

Type RM Length L Ch R = 1 ,18514   ,473,473,473
BEGIN DESCRIPTION:
CRYSTAL CREEK TRIBUTARY NO 1 37.0
END DESCRIPTION:
XS GIS Cut Line= 3
      3857267.85      10101761.1      3857225.17      10100981.6
      3856517.86     10100411.08
#Sta/Elev= 30
  4193.7  174.18  4303.9  173.09  4444.1  169.15  4474.2  169.86  4574.3  166.47
  4655.2  166.13  4664.4  164.86  4694.5  165.45  4764.6  163.41  4980.3  161.12
  4994.7  156.76  5001.1  152.64    5013  149.88  5017.9  149.88  5022.3  152.52
  5044.2   157.4  5058.6     158  5079.4  156.29  5108.2  159.26    5193  159.21
  5271.4  160.77  5285.8  160.71  5300.1   159.3  5306.6  157.43  5328.9  160.96
  5349.7  161.61  5769.5  169.35  5818.9  170.25  5855.1  176.34  5883.1  176.76
#Mann= 4 ,-1 , 0
  4193.7     .17       0  4994.7     .09       0  5044.2     .17       0
  5769.5     .11       0
#XS Ineff= 3 ,-1
  4954.9  4904.8  161.64  5349.7  5370.5  161.61  5370.5  5413.7  161.98
Permanent Ineff=
       F       F       F
Bank Sta=4994.7,5044.2
XS Rating Curve= 0 ,0
Exp/Cntr=0.3,0.1

Type RM Length L Ch R = 1 ,18041   ,303,303,303
BEGIN DESCRIPTION:
CRYSTAL CREEK TRIBUTARY NO 1 36.0
END DESCRIPTION:
XS GIS Cut Line= 3
      3857371.87     10101856.58      3857288.54     10100536.29
       3856547.7     10099844.84
#Sta/Elev= 30
  3713.7  176.34  3769.3  174.53  3881.7  173.71  3959.7  173.57  4020.2  169.76
    4054  169.56  4530.8  161.53  4678.7  162.04  4791.3  160.11  4881.5     156
  4901.6  156.97  4931.6  155.09  4972.4  155.65  5001.8  151.62  5009.3  149.31
  5021.8  150.63  5036.6  154.55 5037.86155.7421  5040.7  158.43  5118.8  162.35
  5231.7  163.31    5366  167.04  5465.2   167.7  5607.9  170.97    5642  171.61
  5649.4   170.7  5694.1   173.1  5861.4  176.25  6003.1  176.74    6050  178.47
#Mann= 8 ,-1 , 0
  3713.7     .17       0  3881.7     .11       0    4054     .17       0
  4678.7     .11       0  4972.4     .09       0 5037.86     .11       0
  5607.9     .17       0  5694.1     .11       0
#XS Ineff= 2 , 0
       0  4661.1  162.76  5118.8       0  162.35
Permanent Ineff=
       F       F
Bank Sta=4972.4,5037.86
XS Rating Curve= 0 ,0
Exp/Cntr=0.3,0.1

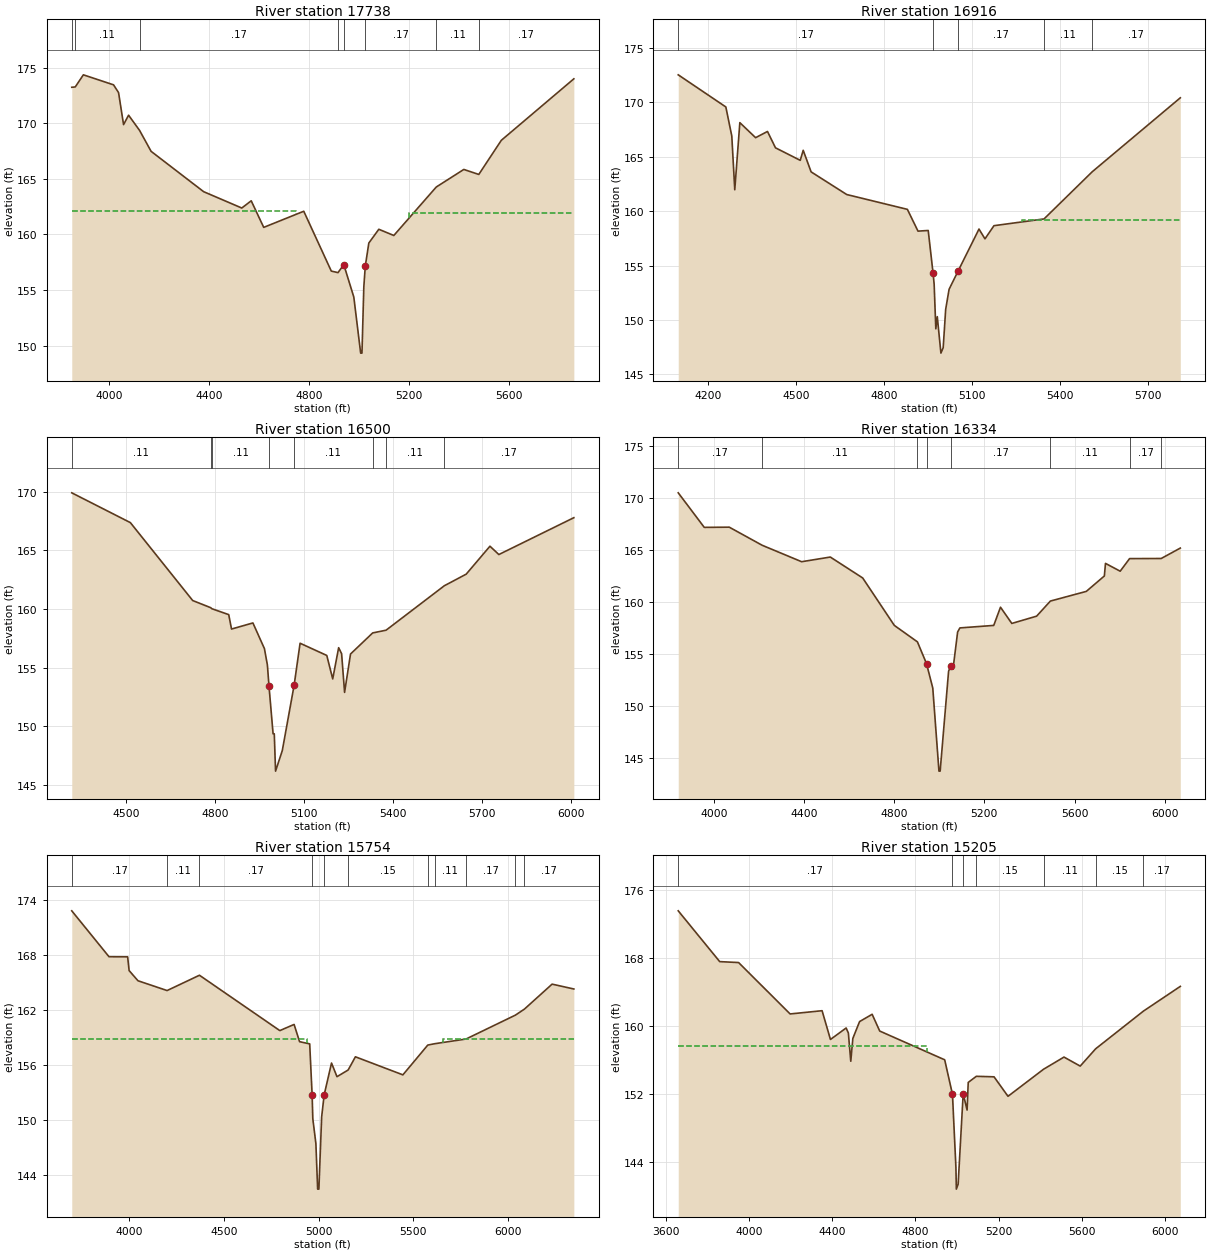
Type RM Length L Ch R = 1 ,17738   ,822,822,822
BEGIN DESCRIPTION:
CRYSTAL CREEK TRIBUTARY NO 1 35.0
END DESCRIPTION:
XS GIS Cut Line= 3
      3857460.42     10101768.01       3857515.1     10100627.43
      3857517.85     10099761.02
#Sta/Elev= 30
    3852  173.23  3865.9  173.26  3898.4  174.35  4019.1  173.45  4039.2  172.75
  4059.2  169.87  4079.2  170.72  4123.3  169.35  4169.3  167.47  4379.5  163.84
    4532  162.37  4569.8  163.02  4619.8  160.63    4780  162.08  4890.1   156.7
  4916.8  156.56  4940.2  157.27  4980.2  154.36  5007.6  149.32  5012.8  149.32
  5020.2  155.26 5025.94157.1197  5040.2  159.22  5080.2  160.46  5140.2   159.9
    5310  164.26  5420.2  165.84  5480.1  165.39  5570.2  168.46  5860.3  173.99
#Mann= 8 ,-1 , 0
    3852     .17       0  3865.9     .11       0  4123.3     .17       0
  4916.8     .11       0  4940.2     .09       0 5025.94     .17       0
    5310     .11       0  5480.1     .17       0
#XS Ineff= 2 , 0
       0    4750  162.11  5200.2       0  161.96
Permanent Ineff=
       F       F
Bank Sta=4940.2,5025.94
XS Rating Curve= 0 ,0
Exp/Cntr=0.3,0.1

Type RM Length L Ch R = 1 ,16916   ,416,416,416
BEGIN DESCRIPTION:
CRYSTAL CREEK TRIBUTARY NO 1 34.0
END DESCRIPTION:
XS GIS Cut Line= 3
      3857767.86     10101711.04      3857916.14     10100825.35
      3857757.28     10100028.45
#Sta/Elev= 30
    4099  172.51  4261.2  169.56  4281.5  166.89  4291.6  161.96  4308.9  168.12
  4362.6  166.74  4403.1  167.31  4430.3  165.81  4514.7  164.66  4524.8  165.58
  4551.7   163.6  4673.1  161.52  4879.7  160.16  4915.9  158.16  4950.7  158.22
 4967.06154.3455  4970.9   153.3  4976.6  149.19  4981.6  150.31    4994  146.96
  5001.7  147.46  5010.2  150.98  5021.8  152.82  5052.4  154.49  5123.7  158.35
  5144.1  157.45  5174.7  158.66  5345.3  159.28  5509.5  163.61  5809.6   170.4
#Mann= 5 ,-1 , 0
    4099     .17       0 4967.06     .09       0  5052.4     .17       0
  5345.3     .11       0  5509.5     .17       0
#XS Ineff= 2 , 0
       0  4879.7  160.16  5270.6       0  159.18
Permanent Ineff=
       F       F
Bank Sta=4967.06,5052.4
XS Rating Curve= 0 ,0
Exp/Cntr=0.3,0.1

Type RM Length L Ch R = 1 ,16500   ,166,166,166
BEGIN DESCRIPTION:
CRYSTAL CREEK TRIBUTARY NO 1 33.0
END DESCRIPTION:
XS GIS Cut Line= 3
      3858059.37     10101585.75      3858141.99     10100908.07
      3858127.08     10099898.28
#Sta/Elev= 30
  4317.3   169.9  4514.9  167.36    4725  160.72  4785.7  160.11  4789.8  160.02
  4846.4  159.52  4855.9  158.29    4928  158.81  4966.8  156.62  4976.8  155.22
 4982.17153.4335    4996  149.36    5000  149.36  5004.3  146.18    5027  147.93
    5067  153.51    5087  157.08    5177  156.04    5197  154.04    5217   156.7
    5227  156.19    5237  152.89    5257  156.16  5331.8  157.96  5376.8  158.19
  5573.3  161.98  5647.1  162.97  5727.1  165.35  5757.1  164.64  6009.9  167.78
#Mann= 8 ,-1 , 0
  4317.3     .11       0  4785.7     .17       0  4789.8     .11       0
 4982.17     .09       0    5067     .11       0  5331.8     .17       0
  5376.8     .11       0  5573.3     .17       0
#XS Ineff= 2 , 0
       0    4928  158.81               0
Permanent Ineff=
       F       F
Bank Sta=4982.17,5067
XS Rating Curve= 0 ,0
Exp/Cntr=0.3,0.1

Type RM Length L Ch R = 1 ,16334   ,580,580,580
BEGIN DESCRIPTION:
CRYSTAL CREEK TRIBUTARY NO 1 32.0
END DESCRIPTION:
XS GIS Cut Line= 4
      3858140.12     10102062.52      3858224.65     10101930.17
      3858290.56      10101037.1      3858349.52     10099864.82
#Sta/Elev= 30
  3842.8  170.49  3958.3  167.17  4069.1  167.19  4215.1  165.45    4390  163.87
  4517.1  164.32  4660.7  162.31  4801.1  157.75  4903.4  156.17  4943.7  154.08
  4971.5  151.73  4998.9  143.75  5004.2  143.75  5041.6  153.35  5051.6  153.88
  5061.6  153.62  5081.6  157.11  5091.6  157.51  5241.8  157.75  5271.8   159.5
  5321.9  157.94    5432  158.64    5493  160.09  5652.3  161.02  5732.3   162.5
  5737.3  163.71  5802.5  162.96  5844.2  164.17  5984.3  164.18  6069.1  165.18
#Mann= 8 ,-1 , 0
  3842.8     .17       0  4215.1     .11       0  4903.4     .17       0
  4943.7     .09       0  5051.6     .17       0    5493     .11       0
  5844.2     .17       0  5984.3     .11       0
#XS Ineff= 2 , 0
       0                  5271.8       0   159.5
Permanent Ineff=
       F       F
Bank Sta=4943.7,5051.6
XS Rating Curve= 0 ,0
Exp/Cntr=0.3,0.1

Type RM Length L Ch R = 1 ,15754   ,549,549,549
BEGIN DESCRIPTION:
CRYSTAL CREEK TRIBUTARY NO 1 31.0
END DESCRIPTION:
XS GIS Cut Line= 3
      3859215.86     10102391.12      3858611.67     10101018.69
      3858387.72      10099888.5
#Sta/Elev= 30
  3696.9  172.81  3893.6   167.8    3992  167.79  3999.8  166.29  4046.5  165.18
  4200.4  164.11  4371.3  165.78  4795.7  159.74  4871.2  160.41    4900  158.53
  4953.5  158.29  4966.4152.6879    4970  150.11  4986.2  147.42  4995.5  142.44
    5002  142.44  5016.7  150.33  5029.9  152.72  5068.8   156.2  5097.6  154.71
  5156.6  155.44    5195  156.88  5445.7  154.91  5577.2  158.16  5614.2  158.31
  5779.2  158.82  6040.1  161.43  6087.9  162.09  6233.8  164.81  6348.6  164.28
#Mann= 11 ,-1 , 0
  3696.9     .17       0  4200.4     .11       0  4371.3     .17       0
  4966.4     .09       0  5029.9     .17       0  5156.6     .15       0
  5577.2     .17       0  5614.2     .11       0  5779.2     .17       0
  6040.1     .11       0  6087.9     .17       0
#XS Ineff= 2 , 0
       0  4941.2  158.77  5655.6       0  158.87
Permanent Ineff=
       F       F
Bank Sta=4966.4,5029.9
XS Rating Curve= 0 ,0
Exp/Cntr=0.3,0.1

Type RM Length L Ch R = 1 ,15205   ,794,794,794
BEGIN DESCRIPTION:
CRYSTAL CREEK TRIBUTARY NO 1 30.0
END DESCRIPTION:
XS GIS Cut Line= 3
      3859546.57     10102190.56      3859072.61     10100995.25
      3858653.35     10099951.02
#Sta/Elev= 30
  3661.1   173.5  3860.3  167.53    3951  167.42  4198.4  161.38  4351.9  161.76
  4392.1  158.38  4467.4  159.73  4478.1  159.14  4489.7  155.82  4499.6   158.5
  4531.9  160.48  4592.3  161.34  4628.7  159.37  4940.7  155.99 4978.04151.9359
  4994.6  143.35  4996.7  140.79  5005.3  141.37  5029.5  152.01  5048.3  150.08
  5053.7  153.33  5092.6  154.05  5177.7  153.99  5244.7   151.7  5415.4  154.88
  5513.6  156.31  5591.5  155.25  5665.9  157.29  5894.9  161.71  6072.2  164.62
#Mann= 7 ,-1 , 0
  3661.1     .17       0 4978.04     .09       0  5029.5     .17       0
  5092.6     .15       0  5415.4     .11       0  5665.9     .15       0
  5894.9     .17       0
#XS Ineff= 2 , 0
       0  4854.6  157.67               0
Permanent Ineff=
       F       F
Bank Sta=4978.04,5029.5
XS Rating Curve= 0 ,0
Exp/Cntr=0.3,0.1