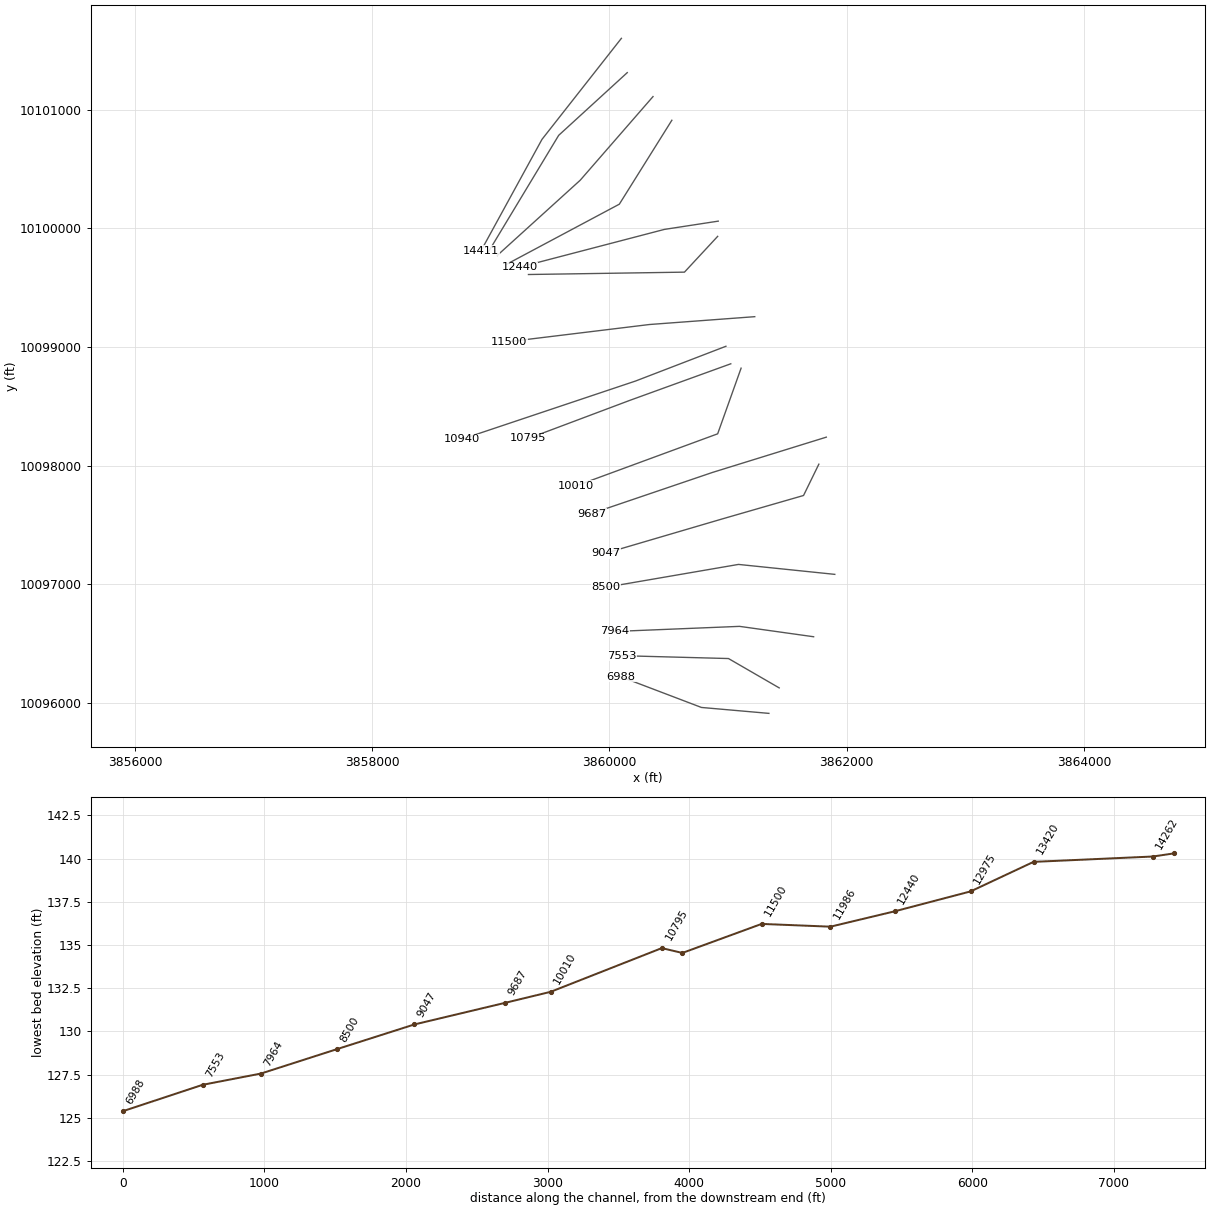
HEC-RAS study CRYSTAL CREEK TRIBUTARY NO 1.prj: CRYSTAL CREEK TRIBUTARY NO 1 Base Level Engineering

--- CRYSTAL CREEK TRIBUTARY NO 1.g01 (geometry) --- (continued)

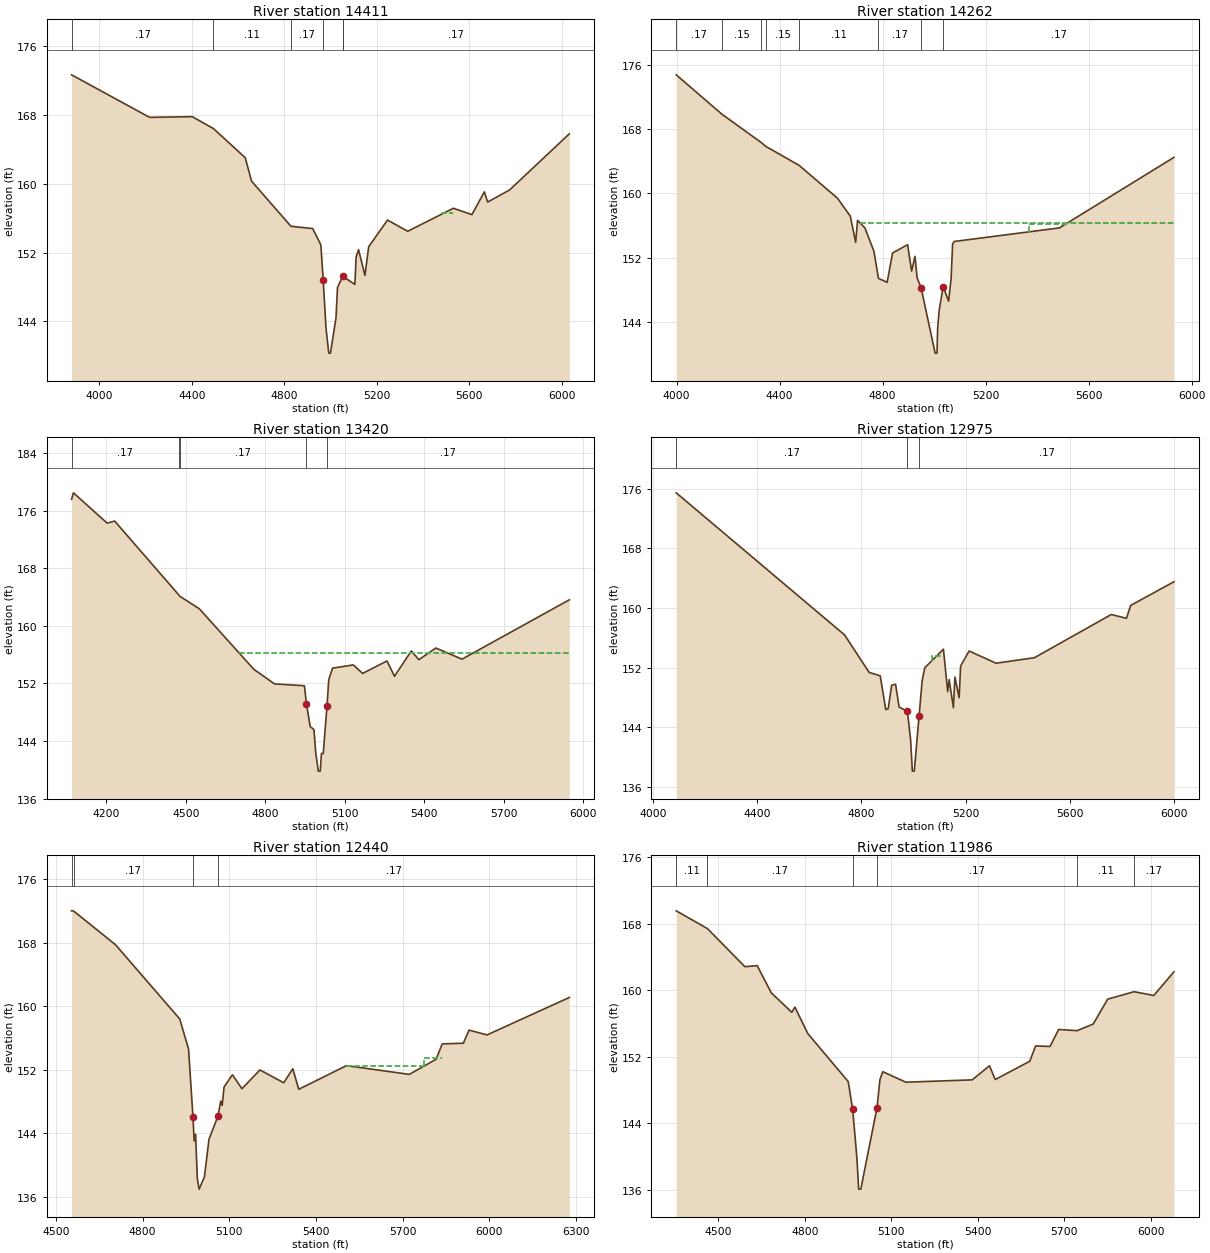
Type RM Length L Ch R = 1 ,14411   ,149,149,149
BEGIN DESCRIPTION:
CRYSTAL CREEK TRIBUTARY NO 1 29.0
END DESCRIPTION:
XS GIS Cut Line= 3
      3860101.28     10101602.06      3859431.98     10100750.46
      3858917.86     10099811.08
#Sta/Elev= 30
  3879.1  172.69  4216.9  167.74  4401.8  167.82  4493.3  166.43  4630.8  163.04
    4658  160.32  4828.7  155.06  4922.7   154.8    4958  152.89 4968.15148.8031
  4979.9  143.34  4992.1   140.3  4999.4   140.3  5023.6  144.42  5029.9  147.94
  5052.7  149.25  5053.1  149.23  5105.1   148.3  5110.8  151.51  5121.1  152.34
  5148.8  149.35  5164.9  152.68  5246.4  155.79  5333.7  154.48  5531.5  157.16
  5611.6  156.42  5665.6  159.07  5679.7  157.88  5774.7  159.29  6033.1  165.82
#Mann= 6 ,-1 , 0
  3879.1     .17       0  4493.3     .11       0  4828.7     .17       0
 4968.15     .09       0  5052.7     .15       0  5053.1     .17       0
#XS Ineff= 2 ,-1
  5480.7  5531.5  156.57  5531.5  5649.5  157.16
Permanent Ineff=
       F       F
Bank Sta=4968.15,5052.7
XS Rating Curve= 0 ,0
Exp/Cntr=0.3,0.1

Type RM Length L Ch R = 1 ,14262   ,842,842,842
BEGIN DESCRIPTION:
CRYSTAL CREEK TRIBUTARY NO 1 28.0
END DESCRIPTION:
XS GIS Cut Line= 3
      3860150.75     10101312.97      3859572.61     10100784.31
      3858978.85     10099799.92
#Sta/Elev= 30
  3998.4  174.75  4175.9  169.85  4327.9  166.34  4346.6  165.84  4475.8  163.48
  4624.9  159.39  4674.3  157.17  4695.2   153.9  4702.6  156.64    4731  155.71
  4766.2  152.79  4783.5  149.43  4817.4  148.93  4838.8  152.59    4897  153.61
  4912.5  150.33  4925.7  152.17  4933.9  149.49  4949.1  148.28  5003.8  140.12
  5011.1  140.12  5013.5  143.12  5019.3  145.36  5034.9   148.4  5056.2  146.59
  5065.9   149.4  5071.7  153.68  5077.6  154.01  5486.3   155.7  5931.4  164.48
#Mann= 8 ,-1 , 0
  3998.4     .17       0  4175.9     .15       0  4327.9     .17       0
  4346.6     .15       0  4475.8     .11       0  4783.5     .17       0
  4949.1     .09       0  5034.9     .17       0
#XS Ineff= 3 ,-1
  4716.8  4674.3  156.31  4674.3  4660.1  157.17  5369.5  5522.1  156.19
Permanent Ineff=
       F       F       F
Bank Sta=4949.1,5034.9
XS Rating Curve= 0 ,0
Exp/Cntr=0.3,0.1

Type RM Length L Ch R = 1 ,13420   ,445,445,445
BEGIN DESCRIPTION:
CRYSTAL CREEK TRIBUTARY NO 1 27.0
END DESCRIPTION:
XS GIS Cut Line= 3
      3860367.84     10101111.06      3859754.03     10100405.84
      3859055.21     10099772.13
#Sta/Elev= 30
  4068.6  177.61  4075.7  178.51  4202.9   174.3  4231.4  174.58  4474.3  164.27
  4476.2  164.15  4550.4   162.4  4756.5  153.97  4834.3  151.94  4947.3  151.68
  4954.9  149.17  4969.2     146  4983.3  145.59    4990   142.4  4999.7  139.81
    5007  139.81  5011.6  142.26  5018.4  142.25  5032.5  148.81  5039.3  152.55
  5053.5  154.13  5131.9  154.58    5167   153.4  5258.9  155.13  5287.3     153
  5350.8  156.53  5379.2   155.3  5443.4  156.93  5542.1  155.38  5946.9  163.63
#Mann= 5 ,-1 , 0
  4068.6     .17       0  4474.3     .15       0  4476.2     .17       0
  4954.9     .09       0  5032.5     .17       0
#XS Ineff= 4 ,-1
  4706.1  4678.4  156.28  5131.9  5258.9  154.58  5258.9  5350.8  155.13
  5350.8  5641.5  156.53
Permanent Ineff=
       F       F       F       F
Bank Sta=4954.9,5032.5
XS Rating Curve= 0 ,0
Exp/Cntr=0.3,0.1

Type RM Length L Ch R = 1 ,12975   ,535,535,535
BEGIN DESCRIPTION:
CRYSTAL CREEK TRIBUTARY NO 1 26.0
END DESCRIPTION:
XS GIS Cut Line= 3
      3860526.62     10100911.51      3860083.89     10100204.02
      3859135.57     10099698.39
#Sta/Elev= 30
  4089.4  175.47  4735.1  156.39  4829.5  151.35  4871.9   150.9  4893.1  146.36
  4902.5  146.48  4915.7  149.64  4930.8  149.77  4944.4   146.7  4976.2  146.14
  4988.3  142.37  4995.1   138.1  5002.5   138.1  5020.9  145.48  5032.8  150.25
  5042.8  151.97  5114.4  154.48  5130.7  148.77  5136.3  150.39  5152.6  146.62
  5158.3  150.73  5174.6  147.96  5180.3  152.21  5212.8  154.23  5316.2  152.59
  5463.5  153.33  5758.1  159.13  5816.4  158.62  5832.7  160.35  5998.7  163.53
#Mann= 3 , 0 , 0
  4089.4     .17       0  4976.2     .09       0  5020.9     .17       0
#XS Ineff= 2 ,-1
  5070.5  5114.4  153.57  5114.4  5558.5  154.48
Permanent Ineff=
       F       F
Bank Sta=4976.2,5020.9
XS Rating Curve= 0 ,0
Exp/Cntr=0.3,0.1

Type RM Length L Ch R = 1 ,12440   ,454,454,454
BEGIN DESCRIPTION:
CRYSTAL CREEK TRIBUTARY NO 1 25.0
END DESCRIPTION:
XS GIS Cut Line= 3
      3860917.83     10100061.07      3860463.67     10099991.34
       3859242.4     10099672.47
#Sta/Elev= 30
  4554.4  172.02  4561.8  171.99  4706.1  167.76  4928.7  158.39  4959.1   154.6
 4974.48145.9767  4978.5  143.02  4983.5  143.86  4989.4  138.28  4995.8  136.95
  5013.9  138.48  5029.9  143.25  5061.2  146.18  5070.4  148.05  5075.5   147.5
  5081.9  149.82  5110.8  151.36  5143.9   149.6  5205.9  151.97  5288.6  150.35
  5319.6  152.12  5340.3  149.53  5505.1  152.51  5722.7  151.41  5815.7  153.32
  5836.4  155.25  5909.7  155.34  5929.4  156.99  5991.4  156.38  6276.1   161.1
#Mann= 4 ,-1 , 0
  4554.4     .11       0  4561.8     .17       0 4974.48     .09       0
  5061.2     .17       0
#XS Ineff= 2 ,-1
  5505.1  5774.4  152.51  5774.4  5836.4  153.42
Permanent Ineff=
       F       F
Bank Sta=4974.48,5061.2
XS Rating Curve= 0 ,0
Exp/Cntr=0.3,0.1

Type RM Length L Ch R = 1 ,11986   ,486,486,486
BEGIN DESCRIPTION:
CRYSTAL CREEK TRIBUTARY NO 1 24.0
END DESCRIPTION:
XS GIS Cut Line= 3
       3860912.9     10099932.76      3860632.94      10099631.1
      3859317.85     10099611.07
#Sta/Elev= 30
  4354.3  169.53  4462.7  167.39  4592.5  162.81    4635  162.94  4684.3  159.66
  4755.2  157.33  4765.9  157.95    4811  154.76    4951  148.99 4966.38145.6641
    4981  139.87  4987.2  136.06  4994.7  136.06    5051  145.87    5061  149.22
    5071  150.18    5151  148.92    5381   149.2    5441  150.89    5461  149.24
    5581  151.44    5601  153.28  5651.1  153.22  5681.1  155.26  5745.5  155.12
  5801.1  155.92  5851.1  158.91  5942.7   159.8  6011.1  159.35  6081.1   162.2
#Mann= 6 ,-1 , 0
  4354.3     .11       0  4462.7     .17       0 4966.38     .09       0
    5051     .17       0  5745.5     .11       0  5942.7     .17       0
Bank Sta=4966.38,5051
XS Rating Curve= 0 ,0
Exp/Cntr=0.3,0.1

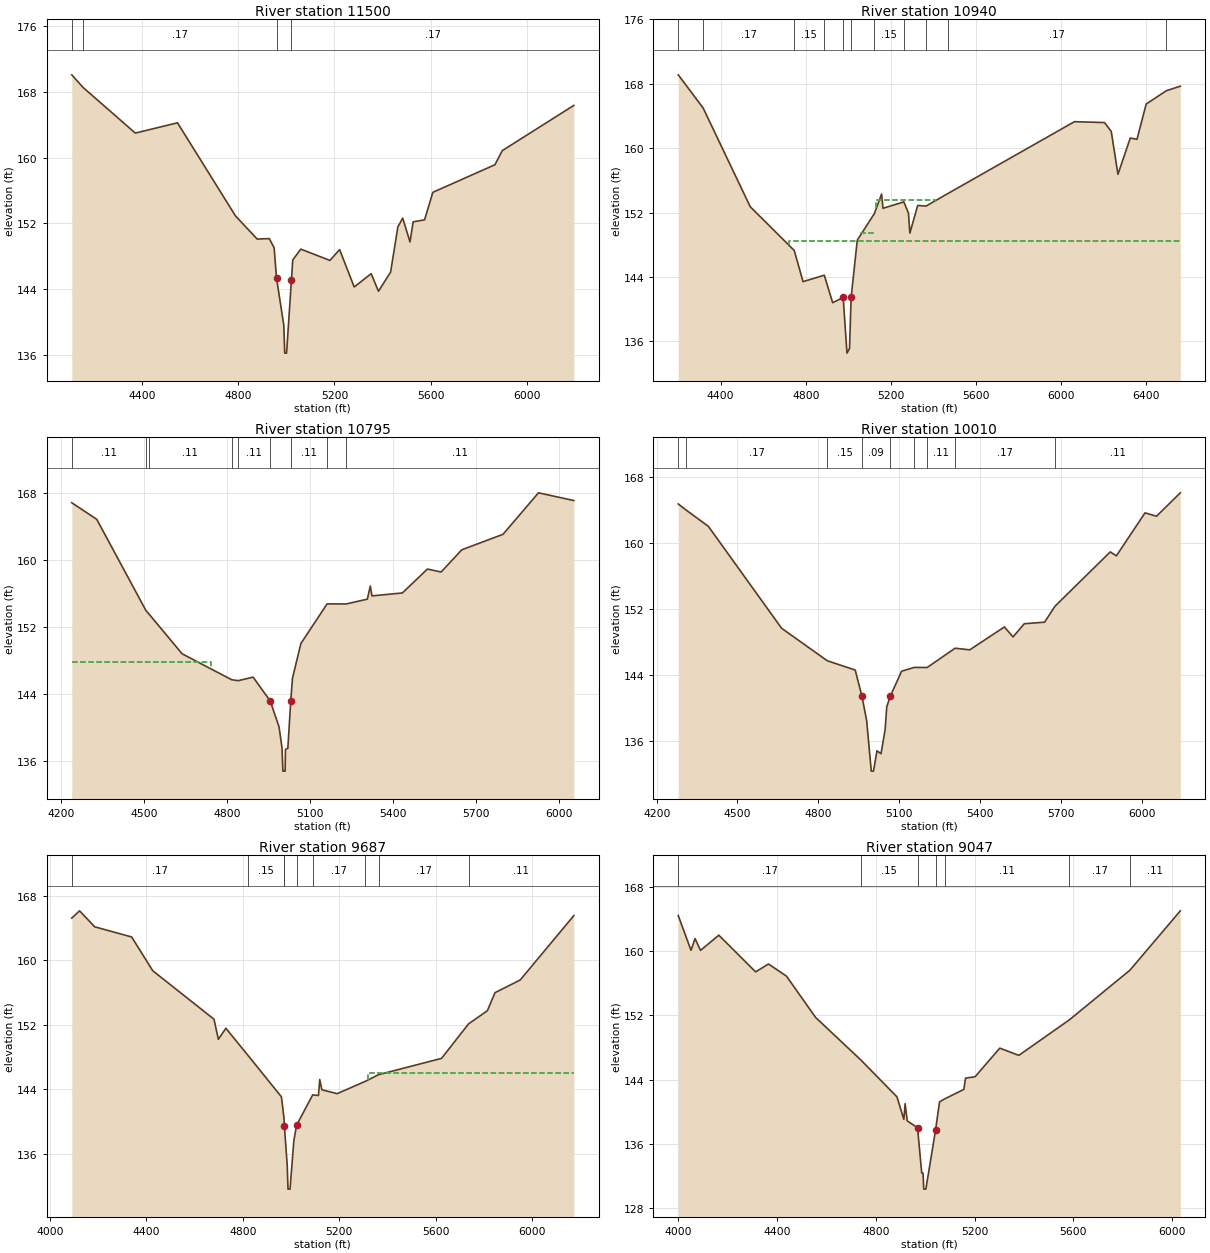
Type RM Length L Ch R = 1 ,11500   ,560,560,560
BEGIN DESCRIPTION:
CRYSTAL CREEK TRIBUTARY NO 1 23.0
END DESCRIPTION:
XS GIS Cut Line= 3
      3861225.44     10099255.67      3860337.59     10099189.57
      3859152.86     10099045.16
#Sta/Elev= 30
  4109.7  170.09  4156.9  168.55  4373.3     163  4548.5  164.25  4789.2  152.92
  4879.4   150.1  4929.5  150.16  4949.6  149.03  4959.6  145.35  4989.7  139.62
  4993.6  136.22  5001.2  136.22 5021.54 145.159  5026.9  147.56  5060.2  148.88
  5181.1   147.5  5221.4  148.82  5281.9  144.27  5352.3  145.89  5382.6  143.75
  5432.9  146.07  5463.1  151.58  5483.3  152.65  5513.5  149.75  5526.7   152.2
    5574  152.44  5608.3  155.79  5866.1  159.15  5896.3  160.86  6193.5  166.37
#Mann= 4 ,-1 , 0
  4109.7     .11       0  4156.9     .17       0  4959.6     .09       0
 5021.54     .17       0
#XS Ineff= 2 , 0
       0                  5483.3       0  152.65
Permanent Ineff=
       F       F
Bank Sta=4959.6,5021.54
XS Rating Curve= 0 ,0
Exp/Cntr=0.3,0.1

Type RM Length L Ch R = 1 ,10940   ,145,145,145
BEGIN DESCRIPTION:
CRYSTAL CREEK TRIBUTARY NO 1 22.0
END DESCRIPTION:
XS GIS Cut Line= 3
      3860982.36     10099006.11      3860220.61     10098713.13
      3858755.79     10098222.69
#Sta/Elev= 30
  4200.6  169.11  4317.7  164.99    4539  152.73  4746.1  147.29  4787.5  143.42
  4887.4  144.22  4926.8   140.8  4976.1  141.45  4994.2  134.54  5006.1  135.13
 5013.54141.4551  5042.5  148.57    5123  151.88  5156.8   154.3  5163.5  152.53
  5261.5  153.33  5283.3  151.92  5289.8  149.45  5326.6  152.88  5366.2  152.81
  5468.9  154.37  6063.7  163.29  6205.2  163.18  6236.8  162.08  6268.3  156.75
  6326.2  161.26  6357.8   161.1  6401.1  165.48  6496.2  167.14  6561.5   167.7
#Mann= 11 ,-1 , 0
  4200.6     .11       0  4317.7     .17       0  4746.1     .15       0
  4887.4     .17       0  4976.1     .09       0 5013.54     .17       0
    5123     .15       0  5261.5     .17       0  5366.2     .15       0
  5468.9     .17       0  6496.2     .11       0
#XS Ineff= 4 ,-1
  4719.7  4666.1  148.44  4666.1    4634  149.27  5061.8  5131.9  149.43
  5131.9  5409.9  153.58
Permanent Ineff=
       F       F       F       F
Bank Sta=4976.1,5013.54
XS Rating Curve= 0 ,0
Exp/Cntr=0.3,0.1

Type RM Length L Ch R = 1 ,10795   ,785,785,785
BEGIN DESCRIPTION:
CRYSTAL CREEK TRIBUTARY NO 1 21.0
END DESCRIPTION:
XS GIS Cut Line= 3
      3861023.52     10098858.51      3860172.87     10098550.37
      3859317.84     10098229.19
#Sta/Elev= 30
  4237.3   166.8  4327.8  164.82    4506  153.95  4517.4  153.52  4636.9   148.8
  4816.5  145.71    4840   145.6  4893.9  146.02  4955.9  143.18  4987.8  140.11
  4998.5  137.64  5001.8  134.82  5009.9  134.82  5011.1  137.41  5019.7  137.53
  5030.4  143.23  5036.5  145.89  5067.1  150.03  5161.9  154.75  5230.9  154.74
  5307.6  155.31  5318.3  156.87  5324.3   155.7  5434.6  156.05  5525.3   158.9
  5574.7  158.54  5649.5  161.19    5799  163.04  5927.3  167.98  6055.4  167.06
#Mann= 9 ,-1 , 0
  4237.3     .11       0    4506     .17       0  4517.4     .11       0
  4816.5     .15       0    4840     .11       0  4955.9     .09       0
  5030.4     .11       0  5161.9     .17       0  5230.9     .11       0
#XS Ineff= 2 , 0
       0  4740.8  147.77               0
Permanent Ineff=
       F       F
Bank Sta=4955.9,5030.4
XS Rating Curve= 0 ,0
Exp/Cntr=0.3,0.1

Type RM Length L Ch R = 1 ,10010   ,323,323,323
BEGIN DESCRIPTION:
CRYSTAL CREEK TRIBUTARY NO 1 20.0
END DESCRIPTION:
XS GIS Cut Line= 3
      3861110.37     10098821.64      3860912.89     10098268.25
      3859714.99     10097827.72
#Sta/Elev= 30
  4280.1  164.72  4307.7  164.02    4392     162  4663.9  149.63  4833.4  145.69
  4937.1  144.56  4962.3  141.36  4979.6  138.42  4996.8  132.29    5005  132.29
  5017.9  134.76  5032.9   134.4  5048.3  137.36  5054.2  140.11 5067.89 141.418
  5109.3  144.42  5156.3  144.88  5204.3  144.87    5308  147.21  5362.2  147.01
    5491  149.79    5523  148.58  5564.8  150.18  5640.2  150.37  5678.6   152.3
    5884   158.9  5906.6  158.42  6013.1  163.64  6055.7  163.23    6144  166.07
#Mann= 9 ,-1 , 0
  4280.1     .11       0  4307.7     .17       0  4833.4     .15       0
  4962.3     .09       0 5067.89     .15       0  5156.3     .17       0
  5204.3     .11       0    5308     .17       0  5678.6     .11       0
Bank Sta=4962.3,5067.89
XS Rating Curve= 0 ,0
Exp/Cntr=0.3,0.1

Type RM Length L Ch R = 1 ,9687    ,640,640,640
BEGIN DESCRIPTION:
CRYSTAL CREEK TRIBUTARY NO 1 19.0
END DESCRIPTION:
XS GIS Cut Line= 3
       3861828.7     10098240.05      3860869.48     10097942.73
      3859848.14     10097595.78
#Sta/Elev= 30
    4090  165.23  4122.3  166.13  4185.1  164.15  4338.4  162.89  4425.9  158.71
    4680   152.7  4698.1  150.22  4729.5  151.58  4822.1  148.18  4959.8  143.08
  4970.3  140.48 4972.07139.4692  4983.8  134.63    4987  131.65  4995.5  131.65
  5011.2  137.62  5022.7  139.57  5089.6  143.33  5113.4  143.25  5118.7  145.23
  5127.6  143.96    5191  143.48  5305.9  144.98    5363  145.83    5624  147.85
  5735.9  152.12  5814.1  153.75  5845.8  155.99  5950.3  157.56  6172.9  165.54
#Mann= 9 ,-1 , 0
    4090     .17       0  4822.1     .15       0  4970.3     .12       0
 4972.07     .09       0  5022.7     .15       0  5089.6     .17       0
  5305.9     .11       0    5363     .17       0  5735.9     .11       0
#XS Ineff= 2 , 0
       0                  5317.7       0  146.05
Permanent Ineff=
       F       F
Bank Sta=4972.07,5022.7
XS Rating Curve= 0 ,0
Exp/Cntr=0.3,0.1

Type RM Length L Ch R = 1 ,9047    ,547,547,547
BEGIN DESCRIPTION:
CRYSTAL CREEK TRIBUTARY NO 1 18.0
END DESCRIPTION:
XS GIS Cut Line= 4
      3861765.77     10098012.22      3861636.83      10097748.3
      3860956.29     10097552.11      3859966.72     10097261.31
#Sta/Elev= 30
  3999.7  164.42  4051.5  160.09  4067.8  161.55    4090  160.08  4164.1  161.97
  4313.2  157.41  4365.2  158.39  4438.1  156.88    4556  151.75  4738.8  146.47
  4885.6  141.87  4913.4  139.07  4918.6  141.02  4927.2  138.88  4968.8  138.04
  4985.9   132.4  4991.1  132.39    4994   130.4  5002.6   130.4  5041.8  137.74
    5058  141.25  5078.9  141.62  5156.4   142.8  5163.3   144.2  5201.9  144.37
    5302  147.93  5379.1  147.03  5583.5  151.44  5829.1  157.62  6033.1     165
#Mann= 7 ,-1 , 0
  3999.7     .17       0  4738.8     .15       0  4968.8     .09       0
  5041.8     .15       0  5078.9     .11       0  5583.5     .17       0
  5829.1     .11       0
#XS Ineff= 2 , 0
       0                  5163.3       0   144.2
Permanent Ineff=
       F       F
Bank Sta=4968.8,5041.8
XS Rating Curve= 0 ,0
Exp/Cntr=0.3,0.1

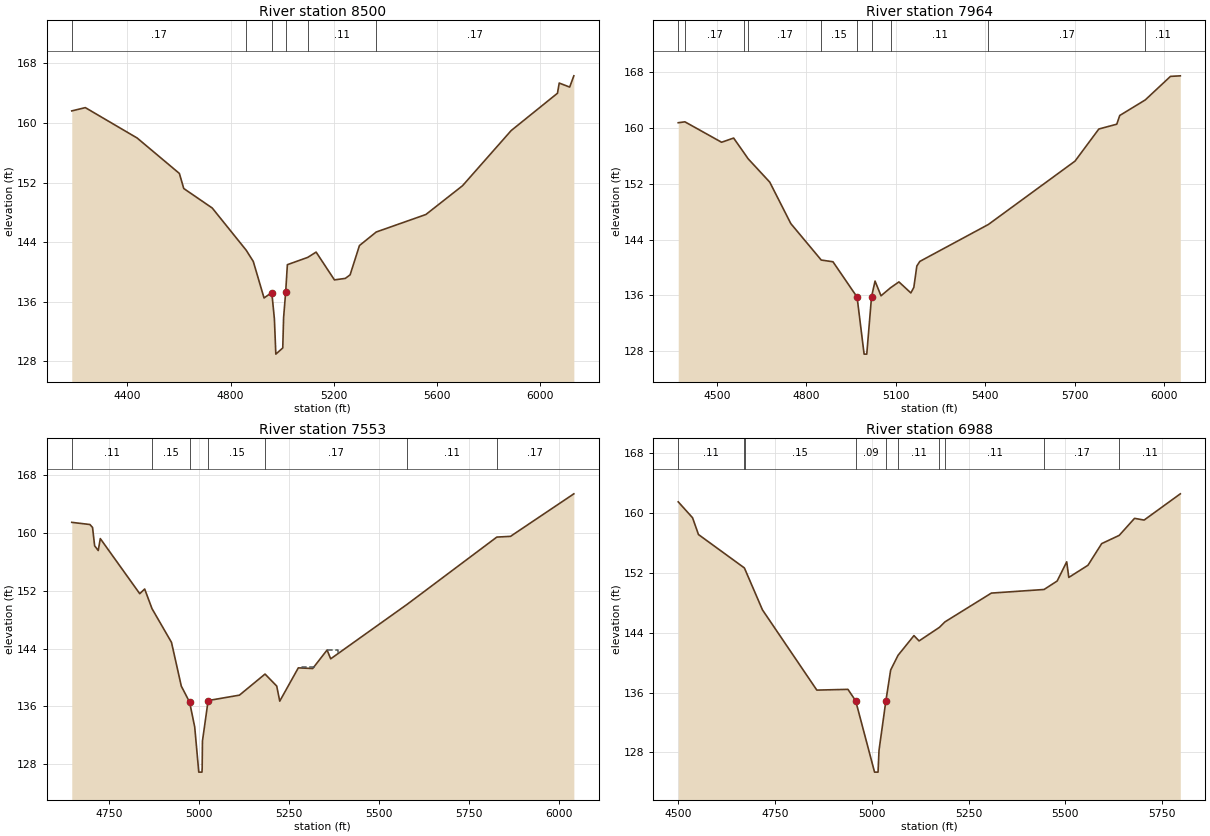
Type RM Length L Ch R = 1 ,8500    ,536,536,536
BEGIN DESCRIPTION:
CRYSTAL CREEK TRIBUTARY NO 1 17.0
END DESCRIPTION:
XS GIS Cut Line= 3
      3861900.26     10097083.36      3861088.28     10097167.18
       3859971.9       10096975.
#Sta/Elev= 30
  4183.7  161.63  4236.4  162.07  4437.5  157.99  4601.5  153.23  4618.4  151.21
    4729  148.59  4860.7  142.93  4888.3  141.42  4930.1  136.51  4960.2  137.24
  4970.3  133.71  4975.9  128.97  5002.8   129.8    5006  133.84  5014.2137.3509
  5020.7  140.98  5099.7  141.96  5132.3  142.67  5203.4  138.94  5245.7  139.14
  5264.3  139.62  5300.5  143.55  5365.8  145.37  5558.5  147.72  5700.6  151.58
  5889.5  158.99  6069.2     164    6076  165.37  6116.6  164.83  6132.8  166.34
#Mann= 6 ,-1 , 0
  4183.7     .17       0  4860.7     .15       0  4960.2     .09       0
  5014.2     .15       0  5099.7     .11       0  5365.8     .17       0
#XS Ineff= 2 , 0
       0                  5300.5       0  143.55
Permanent Ineff=
       F       F
Bank Sta=4960.2,5014.2
XS Rating Curve= 0 ,0
Exp/Cntr=0.3,0.1

Type RM Length L Ch R = 1 ,7964    ,411,411,411
BEGIN DESCRIPTION:
CRYSTAL CREEK TRIBUTARY NO 1 16.0
END DESCRIPTION:
XS GIS Cut Line= 3
      3861721.83     10096557.44      3861097.35     10096644.99
      3860044.91     10096601.96
#Sta/Elev= 30
  4370.3  160.76  4392.7  160.89  4515.7  157.96  4556.1  158.56  4591.6   156.4
  4604.7  155.59  4677.2  152.24  4747.9  146.29  4849.9  141.06  4889.3  140.81
  4970.1  135.75  4993.7  127.56  5002.6  127.56 5018.58135.7738  5030.4  138.04
  5050.4  135.93  5082.6  137.09  5110.5  137.92  5150.5  136.34  5160.5  137.14
  5170.5   140.2  5180.5  140.86  5410.4  146.16    5701  155.25    5781  159.86
  5841.1  160.55  5851.1   161.8  5936.6  164.03  6021.2  167.41  6054.2  167.49
#Mann= 10 ,-1 , 0
  4370.3     .11       0  4392.7     .17       0  4591.6     .11       0
  4604.7     .17       0  4849.9     .15       0  4970.1     .09       0
 5018.58     .15       0  5082.6     .11       0  5410.4     .17       0
  5936.6     .11       0
Bank Sta=4970.1,5018.58
XS Rating Curve= 0 ,0
Exp/Cntr=0.3,0.1

Type RM Length L Ch R = 1 ,7553    ,565,565,565
BEGIN DESCRIPTION:
CRYSTAL CREEK TRIBUTARY NO 1 15.0
END DESCRIPTION:
XS GIS Cut Line= 3
      3861431.54     10096126.33      3861004.03     10096373.72
      3860101.68     10096397.88
#Sta/Elev= 30
  4645.6   161.5  4696.1   161.2  4703.4  160.79  4709.2  158.25  4719.2   157.6
    4725  159.25  4834.7  151.62  4848.4  152.27  4868.8  149.55    4923  144.88
  4950.3  138.82  4973.4   136.6  4987.6  133.16  4998.9  126.91  5007.8  126.91
  5008.3  127.41  5009.1   131.2  5024.9  136.82    5112  137.57  5183.2  140.49
  5215.7  138.83  5224.1  136.74  5275.8  141.35  5315.8  141.26  5355.8  143.82
  5365.8   142.6  5578.3  150.14    5828  159.46    5866  159.56  6042.2  165.45
#Mann= 7 ,-1 , 0
  4645.6     .11       0  4868.8     .15       0  4973.4     .09       0
  5024.9     .15       0  5183.2     .17       0  5578.3     .11       0
    5828     .17       0
#XS Ineff= 2 ,-1
  5285.8  5325.8  141.48  5355.8  5385.8  143.82
Permanent Ineff=
       F       F
Bank Sta=4973.4,5024.9
XS Rating Curve= 0 ,0
Exp/Cntr=0.3,0.1

Type RM Length L Ch R = 1 ,6988    ,420,420,420
BEGIN DESCRIPTION:
CRYSTAL CREEK TRIBUTARY NO 1 14.0
END DESCRIPTION:
XS GIS Cut Line= 3
      3861344.73     10095911.48      3860776.17     10095961.39
      3860096.81     10096219.83
#Sta/Elev= 30
  4499.8  161.43  4536.8  159.31  4552.1  157.07  4670.4  152.63  4671.5  152.53
  4717.5  147.02    4858  136.32  4938.4  136.42  4958.4  134.89  5007.2  125.38
  5016.2  125.38  5018.7  128.28 5036.29134.8297  5048.8     139  5067.9  140.96
    5109  143.59  5122.2  142.88  5174.8  144.69  5189.1  145.42  5309.1  149.26
  5445.3  149.74  5479.1  150.87  5503.8  153.43  5509.2  151.35  5558.7  152.97
  5594.2  155.86  5639.6  156.96  5679.1  159.23  5703.9     159  5797.4   162.5
#Mann= 10 ,-1 , 0
  4499.8     .11       0  4670.4     .17       0  4671.5     .15       0
  4958.4     .09       0 5036.29     .15       0  5067.9     .11       0
  5174.8     .17       0  5189.1     .11       0  5445.3     .17       0
  5639.6     .11       0
Bank Sta=4958.4,5036.29
XS Rating Curve= 0 ,0
Exp/Cntr=0.3,0.1