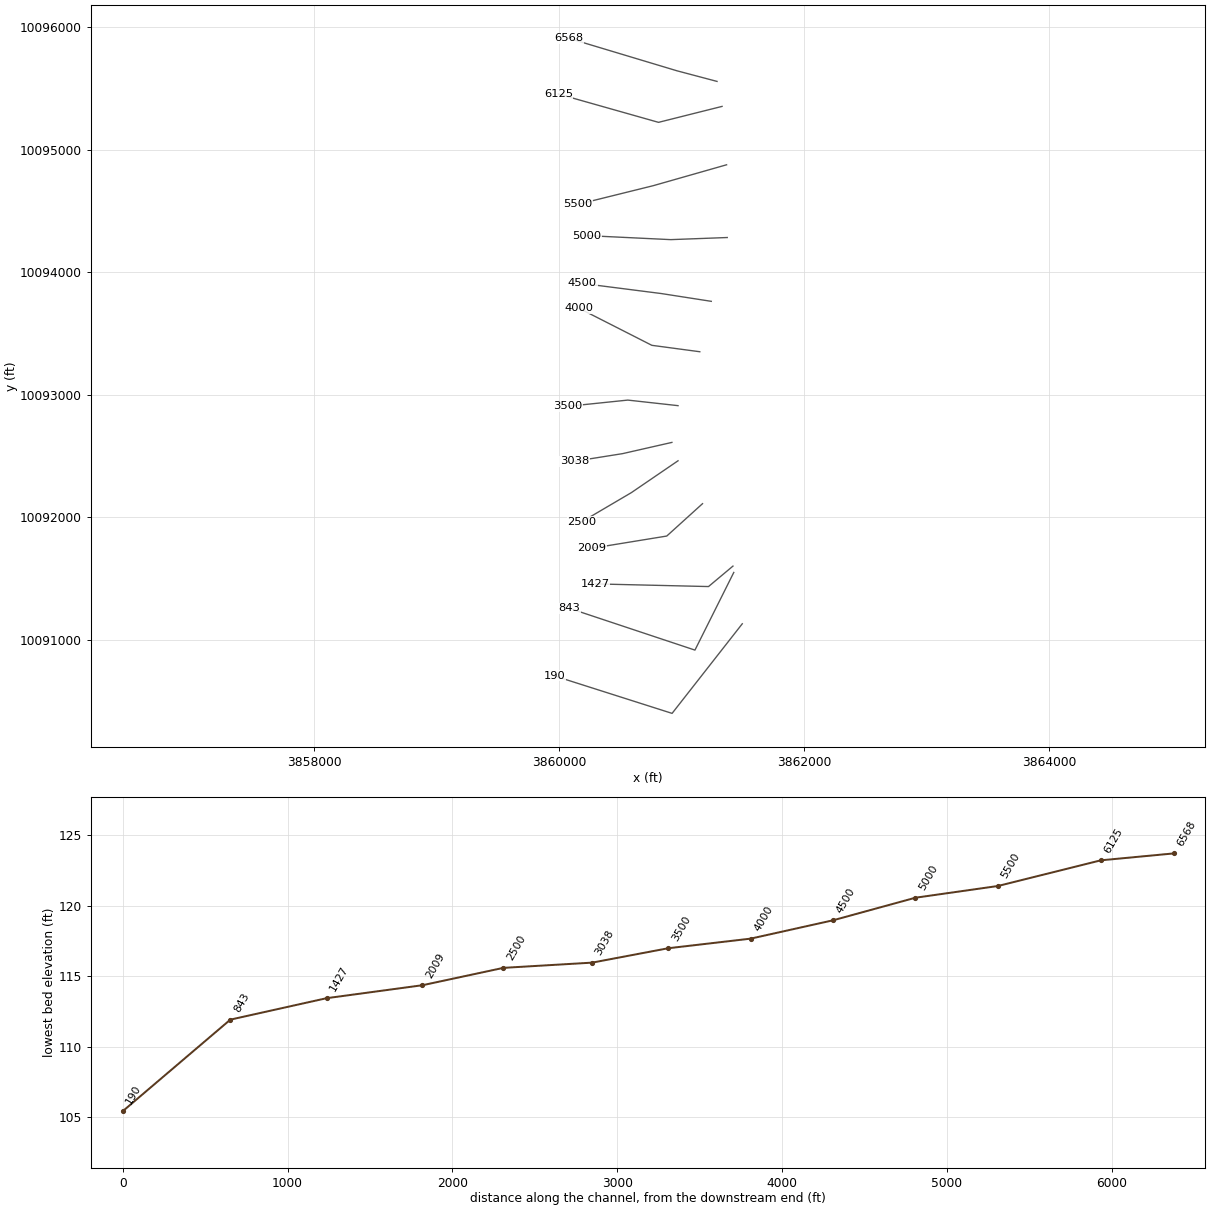
HEC-RAS study CRYSTAL CREEK TRIBUTARY NO 1.prj: CRYSTAL CREEK TRIBUTARY NO 1 Base Level Engineering

--- CRYSTAL CREEK TRIBUTARY NO 1.g01 (geometry) --- (continued)

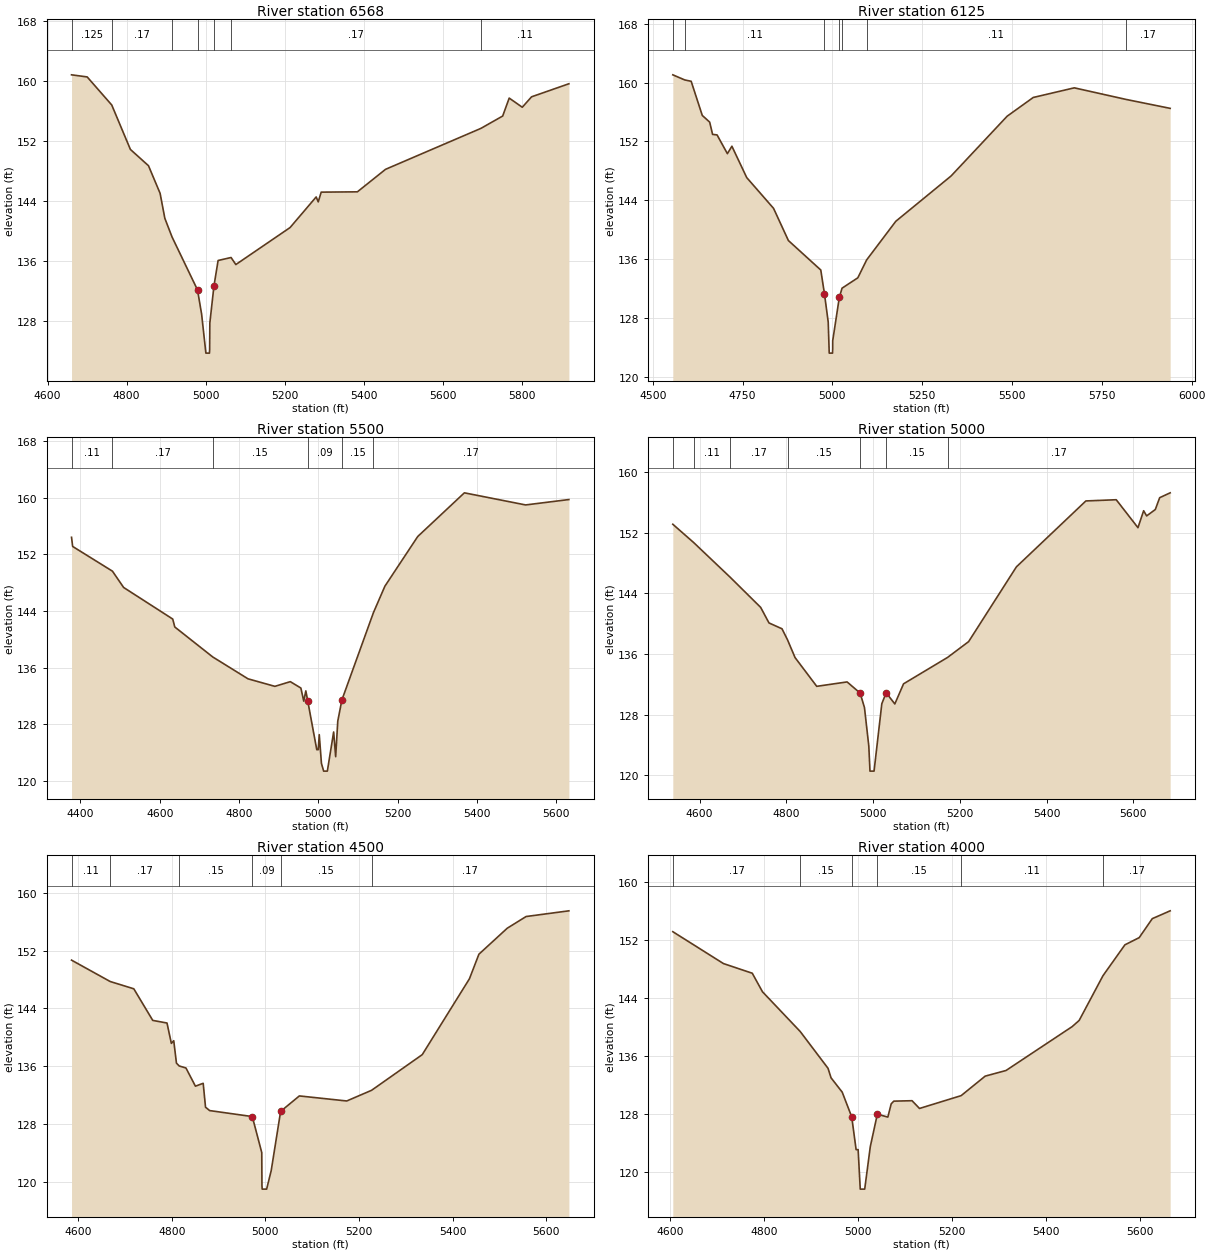
Type RM Length L Ch R = 1 ,6568    ,443,443,443
BEGIN DESCRIPTION:
CRYSTAL CREEK TRIBUTARY NO 1 13.0
END DESCRIPTION:
XS GIS Cut Line= 3
      3861286.16     10095557.74      3860958.46     10095644.55
      3860077.39     10095909.31
#Sta/Elev= 30
  4660.6  160.79  4700.2  160.51  4762.4  156.77  4809.6  150.85  4855.4  148.68
  4884.8     145  4896.8  141.67    4915  139.19  4979.5  132.13  4989.9   128.9
  5000.7  123.71  5009.7  123.71  5010.2  124.21  5010.7  127.73  5021.1  132.65
  5031.6  136.05  5064.4  136.45  5076.5  135.51  5213.8  140.44  5279.9  144.52
  5285.1  143.86  5292.6  145.16  5384.2   145.2  5455.5   148.2  5696.7  153.65
    5752   155.3  5768.5  157.69  5801.6  156.47  5825.1  157.86  5919.6   159.6
#Mann= 7 ,-1 , 0
  4660.6    .125       0  4762.4     .17       0    4915     .15       0
  4979.5     .09       0  5021.1     .15       0  5064.4     .17       0
  5696.7     .11       0
Bank Sta=4979.5,5021.1
XS Rating Curve= 0 ,0
Exp/Cntr=0.3,0.1

Type RM Length L Ch R = 1 ,6125    ,625,625,625
BEGIN DESCRIPTION:
CRYSTAL CREEK TRIBUTARY NO 1 12.0
END DESCRIPTION:
XS GIS Cut Line= 3
      3861327.39     10095353.76      3860808.72     10095223.55
      3859991.07     10095454.84
#Sta/Elev= 30
  4555.7  161.06  4588.6  160.37  4606.8  160.18  4637.7  155.54  4658.3  154.63
  4666.4  152.96  4678.9  152.89  4707.6  150.34  4720.2  151.35  4761.4  147.09
  4836.2   142.9  4877.4  138.53  4967.6  134.52  4977.9  131.27  4988.3  127.43
  4991.1  123.22  5000.2  123.22  5000.7  123.72  5000.8  124.91  5019.2  130.79
  5026.8  132.05  5070.7  133.46  5095.2  135.89  5176.5  141.15  5330.4  147.31
  5486.3  155.43    5559  157.98  5673.3  159.29  5817.9  157.71  5940.2   156.5
#Mann= 7 ,-1 , 0
  4555.7     .15       0  4588.6     .11       0  4977.9     .09       0
  5019.2     .11       0  5026.8     .15       0  5095.2     .11       0
  5817.9     .17       0
Bank Sta=4977.9,5019.2
XS Rating Curve= 0 ,0
Exp/Cntr=0.3,0.1

Type RM Length L Ch R = 1 ,5500    ,500,500,500
BEGIN DESCRIPTION:
CRYSTAL CREEK TRIBUTARY NO 1 11.0
END DESCRIPTION:
XS GIS Cut Line= 3
      3861364.26     10094877.21      3860765.69     10094706.63
      3860151.85     10094554.57
#Sta/Elev= 30
  4377.6  154.41  4380.4  153.12  4480.8  149.63    4509  147.33  4632.9  142.87
  4638.1  141.75  4733.8  137.52  4822.9  134.43  4890.6  133.37  4929.6  134.03
  4956.2  133.13  4963.5  131.28  4968.7  132.73  4973.7131.2601  4996.3  124.43
    5000  124.43  5002.6  126.55  5008.1  122.49  5013.7   121.4    5023   121.4
  5038.9  126.93    5044  123.44  5049.3  128.45  5059.6  131.43  5139.3  143.78
  5168.2  147.51    5251  154.52  5368.7  160.69  5523.2  158.98  5632.4  159.74
#Mann= 6 ,-1 , 0
  4377.6     .11       0  4480.8     .17       0  4733.8     .15       0
  4973.7     .09       0  5059.6     .15       0  5139.3     .17       0
Bank Sta=4973.7,5059.6
XS Rating Curve= 0 ,0
Exp/Cntr=0.3,0.1

Type RM Length L Ch R = 1 ,5000    ,500,500,500
BEGIN DESCRIPTION:
CRYSTAL CREEK TRIBUTARY NO 1 10.0
END DESCRIPTION:
XS GIS Cut Line= 3
      3861369.52     10094283.47      3860908.04     10094266.24
      3860223.63      10094299.1
#Sta/Elev= 30
  4538.2  153.09  4586.1  150.69  4670.5  146.11  4740.8  142.14    4760  140.09
    4790  139.32  4802.7  137.87  4820.1  135.53  4870.1  131.74  4940.1  132.32
  4970.2  130.85  4980.2  128.94  4990.2  123.86  4992.9  120.57  5002.3  120.57
  5020.2  129.45  5030.2  130.89  5050.2  129.42  5070.3  132.07  5171.9  135.55
  5220.4  137.63  5330.6  147.48  5490.8  156.16  5560.8  156.32  5610.9  152.64
    5624  154.87  5630.9  154.19  5650.9  155.03    5661  156.59  5685.2  157.23
#Mann= 7 ,-1 , 0
  4538.2     .17       0  4586.1     .11       0  4670.5     .17       0
  4802.7     .15       0  4970.2     .09       0  5030.2     .15       0
  5171.9     .17       0
Bank Sta=4970.2,5030.2
XS Rating Curve= 0 ,0
Exp/Cntr=0.3,0.1

Type RM Length L Ch R = 1 ,4500    ,500,500,500
BEGIN DESCRIPTION:
CRYSTAL CREEK TRIBUTARY NO 1 9.0
END DESCRIPTION:
XS GIS Cut Line= 3
      3861239.31     10093762.63      3860830.23     10093826.29
      3860187.17     10093908.47
#Sta/Elev= 30
    4586  150.69  4668.5  147.73    4719  146.72  4759.5  142.34  4789.9  141.98
  4799.2  139.16  4804.3  139.53  4810.1  136.42    4816  136.03  4830.4  135.75
  4850.6  133.23  4867.2  133.63  4872.2  130.32    4881  129.85  4972.1  129.02
  4992.3  124.03  4992.7  119.47  4993.2  118.97  5002.7  118.97  5012.5  121.54
  5032.6  129.74  5072.6  131.88  5173.8  131.18  5226.9  132.66  5335.1   137.6
  5435.9  148.11  5456.1  151.51  5516.6  155.11  5556.9  156.73  5648.3  157.52
#Mann= 6 ,-1 , 0
    4586     .11       0  4668.5     .17       0    4816     .15       0
  4972.1     .09       0  5032.6     .15       0  5226.9     .17       0
Bank Sta=4972.1,5032.6
XS Rating Curve= 0 ,0
Exp/Cntr=0.3,0.1

Type RM Length L Ch R = 1 ,4000    ,500,500,500
BEGIN DESCRIPTION:
CRYSTAL CREEK TRIBUTARY NO 1 8.0
END DESCRIPTION:
XS GIS Cut Line= 3
      3861145.51     10093351.18       3860754.3     10093403.53
      3860161.97     10093704.94
#Sta/Elev= 30
  4605.3  153.19  4713.2  148.79  4774.5  147.46  4796.3   144.9  4876.6  139.42
  4935.9  134.34  4942.3  133.03  4966.1  131.05  4986.3  127.65  4995.7  123.12
    5000  123.12  5004.5  117.67    5014  117.67  5025.9  123.53  5040.9  128.01
  5063.3  127.61  5070.4  129.44    5076  129.81  5114.8  129.87  5130.7   128.8
  5219.4  130.57  5270.6  133.26    5315  134.04    5456   140.1  5470.8  140.95
  5521.5  147.12  5568.2  151.38  5598.6  152.37  5626.5  154.99  5664.6  156.07
#Mann= 6 ,-1 , 0
  4605.3     .17       0  4876.6     .15       0  4986.3     .09       0
  5040.9     .15       0  5219.4     .11       0  5521.5     .17       0
Bank Sta=4986.3,5040.9
XS Rating Curve= 0 ,0
Exp/Cntr=0.3,0.1

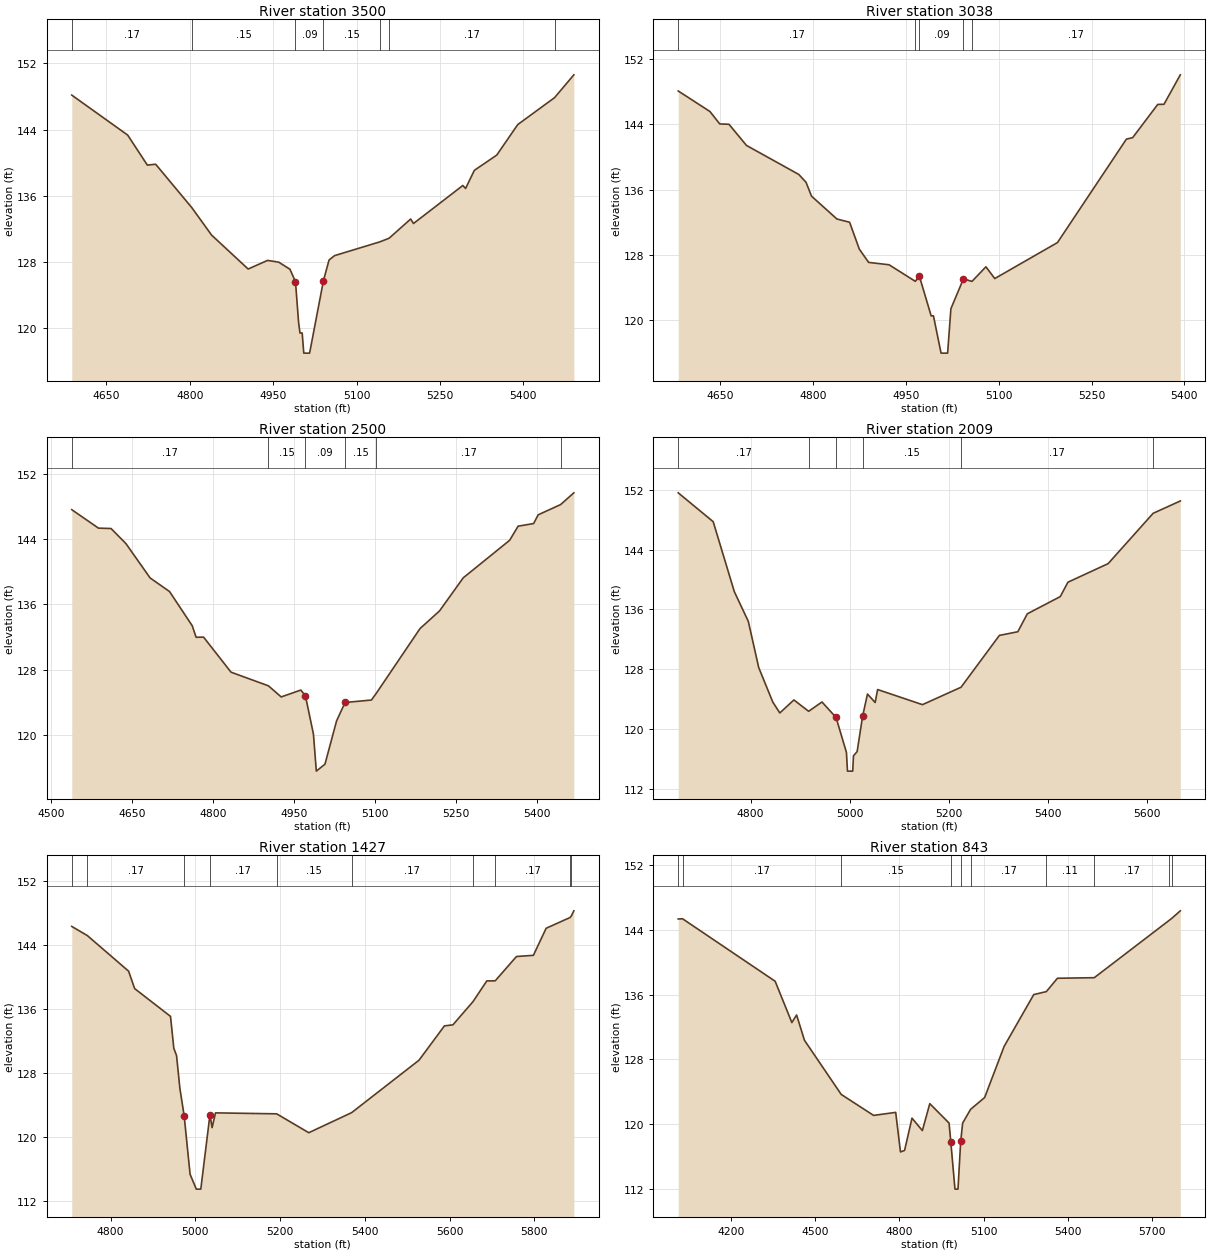
Type RM Length L Ch R = 1 ,3500    ,462,462,462
BEGIN DESCRIPTION:
CRYSTAL CREEK TRIBUTARY NO 1 7.0
END DESCRIPTION:
XS GIS Cut Line= 3
      3860967.83     10092911.07      3860557.94      10092956.5
      3860069.85     10092905.96
#Sta/Elev= 30
  4587.6  148.16  4688.2  143.33  4723.6   139.7  4738.5  139.81  4803.6  134.56
  4839.1  131.25  4904.9  127.15  4939.7  128.19  4959.8  127.98    4980  127.13
    4990  125.63  4995.6   120.7  4998.1  119.42  5002.1  119.42  5004.9  116.99
  5015.4  116.99  5040.3  125.74  5050.4  128.24  5060.4  128.77  5141.7  130.43
  5158.4  130.87  5197.2  133.19  5202.3  132.65    5291  137.24    5296  136.88
  5311.7  139.07    5352  140.91  5389.8   144.6    5456  147.85  5490.7  150.61
#Mann= 7 ,-1 , 0
  4587.6     .17       0  4803.6     .15       0    4990     .09       0
  5040.3     .15       0  5141.7     .11       0  5158.4     .17       0
    5456     .11       0
#XS Ineff= 2 , 0
       0                  5197.2       0  133.19
Permanent Ineff=
       F       F
Bank Sta=4990,5040.3
XS Rating Curve= 0 ,0
Exp/Cntr=0.3,0.1

Type RM Length L Ch R = 1 ,3038    ,538,538,538
BEGIN DESCRIPTION:
CRYSTAL CREEK TRIBUTARY NO 1 6.0
END DESCRIPTION:
XS GIS Cut Line= 3
      3860917.84     10092611.07      3860515.75     10092519.55
      3860121.79     10092456.78
#Sta/Elev= 30
  4582.2   148.1  4633.5  145.58  4649.3  144.06  4664.2  144.02  4692.4  141.43
    4777  137.87  4788.7  136.91  4797.6  135.21  4838.6  132.41  4859.1  132.01
  4874.8  128.72  4889.9  127.09  4922.9   126.8  4965.3  124.77  4971.9  125.39
  4990.9  120.54  4994.6  120.54  5006.9  115.97  5017.5  115.97  5022.8  121.41
  5043.1  125.08  5056.8  124.76  5079.4  126.55  5093.7  125.11    5195  129.52
  5306.4   142.2  5316.5  142.38    5357  146.45  5367.1  146.47  5393.5  150.08
#Mann= 5 ,-1 , 0
  4582.2     .17       0  4965.3     .15       0  4971.9     .09       0
  5043.1     .15       0  5056.8     .17       0
Bank Sta=4971.9,5043.1
XS Rating Curve= 0 ,0
Exp/Cntr=0.3,0.1

Type RM Length L Ch R = 1 ,2500    ,491,491,491
BEGIN DESCRIPTION:
CRYSTAL CREEK TRIBUTARY NO 1 5.0
END DESCRIPTION:
XS GIS Cut Line= 3
      3860967.88     10092461.09      3860586.67     10092200.96
      3860183.69     10091963.98
#Sta/Elev= 30
  4538.5   147.6  4587.9  145.34  4611.2  145.29  4638.8  143.44  4683.5  139.24
  4719.4  137.58  4761.4  133.39  4768.6  131.98  4782.4     132  4833.2  127.71
  4902.4  126.04    4926  124.68  4962.3  125.52  4970.8  124.83  4985.7  120.12
    4991   115.6    5007  116.45  5028.5  121.75  5044.2     124  5092.9   124.3
  5101.9  125.12  5182.8  133.04    5219  135.21  5262.9  139.26  5348.7  143.85
  5364.4  145.58  5393.1   145.9  5401.5  146.97    5443  148.22  5467.5  149.66
#Mann= 6 ,-1 , 0
  4538.5     .17       0  4902.4     .15       0  4970.8     .09       0
  5044.2     .15       0  5101.9     .17       0    5443     .11       0
Bank Sta=4970.8,5044.2
XS Rating Curve= 0 ,0
Exp/Cntr=0.3,0.1

Type RM Length L Ch R = 1 ,2009    ,582,582,582
BEGIN DESCRIPTION:
CRYSTAL CREEK TRIBUTARY NO 1 4.0
END DESCRIPTION:
XS GIS Cut Line= 3
      3861167.82     10092111.04      3860875.99     10091846.81
      3860264.05     10091746.99
#Sta/Elev= 30
    4654  151.59  4724.6  147.73  4767.2  138.38  4795.5   134.4  4816.5  128.22
  4844.9  123.61  4859.1  122.15  4887.5  123.89  4917.3  122.37  4944.2  123.62
  4972.6  121.55  4993.6  116.88  4995.7  114.37  5006.3  114.37  5007.8  116.42
  5015.2  116.98  5026.2121.6923  5036.1  124.68  5051.6  123.55  5056.6  125.28
  5147.1  123.26    5225  125.59  5302.4  132.52  5339.6  133.01  5358.8  135.41
  5425.3  137.71  5440.9  139.64    5522  142.12  5612.8  148.85  5667.7   150.5
#Mann= 6 ,-1 , 0
    4654     .17       0  4917.3     .15       0  4972.6     .09       0
  5026.2     .15       0    5225     .17       0  5612.8     .11       0
Bank Sta=4972.6,5026.2
XS Rating Curve= 0 ,0
Exp/Cntr=0.3,0.1

Type RM Length L Ch R = 1 ,1427    ,584,584,584
BEGIN DESCRIPTION:
CRYSTAL CREEK TRIBUTARY NO 1 3.0
END DESCRIPTION:
XS GIS Cut Line= 3
      3861416.35     10091601.58      3861216.71     10091434.48
      3860292.51     10091456.18
#Sta/Elev= 30
  4708.2  146.28  4744.9  145.14  4842.3  140.69  4856.6  138.51  4941.2  135.04
    4949  131.06  4955.5  130.13  4963.3  126.05 4973.43122.6165  4987.4  115.31
  5002.1  113.45  5012.7  113.45  5034.3  122.76  5039.3  121.13  5047.4  122.98
  5191.7  122.86  5267.5   120.5  5368.7  123.01  5527.6  129.56  5587.6  133.85
  5607.6  133.98    5655  136.88  5687.6  139.47  5707.4  139.48  5757.6  142.52
  5797.6  142.67  5827.6  146.05  5883.9  147.39  5887.1  147.59    5893  148.23
#Mann= 10 ,-1 , 0
  4708.2     .11       0  4744.9     .17       0 4973.43     .09       0
  5034.3     .17       0  5191.7     .15       0  5368.7     .17       0
    5655     .11       0  5707.4     .17       0  5883.9     .11       0
  5887.1     .17       0
Bank Sta=4973.43,5034.3
XS Rating Curve= 0 ,0
Exp/Cntr=0.3,0.1

Type RM Length L Ch R = 1 ,843     ,653,653,653
BEGIN DESCRIPTION:
CRYSTAL CREEK TRIBUTARY NO 1 2.0
END DESCRIPTION:
XS GIS Cut Line= 3
      3861422.88     10091549.52      3861106.03     10090915.82
      3860082.94     10091256.13
#Sta/Elev= 30
  4012.9  145.34  4028.2  145.37  4357.8  137.64  4417.3  132.53  4434.1  133.47
  4462.1  130.34    4593  123.64    4708  121.05  4786.8  121.42  4803.8  116.53
  4818.4  116.72  4844.8  120.71  4881.7  119.17  4908.1   122.5  4976.7   120.1
  4982.9  117.76  4997.7  111.93  5008.4  111.93 5018.08117.8402  5025.1   120.1
  5053.3   121.8  5103.3  123.26  5172.6  129.58    5278  135.99  5322.9  136.36
  5362.3  138.01  5493.4  138.08  5758.5  145.13  5768.8  145.41  5799.6  146.35
#Mann= 10 ,-1 , 0
  4012.9     .11       0  4028.2     .17       0    4593     .15       0
  4982.9     .09       0 5018.08     .15       0  5053.3     .17       0
  5322.9     .11       0  5493.4     .17       0  5758.5     .11       0
  5768.8     .17       0
Bank Sta=4982.9,5018.08
XS Rating Curve= 0 ,0
Exp/Cntr=0.3,0.1

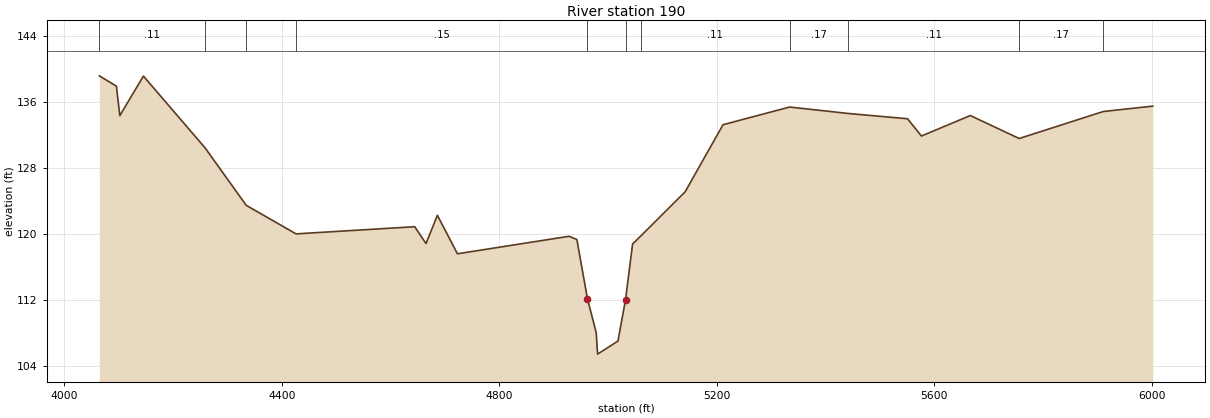
Type RM Length L Ch R = 1 ,190     ,0,0,0
BEGIN DESCRIPTION:
CRYSTAL CREEK TRIBUTARY NO 1 1.0
END DESCRIPTION:
XS GIS Cut Line= 3
       3861492.3     10091130.65       3860919.4     10090399.33
      3859958.03     10090705.32
#Sta/Elev= 30
  4064.3  139.14  4095.7  137.89    4102  134.32  4145.4  139.11  4258.9  130.41
  4334.5  123.46  4426.2     120  4644.5  120.87  4665.3  118.83  4686.2  122.25
  4723.1  117.59  4928.4  119.71  4942.8  119.32 4962.32112.1218  4978.4  108.04
  4980.9  105.44  5018.4  107.02 5032.32112.0336  5045.3  118.77  5060.9  119.78
  5141.9  125.09  5211.7  133.22  5334.2  135.36  5442.1  134.58  5551.1  133.94
  5576.7  131.85  5666.6  134.33  5756.5  131.55  5911.3  134.82  6002.2  135.47
#Mann= 11 ,-1 , 0
  4064.3     .11       0  4258.9     .17       0  4334.5     .11       0
  4426.2     .15       0 4962.32     .09       0 5032.32     .15       0
  5060.9     .11       0  5334.2     .17       0  5442.1     .11       0
  5756.5     .17       0  5911.3     .11       0
#XS Ineff= 2 , 0
       0  4686.2  122.25               0
Permanent Ineff=
       F       F
Bank Sta=4962.32,5032.32
XS Rating Curve= 0 ,0
Exp/Cntr=0.3,0.1

Chan Stop Cuts=-1
Use User Specified Reach Order=0
Composite Channel Slope=5

--- CRYSTAL CREEK TRIBUTARY NO 1.g10 (geometry) ---

Geom Title=Existing Conditions
Program Version=4.10

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
River Reach=CRYSTAL CREEK TR,Reach-1

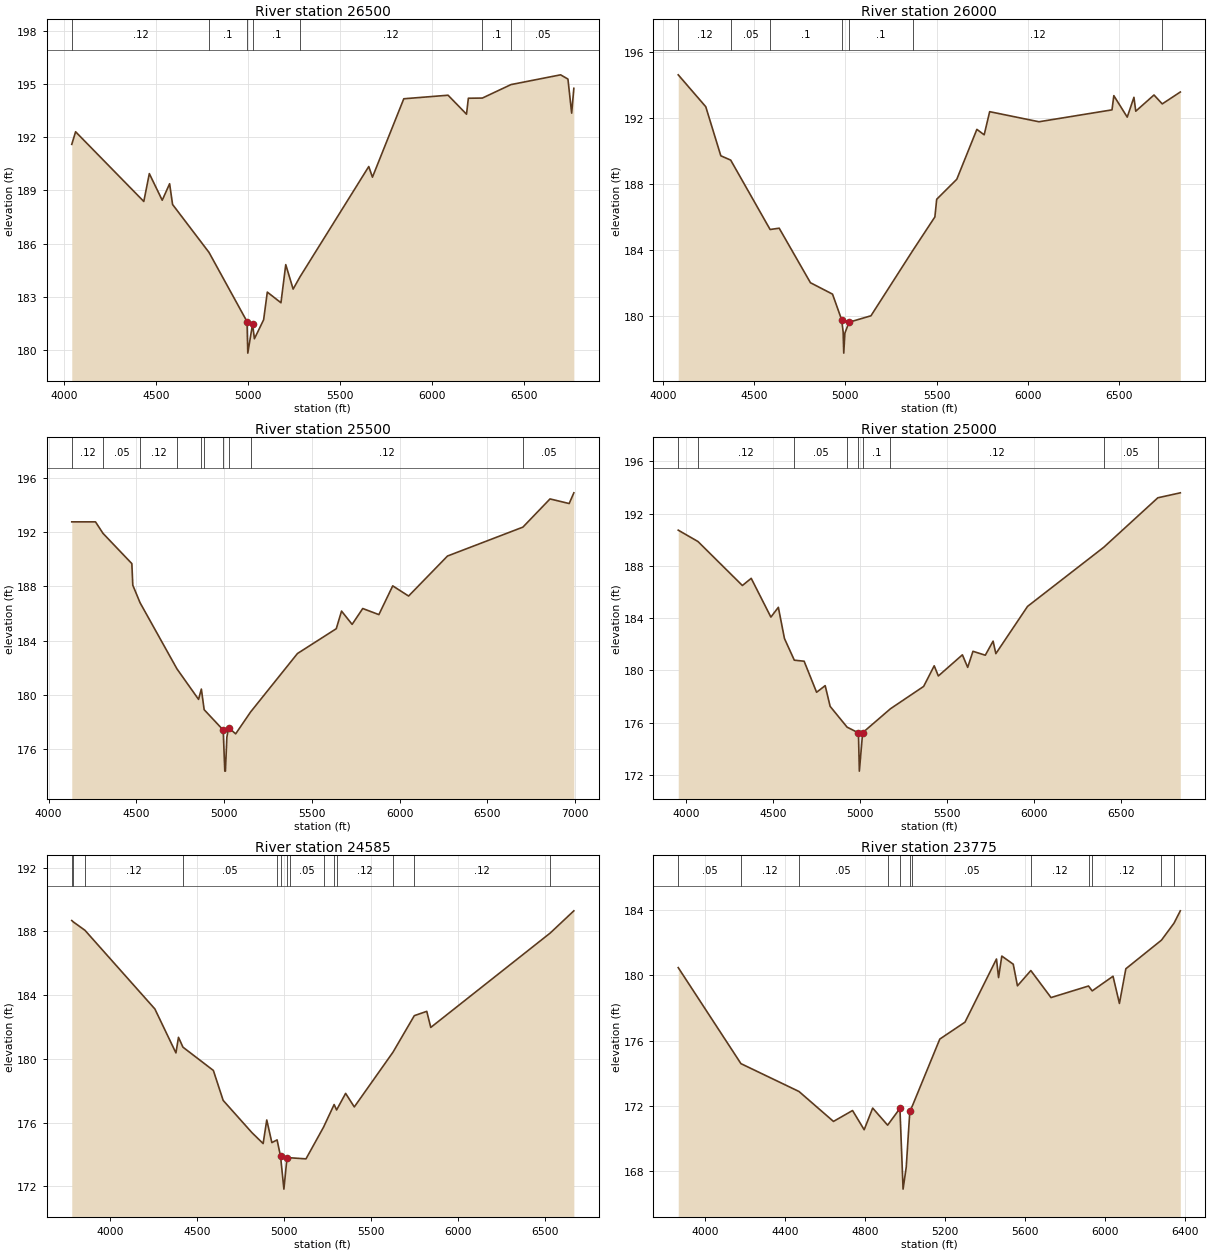
Type RM Length L Ch R = 1 ,26500   ,500,500,500
BEGIN DESCRIPTION:
CRYSTAL CREEK TRIBUTARY NO 1 53.0
END DESCRIPTION:
XS GIS Cut Line= 3
      3854628.64     10106084.02      3853671.08     10106035.18
      3851905.96     10106144.34
#Sta/Elev= 30
  4041.2   191.6    4062  192.31  4432.5  188.38  4462.5  189.95  4532.6  188.45
  4572.7  189.38  4588.8  188.21  4786.6  185.51  4993.2  181.61  4997.4  179.83
  5023.3  181.47  5033.3  180.64  5083.4  181.71  5103.4  183.27  5177.5  182.67
  5203.6  184.82  5243.7  183.44  5280.9  184.13  5654.5  190.35  5674.5  189.75
  5844.8  194.17  6085.3  194.37  6185.5   193.3  6195.5   194.2  6271.7  194.21
  6427.2  194.97  6696.5  195.52  6736.5  195.28  6756.6  193.36  6768.5  194.76
#Mann= 7 ,-1 , 0
  4041.2     .12       0  4786.6      .1       0  4993.2     .07       0
  5023.3      .1       0  5280.9     .12       0  6271.7      .1       0
  6427.2     .05       0
Bank Sta=4993.2,5023.3
XS Rating Curve= 0 ,0
Exp/Cntr=0.3,0.1

Type RM Length L Ch R = 1 ,26000   ,500,500,500
BEGIN DESCRIPTION:
CRYSTAL CREEK TRIBUTARY NO 1 52.0
END DESCRIPTION:
XS GIS Cut Line= 3
      3854596.89     10105693.44      3853688.24     10105584.99
      3851853.86     10105550.59
#Sta/Elev= 30
  4084.9   194.6  4235.7  192.67  4318.2   189.7  4372.2  189.44  4588.1  185.24
  4637.8  185.32    4809  182.02  4929.9  181.33  4980.2  179.77  4988.1  179.04
  4991.4  177.76  4997.7  178.97  5020.4  179.63  5140.4  180.02    5369  183.96
  5490.5     186  5500.5  187.07  5610.5  188.28  5720.5   191.3  5760.5  190.97
  5790.5  192.37  6060.6  191.76  6460.6  192.48  6470.6  193.34    6544  192.04
  6580.7  193.24  6590.7   192.4  6690.7  193.38  6735.7  192.84  6834.7  193.56
#Mann= 7 ,-1 , 0
  4084.9     .12       0  4372.2     .05       0  4588.1      .1       0
  4980.2     .07       0  5020.4      .1       0    5369     .12       0
  6735.7     .05       0
Bank Sta=4980.2,5020.4
XS Rating Curve= 0 ,0
Exp/Cntr=0.3,0.1

Type RM Length L Ch R = 1 ,25500   ,500,500,500
BEGIN DESCRIPTION:
CRYSTAL CREEK TRIBUTARY NO 1 51.0
END DESCRIPTION:
XS GIS Cut Line= 3
      3854664.96     10105489.05      3853863.55     10105156.17
      3851881.36     10104951.78
#Sta/Elev= 30
  4132.2  192.75  4267.4  192.75  4310.2   191.9  4474.5  189.67  4479.9  188.08
  4521.2  186.79  4731.5  181.91  4854.6  179.66  4870.5  180.42  4886.5   178.9
    4995   177.4  5004.1  174.37  5007.6  174.37  5015.8  176.87  5025.8  177.57
    5066  177.12  5150.9  178.73  5417.9  183.04  5639.1  184.87  5669.2  186.17
  5729.5  185.19  5789.9  186.36  5881.9  185.91  5960.8  188.03  6051.2  187.28
  6272.9  190.23  6702.4  192.36  6856.9  194.44  6966.1   194.1  6992.7  194.89
#Mann= 10 ,-1 , 0
  4132.2     .12       0  4310.2     .05       0  4521.2     .12       0
  4731.5      .1       0  4870.5     .05       0  4886.5      .1       0
    4995     .07       0  5025.8      .1       0  5150.9     .12       0
  6702.4     .05       0
Bank Sta=4995,5025.8
XS Rating Curve= 0 ,0
Exp/Cntr=0.3,0.1

Type RM Length L Ch R = 1 ,25000   ,415,415,415
BEGIN DESCRIPTION:
CRYSTAL CREEK TRIBUTARY NO 1 50.0
END DESCRIPTION:
XS GIS Cut Line= 3
      3854760.33     10105389.11      3853958.24     10104716.95
      3852140.34     10104425.59
#Sta/Elev= 30
  3953.5  190.74    4067  189.87  4322.5   186.5  4373.2  187.05  4486.4  184.08
  4529.3  184.83  4564.4  182.44  4621.1  180.78  4677.6   180.7  4749.2  178.32
  4798.6  178.83  4827.2  177.24  4924.6  175.65  4989.9  175.21  4995.2  172.28
 5014.05 175.222  5174.2  177.06    5365  178.77  5425.7  180.35  5449.5  179.57
  5587.8  181.19  5618.2  180.23  5648.6  181.46  5719.5  181.16  5764.4  182.24
  5780.2  181.28  5962.5   184.9  6400.9  189.43  6711.9  193.22  6841.1   193.6
#Mann= 9 ,-1 , 0
  3953.5     .05       0    4067     .12       0  4621.1     .05       0
  4924.6      .1       0  4989.9     .07       0 5014.05      .1       0
  5174.2     .12       0  6400.9     .05       0  6711.9     .12       0
Bank Sta=4989.9,5014.05
XS Rating Curve= 0 ,0
Exp/Cntr=0.3,0.1

Type RM Length L Ch R = 1 ,24585   ,810,810,810
BEGIN DESCRIPTION:
CRYSTAL CREEK TRIBUTARY NO 1 49.0
END DESCRIPTION:
XS GIS Cut Line= 3
      3854846.64     10105330.08      3854130.26     10104362.41
      3852676.86     10103519.36
#Sta/Elev= 30
  3779.5  188.68  3788.8  188.59  3855.1  188.07  4256.9  183.13  4377.9  180.37
  4392.5  181.35  4418.3  180.73  4592.9  179.27  4649.2  177.39  4814.1  175.37
  4878.8  174.68  4899.7  176.16  4928.9  174.74    4959  174.91    4979  173.87
  4998.1  171.82  5015.6  173.75  5030.5  173.79    5125  173.72  5225.8  175.71
  5286.7  177.13  5300.9  176.79  5352.7  177.83  5402.5  176.98    5625  180.42
  5747.3  182.71  5818.8  182.98  5841.8  181.97  6528.4   187.9  6663.7  189.29
#Mann= 14 ,-1 , 0
  3779.5     .12       0  3788.8     .05       0  3855.1     .12       0
  4418.3     .05       0    4959      .1       0    4979     .07       0
  5015.6      .1       0  5030.5     .05       0  5225.8      .1       0
  5286.7     .05       0  5300.9     .12       0    5625     .05       0
  5747.3     .12       0  6528.4     .05       0
Bank Sta=4979,5015.6
XS Rating Curve= 0 ,0
Exp/Cntr=0.3,0.1

Type RM Length L Ch R = 1 ,23775   ,440,440,440
BEGIN DESCRIPTION:
CRYSTAL CREEK TRIBUTARY NO 1 48.0
END DESCRIPTION:
XS GIS Cut Line= 4
      3855187.73     10104268.19      3855139.27     10103931.82
      3854385.64     10103684.81      3853071.71     10103263.31
#Sta/Elev= 30
  3866.2  180.48  4180.1  174.58  4470.5  172.87  4643.1  171.03  4738.6   171.7
  4796.8  170.52  4839.4  171.85  4914.2   170.8  4975.7  171.83  4991.5  166.87
  5007.3  168.22  5025.4  171.68  5037.9  171.98  5175.3  176.09  5301.4  177.13
  5458.9  181.01  5469.4  179.87  5485.6  181.19  5542.9  180.69  5563.9  179.36
  5630.9   180.3  5731.9  178.64  5919.6  179.35    5938  179.05  6042.2  179.95
  6074.3  178.28  6106.4  180.41  6284.8  182.17  6347.4  183.21    6379  183.97
#Mann= 12 ,-1 , 0
  3866.2     .05       0  4180.1     .12       0  4470.5     .05       0
  4914.2      .1       0  4975.7     .07       0  5025.4      .1       0
  5037.9     .05       0  5630.9     .12       0  5919.6     .05       0
    5938     .12       0  6284.8     .05       0  6347.4     .12       0
Bank Sta=4975.7,5025.4
XS Rating Curve= 0 ,0
Exp/Cntr=0.3,0.1

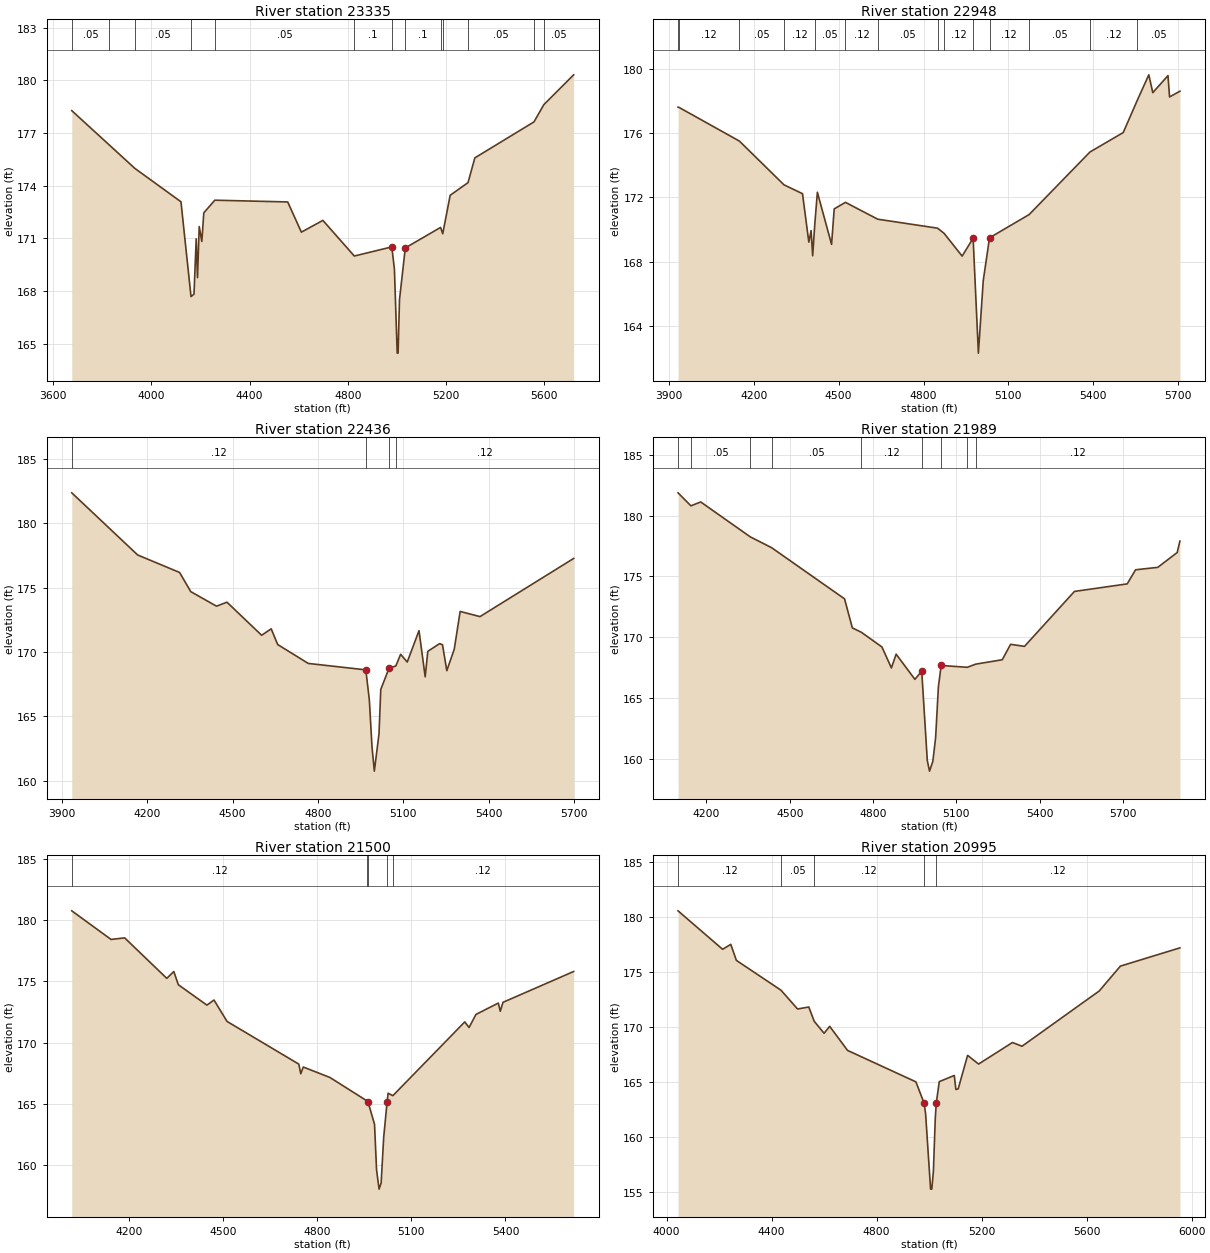
Type RM Length L Ch R = 1 ,23335   ,387,387,387
BEGIN DESCRIPTION:
CRYSTAL CREEK TRIBUTARY NO 1 47.0
END DESCRIPTION:
XS GIS Cut Line= 3
       3855997.6     10104035.32      3854733.73     10103591.06
      3854067.04     10103363.62
#Sta/Elev= 30
  3676.1  178.28  3829.3  176.32  3933.2  174.99  4120.9  173.09  4161.8  167.69
    4174  167.83  4182.9  170.98  4188.2  168.77  4195.2  171.68  4205.8  170.83
  4213.9  172.46  4258.8  173.18  4555.6  173.08  4611.3  171.36  4698.9  172.03
  4826.9     170  4979.6  170.52  4990.2  169.25  5001.6  164.47  5005.1  164.47
  5010.9  167.51  5034.5  170.46  5178.3  171.63    5187  171.27  5217.3  173.46
    5290  174.18  5317.8  175.59  5558.7  177.64  5598.7  178.62  5720.2  180.32
#Mann= 13 ,-1 , 0
  3676.1     .05       0  3829.3     .12       0  3933.2     .05       0
  4161.8     .12       0  4258.8     .05       0  4826.9      .1       0
  4979.6     .07       0  5034.5      .1       0  5178.3     .05       0
    5187     .12       0    5290     .05       0  5558.7     .12       0
  5598.7     .05       0
Bank Sta=4979.6,5034.5
XS Rating Curve= 0 ,0
Exp/Cntr=0.3,0.1

Type RM Length L Ch R = 1 ,22948   ,512,512,512
BEGIN DESCRIPTION:
CRYSTAL CREEK TRIBUTARY NO 1 46.0
END DESCRIPTION:
XS GIS Cut Line= 3
      3855980.25     10103990.36      3855030.61     10103507.73
      3854391.44      10103199.4
#Sta/Elev= 30
  3931.9  177.62  3934.3  177.62  4148.9  175.51  4306.8  172.78  4372.1  172.23
  4394.5  169.21  4402.5  169.93  4408.1  168.36  4415.4  170.28  4424.7  172.32
  4474.9  169.07  4484.2  171.28  4523.9  171.69  4638.1  170.64  4849.7  170.08
  4872.7  169.76  4936.6  168.34  4975.5  169.45  4994.1  162.29  5011.3  166.81
  5033.5  169.48  5173.7  170.93  5388.8  174.83  5506.3  176.04  5556.3  178.06
  5596.8  179.64  5610.9  178.53  5664.6  179.59  5670.2  178.26  5706.8  178.62
#Mann= 14 ,-1 , 0
  3931.9     .05       0  3934.3     .12       0  4148.9     .05       0
  4306.8     .12       0  4415.4     .05       0  4523.9     .12       0
  4638.1     .05       0  4849.7      .1       0  4872.7     .12       0
  4975.5     .07       0  5033.5     .12       0  5173.7     .05       0
  5388.8     .12       0  5556.3     .05       0
Bank Sta=4975.5,5033.5
XS Rating Curve= 0 ,0
Exp/Cntr=0.3,0.1

Type RM Length L Ch R = 1 ,22436   ,447,447,447
BEGIN DESCRIPTION:
CRYSTAL CREEK TRIBUTARY NO 1 45.0
END DESCRIPTION:
XS GIS Cut Line= 3
      3856209.46     10103667.47      3855266.72     10103214.32
      3854571.71     10103034.07
#Sta/Elev= 30
  3934.5  182.36  4166.1  177.53  4313.5  176.17  4352.8  174.68  4443.3  173.55
    4480  173.86  4601.8  171.29  4635.5  171.79  4658.2  170.57  4765.8   169.1
  4968.1   168.6  4980.5  166.24  4989.7  162.63    4998  160.73  5014.4  163.64
  5020.6  167.08  5049.8  168.74  5073.5   168.9  5090.4  169.81  5113.6  169.21
    5155  171.65  5176.7  168.06  5185.9  170.04  5227.3  170.64  5237.6  170.55
  5252.7  168.54  5278.9  170.21  5299.6  173.14  5369.3  172.74  5698.5  177.26
#Mann= 4 ,-1 , 0
  3934.5     .12       0  4968.1     .07       0  5049.8      .1       0
  5073.5     .12       0
Bank Sta=4968.1,5049.8
XS Rating Curve= 0 ,0
Exp/Cntr=0.3,0.1

Type RM Length L Ch R = 1 ,21989   ,489,489,489
BEGIN DESCRIPTION:
CRYSTAL CREEK TRIBUTARY NO 1 44.0
END DESCRIPTION:
XS GIS Cut Line= 3
      3856267.85     10103361.07      3855490.68     10102981.69
      3854548.02     10102976.48
#Sta/Elev= 30
  4097.5  181.87  4143.9   180.8  4179.1  181.12  4358.3  178.24  4434.4  177.36
  4697.2  173.15  4725.3  170.76  4757.8   170.4  4831.9  169.19    4866  167.47
    4883   168.6  4950.6  166.53  4975.2   167.2  4995.2  159.86  5003.2  158.98
  5015.2  159.79  5025.2  161.73  5035.2  165.92  5045.2  167.67    5139  167.52
  5169.7  167.78  5265.2  168.14  5295.2  169.41  5345.2  169.24  5525.2  173.76
  5715.2  174.38  5745.2  175.54  5825.2  175.74  5895.2  176.96    5905   177.9
#Mann= 9 ,-1 , 0
  4097.5     .12       0  4143.9     .05       0  4358.3     .12       0
  4434.4     .05       0  4757.8     .12       0  4975.2     .07       0
  5045.2     .12       0    5139      .1       0  5169.7     .12       0
Bank Sta=4975.2,5045.2
XS Rating Curve= 0 ,0
Exp/Cntr=0.3,0.1

Type RM Length L Ch R = 1 ,21500   ,505,505,505
BEGIN DESCRIPTION:
CRYSTAL CREEK TRIBUTARY NO 1 43.0
END DESCRIPTION:
XS GIS Cut Line= 3
      3856392.45     10103193.17      3855629.23     10102575.58
      3855126.24     10102217.73
#Sta/Elev= 30
  4018.2  180.77  4143.5  178.43  4186.7  178.56    4321  175.25  4343.4  175.81
  4357.7  174.73  4448.9  173.06  4471.3  173.48  4512.9  171.73  4741.5  168.24
  4747.9  167.45  4755.8     168  4840.6  167.15  4960.3  165.21  4962.1  165.16
  4982.9  163.31  4989.3  159.61  4997.4  158.02  5003.9  158.52  5012.1  162.27
 5022.94 165.147  5026.2  165.86  5041.3  165.66  5270.4  171.69    5284  171.23
    5306   172.3  5377.3  173.23  5383.5  172.56  5392.1  173.29  5617.3  175.81
#Mann= 5 ,-1 , 0
  4018.2     .12       0  4960.3      .1       0  4962.1     .07       0
 5022.94      .1       0  5041.3     .12       0
Bank Sta=4962.1,5022.94
XS Rating Curve= 0 ,0
Exp/Cntr=0.3,0.1

Type RM Length L Ch R = 1 ,20995   ,495,495,495
BEGIN DESCRIPTION:
CRYSTAL CREEK TRIBUTARY NO 1 42.0
END DESCRIPTION:
XS GIS Cut Line= 3
      3856438.73     10103134.41      3855923.09     10102277.61
      3855173.11      10101759.4
#Sta/Elev= 30
  4043.8  180.55  4213.6  177.05  4244.7   177.5  4266.1  176.04  4435.9  173.33
  4499.1  171.62  4541.9   171.8  4562.5   170.5  4600.2  169.41  4621.5  170.04
  4689.5  167.85  4949.8  164.99  4980.8  163.07  4986.7  162.11  5005.8  155.23
  5010.3  155.23  5016.4  156.83  5023.6  161.65 5027.39 163.062  5038.9  165.01
    5096  165.57  5102.1   164.3  5110.9  164.35  5146.7   167.4  5188.6  166.61
  5317.6  168.57    5354  168.23  5648.2  173.26  5728.7  175.52  5955.4  177.18
#Mann= 5 ,-1 , 0
  4043.8     .12       0  4435.9     .05       0  4562.5     .12       0
  4980.8     .07       0 5027.39     .12       0
Bank Sta=4980.8,5027.39
XS Rating Curve= 0 ,0
Exp/Cntr=0.3,0.1

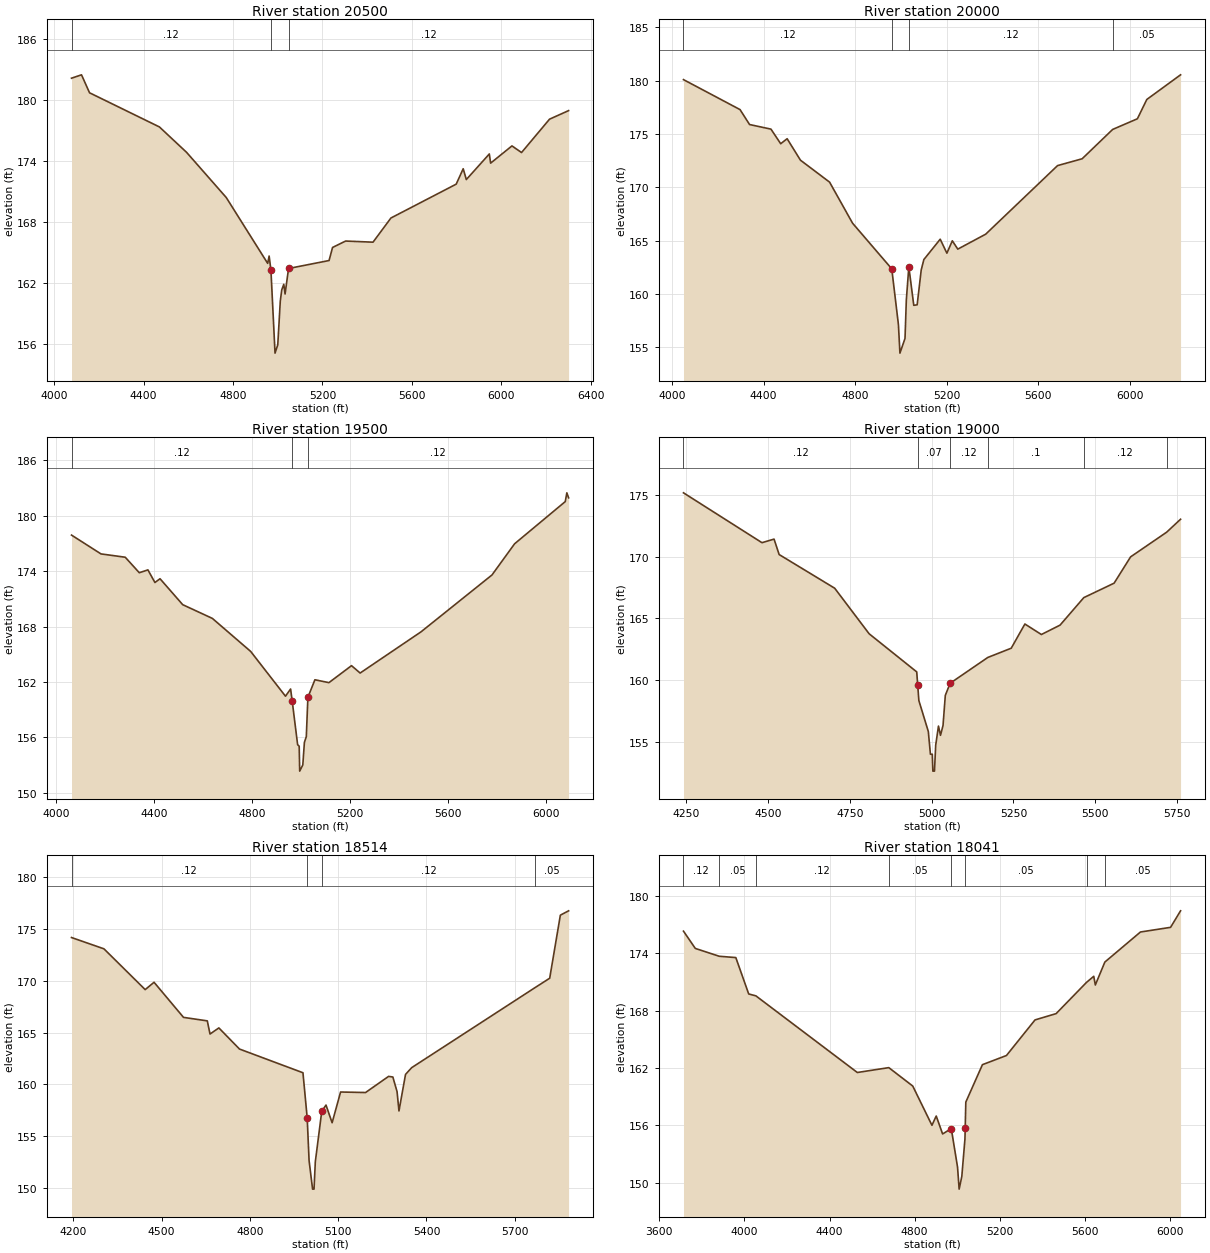
Type RM Length L Ch R = 1 ,20500   ,500,500,500
BEGIN DESCRIPTION:
CRYSTAL CREEK TRIBUTARY NO 1 41.0
END DESCRIPTION:
XS GIS Cut Line= 3
      3856920.51     10102631.79      3856203.11     10102051.52
      3855084.52     10101386.97
#Sta/Elev= 30
  4077.3  182.11    4122  182.44  4157.9  180.68  4470.5  177.33    4592  174.84
  4769.5  170.41  4954.9  163.95  4961.4  164.67 4969.48 163.275  4987.8  155.15
    5000  155.96  5011.3  160.25  5017.7  161.34  5026.9   161.9  5032.7  160.95
  5048.3  163.45  5229.5  164.23  5245.1  165.51  5303.5  166.14  5426.2  166.03
  5506.3   168.4  5798.3  171.72  5829.6  173.23  5843.6  172.17  5946.5  174.68
  5952.3  173.78  6047.7  175.47  6090.6  174.82  6215.8  178.09  6301.1  178.93
#Mann= 3 , 0 , 0
  4077.3     .12       0 4969.48     .07       0  5048.3     .12       0
Bank Sta=4969.48,5048.3
XS Rating Curve= 0 ,0
Exp/Cntr=0.3,0.1

Type RM Length L Ch R = 1 ,20000   ,500,500,500
BEGIN DESCRIPTION:
CRYSTAL CREEK TRIBUTARY NO 1 40.0
END DESCRIPTION:
XS GIS Cut Line= 3
      3857055.92     10102238.56      3856299.74     10101662.83
      3855171.69     10101192.17
#Sta/Elev= 30
  4049.6   180.1  4296.8  177.29  4338.4  175.89  4431.9  175.46  4474.5  174.09
  4502.7  174.56  4560.8  172.55  4688.2  170.49  4788.7  166.64    4960  162.36
  4989.1  157.13  4995.7  154.46  5017.9  155.84  5023.7  159.47  5034.6  162.55
  5056.2  158.94    5071  158.99  5088.7  162.25  5100.2  163.23  5171.7  165.14
  5200.9  163.83  5224.7  164.99  5248.6  164.21  5370.5  165.61  5684.7  172.04
  5792.1  172.68  5925.5  175.43  6033.6  176.43  6074.8  178.24  6222.3  180.55
#Mann= 4 ,-1 , 0
  4049.6     .12       0    4960     .07       0  5034.6     .12       0
  5925.5     .05       0
Bank Sta=4960,5034.6
XS Rating Curve= 0 ,0
Exp/Cntr=0.3,0.1

Type RM Length L Ch R = 1 ,19500   ,500,500,500
BEGIN DESCRIPTION:
CRYSTAL CREEK TRIBUTARY NO 1 39.0
END DESCRIPTION:
XS GIS Cut Line= 3
      3857100.17     10102038.02      3856507.16     10101313.32
      3855667.88      10100611.1
#Sta/Elev= 30
  4063.6  177.91    4184  175.87  4283.1  175.51  4340.5  173.83  4375.7  174.14
  4404.4  172.77  4425.2  173.18  4517.8  170.37  4639.1  168.88  4795.6   165.3
  4937.7  160.45  4958.6  161.23    4965  159.96  4987.3   155.2  4993.7  155.03
  4995.8  152.33  5008.5     153    5015  155.45  5022.8  156.07  5029.3  160.33
  5057.9  162.23  5115.2  161.92  5207.5  163.76  5242.7  162.96  5491.2  167.42
  5781.4  173.59  5873.8  176.97  6080.7  181.54  6087.2  182.49  6094.3  181.95
#Mann= 3 , 0 , 0
  4063.6     .12       0    4965     .07       0  5029.3     .12       0
Bank Sta=4965,5029.3
XS Rating Curve= 0 ,0
Exp/Cntr=0.3,0.1

Type RM Length L Ch R = 1 ,19000   ,486,486,486
BEGIN DESCRIPTION:
CRYSTAL CREEK TRIBUTARY NO 1 38.0
END DESCRIPTION:
XS GIS Cut Line= 3
      3857118.42     10101834.94      3856817.77     10101139.33
       3856373.6     10100522.39
#Sta/Elev= 30
  4242.2  175.18  4481.9  171.14  4518.8  171.43  4534.3  170.18    4704  167.45
  4809.1  163.76  4954.5  160.67  4957.4 159.635    4961  158.35  4989.9  155.84
  4996.3     154    5002     154  5003.8  152.63  5008.7  152.63  5012.4  154.73
  5020.9  156.28  5027.1  155.53  5034.8  156.33  5041.8  158.77  5056.5  159.75
  5171.5  161.84  5243.1  162.59  5284.8  164.55  5335.2   163.7  5392.2  164.46
  5464.8  166.69  5557.3  167.86  5607.6  169.99  5717.7  171.99  5760.2  173.04
#Mann= 6 ,-1 , 0
  4242.2     .12       0  4957.4     .07       0  5056.5     .12       0
  5171.5      .1       0  5464.8     .12       0  5717.7     .05       0
Bank Sta=4957.4,5056.5
XS Rating Curve= 0 ,0
Exp/Cntr=0.3,0.1

Type RM Length L Ch R = 1 ,18514   ,473,473,473
BEGIN DESCRIPTION:
CRYSTAL CREEK TRIBUTARY NO 1 37.0
END DESCRIPTION:
XS GIS Cut Line= 3
      3857267.85      10101761.1      3857225.17      10100981.6
      3856517.86     10100411.08
#Sta/Elev= 30
  4193.7  174.18  4303.9  173.09  4444.1  169.15  4474.2  169.86  4574.3  166.47
  4655.2  166.13  4664.4  164.86  4694.5  165.45  4764.6  163.41  4980.3  161.12
  4994.7  156.76  5001.1  152.64    5013  149.88  5017.9  149.88  5022.3  152.52
  5044.2   157.4  5058.6     158  5079.4  156.29  5108.2  159.26    5193  159.21
  5271.4  160.77  5285.8  160.71  5300.1   159.3  5306.6  157.43  5328.9  160.96
  5349.7  161.61  5769.5  169.35  5818.9  170.25  5855.1  176.34  5883.1  176.76
#Mann= 4 ,-1 , 0
  4193.7     .12       0  4994.7     .07       0  5044.2     .12       0
  5769.5     .05       0
Bank Sta=4994.7,5044.2
XS Rating Curve= 0 ,0
Exp/Cntr=0.3,0.1

Type RM Length L Ch R = 1 ,18041   ,303,303,303
BEGIN DESCRIPTION:
CRYSTAL CREEK TRIBUTARY NO 1 36.0
END DESCRIPTION:
XS GIS Cut Line= 3
      3857371.87     10101856.58      3857288.54     10100536.29
       3856547.7     10099844.84
#Sta/Elev= 30
  3713.7  176.34  3769.3  174.53  3881.7  173.71  3959.7  173.57  4020.2  169.76
    4054  169.56  4530.8  161.53  4678.7  162.04  4791.3  160.11  4881.5     156
  4901.6  156.97  4931.6  155.09  4972.4  155.65  5001.8  151.62  5009.3  149.31
  5021.8  150.63  5036.6  154.55 5037.86 155.742  5040.7  158.43  5118.8  162.35
  5231.7  163.31    5366  167.04  5465.2   167.7  5607.9  170.97    5642  171.61
  5649.4   170.7  5694.1   173.1  5861.4  176.25  6003.1  176.74    6050  178.47
#Mann= 8 ,-1 , 0
  3713.7     .12       0  3881.7     .05       0    4054     .12       0
  4678.7     .05       0  4972.4     .07       0 5037.86     .05       0
  5607.9     .12       0  5694.1     .05       0
Bank Sta=4972.4,5037.86
XS Rating Curve= 0 ,0
Exp/Cntr=0.3,0.1