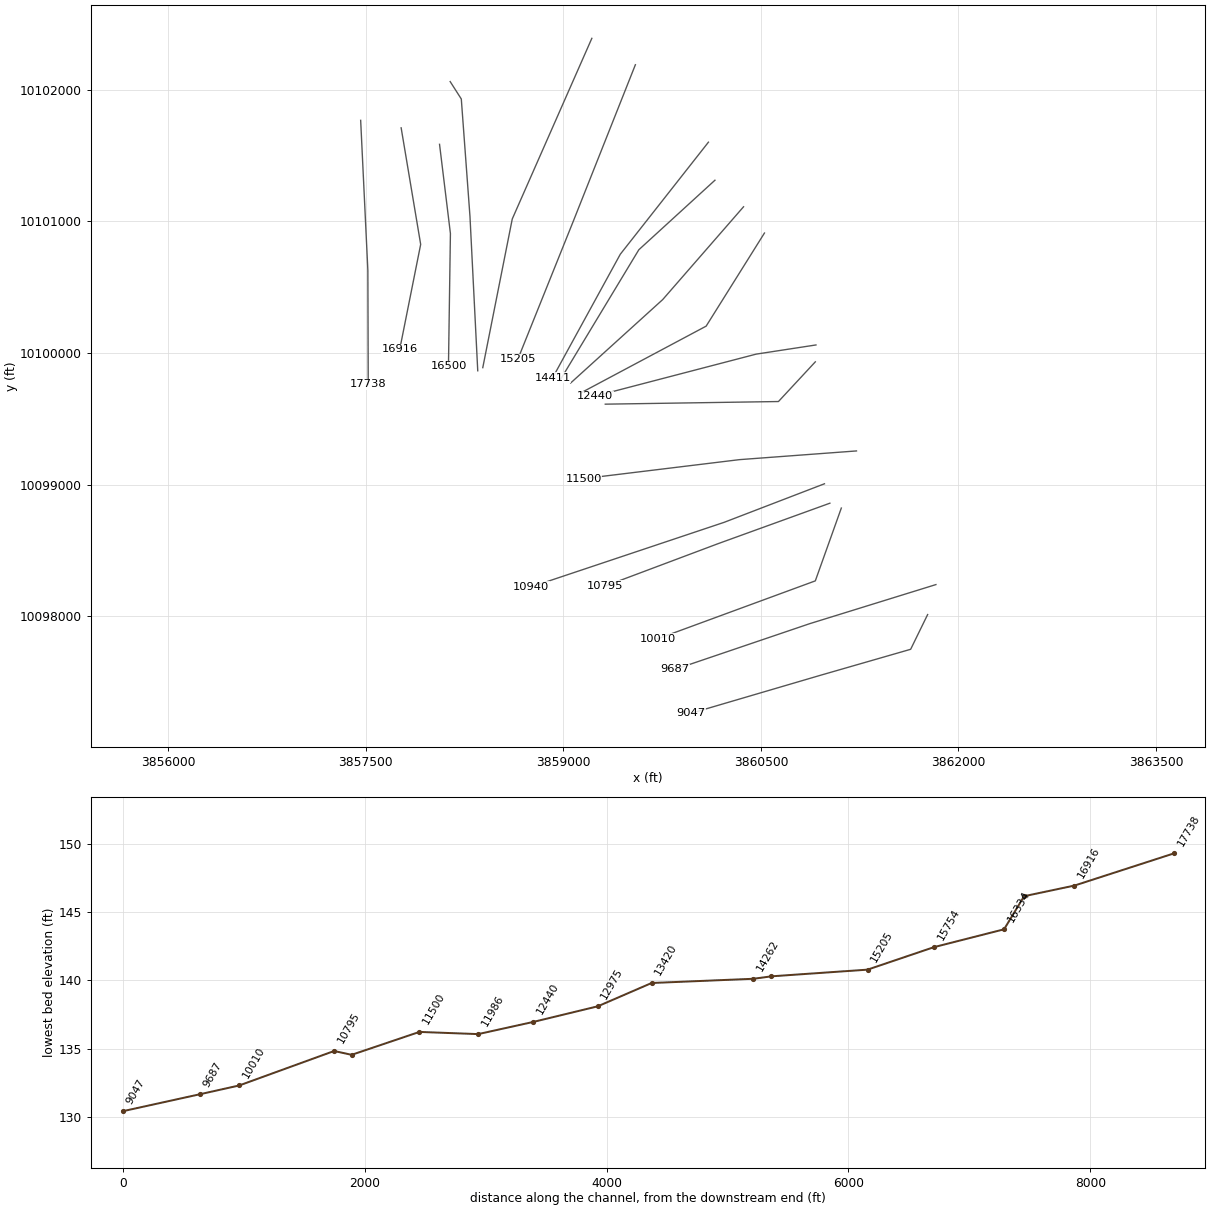
HEC-RAS study CRYSTAL CREEK TRIBUTARY NO 1.prj: CRYSTAL CREEK TRIBUTARY NO 1 Base Level Engineering

--- CRYSTAL CREEK TRIBUTARY NO 1.g10 (geometry) --- (continued)

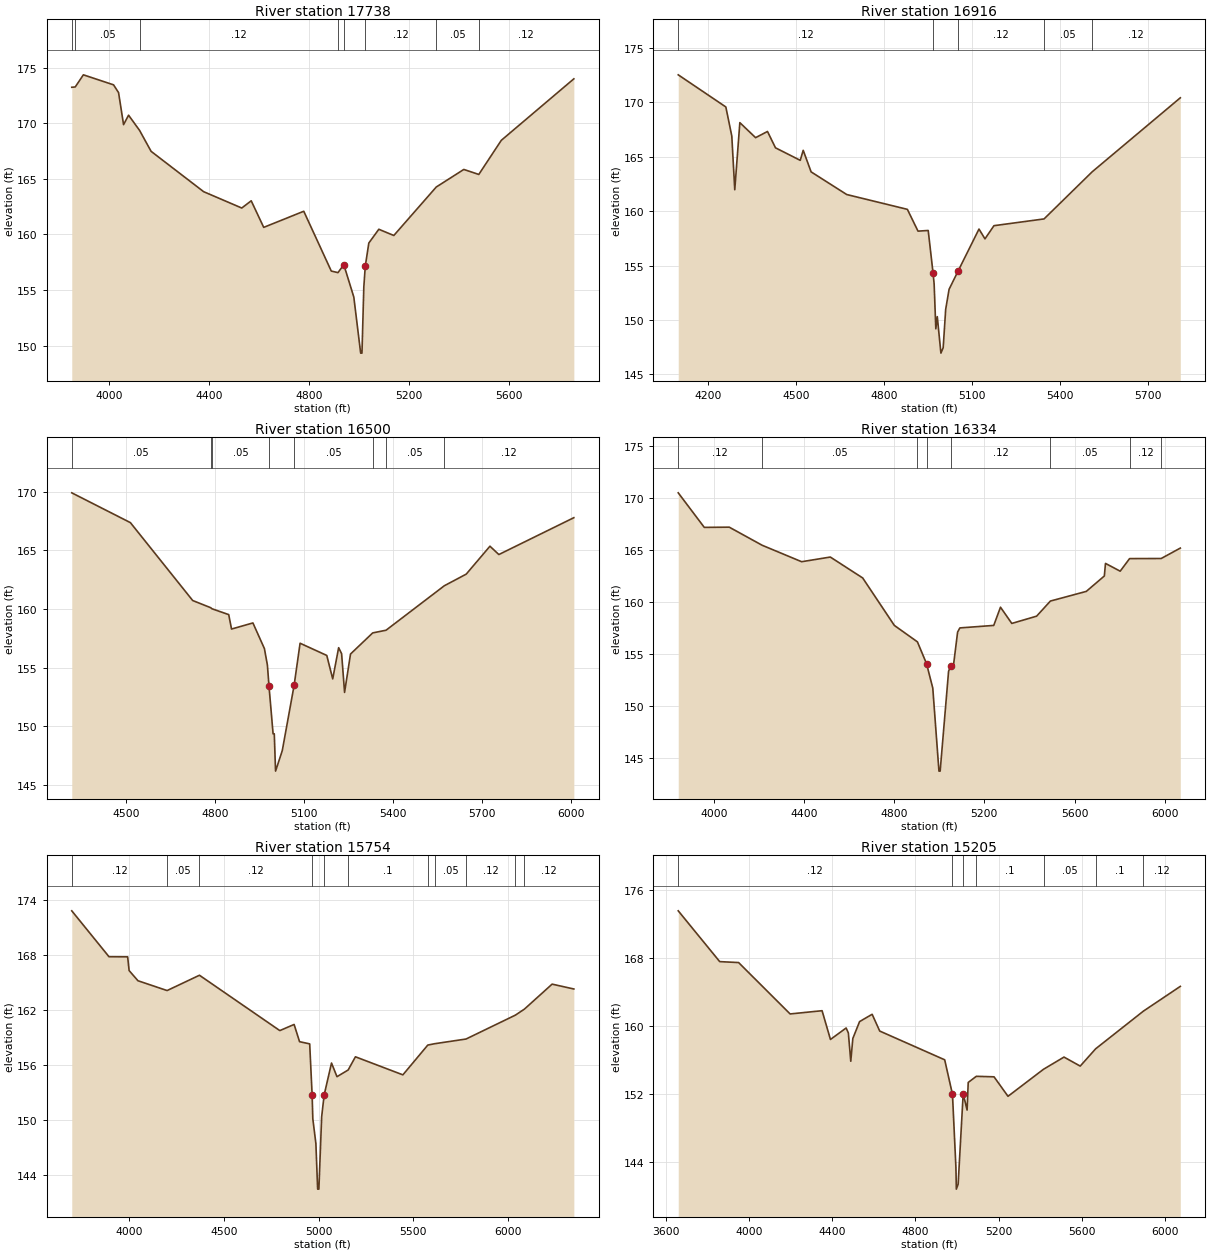
Type RM Length L Ch R = 1 ,17738   ,822,822,822
BEGIN DESCRIPTION:
CRYSTAL CREEK TRIBUTARY NO 1 35.0
END DESCRIPTION:
XS GIS Cut Line= 3
      3857460.42     10101768.01       3857515.1     10100627.43
      3857517.85     10099761.02
#Sta/Elev= 30
    3852  173.23  3865.9  173.26  3898.4  174.35  4019.1  173.45  4039.2  172.75
  4059.2  169.87  4079.2  170.72  4123.3  169.35  4169.3  167.47  4379.5  163.84
    4532  162.37  4569.8  163.02  4619.8  160.63    4780  162.08  4890.1   156.7
  4916.8  156.56  4940.2  157.27  4980.2  154.36  5007.6  149.32  5012.8  149.32
  5020.2  155.26 5025.94  157.12  5040.2  159.22  5080.2  160.46  5140.2   159.9
    5310  164.26  5420.2  165.84  5480.1  165.39  5570.2  168.46  5860.3  173.99
#Mann= 8 ,-1 , 0
    3852     .12       0  3865.9     .05       0  4123.3     .12       0
  4916.8     .05       0  4940.2     .07       0 5025.94     .12       0
    5310     .05       0  5480.1     .12       0
Bank Sta=4940.2,5025.94
XS Rating Curve= 0 ,0
Exp/Cntr=0.3,0.1

Type RM Length L Ch R = 1 ,16916   ,416,416,416
BEGIN DESCRIPTION:
CRYSTAL CREEK TRIBUTARY NO 1 34.0
END DESCRIPTION:
XS GIS Cut Line= 3
      3857767.86     10101711.04      3857916.14     10100825.35
      3857757.28     10100028.45
#Sta/Elev= 30
    4099  172.51  4261.2  169.56  4281.5  166.89  4291.6  161.96  4308.9  168.12
  4362.6  166.74  4403.1  167.31  4430.3  165.81  4514.7  164.66  4524.8  165.58
  4551.7   163.6  4673.1  161.52  4879.7  160.16  4915.9  158.16  4950.7  158.22
 4967.06 154.346  4970.9   153.3  4976.6  149.19  4981.6  150.31    4994  146.96
  5001.7  147.46  5010.2  150.98  5021.8  152.82  5052.4  154.49  5123.7  158.35
  5144.1  157.45  5174.7  158.66  5345.3  159.28  5509.5  163.61  5809.6   170.4
#Mann= 5 ,-1 , 0
    4099     .12       0 4967.06     .07       0  5052.4     .12       0
  5345.3     .05       0  5509.5     .12       0
Bank Sta=4967.06,5052.4
XS Rating Curve= 0 ,0
Exp/Cntr=0.3,0.1

Type RM Length L Ch R = 1 ,16500   ,166,166,166
BEGIN DESCRIPTION:
CRYSTAL CREEK TRIBUTARY NO 1 33.0
END DESCRIPTION:
XS GIS Cut Line= 3
      3858059.37     10101585.75      3858141.99     10100908.07
      3858127.08     10099898.28
#Sta/Elev= 30
  4317.3   169.9  4514.9  167.36    4725  160.72  4785.7  160.11  4789.8  160.02
  4846.4  159.52  4855.9  158.29    4928  158.81  4966.8  156.62  4976.8  155.22
 4982.17 153.434    4996  149.36    5000  149.36  5004.3  146.18    5027  147.93
    5067  153.51    5087  157.08    5177  156.04    5197  154.04    5217   156.7
    5227  156.19    5237  152.89    5257  156.16  5331.8  157.96  5376.8  158.19
  5573.3  161.98  5647.1  162.97  5727.1  165.35  5757.1  164.64  6009.9  167.78
#Mann= 8 ,-1 , 0
  4317.3     .05       0  4785.7     .12       0  4789.8     .05       0
 4982.17     .07       0    5067     .05       0  5331.8     .12       0
  5376.8     .05       0  5573.3     .12       0
Bank Sta=4982.17,5067
XS Rating Curve= 0 ,0
Exp/Cntr=0.3,0.1

Type RM Length L Ch R = 1 ,16334   ,580,580,580
BEGIN DESCRIPTION:
CRYSTAL CREEK TRIBUTARY NO 1 32.0
END DESCRIPTION:
XS GIS Cut Line= 4
      3858140.12     10102062.52      3858224.65     10101930.17
      3858290.56      10101037.1      3858349.52     10099864.82
#Sta/Elev= 30
  3842.8  170.49  3958.3  167.17  4069.1  167.19  4215.1  165.45    4390  163.87
  4517.1  164.32  4660.7  162.31  4801.1  157.75  4903.4  156.17  4943.7  154.08
  4971.5  151.73  4998.9  143.75  5004.2  143.75  5041.6  153.35  5051.6  153.88
  5061.6  153.62  5081.6  157.11  5091.6  157.51  5241.8  157.75  5271.8   159.5
  5321.9  157.94    5432  158.64    5493  160.09  5652.3  161.02  5732.3   162.5
  5737.3  163.71  5802.5  162.96  5844.2  164.17  5984.3  164.18  6069.1  165.18
#Mann= 8 ,-1 , 0
  3842.8     .12       0  4215.1     .05       0  4903.4     .12       0
  4943.7     .07       0  5051.6     .12       0    5493     .05       0
  5844.2     .12       0  5984.3     .05       0
Bank Sta=4943.7,5051.6
XS Rating Curve= 0 ,0
Exp/Cntr=0.3,0.1

Type RM Length L Ch R = 1 ,15754   ,549,549,549
BEGIN DESCRIPTION:
CRYSTAL CREEK TRIBUTARY NO 1 31.0
END DESCRIPTION:
XS GIS Cut Line= 3
      3859215.86     10102391.12      3858611.67     10101018.69
      3858387.72      10099888.5
#Sta/Elev= 30
  3696.9  172.81  3893.6   167.8    3992  167.79  3999.8  166.29  4046.5  165.18
  4200.4  164.11  4371.3  165.78  4795.7  159.74  4871.2  160.41    4900  158.53
  4953.5  158.29  4966.4 152.688    4970  150.11  4986.2  147.42  4995.5  142.44
    5002  142.44  5016.7  150.33  5029.9  152.72  5068.8   156.2  5097.6  154.71
  5156.6  155.44    5195  156.88  5445.7  154.91  5577.2  158.16  5614.2  158.31
  5779.2  158.82  6040.1  161.43  6087.9  162.09  6233.8  164.81  6348.6  164.28
#Mann= 11 ,-1 , 0
  3696.9     .12       0  4200.4     .05       0  4371.3     .12       0
  4966.4     .07       0  5029.9     .12       0  5156.6      .1       0
  5577.2     .12       0  5614.2     .05       0  5779.2     .12       0
  6040.1     .05       0  6087.9     .12       0
Bank Sta=4966.4,5029.9
XS Rating Curve= 0 ,0
Exp/Cntr=0.3,0.1

Type RM Length L Ch R = 1 ,15205   ,794,794,794
BEGIN DESCRIPTION:
CRYSTAL CREEK TRIBUTARY NO 1 30.0
END DESCRIPTION:
XS GIS Cut Line= 3
      3859546.57     10102190.56      3859072.61     10100995.25
      3858653.35     10099951.02
#Sta/Elev= 30
  3661.1   173.5  3860.3  167.53    3951  167.42  4198.4  161.38  4351.9  161.76
  4392.1  158.38  4467.4  159.73  4478.1  159.14  4489.7  155.82  4499.6   158.5
  4531.9  160.48  4592.3  161.34  4628.7  159.37  4940.7  155.99 4978.04 151.936
  4994.6  143.35  4996.7  140.79  5005.3  141.37  5029.5  152.01  5048.3  150.08
  5053.7  153.33  5092.6  154.05  5177.7  153.99  5244.7   151.7  5415.4  154.88
  5513.6  156.31  5591.5  155.25  5665.9  157.29  5894.9  161.71  6072.2  164.62
#Mann= 7 ,-1 , 0
  3661.1     .12       0 4978.04     .07       0  5029.5     .12       0
  5092.6      .1       0  5415.4     .05       0  5665.9      .1       0
  5894.9     .12       0
Bank Sta=4978.04,5029.5
XS Rating Curve= 0 ,0
Exp/Cntr=0.3,0.1

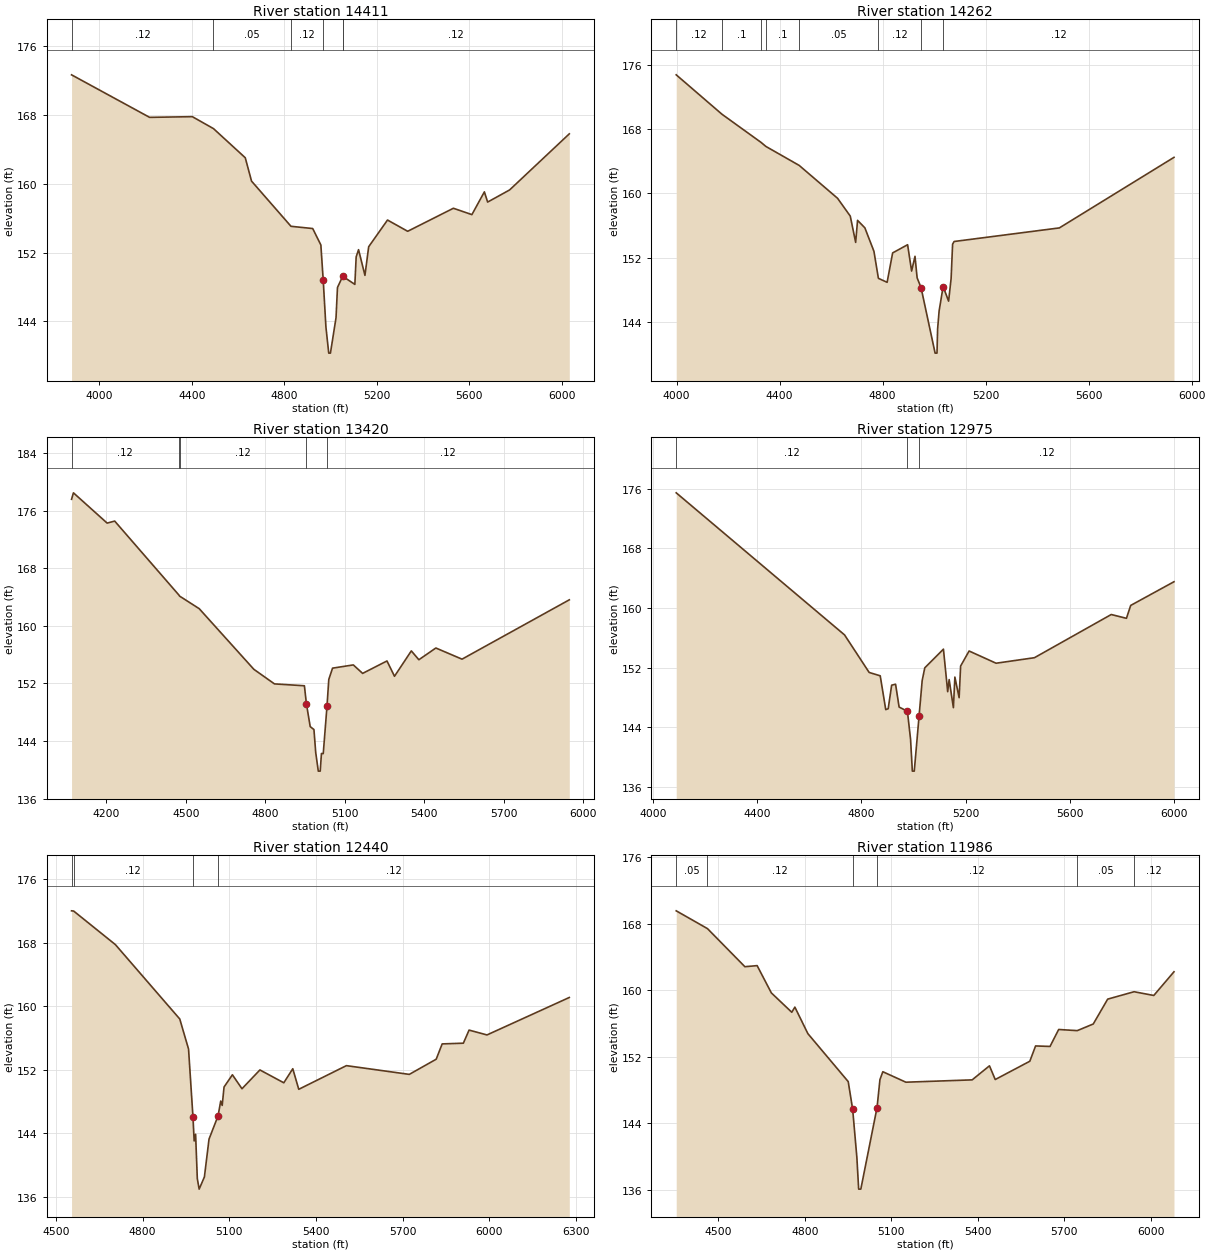
Type RM Length L Ch R = 1 ,14411   ,149,149,149
BEGIN DESCRIPTION:
CRYSTAL CREEK TRIBUTARY NO 1 29.0
END DESCRIPTION:
XS GIS Cut Line= 3
      3860101.28     10101602.06      3859431.98     10100750.46
      3858917.86     10099811.08
#Sta/Elev= 30
  3879.1  172.69  4216.9  167.74  4401.8  167.82  4493.3  166.43  4630.8  163.04
    4658  160.32  4828.7  155.06  4922.7   154.8    4958  152.89 4968.15 148.803
  4979.9  143.34  4992.1   140.3  4999.4   140.3  5023.6  144.42  5029.9  147.94
  5052.7  149.25  5053.1  149.23  5105.1   148.3  5110.8  151.51  5121.1  152.34
  5148.8  149.35  5164.9  152.68  5246.4  155.79  5333.7  154.48  5531.5  157.16
  5611.6  156.42  5665.6  159.07  5679.7  157.88  5774.7  159.29  6033.1  165.82
#Mann= 6 ,-1 , 0
  3879.1     .12       0  4493.3     .05       0  4828.7     .12       0
 4968.15     .07       0  5052.7      .1       0  5053.1     .12       0
Bank Sta=4968.15,5052.7
XS Rating Curve= 0 ,0
Exp/Cntr=0.3,0.1

Type RM Length L Ch R = 1 ,14262   ,842,842,842
BEGIN DESCRIPTION:
CRYSTAL CREEK TRIBUTARY NO 1 28.0
END DESCRIPTION:
XS GIS Cut Line= 3
      3860150.75     10101312.97      3859572.61     10100784.31
      3858978.85     10099799.92
#Sta/Elev= 30
  3998.4  174.75  4175.9  169.85  4327.9  166.34  4346.6  165.84  4475.8  163.48
  4624.9  159.39  4674.3  157.17  4695.2   153.9  4702.6  156.64    4731  155.71
  4766.2  152.79  4783.5  149.43  4817.4  148.93  4838.8  152.59    4897  153.61
  4912.5  150.33  4925.7  152.17  4933.9  149.49  4949.1  148.28  5003.8  140.12
  5011.1  140.12  5013.5  143.12  5019.3  145.36  5034.9   148.4  5056.2  146.59
  5065.9   149.4  5071.7  153.68  5077.6  154.01  5486.3   155.7  5931.4  164.48
#Mann= 8 ,-1 , 0
  3998.4     .12       0  4175.9      .1       0  4327.9     .12       0
  4346.6      .1       0  4475.8     .05       0  4783.5     .12       0
  4949.1     .07       0  5034.9     .12       0
Bank Sta=4949.1,5034.9
XS Rating Curve= 0 ,0
Exp/Cntr=0.3,0.1

Type RM Length L Ch R = 1 ,13420   ,445,445,445
BEGIN DESCRIPTION:
CRYSTAL CREEK TRIBUTARY NO 1 27.0
END DESCRIPTION:
XS GIS Cut Line= 3
      3860367.84     10101111.06      3859754.03     10100405.84
      3859055.21     10099772.13
#Sta/Elev= 30
  4068.6  177.61  4075.7  178.51  4202.9   174.3  4231.4  174.58  4474.3  164.27
  4476.2  164.15  4550.4   162.4  4756.5  153.97  4834.3  151.94  4947.3  151.68
  4954.9  149.17  4969.2     146  4983.3  145.59    4990   142.4  4999.7  139.81
    5007  139.81  5011.6  142.26  5018.4  142.25  5032.5  148.81  5039.3  152.55
  5053.5  154.13  5131.9  154.58    5167   153.4  5258.9  155.13  5287.3     153
  5350.8  156.53  5379.2   155.3  5443.4  156.93  5542.1  155.38  5946.9  163.63
#Mann= 5 ,-1 , 0
  4068.6     .12       0  4474.3      .1       0  4476.2     .12       0
  4954.9     .07       0  5032.5     .12       0
Bank Sta=4954.9,5032.5
XS Rating Curve= 0 ,0
Exp/Cntr=0.3,0.1

Type RM Length L Ch R = 1 ,12975   ,535,535,535
BEGIN DESCRIPTION:
CRYSTAL CREEK TRIBUTARY NO 1 26.0
END DESCRIPTION:
XS GIS Cut Line= 3
      3860526.62     10100911.51      3860083.89     10100204.02
      3859135.57     10099698.39
#Sta/Elev= 30
  4089.4  175.47  4735.1  156.39  4829.5  151.35  4871.9   150.9  4893.1  146.36
  4902.5  146.48  4915.7  149.64  4930.8  149.77  4944.4   146.7  4976.2  146.14
  4988.3  142.37  4995.1   138.1  5002.5   138.1  5020.9  145.48  5032.8  150.25
  5042.8  151.97  5114.4  154.48  5130.7  148.77  5136.3  150.39  5152.6  146.62
  5158.3  150.73  5174.6  147.96  5180.3  152.21  5212.8  154.23  5316.2  152.59
  5463.5  153.33  5758.1  159.13  5816.4  158.62  5832.7  160.35  5998.7  163.53
#Mann= 3 , 0 , 0
  4089.4     .12       0  4976.2     .07       0  5020.9     .12       0
Bank Sta=4976.2,5020.9
XS Rating Curve= 0 ,0
Exp/Cntr=0.3,0.1

Type RM Length L Ch R = 1 ,12440   ,454,454,454
BEGIN DESCRIPTION:
CRYSTAL CREEK TRIBUTARY NO 1 25.0
END DESCRIPTION:
XS GIS Cut Line= 3
      3860917.83     10100061.07      3860463.67     10099991.34
       3859242.4     10099672.47
#Sta/Elev= 30
  4554.4  172.02  4561.8  171.99  4706.1  167.76  4928.7  158.39  4959.1   154.6
 4974.48 145.977  4978.5  143.02  4983.5  143.86  4989.4  138.28  4995.8  136.95
  5013.9  138.48  5029.9  143.25  5061.2  146.18  5070.4  148.05  5075.5   147.5
  5081.9  149.82  5110.8  151.36  5143.9   149.6  5205.9  151.97  5288.6  150.35
  5319.6  152.12  5340.3  149.53  5505.1  152.51  5722.7  151.41  5815.7  153.32
  5836.4  155.25  5909.7  155.34  5929.4  156.99  5991.4  156.38  6276.1   161.1
#Mann= 4 ,-1 , 0
  4554.4     .05       0  4561.8     .12       0 4974.48     .07       0
  5061.2     .12       0
Bank Sta=4974.48,5061.2
XS Rating Curve= 0 ,0
Exp/Cntr=0.3,0.1

Type RM Length L Ch R = 1 ,11986   ,486,486,486
BEGIN DESCRIPTION:
CRYSTAL CREEK TRIBUTARY NO 1 24.0
END DESCRIPTION:
XS GIS Cut Line= 3
       3860912.9     10099932.76      3860632.94      10099631.1
      3859317.85     10099611.07
#Sta/Elev= 30
  4354.3  169.53  4462.7  167.39  4592.5  162.81    4635  162.94  4684.3  159.66
  4755.2  157.33  4765.9  157.95    4811  154.76    4951  148.99 4966.38 145.664
    4981  139.87  4987.2  136.06  4994.7  136.06    5051  145.87    5061  149.22
    5071  150.18    5151  148.92    5381   149.2    5441  150.89    5461  149.24
    5581  151.44    5601  153.28  5651.1  153.22  5681.1  155.26  5745.5  155.12
  5801.1  155.92  5851.1  158.91  5942.7   159.8  6011.1  159.35  6081.1   162.2
#Mann= 6 ,-1 , 0
  4354.3     .05       0  4462.7     .12       0 4966.38     .07       0
    5051     .12       0  5745.5     .05       0  5942.7     .12       0
Bank Sta=4966.38,5051
XS Rating Curve= 0 ,0
Exp/Cntr=0.3,0.1

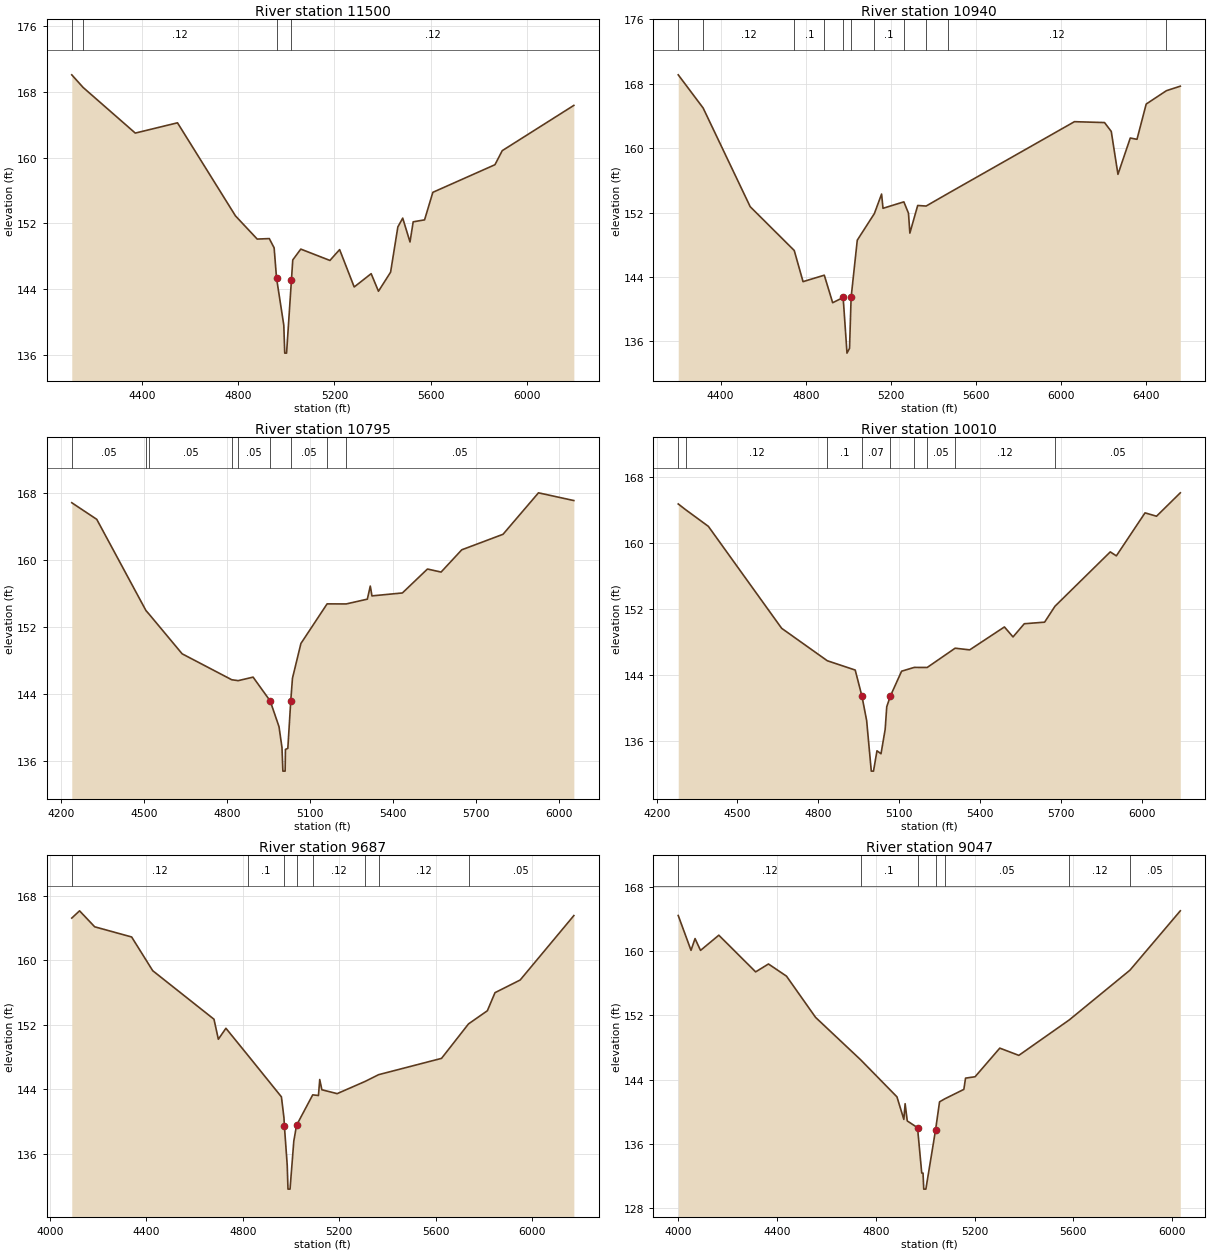
Type RM Length L Ch R = 1 ,11500   ,560,560,560
BEGIN DESCRIPTION:
CRYSTAL CREEK TRIBUTARY NO 1 23.0
END DESCRIPTION:
XS GIS Cut Line= 3
      3861225.44     10099255.67      3860337.59     10099189.57
      3859152.86     10099045.16
#Sta/Elev= 30
  4109.7  170.09  4156.9  168.55  4373.3     163  4548.5  164.25  4789.2  152.92
  4879.4   150.1  4929.5  150.16  4949.6  149.03  4959.6  145.35  4989.7  139.62
  4993.6  136.22  5001.2  136.22 5021.54 145.159  5026.9  147.56  5060.2  148.88
  5181.1   147.5  5221.4  148.82  5281.9  144.27  5352.3  145.89  5382.6  143.75
  5432.9  146.07  5463.1  151.58  5483.3  152.65  5513.5  149.75  5526.7   152.2
    5574  152.44  5608.3  155.79  5866.1  159.15  5896.3  160.86  6193.5  166.37
#Mann= 4 ,-1 , 0
  4109.7     .05       0  4156.9     .12       0  4959.6     .07       0
 5021.54     .12       0
Bank Sta=4959.6,5021.54
XS Rating Curve= 0 ,0
Exp/Cntr=0.3,0.1

Type RM Length L Ch R = 1 ,10940   ,145,145,145
BEGIN DESCRIPTION:
CRYSTAL CREEK TRIBUTARY NO 1 22.0
END DESCRIPTION:
XS GIS Cut Line= 3
      3860982.36     10099006.11      3860220.61     10098713.13
      3858755.79     10098222.69
#Sta/Elev= 30
  4200.6  169.11  4317.7  164.99    4539  152.73  4746.1  147.29  4787.5  143.42
  4887.4  144.22  4926.8   140.8  4976.1  141.45  4994.2  134.54  5006.1  135.13
 5013.54 141.455  5042.5  148.57    5123  151.88  5156.8   154.3  5163.5  152.53
  5261.5  153.33  5283.3  151.92  5289.8  149.45  5326.6  152.88  5366.2  152.81
  5468.9  154.37  6063.7  163.29  6205.2  163.18  6236.8  162.08  6268.3  156.75
  6326.2  161.26  6357.8   161.1  6401.1  165.48  6496.2  167.14  6561.5   167.7
#Mann= 11 ,-1 , 0
  4200.6     .05       0  4317.7     .12       0  4746.1      .1       0
  4887.4     .12       0  4976.1     .07       0 5013.54     .12       0
    5123      .1       0  5261.5     .12       0  5366.2      .1       0
  5468.9     .12       0  6496.2     .05       0
Bank Sta=4976.1,5013.54
XS Rating Curve= 0 ,0
Exp/Cntr=0.3,0.1

Type RM Length L Ch R = 1 ,10795   ,785,785,785
BEGIN DESCRIPTION:
CRYSTAL CREEK TRIBUTARY NO 1 21.0
END DESCRIPTION:
XS GIS Cut Line= 3
      3861023.52     10098858.51      3860172.87     10098550.37
      3859317.84     10098229.19
#Sta/Elev= 30
  4237.3   166.8  4327.8  164.82    4506  153.95  4517.4  153.52  4636.9   148.8
  4816.5  145.71    4840   145.6  4893.9  146.02  4955.9  143.18  4987.8  140.11
  4998.5  137.64  5001.8  134.82  5009.9  134.82  5011.1  137.41  5019.7  137.53
  5030.4  143.23  5036.5  145.89  5067.1  150.03  5161.9  154.75  5230.9  154.74
  5307.6  155.31  5318.3  156.87  5324.3   155.7  5434.6  156.05  5525.3   158.9
  5574.7  158.54  5649.5  161.19    5799  163.04  5927.3  167.98  6055.4  167.06
#Mann= 9 ,-1 , 0
  4237.3     .05       0    4506     .12       0  4517.4     .05       0
  4816.5      .1       0    4840     .05       0  4955.9     .07       0
  5030.4     .05       0  5161.9     .12       0  5230.9     .05       0
Bank Sta=4955.9,5030.4
XS Rating Curve= 0 ,0
Exp/Cntr=0.3,0.1

Type RM Length L Ch R = 1 ,10010   ,323,323,323
BEGIN DESCRIPTION:
CRYSTAL CREEK TRIBUTARY NO 1 20.0
END DESCRIPTION:
XS GIS Cut Line= 3
      3861110.37     10098821.64      3860912.89     10098268.25
      3859714.99     10097827.72
#Sta/Elev= 30
  4280.1  164.72  4307.7  164.02    4392     162  4663.9  149.63  4833.4  145.69
  4937.1  144.56  4962.3  141.36  4979.6  138.42  4996.8  132.29    5005  132.29
  5017.9  134.76  5032.9   134.4  5048.3  137.36  5054.2  140.11 5067.89 141.418
  5109.3  144.42  5156.3  144.88  5204.3  144.87    5308  147.21  5362.2  147.01
    5491  149.79    5523  148.58  5564.8  150.18  5640.2  150.37  5678.6   152.3
    5884   158.9  5906.6  158.42  6013.1  163.64  6055.7  163.23    6144  166.07
#Mann= 9 ,-1 , 0
  4280.1     .05       0  4307.7     .12       0  4833.4      .1       0
  4962.3     .07       0 5067.89      .1       0  5156.3     .12       0
  5204.3     .05       0    5308     .12       0  5678.6     .05       0
Bank Sta=4962.3,5067.89
XS Rating Curve= 0 ,0
Exp/Cntr=0.3,0.1

Type RM Length L Ch R = 1 ,9687    ,640,640,640
BEGIN DESCRIPTION:
CRYSTAL CREEK TRIBUTARY NO 1 19.0
END DESCRIPTION:
XS GIS Cut Line= 3
       3861828.7     10098240.05      3860869.48     10097942.73
      3859848.14     10097595.78
#Sta/Elev= 30
    4090  165.23  4122.3  166.13  4185.1  164.15  4338.4  162.89  4425.9  158.71
    4680   152.7  4698.1  150.22  4729.5  151.58  4822.1  148.18  4959.8  143.08
  4970.3  140.48 4972.07 139.469  4983.8  134.63    4987  131.65  4995.5  131.65
  5011.2  137.62  5022.7  139.57  5089.6  143.33  5113.4  143.25  5118.7  145.23
  5127.6  143.96    5191  143.48  5305.9  144.98    5363  145.83    5624  147.85
  5735.9  152.12  5814.1  153.75  5845.8  155.99  5950.3  157.56  6172.9  165.54
#Mann= 8 ,-1 , 0
    4090     .12       0  4822.1      .1       0  4970.3     .07       0
  5022.7      .1       0  5089.6     .12       0  5305.9     .05       0
    5363     .12       0  5735.9     .05       0
Bank Sta=4972.07,5022.7
XS Rating Curve= 0 ,0
Exp/Cntr=0.3,0.1

Type RM Length L Ch R = 1 ,9047    ,547,547,547
BEGIN DESCRIPTION:
CRYSTAL CREEK TRIBUTARY NO 1 18.0
END DESCRIPTION:
XS GIS Cut Line= 4
      3861765.77     10098012.22      3861636.83      10097748.3
      3860956.29     10097552.11      3859966.72     10097261.31
#Sta/Elev= 30
  3999.7  164.42  4051.5  160.09  4067.8  161.55    4090  160.08  4164.1  161.97
  4313.2  157.41  4365.2  158.39  4438.1  156.88    4556  151.75  4738.8  146.47
  4885.6  141.87  4913.4  139.07  4918.6  141.02  4927.2  138.88  4968.8  138.04
  4985.9   132.4  4991.1  132.39    4994   130.4  5002.6   130.4  5041.8  137.74
    5058  141.25  5078.9  141.62  5156.4   142.8  5163.3   144.2  5201.9  144.37
    5302  147.93  5379.1  147.03  5583.5  151.44  5829.1  157.62  6033.1     165
#Mann= 7 ,-1 , 0
  3999.7     .12       0  4738.8      .1       0  4968.8     .07       0
  5041.8      .1       0  5078.9     .05       0  5583.5     .12       0
  5829.1     .05       0
Bank Sta=4968.8,5041.8
XS Rating Curve= 0 ,0
Exp/Cntr=0.3,0.1