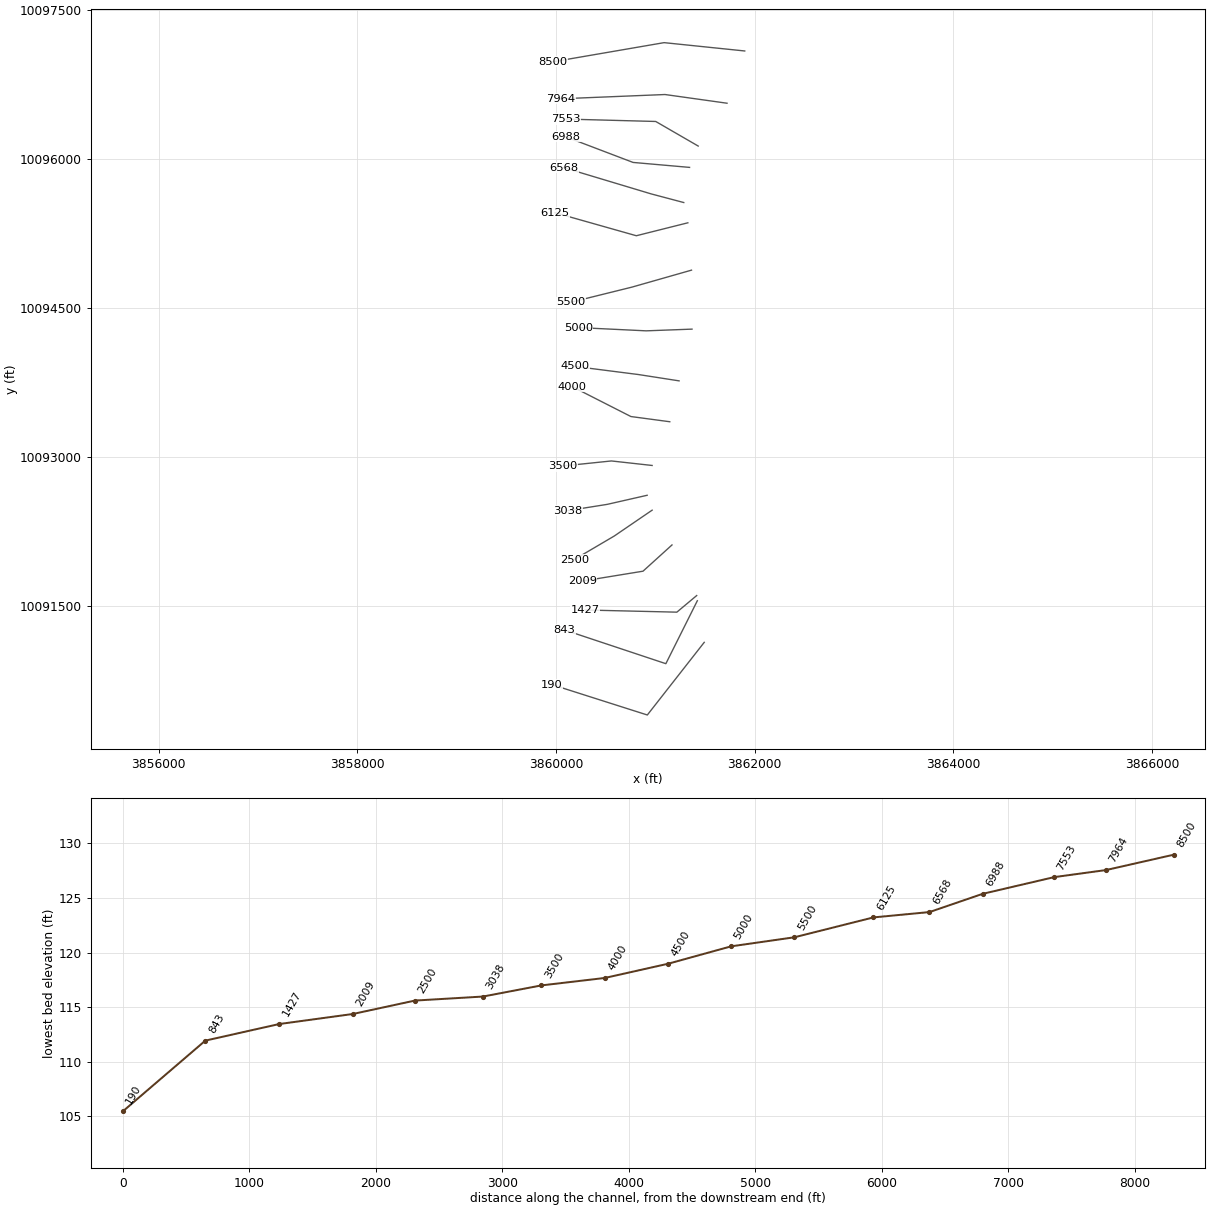
HEC-RAS study CRYSTAL CREEK TRIBUTARY NO 1.prj: CRYSTAL CREEK TRIBUTARY NO 1 Base Level Engineering

--- CRYSTAL CREEK TRIBUTARY NO 1.g10 (geometry) --- (continued)

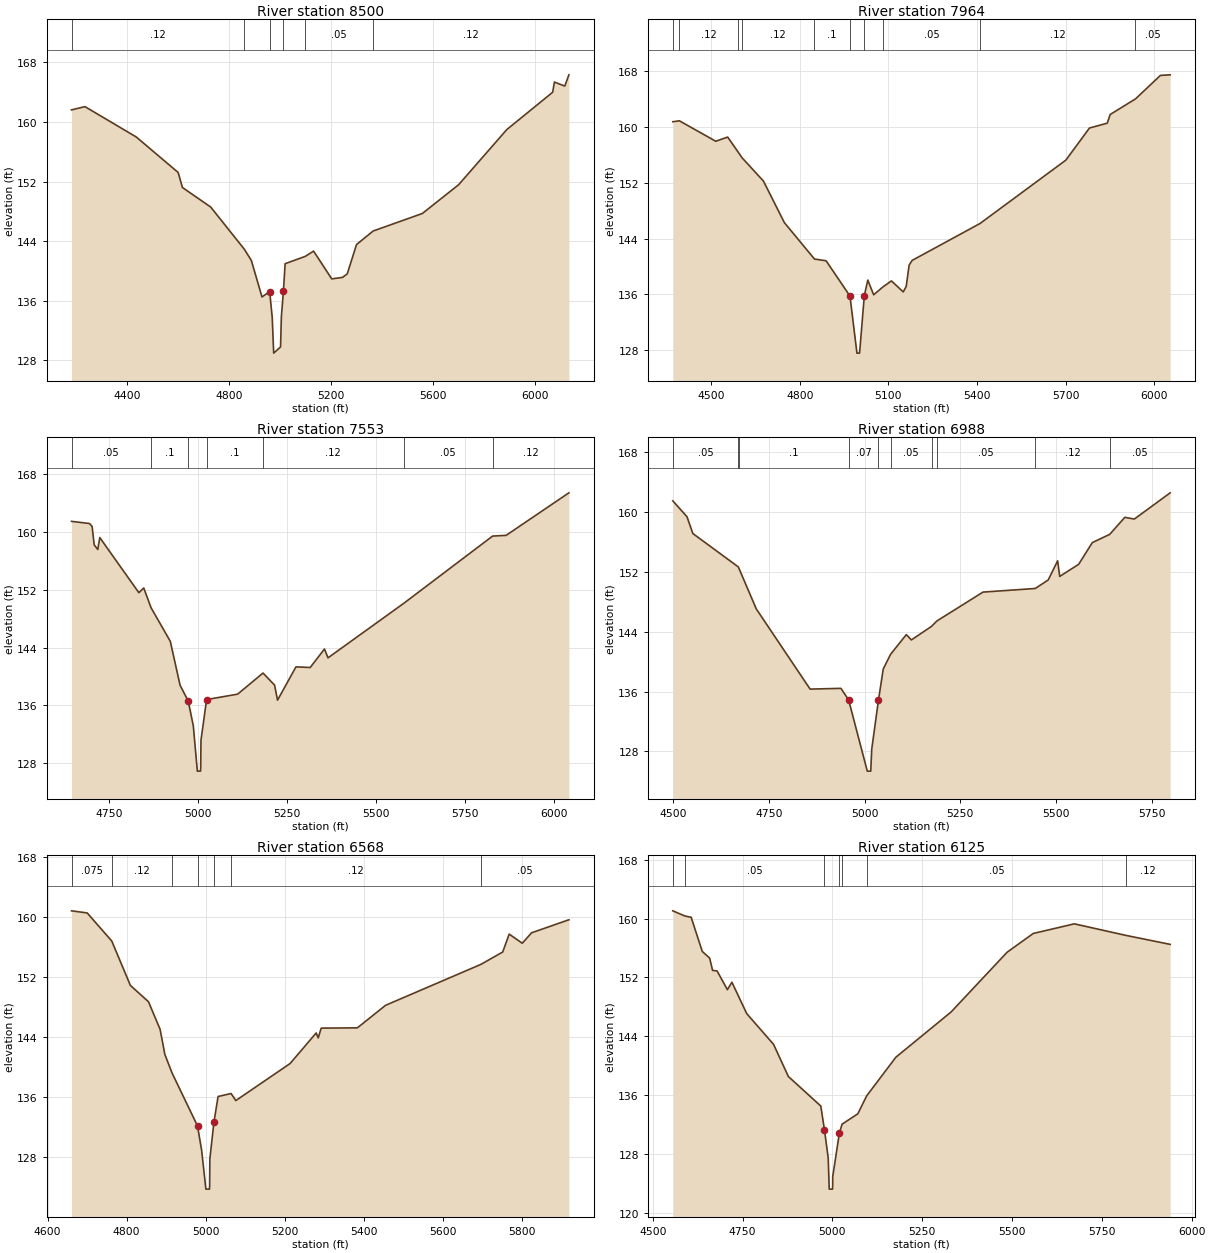
Type RM Length L Ch R = 1 ,8500    ,536,536,536
BEGIN DESCRIPTION:
CRYSTAL CREEK TRIBUTARY NO 1 17.0
END DESCRIPTION:
XS GIS Cut Line= 3
      3861900.26     10097083.36      3861088.28     10097167.18
       3859971.9       10096975.
#Sta/Elev= 30
  4183.7  161.63  4236.4  162.07  4437.5  157.99  4601.5  153.23  4618.4  151.21
    4729  148.59  4860.7  142.93  4888.3  141.42  4930.1  136.51  4960.2  137.24
  4970.3  133.71  4975.9  128.97  5002.8   129.8    5006  133.84  5014.2 137.351
  5020.7  140.98  5099.7  141.96  5132.3  142.67  5203.4  138.94  5245.7  139.14
  5264.3  139.62  5300.5  143.55  5365.8  145.37  5558.5  147.72  5700.6  151.58
  5889.5  158.99  6069.2     164    6076  165.37  6116.6  164.83  6132.8  166.34
#Mann= 6 ,-1 , 0
  4183.7     .12       0  4860.7      .1       0  4960.2     .07       0
  5014.2      .1       0  5099.7     .05       0  5365.8     .12       0
Bank Sta=4960.2,5014.2
XS Rating Curve= 0 ,0
Exp/Cntr=0.3,0.1

Type RM Length L Ch R = 1 ,7964    ,411,411,411
BEGIN DESCRIPTION:
CRYSTAL CREEK TRIBUTARY NO 1 16.0
END DESCRIPTION:
XS GIS Cut Line= 3
      3861721.83     10096557.44      3861097.35     10096644.99
      3860044.91     10096601.96
#Sta/Elev= 30
  4370.3  160.76  4392.7  160.89  4515.7  157.96  4556.1  158.56  4591.6   156.4
  4604.7  155.59  4677.2  152.24  4747.9  146.29  4849.9  141.06  4889.3  140.81
  4970.1  135.75  4993.7  127.56  5002.6  127.56 5018.58 135.774  5030.4  138.04
  5050.4  135.93  5082.6  137.09  5110.5  137.92  5150.5  136.34  5160.5  137.14
  5170.5   140.2  5180.5  140.86  5410.4  146.16    5701  155.25    5781  159.86
  5841.1  160.55  5851.1   161.8  5936.6  164.03  6021.2  167.41  6054.2  167.49
#Mann= 10 ,-1 , 0
  4370.3     .05       0  4392.7     .12       0  4591.6     .05       0
  4604.7     .12       0  4849.9      .1       0  4970.1     .07       0
 5018.58      .1       0  5082.6     .05       0  5410.4     .12       0
  5936.6     .05       0
Bank Sta=4970.1,5018.58
XS Rating Curve= 0 ,0
Exp/Cntr=0.3,0.1

Type RM Length L Ch R = 1 ,7553    ,565,565,565
BEGIN DESCRIPTION:
CRYSTAL CREEK TRIBUTARY NO 1 15.0
END DESCRIPTION:
XS GIS Cut Line= 3
      3861431.54     10096126.33      3861004.03     10096373.72
      3860101.68     10096397.88
#Sta/Elev= 30
  4645.6   161.5  4696.1   161.2  4703.4  160.79  4709.2  158.25  4719.2   157.6
    4725  159.25  4834.7  151.62  4848.4  152.27  4868.8  149.55    4923  144.88
  4950.3  138.82  4973.4   136.6  4987.6  133.16  4998.9  126.91  5007.8  126.91
  5008.3  127.41  5009.1   131.2  5024.9  136.82    5112  137.57  5183.2  140.49
  5215.7  138.83  5224.1  136.74  5275.8  141.35  5315.8  141.26  5355.8  143.82
  5365.8   142.6  5578.3  150.14    5828  159.46    5866  159.56  6042.2  165.45
#Mann= 7 ,-1 , 0
  4645.6     .05       0  4868.8      .1       0  4973.4     .07       0
  5024.9      .1       0  5183.2     .12       0  5578.3     .05       0
    5828     .12       0
Bank Sta=4973.4,5024.9
XS Rating Curve= 0 ,0
Exp/Cntr=0.3,0.1

Type RM Length L Ch R = 1 ,6988    ,420,420,420
BEGIN DESCRIPTION:
CRYSTAL CREEK TRIBUTARY NO 1 14.0
END DESCRIPTION:
XS GIS Cut Line= 3
      3861344.73     10095911.48      3860776.17     10095961.39
      3860096.81     10096219.83
#Sta/Elev= 30
  4499.8  161.43  4536.8  159.31  4552.1  157.07  4670.4  152.63  4671.5  152.53
  4717.5  147.02    4858  136.32  4938.4  136.42  4958.4  134.89  5007.2  125.38
  5016.2  125.38  5018.7  128.28 5036.29  134.83  5048.8     139  5067.9  140.96
    5109  143.59  5122.2  142.88  5174.8  144.69  5189.1  145.42  5309.1  149.26
  5445.3  149.74  5479.1  150.87  5503.8  153.43  5509.2  151.35  5558.7  152.97
  5594.2  155.86  5639.6  156.96  5679.1  159.23  5703.9     159  5797.4   162.5
#Mann= 10 ,-1 , 0
  4499.8     .05       0  4670.4     .12       0  4671.5      .1       0
  4958.4     .07       0 5036.29      .1       0  5067.9     .05       0
  5174.8     .12       0  5189.1     .05       0  5445.3     .12       0
  5639.6     .05       0
Bank Sta=4958.4,5036.29
XS Rating Curve= 0 ,0
Exp/Cntr=0.3,0.1

Type RM Length L Ch R = 1 ,6568    ,443,443,443
BEGIN DESCRIPTION:
CRYSTAL CREEK TRIBUTARY NO 1 13.0
END DESCRIPTION:
XS GIS Cut Line= 3
      3861286.16     10095557.74      3860958.46     10095644.55
      3860077.39     10095909.31
#Sta/Elev= 30
  4660.6  160.79  4700.2  160.51  4762.4  156.77  4809.6  150.85  4855.4  148.68
  4884.8     145  4896.8  141.67    4915  139.19  4979.5  132.13  4989.9   128.9
  5000.7  123.71  5009.7  123.71  5010.2  124.21  5010.7  127.73  5021.1  132.65
  5031.6  136.05  5064.4  136.45  5076.5  135.51  5213.8  140.44  5279.9  144.52
  5285.1  143.86  5292.6  145.16  5384.2   145.2  5455.5   148.2  5696.7  153.65
    5752   155.3  5768.5  157.69  5801.6  156.47  5825.1  157.86  5919.6   159.6
#Mann= 7 ,-1 , 0
  4660.6    .075       0  4762.4     .12       0    4915      .1       0
  4979.5     .07       0  5021.1      .1       0  5064.4     .12       0
  5696.7     .05       0
Bank Sta=4979.5,5021.1
XS Rating Curve= 0 ,0
Exp/Cntr=0.3,0.1

Type RM Length L Ch R = 1 ,6125    ,625,625,625
BEGIN DESCRIPTION:
CRYSTAL CREEK TRIBUTARY NO 1 12.0
END DESCRIPTION:
XS GIS Cut Line= 3
      3861327.39     10095353.76      3860808.72     10095223.55
      3859991.07     10095454.84
#Sta/Elev= 30
  4555.7  161.06  4588.6  160.37  4606.8  160.18  4637.7  155.54  4658.3  154.63
  4666.4  152.96  4678.9  152.89  4707.6  150.34  4720.2  151.35  4761.4  147.09
  4836.2   142.9  4877.4  138.53  4967.6  134.52  4977.9  131.27  4988.3  127.43
  4991.1  123.22  5000.2  123.22  5000.7  123.72  5000.8  124.91  5019.2  130.79
  5026.8  132.05  5070.7  133.46  5095.2  135.89  5176.5  141.15  5330.4  147.31
  5486.3  155.43    5559  157.98  5673.3  159.29  5817.9  157.71  5940.2   156.5
#Mann= 7 ,-1 , 0
  4555.7      .1       0  4588.6     .05       0  4977.9     .07       0
  5019.2     .05       0  5026.8      .1       0  5095.2     .05       0
  5817.9     .12       0
Bank Sta=4977.9,5019.2
XS Rating Curve= 0 ,0
Exp/Cntr=0.3,0.1

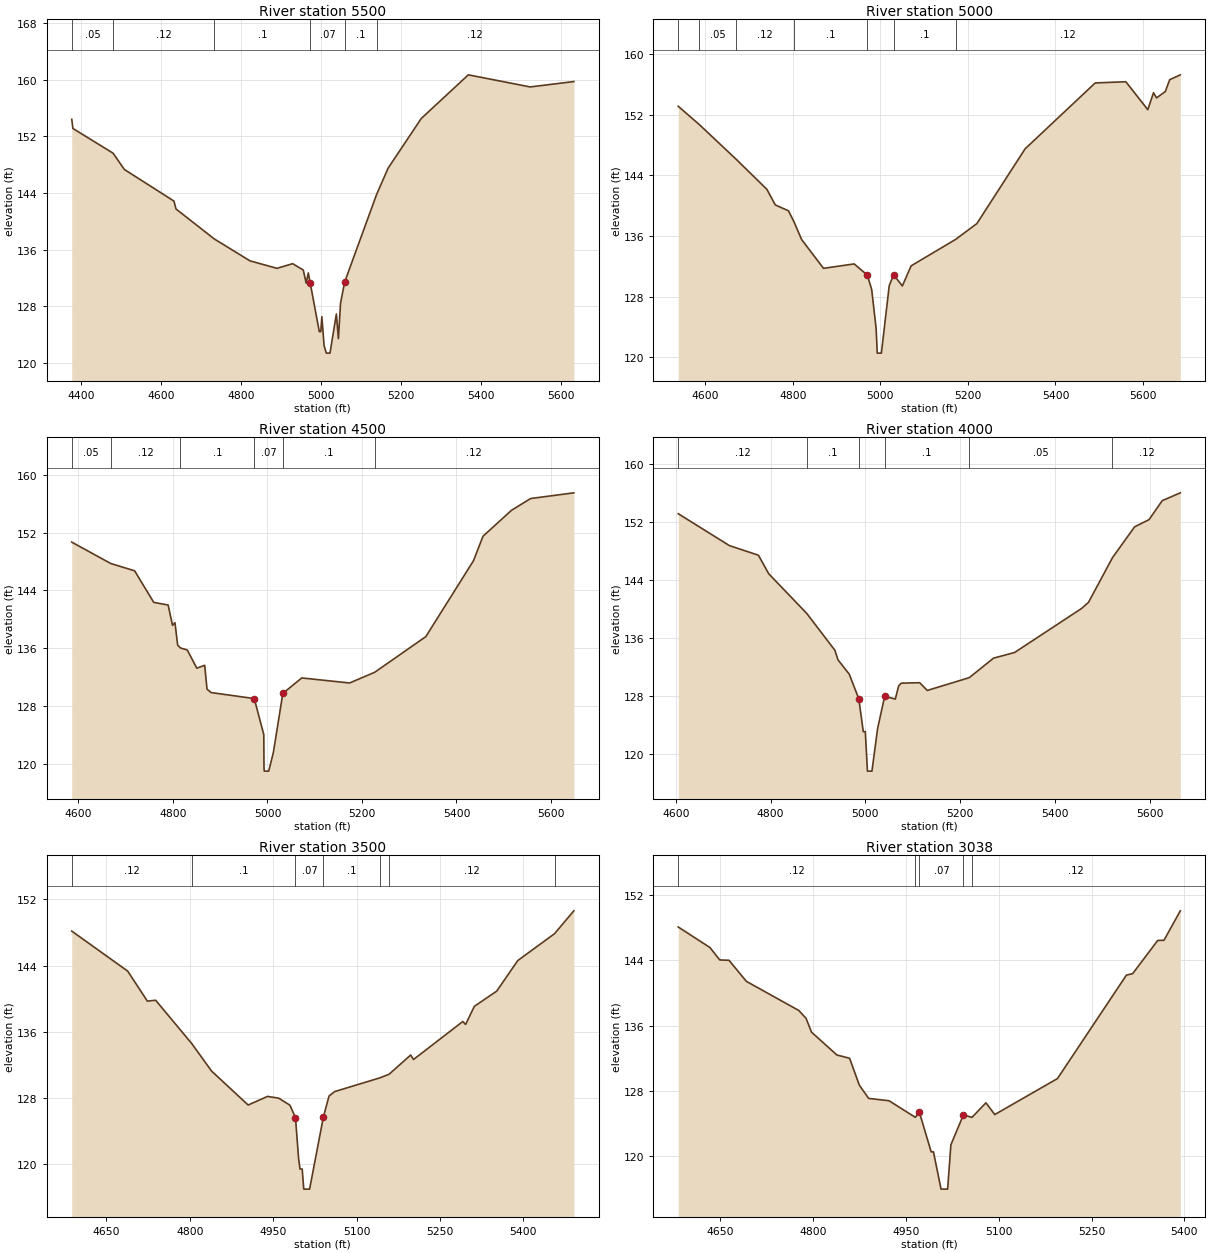
Type RM Length L Ch R = 1 ,5500    ,500,500,500
BEGIN DESCRIPTION:
CRYSTAL CREEK TRIBUTARY NO 1 11.0
END DESCRIPTION:
XS GIS Cut Line= 3
      3861364.26     10094877.21      3860765.69     10094706.63
      3860151.85     10094554.57
#Sta/Elev= 30
  4377.6  154.41  4380.4  153.12  4480.8  149.63    4509  147.33  4632.9  142.87
  4638.1  141.75  4733.8  137.52  4822.9  134.43  4890.6  133.37  4929.6  134.03
  4956.2  133.13  4963.5  131.28  4968.7  132.73  4973.7  131.26  4996.3  124.43
    5000  124.43  5002.6  126.55  5008.1  122.49  5013.7   121.4    5023   121.4
  5038.9  126.93    5044  123.44  5049.3  128.45  5059.6  131.43  5139.3  143.78
  5168.2  147.51    5251  154.52  5368.7  160.69  5523.2  158.98  5632.4  159.74
#Mann= 6 ,-1 , 0
  4377.6     .05       0  4480.8     .12       0  4733.8      .1       0
  4973.7     .07       0  5059.6      .1       0  5139.3     .12       0
Bank Sta=4973.7,5059.6
XS Rating Curve= 0 ,0
Exp/Cntr=0.3,0.1

Type RM Length L Ch R = 1 ,5000    ,500,500,500
BEGIN DESCRIPTION:
CRYSTAL CREEK TRIBUTARY NO 1 10.0
END DESCRIPTION:
XS GIS Cut Line= 3
      3861369.52     10094283.47      3860908.04     10094266.24
      3860223.63      10094299.1
#Sta/Elev= 30
  4538.2  153.09  4586.1  150.69  4670.5  146.11  4740.8  142.14    4760  140.09
    4790  139.32  4802.7  137.87  4820.1  135.53  4870.1  131.74  4940.1  132.32
  4970.2  130.85  4980.2  128.94  4990.2  123.86  4992.9  120.57  5002.3  120.57
  5020.2  129.45  5030.2  130.89  5050.2  129.42  5070.3  132.07  5171.9  135.55
  5220.4  137.63  5330.6  147.48  5490.8  156.16  5560.8  156.32  5610.9  152.64
    5624  154.87  5630.9  154.19  5650.9  155.03    5661  156.59  5685.2  157.23
#Mann= 7 ,-1 , 0
  4538.2     .12       0  4586.1     .05       0  4670.5     .12       0
  4802.7      .1       0  4970.2     .07       0  5030.2      .1       0
  5171.9     .12       0
Bank Sta=4970.2,5030.2
XS Rating Curve= 0 ,0
Exp/Cntr=0.3,0.1

Type RM Length L Ch R = 1 ,4500    ,500,500,500
BEGIN DESCRIPTION:
CRYSTAL CREEK TRIBUTARY NO 1 9.0
END DESCRIPTION:
XS GIS Cut Line= 3
      3861239.31     10093762.63      3860830.23     10093826.29
      3860187.17     10093908.47
#Sta/Elev= 30
    4586  150.69  4668.5  147.73    4719  146.72  4759.5  142.34  4789.9  141.98
  4799.2  139.16  4804.3  139.53  4810.1  136.42    4816  136.03  4830.4  135.75
  4850.6  133.23  4867.2  133.63  4872.2  130.32    4881  129.85  4972.1  129.02
  4992.3  124.03  4992.7  119.47  4993.2  118.97  5002.7  118.97  5012.5  121.54
  5032.6  129.74  5072.6  131.88  5173.8  131.18  5226.9  132.66  5335.1   137.6
  5435.9  148.11  5456.1  151.51  5516.6  155.11  5556.9  156.73  5648.3  157.52
#Mann= 6 ,-1 , 0
    4586     .05       0  4668.5     .12       0    4816      .1       0
  4972.1     .07       0  5032.6      .1       0  5226.9     .12       0
Bank Sta=4972.1,5032.6
XS Rating Curve= 0 ,0
Exp/Cntr=0.3,0.1

Type RM Length L Ch R = 1 ,4000    ,500,500,500
BEGIN DESCRIPTION:
CRYSTAL CREEK TRIBUTARY NO 1 8.0
END DESCRIPTION:
XS GIS Cut Line= 3
      3861145.51     10093351.18       3860754.3     10093403.53
      3860161.97     10093704.94
#Sta/Elev= 30
  4605.3  153.19  4713.2  148.79  4774.5  147.46  4796.3   144.9  4876.6  139.42
  4935.9  134.34  4942.3  133.03  4966.1  131.05  4986.3  127.65  4995.7  123.12
    5000  123.12  5004.5  117.67    5014  117.67  5025.9  123.53  5040.9  128.01
  5063.3  127.61  5070.4  129.44    5076  129.81  5114.8  129.87  5130.7   128.8
  5219.4  130.57  5270.6  133.26    5315  134.04    5456   140.1  5470.8  140.95
  5521.5  147.12  5568.2  151.38  5598.6  152.37  5626.5  154.99  5664.6  156.07
#Mann= 6 ,-1 , 0
  4605.3     .12       0  4876.6      .1       0  4986.3     .07       0
  5040.9      .1       0  5219.4     .05       0  5521.5     .12       0
Bank Sta=4986.3,5040.9
XS Rating Curve= 0 ,0
Exp/Cntr=0.3,0.1

Type RM Length L Ch R = 1 ,3500    ,462,462,462
BEGIN DESCRIPTION:
CRYSTAL CREEK TRIBUTARY NO 1 7.0
END DESCRIPTION:
XS GIS Cut Line= 3
      3860967.83     10092911.07      3860557.94      10092956.5
      3860069.85     10092905.96
#Sta/Elev= 30
  4587.6  148.16  4688.2  143.33  4723.6   139.7  4738.5  139.81  4803.6  134.56
  4839.1  131.25  4904.9  127.15  4939.7  128.19  4959.8  127.98    4980  127.13
    4990  125.63  4995.6   120.7  4998.1  119.42  5002.1  119.42  5004.9  116.99
  5015.4  116.99  5040.3  125.74  5050.4  128.24  5060.4  128.77  5141.7  130.43
  5158.4  130.87  5197.2  133.19  5202.3  132.65    5291  137.24    5296  136.88
  5311.7  139.07    5352  140.91  5389.8   144.6    5456  147.85  5490.7  150.61
#Mann= 7 ,-1 , 0
  4587.6     .12       0  4803.6      .1       0    4990     .07       0
  5040.3      .1       0  5141.7     .05       0  5158.4     .12       0
    5456     .05       0
Bank Sta=4990,5040.3
XS Rating Curve= 0 ,0
Exp/Cntr=0.3,0.1

Type RM Length L Ch R = 1 ,3038    ,538,538,538
BEGIN DESCRIPTION:
CRYSTAL CREEK TRIBUTARY NO 1 6.0
END DESCRIPTION:
XS GIS Cut Line= 3
      3860917.84     10092611.07      3860515.75     10092519.55
      3860121.79     10092456.78
#Sta/Elev= 30
  4582.2   148.1  4633.5  145.58  4649.3  144.06  4664.2  144.02  4692.4  141.43
    4777  137.87  4788.7  136.91  4797.6  135.21  4838.6  132.41  4859.1  132.01
  4874.8  128.72  4889.9  127.09  4922.9   126.8  4965.3  124.77  4971.9  125.39
  4990.9  120.54  4994.6  120.54  5006.9  115.97  5017.5  115.97  5022.8  121.41
  5043.1  125.08  5056.8  124.76  5079.4  126.55  5093.7  125.11    5195  129.52
  5306.4   142.2  5316.5  142.38    5357  146.45  5367.1  146.47  5393.5  150.08
#Mann= 5 ,-1 , 0
  4582.2     .12       0  4965.3      .1       0  4971.9     .07       0
  5043.1      .1       0  5056.8     .12       0
Bank Sta=4971.9,5043.1
XS Rating Curve= 0 ,0
Exp/Cntr=0.3,0.1

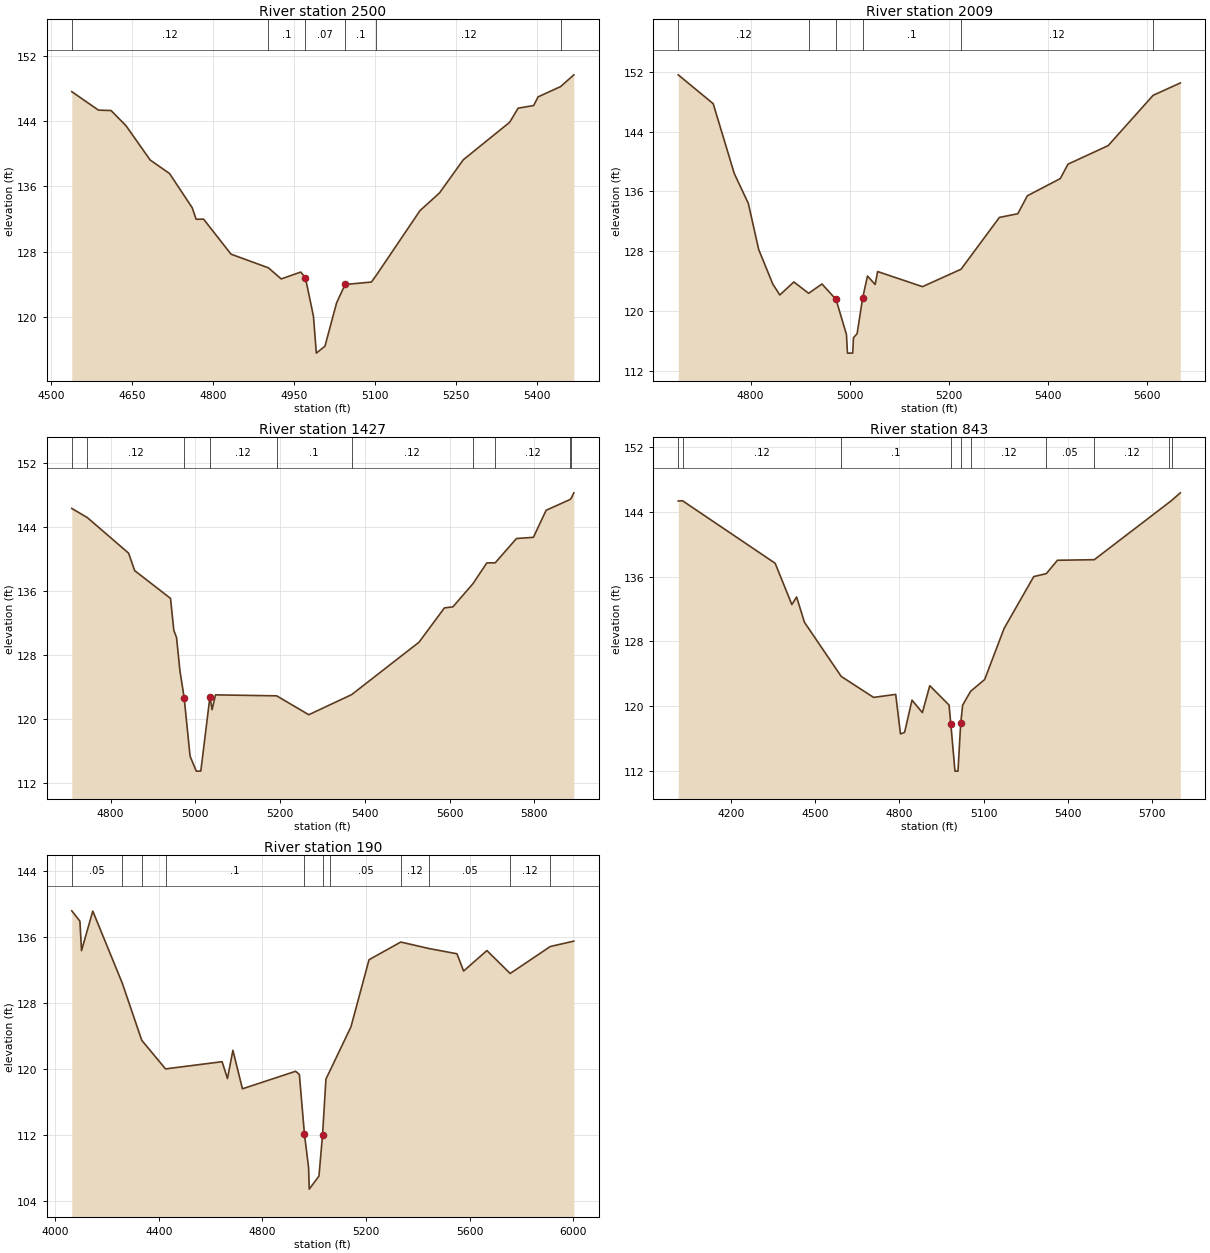
Type RM Length L Ch R = 1 ,2500    ,491,491,491
BEGIN DESCRIPTION:
CRYSTAL CREEK TRIBUTARY NO 1 5.0
END DESCRIPTION:
XS GIS Cut Line= 3
      3860967.88     10092461.09      3860586.67     10092200.96
      3860183.69     10091963.98
#Sta/Elev= 30
  4538.5   147.6  4587.9  145.34  4611.2  145.29  4638.8  143.44  4683.5  139.24
  4719.4  137.58  4761.4  133.39  4768.6  131.98  4782.4     132  4833.2  127.71
  4902.4  126.04    4926  124.68  4962.3  125.52  4970.8  124.83  4985.7  120.12
    4991   115.6    5007  116.45  5028.5  121.75  5044.2     124  5092.9   124.3
  5101.9  125.12  5182.8  133.04    5219  135.21  5262.9  139.26  5348.7  143.85
  5364.4  145.58  5393.1   145.9  5401.5  146.97    5443  148.22  5467.5  149.66
#Mann= 6 ,-1 , 0
  4538.5     .12       0  4902.4      .1       0  4970.8     .07       0
  5044.2      .1       0  5101.9     .12       0    5443     .05       0
Bank Sta=4970.8,5044.2
XS Rating Curve= 0 ,0
Exp/Cntr=0.3,0.1

Type RM Length L Ch R = 1 ,2009    ,582,582,582
BEGIN DESCRIPTION:
CRYSTAL CREEK TRIBUTARY NO 1 4.0
END DESCRIPTION:
XS GIS Cut Line= 3
      3861167.82     10092111.04      3860875.99     10091846.81
      3860264.05     10091746.99
#Sta/Elev= 30
    4654  151.59  4724.6  147.73  4767.2  138.38  4795.5   134.4  4816.5  128.22
  4844.9  123.61  4859.1  122.15  4887.5  123.89  4917.3  122.37  4944.2  123.62
  4972.6  121.55  4993.6  116.88  4995.7  114.37  5006.3  114.37  5007.8  116.42
  5015.2  116.98  5026.2 121.692  5036.1  124.68  5051.6  123.55  5056.6  125.28
  5147.1  123.26    5225  125.59  5302.4  132.52  5339.6  133.01  5358.8  135.41
  5425.3  137.71  5440.9  139.64    5522  142.12  5612.8  148.85  5667.7   150.5
#Mann= 6 ,-1 , 0
    4654     .12       0  4917.3      .1       0  4972.6     .07       0
  5026.2      .1       0    5225     .12       0  5612.8     .05       0
Bank Sta=4972.6,5026.2
XS Rating Curve= 0 ,0
Exp/Cntr=0.3,0.1

Type RM Length L Ch R = 1 ,1427    ,584,584,584
BEGIN DESCRIPTION:
CRYSTAL CREEK TRIBUTARY NO 1 3.0
END DESCRIPTION:
XS GIS Cut Line= 3
      3861416.35     10091601.58      3861216.71     10091434.48
      3860292.51     10091456.18
#Sta/Elev= 30
  4708.2  146.28  4744.9  145.14  4842.3  140.69  4856.6  138.51  4941.2  135.04
    4949  131.06  4955.5  130.13  4963.3  126.05 4973.43 122.617  4987.4  115.31
  5002.1  113.45  5012.7  113.45  5034.3  122.76  5039.3  121.13  5047.4  122.98
  5191.7  122.86  5267.5   120.5  5368.7  123.01  5527.6  129.56  5587.6  133.85
  5607.6  133.98    5655  136.88  5687.6  139.47  5707.4  139.48  5757.6  142.52
  5797.6  142.67  5827.6  146.05  5883.9  147.39  5887.1  147.59    5893  148.23
#Mann= 10 ,-1 , 0
  4708.2     .05       0  4744.9     .12       0 4973.43     .07       0
  5034.3     .12       0  5191.7      .1       0  5368.7     .12       0
    5655     .05       0  5707.4     .12       0  5883.9     .05       0
  5887.1     .12       0
Bank Sta=4973.43,5034.3
XS Rating Curve= 0 ,0
Exp/Cntr=0.3,0.1

Type RM Length L Ch R = 1 ,843     ,653,653,653
BEGIN DESCRIPTION:
CRYSTAL CREEK TRIBUTARY NO 1 2.0
END DESCRIPTION:
XS GIS Cut Line= 3
      3861422.88     10091549.52      3861106.03     10090915.82
      3860082.94     10091256.13
#Sta/Elev= 30
  4012.9  145.34  4028.2  145.37  4357.8  137.64  4417.3  132.53  4434.1  133.47
  4462.1  130.34    4593  123.64    4708  121.05  4786.8  121.42  4803.8  116.53
  4818.4  116.72  4844.8  120.71  4881.7  119.17  4908.1   122.5  4976.7   120.1
  4982.9  117.76  4997.7  111.93  5008.4  111.93 5018.08  117.84  5025.1   120.1
  5053.3   121.8  5103.3  123.26  5172.6  129.58    5278  135.99  5322.9  136.36
  5362.3  138.01  5493.4  138.08  5758.5  145.13  5768.8  145.41  5799.6  146.35
#Mann= 10 ,-1 , 0
  4012.9     .05       0  4028.2     .12       0    4593      .1       0
  4982.9     .07       0 5018.08      .1       0  5053.3     .12       0
  5322.9     .05       0  5493.4     .12       0  5758.5     .05       0
  5768.8     .12       0
Bank Sta=4982.9,5018.08
XS Rating Curve= 0 ,0
Exp/Cntr=0.3,0.1

Type RM Length L Ch R = 1 ,190     ,0,0,0
BEGIN DESCRIPTION:
CRYSTAL CREEK TRIBUTARY NO 1 1.0
END DESCRIPTION:
XS GIS Cut Line= 3
       3861492.3     10091130.65       3860919.4     10090399.33
      3859958.03     10090705.32
#Sta/Elev= 30
  4064.3  139.14  4095.7  137.89    4102  134.32  4145.4  139.11  4258.9  130.41
  4334.5  123.46  4426.2     120  4644.5  120.87  4665.3  118.83  4686.2  122.25
  4723.1  117.59  4928.4  119.71  4942.8  119.32 4962.32 112.122  4978.4  108.04
  4980.9  105.44  5018.4  107.02 5032.32 112.034  5045.3  118.77  5060.9  119.78
  5141.9  125.09  5211.7  133.22  5334.2  135.36  5442.1  134.58  5551.1  133.94
  5576.7  131.85  5666.6  134.33  5756.5  131.55  5911.3  134.82  6002.2  135.47
#Mann= 11 ,-1 , 0
  4064.3     .05       0  4258.9     .12       0  4334.5     .05       0
  4426.2      .1       0 4962.32     .07       0 5032.32      .1       0
  5060.9     .05       0  5334.2     .12       0  5442.1     .05       0
  5756.5     .12       0  5911.3     .05       0
Bank Sta=4962.32,5032.32
XS Rating Curve= 0 ,0
Exp/Cntr=0.3,0.1