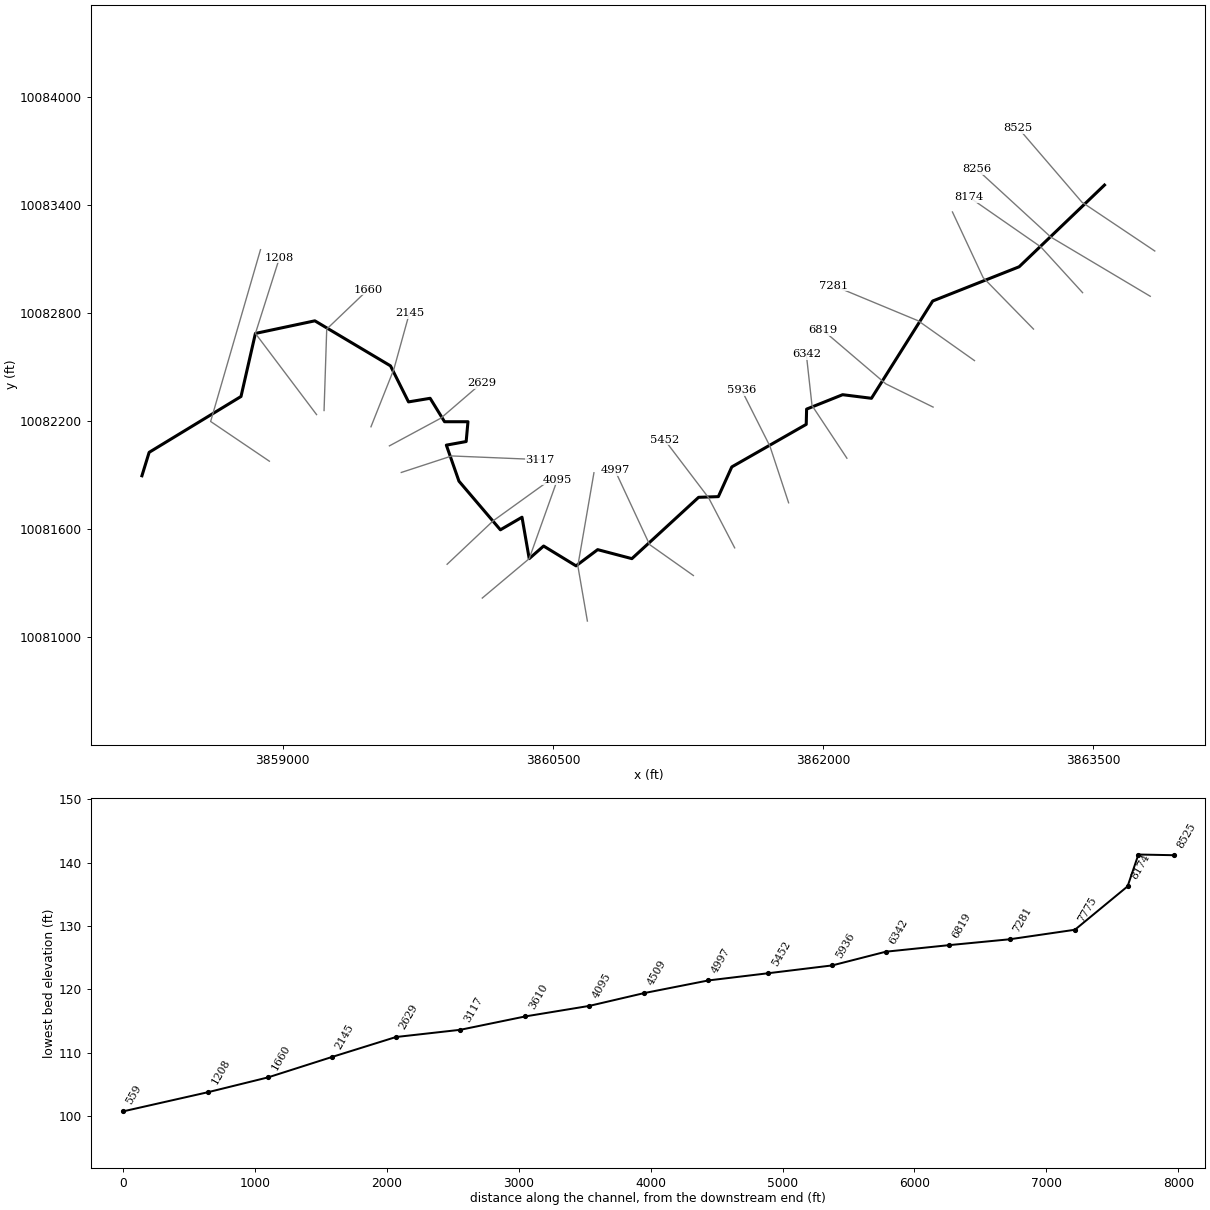
--- CRYSTAL CREEK TRIBUTARY NO 10.prj (project) ---

Proj Title=CRYSTAL CREEK TRIBUTARY NO 10 Base Level Engineering
Current Plan=p01
Default Exp/Contr=0.3,0.1
English Units
Geom File=g01
Flow File=f01
Plan File=p01
Y Axis Title=Elevation
X Axis Title(PF)=Main Channel Distance
X Axis Title(XS)=Station
BEGIN DESCRIPTION:
CRYSTAL CREEK TRIBUTARY NO 10
END DESCRIPTION:
DSS Export Rating Curves= 0
DSS Export Rating Curve Sorted= 0
DSS Export Volume Flow Curves= 0
DXF OffsetX= 0
DXF OffsetY= 0
DXF ScaleX= 1
DXF ScaleY= 10

--- CRYSTAL CREEK TRIBUTARY NO 10.p01 (plan) ---

Plan Title=Multiple Run
Short Identifier=Multiple
Geom File=g01
Flow File=f01
Subcritical Flow
K Sum by GR= 0
Std Step Tol= 0.01
Critical Tol= 0.01
Num of Std Step Trials= 20
Max Error Tol= 0.3
Flow Tol Ratio= 0.001
Split Flow NTrial= 30
Split Flow Tol= 0.02
Split Flow Ratio= 0.02
Log Output Level= 0
Friction Slope Method= 1
Unsteady Friction Slope Method= 2
Unsteady Bridges Friction Slope Method= 1
Parabolic Critical Depth
Global Vel Dist=  1 , 1 , 1
Global Log Level= 0
CheckData=True
Encroach Param= -1, 0, 0, 0
BEGIN DESCRIPTION:
Multiple Run
END DESCRIPTION:

--- CRYSTAL CREEK TRIBUTARY NO 10.f01 (steady flow) ---

Flow Title=Multiple
Program Version=4.10
Number of Profiles= 7
Profile Names=10-year,25-year,50-year,1pct_min,100-year,1pct_plu,500-year
River Rch & RM=CRYSTAL CREEK TR,Reach-1         ,8525
     665     876    1162     505    1526    4608    2724
River Rch & RM=CRYSTAL CREEK TR,Reach-1         ,6819
     786    1042    1389     607    1832    5533    3296
Boundary for River Rch & Prof#=CRYSTAL CREEK TR,Reach-1         , 1
Up Type= 0
Dn Type= 3
Dn Slope=0.005
Boundary for River Rch & Prof#=CRYSTAL CREEK TR,Reach-1         , 2
Up Type= 0
Dn Type= 3
Dn Slope=0.005
Boundary for River Rch & Prof#=CRYSTAL CREEK TR,Reach-1         , 3
Up Type= 0
Dn Type= 3
Dn Slope=0.005
Boundary for River Rch & Prof#=CRYSTAL CREEK TR,Reach-1         , 4
Up Type= 0
Dn Type= 3
Dn Slope=0.005
Boundary for River Rch & Prof#=CRYSTAL CREEK TR,Reach-1         , 5
Up Type= 0
Dn Type= 3
Dn Slope=0.005
Boundary for River Rch & Prof#=CRYSTAL CREEK TR,Reach-1         , 6
Up Type= 0
Dn Type= 3
Dn Slope=0.005
Boundary for River Rch & Prof#=CRYSTAL CREEK TR,Reach-1         , 7
Up Type= 0
Dn Type= 3
Dn Slope=0.005
DSS Import GetInterval= 0
DSS Import GetPeak= 0
DSS Import FillOption= 0

--- CRYSTAL CREEK TRIBUTARY NO 10.g01 (geometry) ---

Geom Title=Existing Conditions
Program Version=4.10

River Reach=CRYSTAL CREEK TR,Reach-1
Reach XY= 30
      3863561.95     10083510.45      3863088.24     10083056.86
      3862608.24     10082866.86      3862268.24     10082326.86
      3862108.24     10082346.86      3861908.24     10082266.86
      3861906.14     10082182.16      3861492.95     10081946.05
      3861418.29     10081781.12      3861308.66     10081777.29
      3860938.24     10081436.86      3860748.24     10081486.86
      3860628.24     10081396.86      3860448.24     10081506.86
      3860368.24     10081436.86      3860328.24     10081666.86
      3860208.24     10081596.86      3859978.24     10081866.86
      3859908.24     10082066.86      3860018.24     10082086.86
      3860028.24     10082196.86      3859898.24     10082196.86
      3859818.24     10082326.86      3859698.24     10082306.86
      3859598.24     10082506.86      3859178.24     10082756.86
      3858848.24     10082686.86      3858768.24     10082336.86
      3858258.24     10082026.86      3858218.24     10081896.86

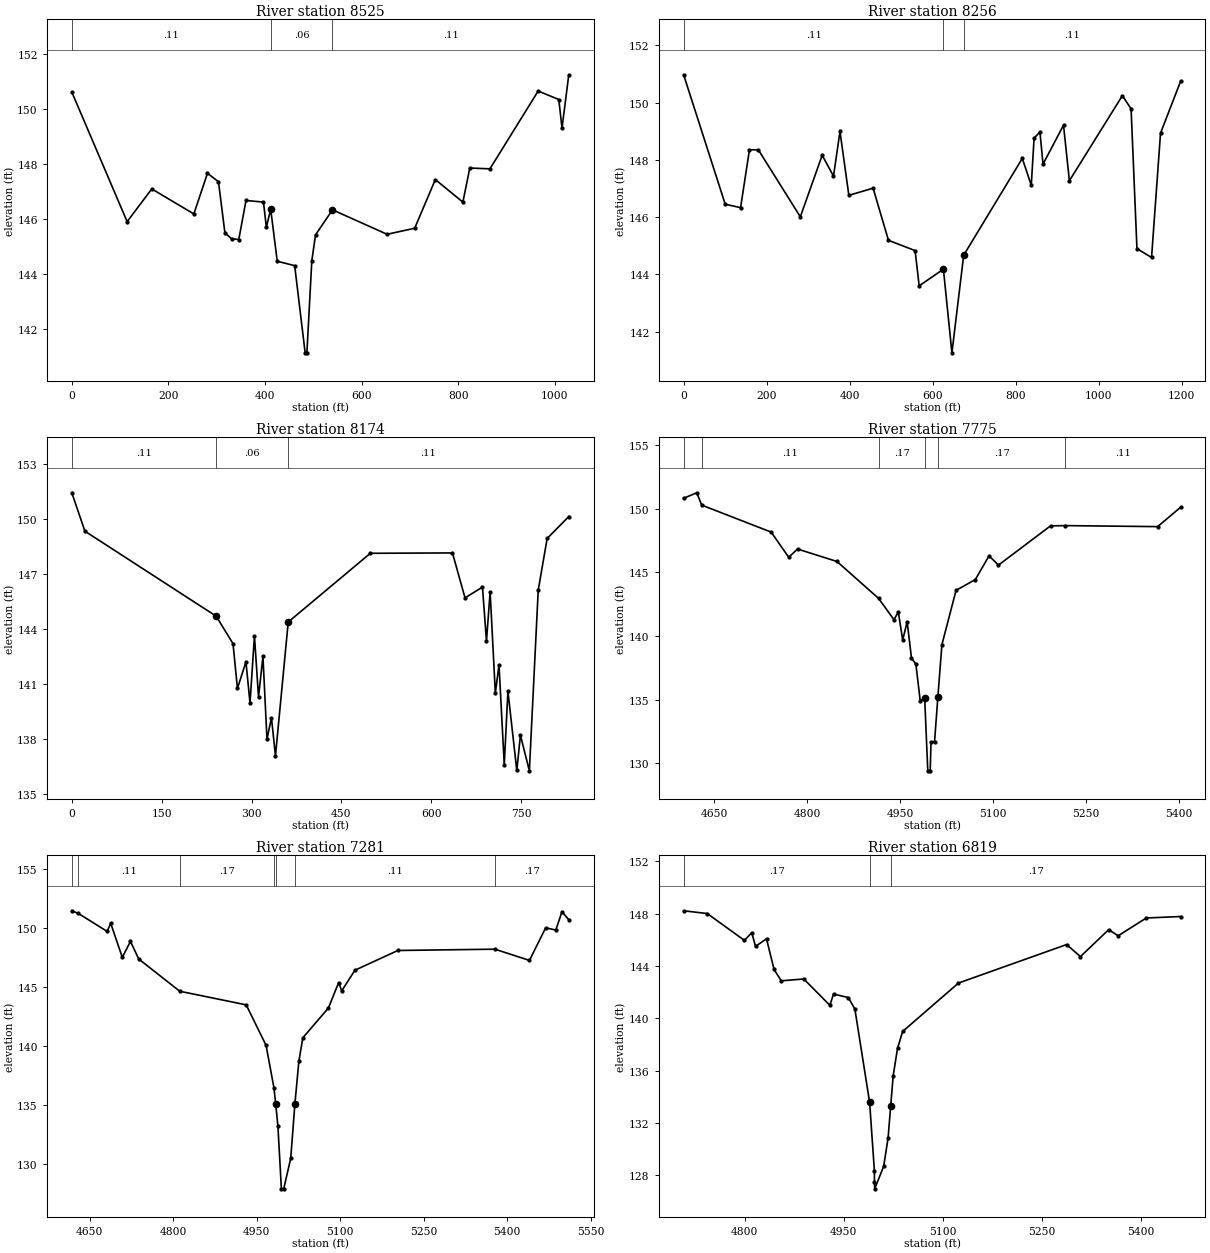
Type RM Length L Ch R = 1 ,8525    ,269,269,269
XS GIS Cut Line= 3
      3863841.12     10083144.43      3863436.86     10083415.27
      3863083.21     10083826.74
#Sta/Elev= 30
       0  150.63   114.5  145.92   165.5  147.11   252.6   146.2   280.8  147.68
   303.6  147.37   316.9  145.51   330.6   145.3   345.6  145.27   360.6  146.69
   396.7  146.63   402.7  145.72   411.7  146.37   425.2  144.48   461.3  144.32
     483  141.15   486.6  141.15   496.8   144.5   504.5  145.44   539.6  146.35
   652.6  145.46   709.7  145.68   752.5  147.45   809.5  146.63   823.8  147.87
   865.5  147.84   965.4  150.67  1008.1  150.36  1014.7  149.32  1028.7  151.26
#Mann= 3 , 0 , 0
       0     .11       0   411.7     .06       0   539.6     .11       0
Bank Sta=411.7,539.6
XS Rating Curve= 0 ,0
Exp/Cntr=0.3,0.1

Type RM Length L Ch R = 1 ,8256    ,82,82,82
XS GIS Cut Line= 3
      3863816.01      10082893.1      3863263.79     10083221.86
      3862854.36     10083597.35
#Sta/Elev= 30
       0  150.97   100.2  146.45   137.2  146.33   158.6  148.35     180  148.35
   281.2  146.01   333.8  148.16   361.1  147.43   376.7  148.99   398.1  146.76
   456.5  147.01   493.5  145.19   557.7  144.83   567.5   143.6   625.9  144.18
   646.4  141.26   674.8  144.67     816  148.05   837.6  147.11   844.4  148.76
   858.5  148.97   865.9  147.85   915.3  149.21   929.4  147.27  1057.1  150.24
  1078.1  149.78  1092.2   144.9  1127.4  144.59    1149  148.93  1197.3  150.74
#Mann= 3 , 0 , 0
       0     .11       0   625.9     .06       0   674.8     .11       0
#Block Obstruct= 2 , 0
       0                  1057.1       0  150.24
Bank Sta=625.9,674.8
XS Rating Curve= 0 ,0
Exp/Cntr=0.3,0.1

Type RM Length L Ch R = 1 ,8174    ,399,399,399
XS GIS Cut Line= 3
      3863440.44     10082913.11       3863208.5     10083167.13
      3862809.51     10083444.06
#Sta/Elev= 30
       0  151.45    21.8  149.35     241   144.7   269.1   143.2   276.5  140.75
   290.7   142.2   297.5  139.95   304.9  143.62   311.7  140.28   319.1   142.5
   325.8  137.97   333.3  139.14     340  137.06   361.3  144.38   498.4  148.14
   635.5  148.16   656.5   145.7   685.6  146.29   692.3  143.34   698.4  146.03
   707.1  140.49   713.2  142.04     722  136.58   728.1   140.6   742.9  136.26
     749  138.19   763.9  136.24   778.7  146.12   793.6  148.95   829.7  150.15
#Mann= 3 , 0 , 0
       0     .11       0     241     .06       0   361.3     .11       0
#Block Obstruct= 2 , 0
       0                   635.5       0  148.16
Bank Sta=241,361.3
XS Rating Curve= 0 ,0
Exp/Cntr=0.3,0.1

Type RM Length L Ch R = 1 ,7775    ,494,494,494
BEGIN DESCRIPTION:
CRYSTAL CREEK TRIBUTARY NO 10 15.0
END DESCRIPTION:
XS GIS Cut Line= 3
      3863167.83     10082711.09      3862888.24     10082996.86
      3862717.85     10083361.08
#Sta/Elev= 30
  4600.2  150.82  4621.4  151.25  4629.4  150.28  4741.5  148.16  4769.8  146.18
    4784  146.83  4847.7  145.85  4914.8  142.95  4939.6  141.28  4946.7  141.88
  4953.7  139.68  4960.9  141.11  4967.9  138.26    4975  137.78    4982   134.9
  4989.2   135.1  4994.2   129.4  4998.1   129.4  4999.4  131.68  5005.1  131.68
  5010.5  135.22    5017  139.32  5039.8  143.58  5070.9  144.43    5093  146.29
  5108.3  145.57  5192.3  148.65  5216.2  148.67  5365.1  148.59  5402.1  150.11
#Mann= 6 ,-1 , 0
  4600.2     .17       0  4629.4     .11       0  4914.8     .17       0
  4989.2     .09       0  5010.5     .17       0  5216.2     .11       0
#XS Ineff= 2 , 0
       0  4960.9  141.11               0
Permanent Ineff=
       F       F
Bank Sta=4989.2,5010.5
XS Rating Curve= 0 ,0
Exp/Cntr=0.3,0.1

Type RM Length L Ch R = 1 ,7281    ,462,462,462
BEGIN DESCRIPTION:
CRYSTAL CREEK TRIBUTARY NO 10 14.0
END DESCRIPTION:
XS GIS Cut Line= 3
       3862840.2     10082536.06      3862528.24     10082756.86
      3862056.36     10082952.71
#Sta/Elev= 30
  4617.8  151.43  4629.7   151.2  4681.4  149.68  4687.6  150.38  4708.5  147.49
  4723.2  148.84    4738  147.35  4811.8  144.62  4931.2  143.47  4966.9  140.04
    4981  136.46 4984.26135.0611  4988.2   133.2  4994.4   127.9  4998.6   127.9
  5011.2  130.48 5018.73135.1056  5025.8  138.68  5032.9  140.68  5078.9   143.2
  5097.4  145.36  5102.8  144.65  5126.6   146.4  5203.7  148.07  5378.1  148.18
  5440.2  147.23  5469.4  149.99  5487.6   149.8  5498.7  151.35  5510.9  150.67
#Mann= 7 ,-1 , 0
  4617.8     .17       0  4629.7     .11       0  4811.8     .17       0
    4981     .11       0 4984.26     .09       0 5018.73     .11       0
  5378.1     .17       0
Bank Sta=4984.26,5018.73
XS Rating Curve= 0 ,0
Exp/Cntr=0.3,0.1

Type RM Length L Ch R = 1 ,6819    ,477,477,477
BEGIN DESCRIPTION:
CRYSTAL CREEK TRIBUTARY NO 10 13.0
END DESCRIPTION:
XS GIS Cut Line= 3
      3862610.42     10082278.09      3862348.24     10082406.86
      3861998.46     10082705.16
#Sta/Elev= 30
  4707.9  148.21  4743.6     148  4799.9  145.95    4811  146.54  4816.7  145.49
  4833.3  146.07  4844.7  143.73  4855.6  142.86  4889.7     143  4929.1  140.99
  4934.7  141.85  4957.1  141.58    4967   140.7  4989.3  133.57  4996.5  128.35
  4996.6  127.47    4997  126.97  5010.6   128.7  5017.2  130.85 5021.17 133.299
  5024.9   135.6  5031.5   137.7  5039.2  138.99  5123.7  142.69  5287.3  145.63
  5308.2  144.71    5351  146.77  5365.3   146.3  5407.9  147.66  5459.7  147.77
#Mann= 3 , 0 , 0
  4707.9     .17       0  4989.3     .09       0 5021.17     .17       0
Bank Sta=4989.3,5021.17
XS Rating Curve= 0 ,0
Exp/Cntr=0.3,0.1

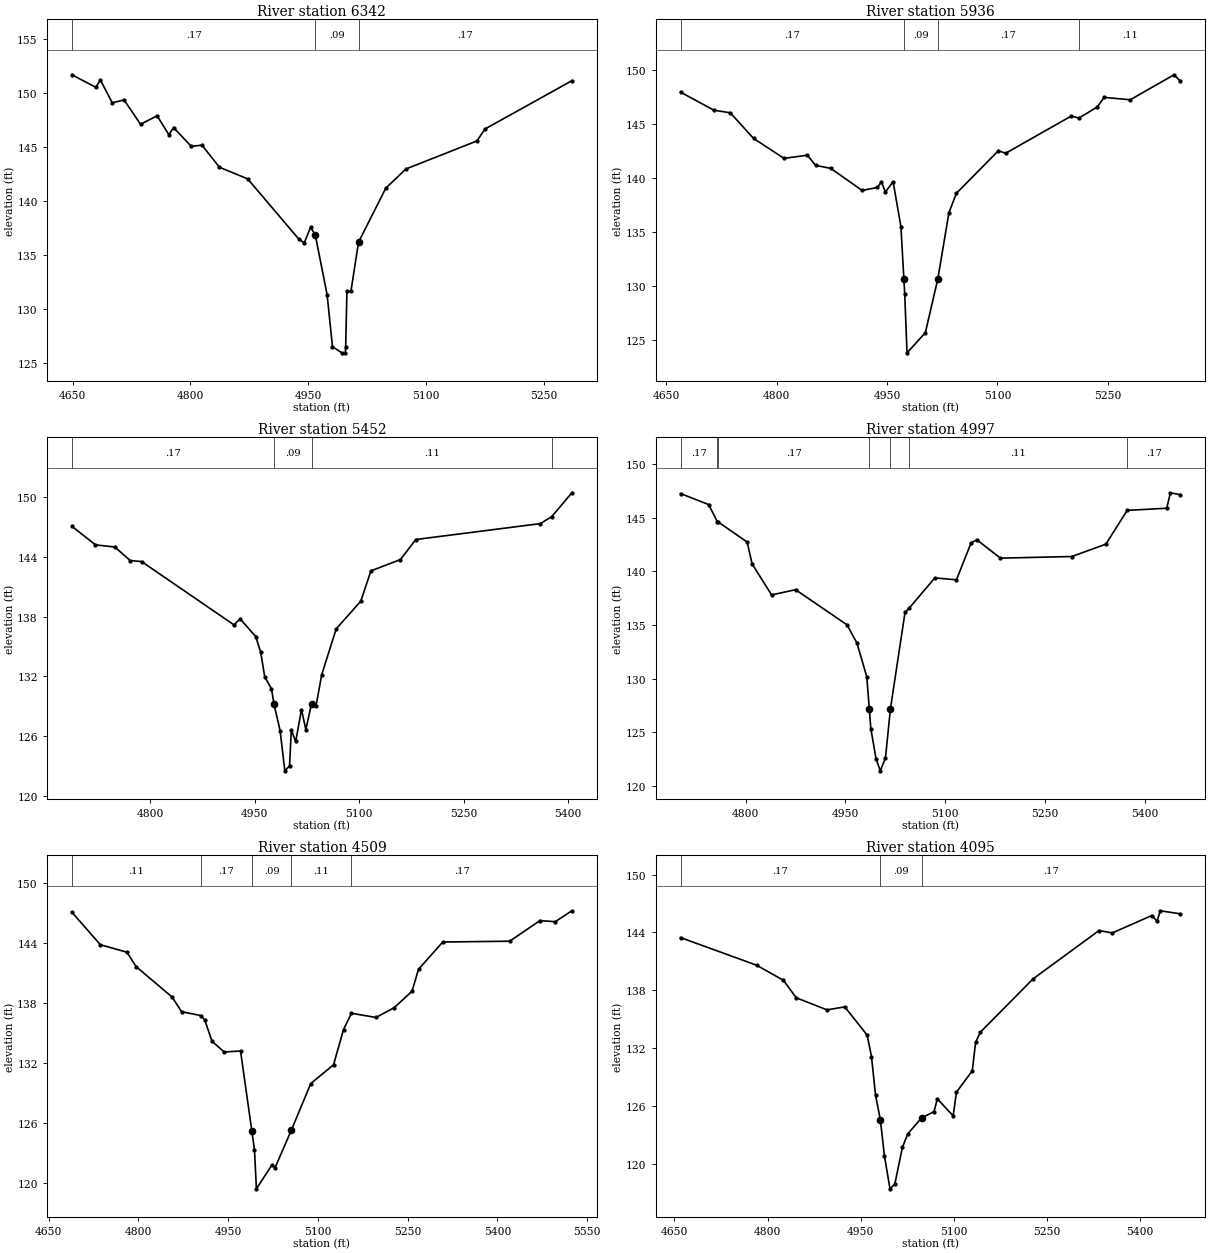
Type RM Length L Ch R = 1 ,6342    ,406,406,406
BEGIN DESCRIPTION:
CRYSTAL CREEK TRIBUTARY NO 10 12.0
END DESCRIPTION:
XS GIS Cut Line= 3
       3862131.9     10081994.37      3861938.24     10082286.86
      3861906.64     10082571.21
#Sta/Elev= 30
  4649.2  151.71  4679.5  150.55  4685.5  151.22  4700.5  149.11  4715.6  149.38
  4736.6  147.12  4757.7  147.91  4772.7  146.15  4778.7  146.82  4801.2  145.07
  4814.8  145.19  4837.1  143.14  4873.1  142.06  4938.2  136.48  4945.1  136.13
  4953.2  137.58  4959.2  136.86  4974.3  131.31  4981.1  126.51  4993.1  125.94
  4997.5  125.94  4997.9  126.44  4999.5  131.64  5004.6  131.64  5014.3   136.2
  5049.1  141.21  5074.7  142.98  5165.2  145.58  5175.3  146.68  5286.1  151.16
#Mann= 3 , 0 , 0
  4649.2     .17       0  4959.2     .09       0  5014.3     .17       0
#XS Ineff= 2 , 0
       0  4953.2  137.58               0
Permanent Ineff=
       F       F
Bank Sta=4959.2,5014.3
XS Rating Curve= 0 ,0
Exp/Cntr=0.3,0.1

Type RM Length L Ch R = 1 ,5936    ,484,484,484
BEGIN DESCRIPTION:
CRYSTAL CREEK TRIBUTARY NO 10 11.0
END DESCRIPTION:
XS GIS Cut Line= 3
      3861808.32     10081746.89      3861704.75     10082060.64
      3861547.91     10082371.85
#Sta/Elev= 30
  4669.6  147.99  4714.9  146.31  4737.2  146.07  4768.8  143.69  4810.1  141.84
  4841.9  142.13    4853  141.19  4873.6  140.91  4916.2  138.86  4937.1  139.14
  4942.4  139.67  4947.8  138.71  4958.3  139.67  4968.9  135.51 4972.89130.6759
  4974.1  129.21  4977.2  123.78  5002.1  125.65 5019.08 130.661  5034.1  136.78
  5044.2  138.59  5101.3  142.55  5111.1  142.31  5200.3  145.77  5210.6  145.58
  5235.6  146.61  5244.9   147.5  5280.4  147.28  5339.8   149.6  5348.5  149.01
#Mann= 4 ,-1 , 0
  4669.6     .17       0 4972.89     .09       0 5019.08     .17       0
  5210.6     .11       0
Bank Sta=4972.89,5019.08
XS Rating Curve= 0 ,0
Exp/Cntr=0.3,0.1

Type RM Length L Ch R = 1 ,5452    ,455,455,455
BEGIN DESCRIPTION:
CRYSTAL CREEK TRIBUTARY NO 10 10.0
END DESCRIPTION:
XS GIS Cut Line= 3
      3861508.87     10081496.81      3861364.48     10081774.18
       3861119.1     10082097.26
#Sta/Elev= 30
  4687.3  147.04  4721.1  145.18  4748.9  144.97    4771  143.61  4787.4  143.51
  4920.1  137.17  4928.9  137.77  4951.4     136  4958.6  134.41  4964.3  131.96
    4974  130.77  4977.7129.1961  4986.4  126.59  4993.2  122.55    5000  123.05
  5002.5  126.65  5008.8  125.49  5017.1  128.68  5023.4  126.69  5031.6  129.28
  5037.9     129  5046.2  132.18    5067  136.77  5102.4  139.55  5116.9  142.58
  5159.3  143.71  5181.4  145.72  5360.2  147.31  5376.5  147.99  5405.7   150.4
#Mann= 4 ,-1 , 0
  4687.3     .17       0  4977.7     .09       0  5031.6     .11       0
  5376.5     .17       0
Bank Sta=4977.7,5031.6
XS Rating Curve= 0 ,0
Exp/Cntr=0.3,0.1

Type RM Length L Ch R = 1 ,4997    ,488,488,488
BEGIN DESCRIPTION:
CRYSTAL CREEK TRIBUTARY NO 10 9.0
END DESCRIPTION:
XS GIS Cut Line= 3
      3861279.65     10081343.22      3861036.43     10081515.05
      3860844.88     10081926.34
#Sta/Elev= 30
  4702.2  147.25  4744.5  146.22  4757.6  144.62  4758.3  144.62  4802.4  142.73
  4809.8   140.7  4839.1   137.8  4875.1  138.29  4952.6  135.01  4967.4  133.31
  4982.2  130.18 4986.03127.1412  4988.3  125.34  4996.1  122.55  5002.5  121.41
  5010.3  122.61  5017.7  127.17  5039.7  136.18  5045.7  136.55  5084.5  139.39
    5117  139.21    5139  142.65  5147.6  142.94  5183.1  141.23  5290.3  141.38
  5341.6  142.53  5373.7  145.68  5433.1  145.88  5438.6  147.32  5453.7  147.14
#Mann= 7 ,-1 , 0
  4702.2     .17       0  4757.6     .11       0  4758.3     .17       0
 4986.03     .09       0  5017.7     .17       0  5045.7     .11       0
  5373.7     .17       0
Bank Sta=4986.03,5017.7
XS Rating Curve= 0 ,0
Exp/Cntr=0.3,0.1

Type RM Length L Ch R = 1 ,4509    ,414,414,414
BEGIN DESCRIPTION:
CRYSTAL CREEK TRIBUTARY NO 10 8.0
END DESCRIPTION:
XS GIS Cut Line= 3
      3860691.14      10081090.6      3860638.24     10081396.86
       3860727.6     10081913.49
#Sta/Elev= 30
  4689.2  147.04  4736.6   143.8    4781  143.05  4796.4  141.61  4856.3  138.58
  4872.3  137.11  4904.4  136.72    4911  136.28  4923.1  134.16  4943.4  133.08
  4970.8  133.18 4989.66125.1908  4994.1  123.31  4997.3  119.41  5023.3   121.8
  5028.4  121.51  5055.6  125.26  5088.1  129.93  5126.1   131.8  5142.8  135.32
  5156.1  136.95  5197.1  136.53  5227.5  137.51  5257.3  139.15  5268.1  141.35
  5308.7  144.07  5420.4  144.15  5471.1  146.21  5496.5   146.1  5524.3  147.19
#Mann= 5 ,-1 , 0
  4689.2     .11       0  4904.4     .17       0 4989.66     .09       0
  5055.6     .11       0  5156.1     .17       0
Bank Sta=4989.66,5055.6
XS Rating Curve= 0 ,0
Exp/Cntr=0.3,0.1

Type RM Length L Ch R = 1 ,4095    ,485,485,485
BEGIN DESCRIPTION:
CRYSTAL CREEK TRIBUTARY NO 10 7.0
END DESCRIPTION:
XS GIS Cut Line= 3
      3860107.77     10081218.17      3860368.24     10081436.86
      3860524.46     10081874.41
#Sta/Elev= 30
  4659.9  143.47  4782.5   140.6  4825.5  139.04  4846.3  137.22  4895.7  135.97
  4924.3  136.28  4960.3  133.35  4967.3  131.13  4973.8  127.13  4981.6  124.56
  4988.1  120.84  4997.1   117.4  5004.9   117.9  5017.1  121.71  5025.7   123.1
  5047.9  124.76    5068  125.41  5073.3  126.74  5098.8  124.97  5104.1  127.43
  5129.6  129.65  5134.9  132.61  5142.5  133.65  5227.5  139.19  5333.6   144.2
  5354.9  143.95  5418.6  145.76    5427  145.17  5432.3  146.25  5464.6  145.93
#Mann= 3 , 0 , 0
  4659.9     .17       0  4981.6     .09       0  5047.9     .17       0
Bank Sta=4981.6,5047.9
XS Rating Curve= 0 ,0
Exp/Cntr=0.3,0.1

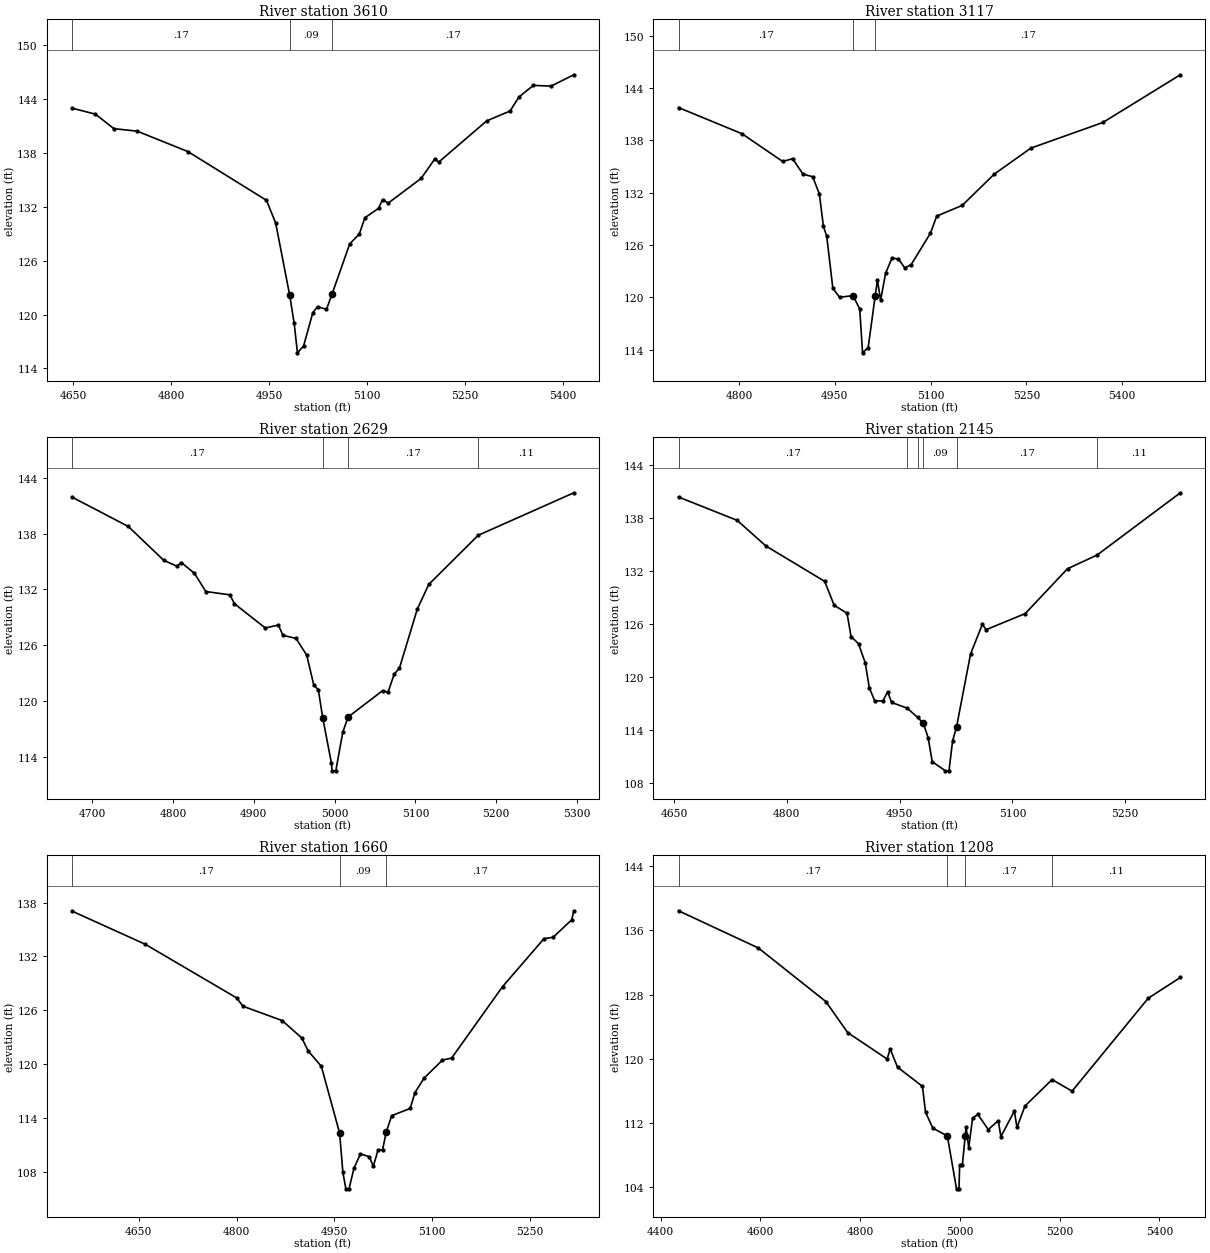
Type RM Length L Ch R = 1 ,3610    ,493,493,493
BEGIN DESCRIPTION:
CRYSTAL CREEK TRIBUTARY NO 10 6.0
END DESCRIPTION:
XS GIS Cut Line= 3
      3859912.51     10081405.71      3860168.24     10081646.86
      3860506.23     10081890.06
#Sta/Elev= 30
  4648.5  142.95  4684.2  142.28  4712.5  140.67  4748.1  140.39  4825.8  138.12
    4946   132.7  4960.1  130.17  4981.6  122.12  4988.4  119.01  4993.4  115.74
  5002.8   116.5  5016.9   120.2  5024.2  120.88  5037.8  120.57  5046.3  122.26
  5073.4  127.86  5088.1  128.96  5096.6  130.76  5117.5  131.81  5123.7  132.79
  5132.3  132.39  5182.6  135.13  5203.5  137.29  5209.6  136.95  5282.9  141.53
  5318.8  142.63  5332.2  144.18  5354.4  145.48  5381.5   145.4  5416.4  146.66
#Mann= 3 , 0 , 0
  4648.5     .17       0  4981.6     .09       0  5046.3     .17       0
Bank Sta=4981.6,5046.3
XS Rating Curve= 0 ,0
Exp/Cntr=0.3,0.1

Type RM Length L Ch R = 1 ,3117    ,488,488,488
BEGIN DESCRIPTION:
CRYSTAL CREEK TRIBUTARY NO 10 5.0
END DESCRIPTION:
XS GIS Cut Line= 3
      3859658.14     10081915.24      3859938.24     10082006.86
      3860429.01     10081986.43
#Sta/Elev= 30
  4705.3  141.75  4804.7  138.75  4868.4  135.57  4883.9  135.89  4900.3  134.11
  4915.4  133.83  4925.9  131.83  4932.2  128.14  4937.4  126.99    4947  121.02
  4957.5  120.01  4978.6  120.18  4989.1  118.65  4993.5  113.63  5002.3  114.23
 5013.34120.1775  5016.8  121.97  5021.8  119.65  5029.6  122.76  5039.7   124.5
  5049.7  124.39  5059.7  123.36  5069.7  123.75  5099.7  127.33  5109.7  129.31
  5149.7  130.54  5199.8  134.12  5257.1   137.1  5369.9  140.04  5491.2  145.51
#Mann= 3 , 0 , 0
  4705.3     .17       0  4978.6     .09       0 5013.34     .17       0
#XS Ineff= 2 , 0
       0                  5039.7       0   124.5
Permanent Ineff=
       F       F
Bank Sta=4978.6,5013.34
XS Rating Curve= 0 ,0
Exp/Cntr=0.3,0.1

Type RM Length L Ch R = 1 ,2629    ,484,484,484
BEGIN DESCRIPTION:
CRYSTAL CREEK TRIBUTARY NO 10 4.0
END DESCRIPTION:
XS GIS Cut Line= 3
      3859592.18     10082062.81      3859878.24     10082216.86
      3860102.63     10082410.06
#Sta/Elev= 30
  4675.1  141.93  4744.6  138.78  4788.4  135.15  4804.7   134.5  4810.3   134.9
  4826.6  133.73  4840.6  131.78  4870.4  131.42    4876  130.47  4914.2  127.86
  4930.4  128.17  4936.1  127.07  4952.3  126.73  4965.5  124.93  4974.2  121.73
  4979.9   121.2 4985.24118.2275  4996.1  113.31  4996.8  112.49  5001.5  112.49
  5010.1  116.64  5016.7  118.28  5059.5  121.12  5066.1  120.94  5073.7  122.88
  5080.3  123.55  5102.3  129.88  5116.5  132.54  5177.6  137.82  5296.1   142.4
#Mann= 4 ,-1 , 0
  4675.1     .17       0 4985.24     .09       0  5016.7     .17       0
  5177.6     .11       0
#XS Ineff= 2 , 0
       0                  5059.5       0  121.12
Permanent Ineff=
       F       F
Bank Sta=4985.24,5016.7
XS Rating Curve= 0 ,0
Exp/Cntr=0.3,0.1

Type RM Length L Ch R = 1 ,2145    ,485,485,485
BEGIN DESCRIPTION:
CRYSTAL CREEK TRIBUTARY NO 10 3.0
END DESCRIPTION:
XS GIS Cut Line= 3
      3859489.75      10082168.7      3859616.85     10082488.25
      3859703.07     10082799.84
#Sta/Elev= 30
  4656.1  140.36    4734  137.72  4772.2  134.82  4850.4  130.81  4863.1  128.09
  4880.1   127.2  4885.5  124.56  4895.4  123.75  4904.4  121.57  4909.8  118.74
  4916.9  117.29  4927.7  117.25  4934.1  118.29  4939.5  117.09  4960.3  116.44
    4974   115.4  4981.5  114.75    4988   113.1  4993.4  110.39    5011  109.35
  5015.7  109.35  5020.5  112.74  5025.7   114.3  5044.4  122.59    5060  125.93
  5065.2  125.34  5117.1  127.16  5173.3  132.24  5212.5  133.78  5323.3  140.84
#Mann= 6 ,-1 , 0
  4656.1     .17       0  4960.3     .11       0    4974     .17       0
  4981.5     .09       0  5025.7     .17       0  5212.5     .11       0
#XS Ineff= 2 , 0
       0  4934.1  118.29               0
Permanent Ineff=
       F       F
Bank Sta=4981.5,5025.7
XS Rating Curve= 0 ,0
Exp/Cntr=0.3,0.1

Type RM Length L Ch R = 1 ,1660    ,452,452,452
BEGIN DESCRIPTION:
CRYSTAL CREEK TRIBUTARY NO 10 2.0
END DESCRIPTION:
XS GIS Cut Line= 3
      3859229.34     10082259.02      3859244.12     10082710.98
      3859473.47     10082930.24
#Sta/Elev= 30
  4547.8  137.04  4660.1  133.35    4800  127.39    4810  126.45    4870  124.86
    4900  122.93    4910  121.47  4930.1  119.76  4958.1  112.33  4963.1  107.96
  4967.7  106.13  4972.5  106.13  4980.1  108.42  4990.1  110.03  5003.7   109.7
  5009.7  108.63    5017  110.44  5023.9  110.46 5029.57112.4523    5038  114.28
  5066.3  115.08  5073.6  116.84  5087.7  118.46  5115.8  120.46  5129.9  120.69
  5207.9  128.63  5271.4  133.97  5285.5  134.13  5313.9  136.07  5317.3  137.08
#Mann= 3 , 0 , 0
  4547.8     .17       0  4958.1     .09       0 5029.57     .17       0
Bank Sta=4958.1,5029.57
XS Rating Curve= 0 ,0
Exp/Cntr=0.3,0.1

Type RM Length L Ch R = 1 ,1208    ,649,649,649
BEGIN DESCRIPTION:
CRYSTAL CREEK TRIBUTARY NO 10 1.0
END DESCRIPTION:
XS GIS Cut Line= 3
      3859187.67     10082236.44      3858848.24     10082686.86
      3858982.23     10083107.85
#Sta/Elev= 30
    4436  138.45  4595.9  133.82  4731.3  127.14    4775  123.28  4854.1  119.98
  4860.3  121.24  4874.9  118.97  4924.9  116.58  4931.1  113.35  4945.7  111.37
  4974.8   110.4  4993.2  103.81  4998.1  103.81  4999.5  106.75  5004.8  106.75
 5010.65110.4217  5012.4  111.52  5017.7  108.92  5025.4  112.63  5035.9  113.08
  5056.9   111.2  5076.9   112.3  5082.1  110.31  5109.1   113.5  5114.4  111.46
  5130.3  114.12  5184.7  117.42  5224.8  115.98  5377.4  127.55  5441.8  130.14
#Mann= 4 ,-1 , 0
    4436     .17       0  4974.8     .09       0 5010.65     .17       0
  5184.7     .11       0
#XS Ineff= 2 ,-1
  5035.9  5109.1  113.08  5109.1  5140.8   113.5
Permanent Ineff=
       F       F
Bank Sta=4974.8,5010.65
XS Rating Curve= 0 ,0
Exp/Cntr=0.3,0.1

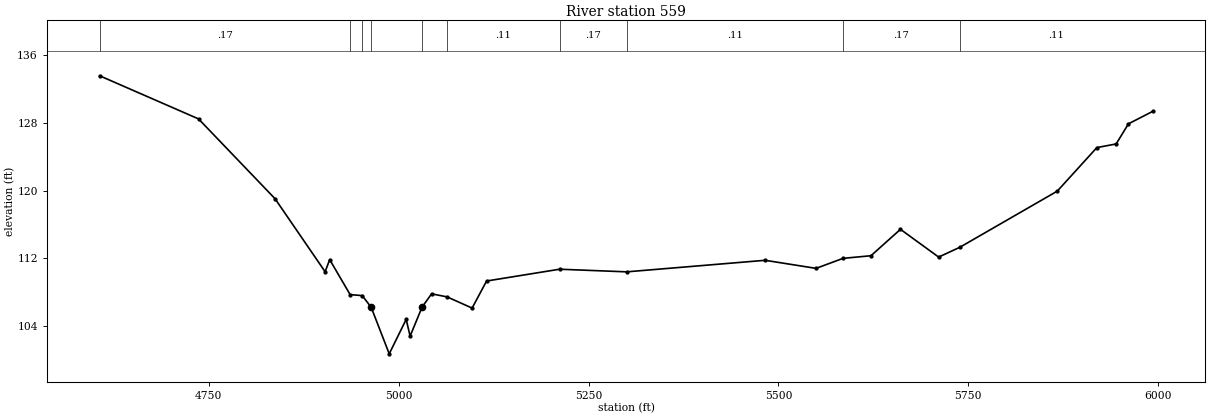
Type RM Length L Ch R = 1 ,559     ,0,0,0
BEGIN DESCRIPTION:
CRYSTAL CREEK TRIBUTARY NO 10 1.5
END DESCRIPTION:
XS GIS Cut Line= 3
      3858925.74      10081977.7      3858599.61     10082198.24
      3858876.45     10083151.76
#Sta/Elev= 30
  4606.3  133.52  4736.5  128.44  4837.3  119.03  4903.2  110.43  4909.2  111.86
  4936.1  107.74    4952  107.62 4963.82106.2486  4987.6  100.76  5009.9  104.82
  5015.1  102.85 5030.92106.2821  5043.4  107.83  5063.8  107.47  5096.7  106.15
  5115.8  109.34  5211.9  110.73  5300.2  110.42  5482.5  111.78  5549.6  110.83
  5585.1  112.01  5621.9  112.32  5660.7  115.43    5711  112.16    5739  113.32
  5867.2  119.93  5919.3  125.06  5944.7  125.49  5960.9  127.86  5992.9  129.33
#Mann= 10 ,-1 , 0
  4606.3     .17       0  4936.1     .11       0    4952     .15       0
 4963.82     .09       0 5030.92     .15       0  5063.8     .11       0
  5211.9     .17       0  5300.2     .11       0  5585.1     .17       0
    5739     .11       0
Bank Sta=4963.82,5030.92
XS Rating Curve= 0 ,0
Exp/Cntr=0.3,0.1

Chan Stop Cuts=-1
Use User Specified Reach Order=0
Composite Channel Slope=5

--- CRYSTAL CREEK TRIBUTARY NO 10.g10 (geometry) ---

Geom Title=Existing Conditions
Program Version=4.10

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
River Reach=CRYSTAL CREEK TR,Reach-1

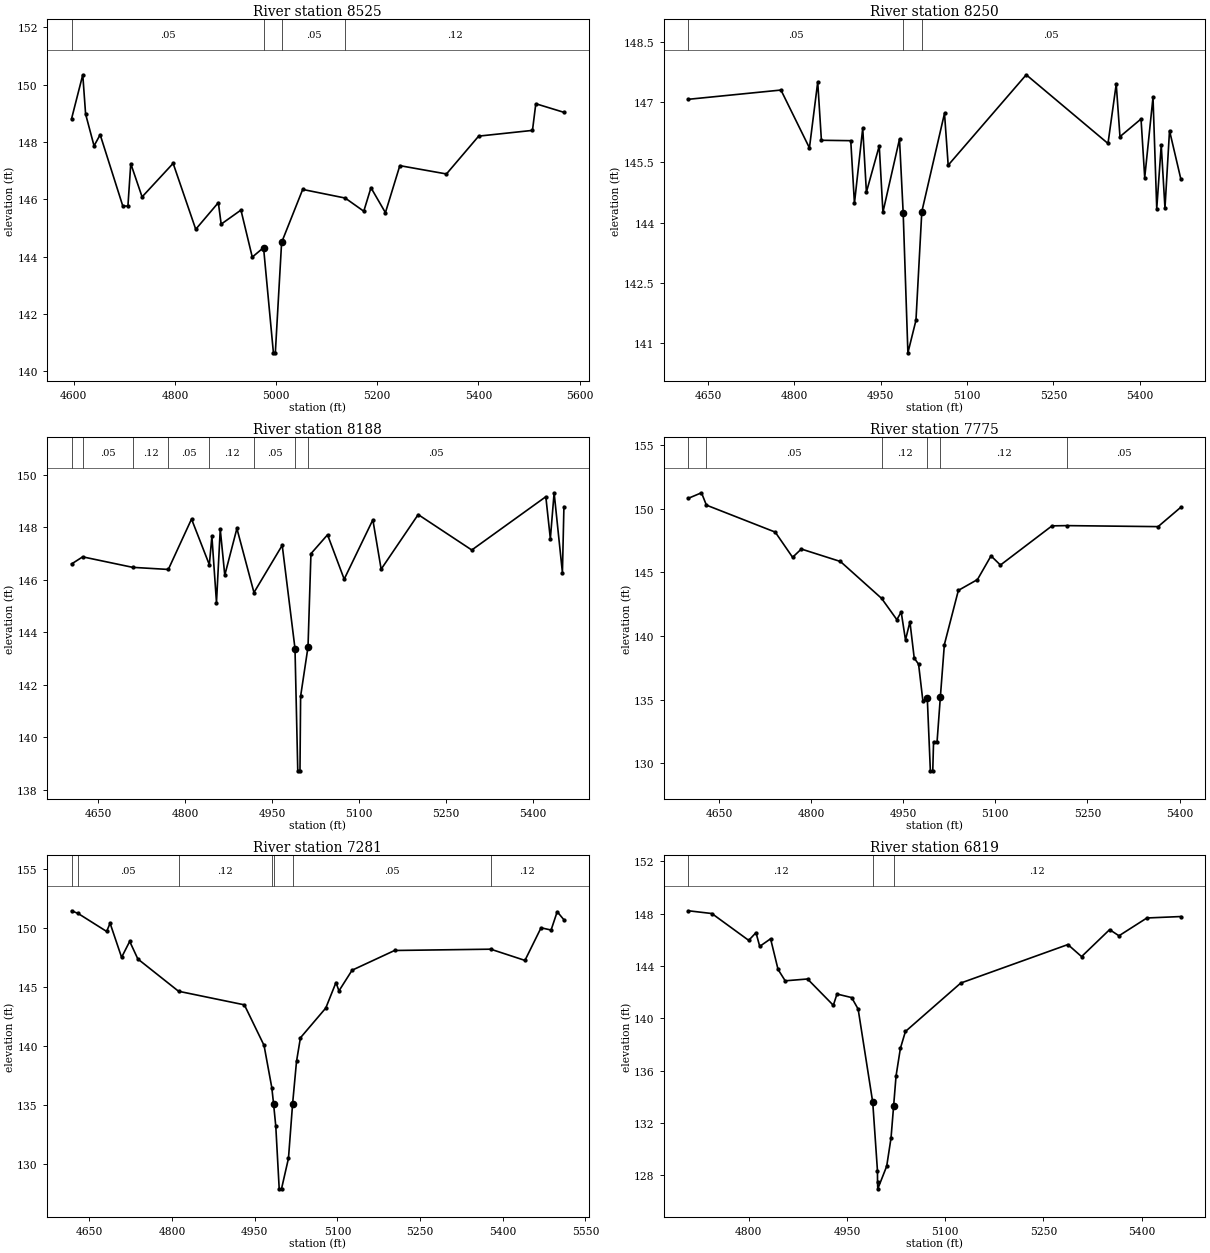
Type RM Length L Ch R = 1 ,8525    ,275,275,275
BEGIN DESCRIPTION:
CRYSTAL CREEK TRIBUTARY NO 10 16.25
END DESCRIPTION:
XS GIS Cut Line= 3
      3863798.41      10083234.1      3863436.86     10083415.27
      3863004.68     10083785.68
#Sta/Elev= 30
  4595.6  148.82  4617.7  150.35  4623.3  148.98    4640  147.87  4652.1  148.26
  4696.9  145.77    4707  145.77  4712.6  147.25    4735  146.09  4796.4  147.26
  4841.1  144.96  4885.8  145.89  4891.4  145.14  4930.5  145.63  4952.9  143.99
  4975.2  144.32  4994.7  140.65  4998.5  140.65  5010.9   144.5  5052.6  146.35
  5136.6  146.05  5173.4  145.59  5187.6  146.41  5216.2  145.54  5244.7  147.18
  5336.9  146.89  5400.6  148.21    5507  148.41  5513.6  149.34  5569.2  149.04
#Mann= 4 ,-1 , 0
  4595.6     .05       0  4975.2     .07       0  5010.9     .05       0
  5136.6     .12       0
Bank Sta=4975.2,5010.9
XS Rating Curve= 0 ,0
Exp/Cntr=0.3,0.1

Type RM Length L Ch R = 1 ,8250    ,62,62,62
BEGIN DESCRIPTION:
CRYSTAL CREEK TRIBUTARY NO 10 16.5
END DESCRIPTION:
XS GIS Cut Line= 3
      3863556.35     10082973.56      3863259.42     10083217.06
      3862895.17     10083516.46
#Sta/Elev= 30
    4616  147.07  4776.7   147.3  4826.2  145.86  4840.6   147.5    4847  146.05
    4898  146.04  4904.4  144.48  4918.8  146.35  4925.2  144.76  4947.5  145.91
  4953.9  144.26  4982.7  146.08  4989.1  144.24  4997.3  140.76  5011.3  141.57
 5021.46 144.272  5060.9  146.72  5067.3  145.43  5202.9  147.68    5345  145.97
  5359.3  147.45  5365.8  146.14  5402.4  146.58  5408.8  145.12  5423.2  147.12
  5429.7  144.35  5437.5  145.93    5444  144.36  5451.9  146.29  5471.5  145.09
#Mann= 3 , 0 , 0
    4616     .05       0  4989.1     .07       0 5021.46     .05       0
Bank Sta=4989.1,5021.46
XS Rating Curve= 0 ,0
Exp/Cntr=0.3,0.1

Type RM Length L Ch R = 1 ,8188    ,413,413,413
BEGIN DESCRIPTION:
CRYSTAL CREEK TRIBUTARY NO 10 16.75
END DESCRIPTION:
XS GIS Cut Line= 3
      3863522.94     10082925.04      3863218.24     10083176.86
      3862870.24     10083467.19
#Sta/Elev= 30
  4604.7   146.6  4623.8  146.87    4710  146.47  4771.4  146.39  4811.4  148.31
  4842.1  146.57  4846.5  147.65  4854.4  145.13  4860.9  147.92  4868.7  146.17
  4889.6  147.95    4919  145.51  4967.7  147.31 4989.71 143.379  4994.5  138.72
  4998.3  138.72  4999.4  141.56 5012.15 143.439  5017.2  146.99  5045.8  147.71
  5074.5  146.02  5123.9  148.28  5138.2   146.4    5202  148.48  5294.4  147.13
    5422  149.16  5429.8  147.56  5436.3  149.31  5450.6  146.27  5453.2  148.78
#Mann= 8 ,-1 , 0
  4604.7     .12       0  4623.8     .05       0    4710     .12       0
  4771.4     .05       0  4842.1     .12       0    4919     .05       0
 4989.71     .07       0 5012.15     .05       0
Bank Sta=4989.71,5012.15
XS Rating Curve= 0 ,0
Exp/Cntr=0.3,0.1

Type RM Length L Ch R = 1 ,7775    ,494,494,494
BEGIN DESCRIPTION:
CRYSTAL CREEK TRIBUTARY NO 10 15.0
END DESCRIPTION:
XS GIS Cut Line= 3
      3863167.83     10082711.09      3862888.24     10082996.86
      3862717.85     10083361.08
#Sta/Elev= 30
  4600.2  150.82  4621.4  151.25  4629.4  150.28  4741.5  148.16  4769.8  146.18
    4784  146.83  4847.7  145.85  4914.8  142.95  4939.6  141.28  4946.7  141.88
  4953.7  139.68  4960.9  141.11  4967.9  138.26    4975  137.78    4982   134.9
  4989.2   135.1  4994.2   129.4  4998.1   129.4  4999.4  131.68  5005.1  131.68
  5010.5  135.22    5017  139.32  5039.8  143.58  5070.9  144.43    5093  146.29
  5108.3  145.57  5192.3  148.65  5216.2  148.67  5365.1  148.59  5402.1  150.11
#Mann= 6 ,-1 , 0
  4600.2     .12       0  4629.4     .05       0  4914.8     .12       0
  4989.2     .07       0  5010.5     .12       0  5216.2     .05       0
Bank Sta=4989.2,5010.5
XS Rating Curve= 0 ,0
Exp/Cntr=0.3,0.1

Type RM Length L Ch R = 1 ,7281    ,462,462,462
BEGIN DESCRIPTION:
CRYSTAL CREEK TRIBUTARY NO 10 14.0
END DESCRIPTION:
XS GIS Cut Line= 3
       3862840.2     10082536.06      3862528.24     10082756.86
      3862056.36     10082952.71
#Sta/Elev= 30
  4617.8  151.43  4629.7   151.2  4681.4  149.68  4687.6  150.38  4708.5  147.49
  4723.2  148.84    4738  147.35  4811.8  144.62  4931.2  143.47  4966.9  140.04
    4981  136.46 4984.26 135.061  4988.2   133.2  4994.4   127.9  4998.6   127.9
  5011.2  130.48 5018.73 135.106  5025.8  138.68  5032.9  140.68  5078.9   143.2
  5097.4  145.36  5102.8  144.65  5126.6   146.4  5203.7  148.07  5378.1  148.18
  5440.2  147.23  5469.4  149.99  5487.6   149.8  5498.7  151.35  5510.9  150.67
#Mann= 7 ,-1 , 0
  4617.8     .12       0  4629.7     .05       0  4811.8     .12       0
    4981     .05       0 4984.26     .07       0 5018.73     .05       0
  5378.1     .12       0
Bank Sta=4984.26,5018.73
XS Rating Curve= 0 ,0
Exp/Cntr=0.3,0.1

Type RM Length L Ch R = 1 ,6819    ,477,477,477
BEGIN DESCRIPTION:
CRYSTAL CREEK TRIBUTARY NO 10 13.0
END DESCRIPTION:
XS GIS Cut Line= 3
      3862610.42     10082278.09      3862348.24     10082406.86
      3861998.46     10082705.16
#Sta/Elev= 30
  4707.9  148.21  4743.6     148  4799.9  145.95    4811  146.54  4816.7  145.49
  4833.3  146.07  4844.7  143.73  4855.6  142.86  4889.7     143  4929.1  140.99
  4934.7  141.85  4957.1  141.58    4967   140.7  4989.3  133.57  4996.5  128.35
  4996.6  127.47    4997  126.97  5010.6   128.7  5017.2  130.85 5021.17 133.299
  5024.9   135.6  5031.5   137.7  5039.2  138.99  5123.7  142.69  5287.3  145.63
  5308.2  144.71    5351  146.77  5365.3   146.3  5407.9  147.66  5459.7  147.77
#Mann= 3 , 0 , 0
  4707.9     .12       0  4989.3     .07       0 5021.17     .12       0
Bank Sta=4989.3,5021.17
XS Rating Curve= 0 ,0
Exp/Cntr=0.3,0.1

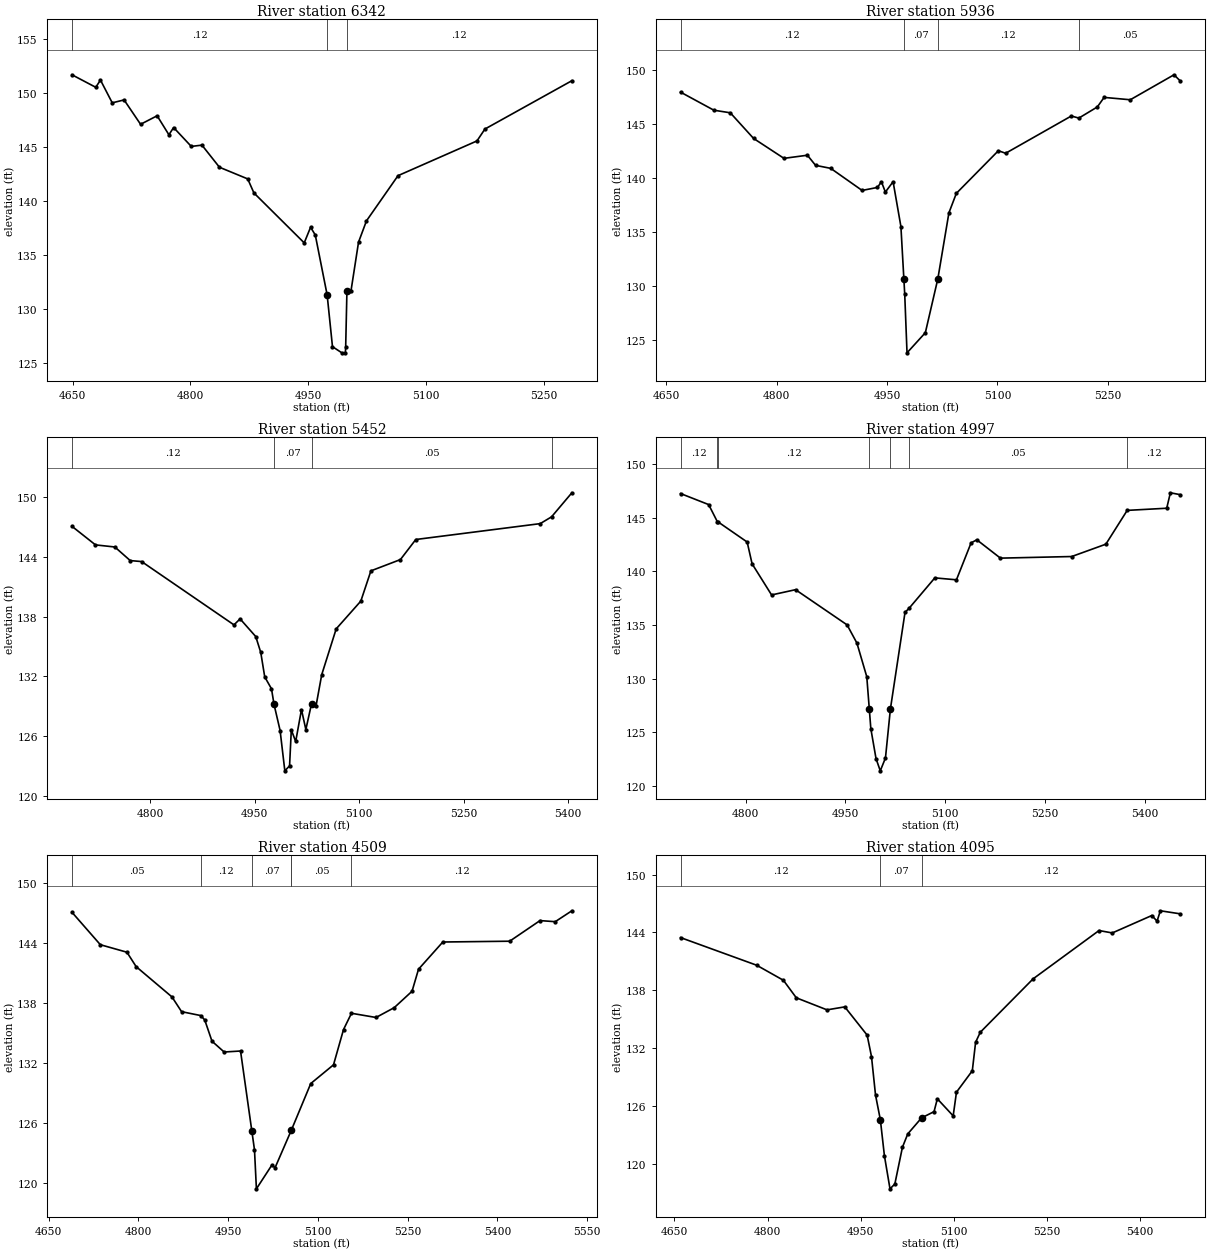
Type RM Length L Ch R = 1 ,6342    ,406,406,406
BEGIN DESCRIPTION:
CRYSTAL CREEK TRIBUTARY NO 10 12.0
END DESCRIPTION:
XS GIS Cut Line= 3
       3862131.9     10081994.37      3861938.24     10082286.86
      3861906.64     10082571.21
#Sta/Elev= 30
  4649.2  151.71  4679.5  150.55  4685.5  151.22  4700.5  149.11  4715.6  149.38
  4736.6  147.12  4757.7  147.91  4772.7  146.15  4778.7  146.82  4801.2  145.07
  4814.8  145.19  4837.1  143.14  4873.1  142.06    4881  140.76  4945.1  136.13
  4953.2  137.58  4959.2  136.86  4974.3  131.31  4981.1  126.51  4993.1  125.94
  4997.5  125.94  4997.9  126.44  4999.5  131.64  5004.6  131.64  5014.3   136.2
  5024.4  138.17  5064.6  142.36  5165.2  145.58  5175.3  146.68  5286.1  151.16
#Mann= 3 , 0 , 0
  4649.2     .12       0  4974.3     .07       0  4999.5     .12       0
Bank Sta=4974.3,4999.5
XS Rating Curve= 0 ,0
Exp/Cntr=0.3,0.1

Type RM Length L Ch R = 1 ,5936    ,484,484,484
BEGIN DESCRIPTION:
CRYSTAL CREEK TRIBUTARY NO 10 11.0
END DESCRIPTION:
XS GIS Cut Line= 3
      3861808.32     10081746.89      3861704.75     10082060.64
      3861547.91     10082371.85
#Sta/Elev= 30
  4669.6  147.99  4714.9  146.31  4737.2  146.07  4768.8  143.69  4810.1  141.84
  4841.9  142.13    4853  141.19  4873.6  140.91  4916.2  138.86  4937.1  139.14
  4942.4  139.67  4947.8  138.71  4958.3  139.67  4968.9  135.51 4972.89 130.676
  4974.1  129.21  4977.2  123.78  5002.1  125.65 5019.08 130.661  5034.1  136.78
  5044.2  138.59  5101.3  142.55  5111.1  142.31  5200.3  145.77  5210.6  145.58
  5235.6  146.61  5244.9   147.5  5280.4  147.28  5339.8   149.6  5348.5  149.01
#Mann= 4 ,-1 , 0
  4669.6     .12       0 4972.89     .07       0 5019.08     .12       0
  5210.6     .05       0
Bank Sta=4972.89,5019.08
XS Rating Curve= 0 ,0
Exp/Cntr=0.3,0.1

Type RM Length L Ch R = 1 ,5452    ,455,455,455
BEGIN DESCRIPTION:
CRYSTAL CREEK TRIBUTARY NO 10 10.0
END DESCRIPTION:
XS GIS Cut Line= 3
      3861508.87     10081496.81      3861364.48     10081774.18
       3861119.1     10082097.26
#Sta/Elev= 30
  4687.3  147.04  4721.1  145.18  4748.9  144.97    4771  143.61  4787.4  143.51
  4920.1  137.17  4928.9  137.77  4951.4     136  4958.6  134.41  4964.3  131.96
    4974  130.77  4977.7 129.196  4986.4  126.59  4993.2  122.55    5000  123.05
  5002.5  126.65  5008.8  125.49  5017.1  128.68  5023.4  126.69  5031.6  129.28
  5037.9     129  5046.2  132.18    5067  136.77  5102.4  139.55  5116.9  142.58
  5159.3  143.71  5181.4  145.72  5360.2  147.31  5376.5  147.99  5405.7   150.4
#Mann= 4 ,-1 , 0
  4687.3     .12       0  4977.7     .07       0  5031.6     .05       0
  5376.5     .12       0
Bank Sta=4977.7,5031.6
XS Rating Curve= 0 ,0
Exp/Cntr=0.3,0.1

Type RM Length L Ch R = 1 ,4997    ,488,488,488
BEGIN DESCRIPTION:
CRYSTAL CREEK TRIBUTARY NO 10 9.0
END DESCRIPTION:
XS GIS Cut Line= 3
      3861279.65     10081343.22      3861036.43     10081515.05
      3860844.88     10081926.34
#Sta/Elev= 30
  4702.2  147.25  4744.5  146.22  4757.6  144.62  4758.3  144.62  4802.4  142.73
  4809.8   140.7  4839.1   137.8  4875.1  138.29  4952.6  135.01  4967.4  133.31
  4982.2  130.18 4986.03 127.141  4988.3  125.34  4996.1  122.55  5002.5  121.41
  5010.3  122.61  5017.7  127.17  5039.7  136.18  5045.7  136.55  5084.5  139.39
    5117  139.21    5139  142.65  5147.6  142.94  5183.1  141.23  5290.3  141.38
  5341.6  142.53  5373.7  145.68  5433.1  145.88  5438.6  147.32  5453.7  147.14
#Mann= 7 ,-1 , 0
  4702.2     .12       0  4757.6     .05       0  4758.3     .12       0
 4986.03     .07       0  5017.7     .12       0  5045.7     .05       0
  5373.7     .12       0
Bank Sta=4986.03,5017.7
XS Rating Curve= 0 ,0
Exp/Cntr=0.3,0.1

Type RM Length L Ch R = 1 ,4509    ,414,414,414
BEGIN DESCRIPTION:
CRYSTAL CREEK TRIBUTARY NO 10 8.0
END DESCRIPTION:
XS GIS Cut Line= 3
      3860691.14      10081090.6      3860638.24     10081396.86
       3860727.6     10081913.49
#Sta/Elev= 30
  4689.2  147.04  4736.6   143.8    4781  143.05  4796.4  141.61  4856.3  138.58
  4872.3  137.11  4904.4  136.72    4911  136.28  4923.1  134.16  4943.4  133.08
  4970.8  133.18 4989.66 125.191  4994.1  123.31  4997.3  119.41  5023.3   121.8
  5028.4  121.51  5055.6  125.26  5088.1  129.93  5126.1   131.8  5142.8  135.32
  5156.1  136.95  5197.1  136.53  5227.5  137.51  5257.3  139.15  5268.1  141.35
  5308.7  144.07  5420.4  144.15  5471.1  146.21  5496.5   146.1  5524.3  147.19
#Mann= 6 ,-1 , 0
  4689.2     .05       0  4904.4     .12       0 4989.66     .07       0
  5055.6     .12       0  5055.6     .05       0  5156.1     .12       0
Bank Sta=4989.66,5055.6
XS Rating Curve= 0 ,0
Exp/Cntr=0.3,0.1

Type RM Length L Ch R = 1 ,4095    ,485,485,485
BEGIN DESCRIPTION:
CRYSTAL CREEK TRIBUTARY NO 10 7.0
END DESCRIPTION:
XS GIS Cut Line= 3
      3860107.77     10081218.17      3860368.24     10081436.86
      3860524.46     10081874.41
#Sta/Elev= 30
  4659.9  143.47  4782.5   140.6  4825.5  139.04  4846.3  137.22  4895.7  135.97
  4924.3  136.28  4960.3  133.35  4967.3  131.13  4973.8  127.13  4981.6  124.56
  4988.1  120.84  4997.1   117.4  5004.9   117.9  5017.1  121.71  5025.7   123.1
  5047.9  124.76    5068  125.41  5073.3  126.74  5098.8  124.97  5104.1  127.43
  5129.6  129.65  5134.9  132.61  5142.5  133.65  5227.5  139.19  5333.6   144.2
  5354.9  143.95  5418.6  145.76    5427  145.17  5432.3  146.25  5464.6  145.93
#Mann= 3 , 0 , 0
  4659.9     .12       0  4981.6     .07       0  5047.9     .12       0
Bank Sta=4981.6,5047.9
XS Rating Curve= 0 ,0
Exp/Cntr=0.3,0.1