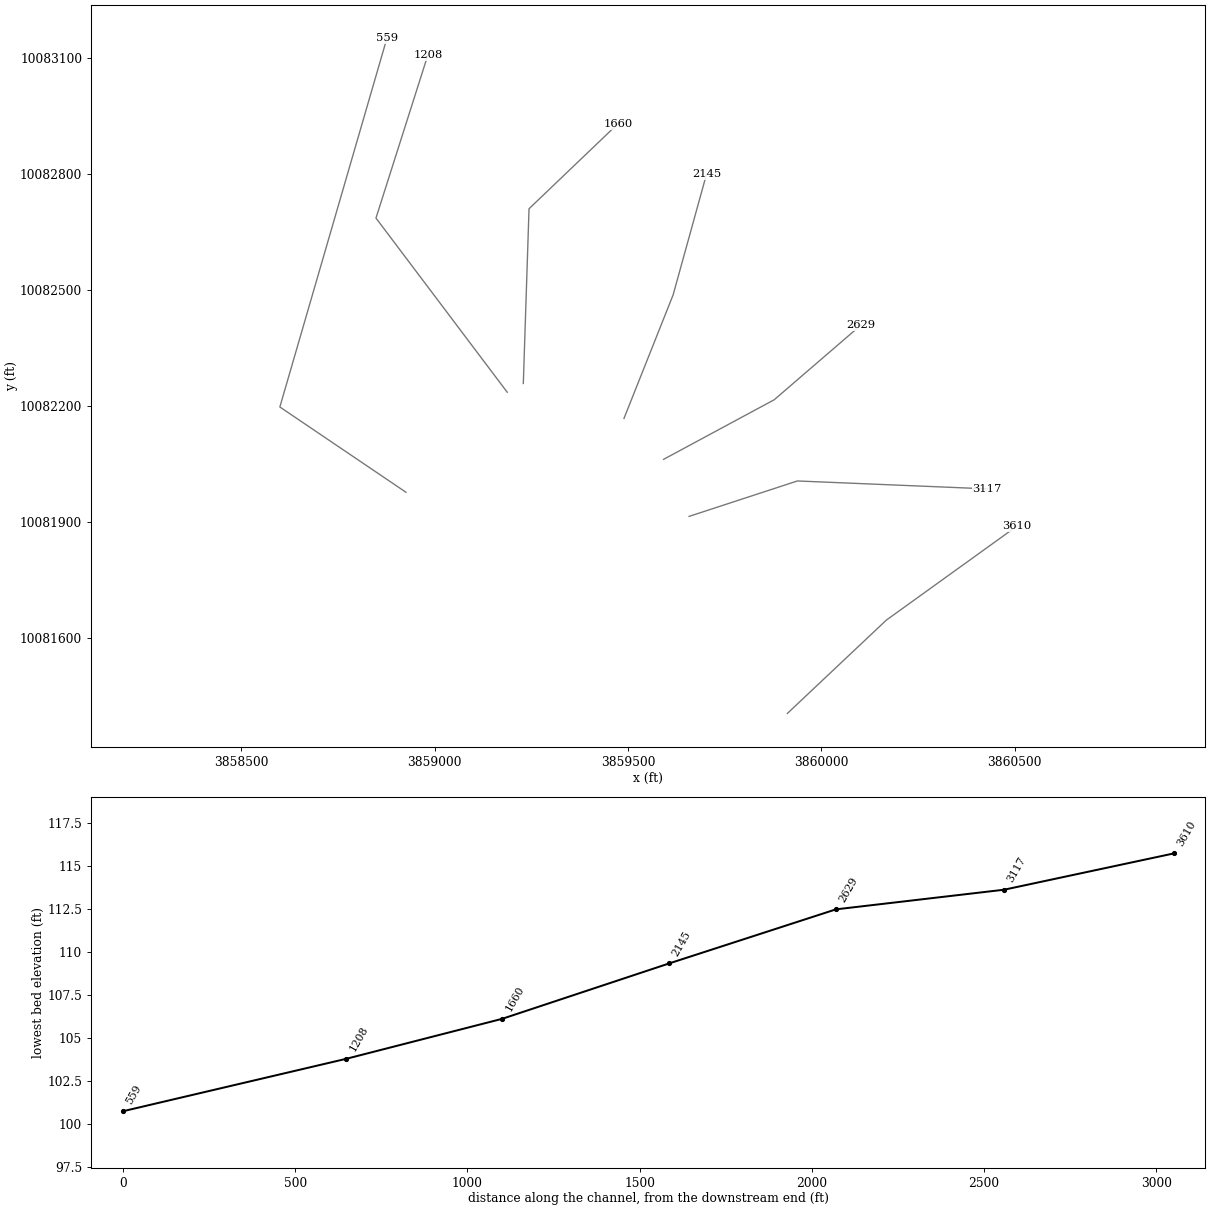
HEC-RAS study CRYSTAL CREEK TRIBUTARY NO 10.prj: CRYSTAL CREEK TRIBUTARY NO 10 Base Level Engineering

--- CRYSTAL CREEK TRIBUTARY NO 10.g10 (geometry) --- (continued)

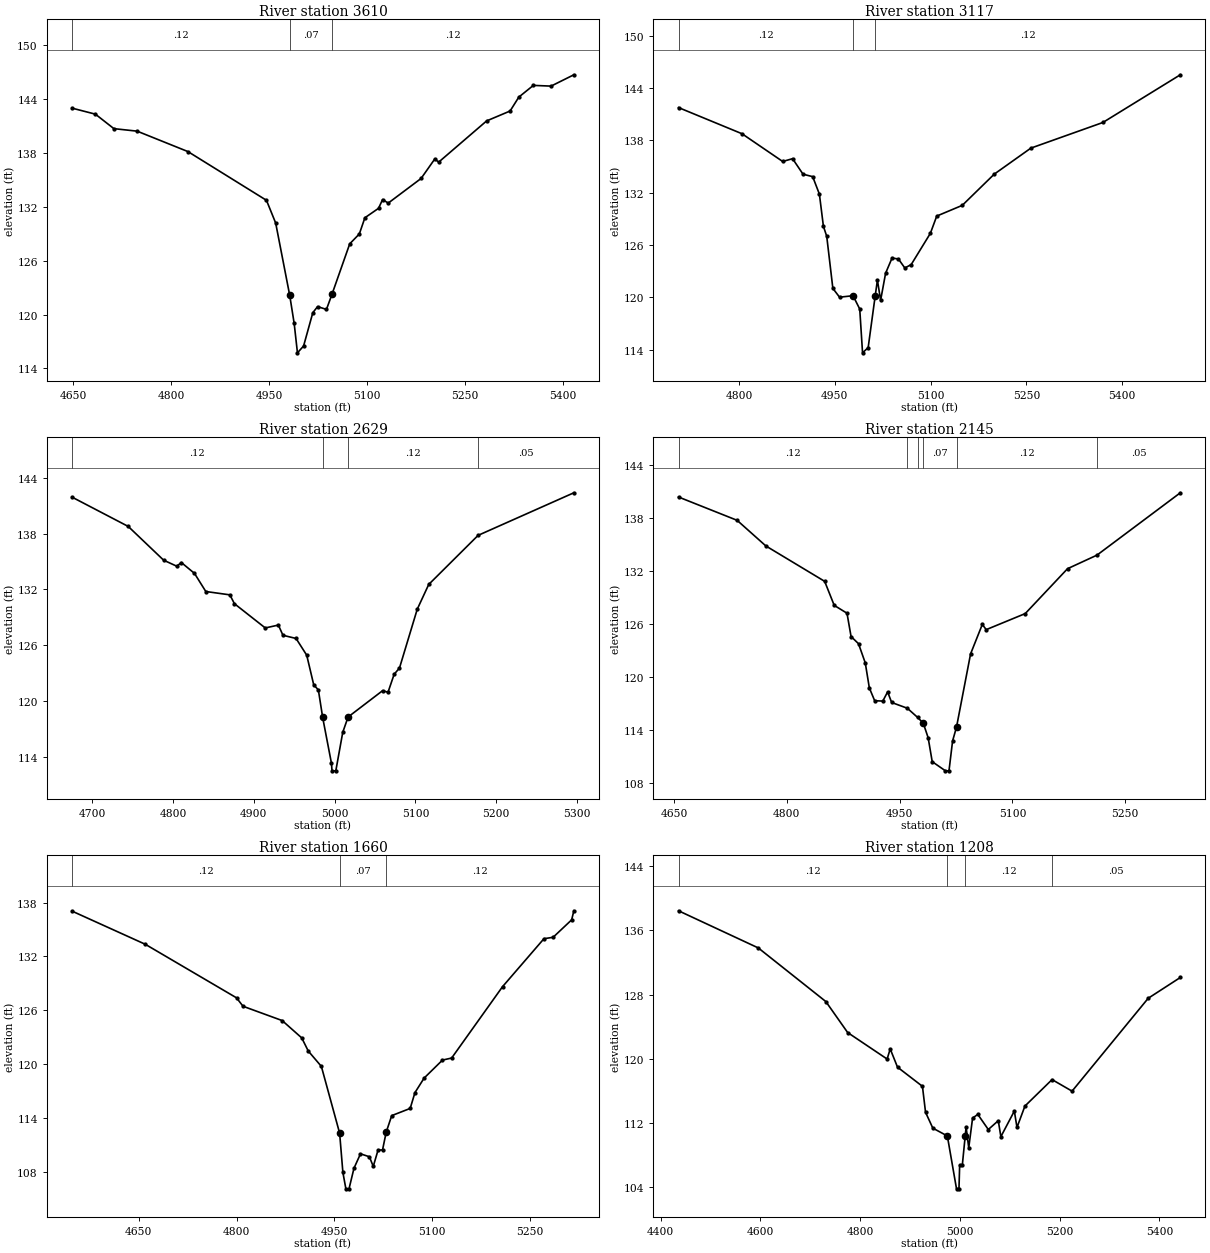
Type RM Length L Ch R = 1 ,3610    ,493,493,493
BEGIN DESCRIPTION:
CRYSTAL CREEK TRIBUTARY NO 10 6.0
END DESCRIPTION:
XS GIS Cut Line= 3
      3859912.51     10081405.71      3860168.24     10081646.86
      3860506.23     10081890.06
#Sta/Elev= 30
  4648.5  142.95  4684.2  142.28  4712.5  140.67  4748.1  140.39  4825.8  138.12
    4946   132.7  4960.1  130.17  4981.6  122.12  4988.4  119.01  4993.4  115.74
  5002.8   116.5  5016.9   120.2  5024.2  120.88  5037.8  120.57  5046.3  122.26
  5073.4  127.86  5088.1  128.96  5096.6  130.76  5117.5  131.81  5123.7  132.79
  5132.3  132.39  5182.6  135.13  5203.5  137.29  5209.6  136.95  5282.9  141.53
  5318.8  142.63  5332.2  144.18  5354.4  145.48  5381.5   145.4  5416.4  146.66
#Mann= 3 , 0 , 0
  4648.5     .12       0  4981.6     .07       0  5046.3     .12       0
Bank Sta=4981.6,5046.3
XS Rating Curve= 0 ,0
Exp/Cntr=0.3,0.1

Type RM Length L Ch R = 1 ,3117    ,488,488,488
BEGIN DESCRIPTION:
CRYSTAL CREEK TRIBUTARY NO 10 5.0
END DESCRIPTION:
XS GIS Cut Line= 3
      3859658.14     10081915.24      3859938.24     10082006.86
      3860429.01     10081986.43
#Sta/Elev= 30
  4705.3  141.75  4804.7  138.75  4868.4  135.57  4883.9  135.89  4900.3  134.11
  4915.4  133.83  4925.9  131.83  4932.2  128.14  4937.4  126.99    4947  121.02
  4957.5  120.01  4978.6  120.18  4989.1  118.65  4993.5  113.63  5002.3  114.23
 5013.34 120.178  5016.8  121.97  5021.8  119.65  5029.6  122.76  5039.7   124.5
  5049.7  124.39  5059.7  123.36  5069.7  123.75  5099.7  127.33  5109.7  129.31
  5149.7  130.54  5199.8  134.12  5257.1   137.1  5369.9  140.04  5491.2  145.51
#Mann= 3 , 0 , 0
  4705.3     .12       0  4978.6     .07       0 5013.34     .12       0
Bank Sta=4978.6,5013.34
XS Rating Curve= 0 ,0
Exp/Cntr=0.3,0.1

Type RM Length L Ch R = 1 ,2629    ,484,484,484
BEGIN DESCRIPTION:
CRYSTAL CREEK TRIBUTARY NO 10 4.0
END DESCRIPTION:
XS GIS Cut Line= 3
      3859592.18     10082062.81      3859878.24     10082216.86
      3860102.63     10082410.06
#Sta/Elev= 30
  4675.1  141.93  4744.6  138.78  4788.4  135.15  4804.7   134.5  4810.3   134.9
  4826.6  133.73  4840.6  131.78  4870.4  131.42    4876  130.47  4914.2  127.86
  4930.4  128.17  4936.1  127.07  4952.3  126.73  4965.5  124.93  4974.2  121.73
  4979.9   121.2 4985.24 118.228  4996.1  113.31  4996.8  112.49  5001.5  112.49
  5010.1  116.64  5016.7  118.28  5059.5  121.12  5066.1  120.94  5073.7  122.88
  5080.3  123.55  5102.3  129.88  5116.5  132.54  5177.6  137.82  5296.1   142.4
#Mann= 4 ,-1 , 0
  4675.1     .12       0 4985.24     .07       0  5016.7     .12       0
  5177.6     .05       0
Bank Sta=4985.24,5016.7
XS Rating Curve= 0 ,0
Exp/Cntr=0.3,0.1

Type RM Length L Ch R = 1 ,2145    ,485,485,485
BEGIN DESCRIPTION:
CRYSTAL CREEK TRIBUTARY NO 10 3.0
END DESCRIPTION:
XS GIS Cut Line= 3
      3859489.75      10082168.7      3859616.85     10082488.25
      3859703.07     10082799.84
#Sta/Elev= 30
  4656.1  140.36    4734  137.72  4772.2  134.82  4850.4  130.81  4863.1  128.09
  4880.1   127.2  4885.5  124.56  4895.4  123.75  4904.4  121.57  4909.8  118.74
  4916.9  117.29  4927.7  117.25  4934.1  118.29  4939.5  117.09  4960.3  116.44
    4974   115.4  4981.5  114.75    4988   113.1  4993.4  110.39    5011  109.35
  5015.7  109.35  5020.5  112.74  5025.7   114.3  5044.4  122.59    5060  125.93
  5065.2  125.34  5117.1  127.16  5173.3  132.24  5212.5  133.78  5323.3  140.84
#Mann= 6 ,-1 , 0
  4656.1     .12       0  4960.3     .05       0    4974     .12       0
  4981.5     .07       0  5025.7     .12       0  5212.5     .05       0
Bank Sta=4981.5,5025.7
XS Rating Curve= 0 ,0
Exp/Cntr=0.3,0.1

Type RM Length L Ch R = 1 ,1660    ,452,452,452
BEGIN DESCRIPTION:
CRYSTAL CREEK TRIBUTARY NO 10 2.0
END DESCRIPTION:
XS GIS Cut Line= 3
      3859229.34     10082259.02      3859244.12     10082710.98
      3859473.47     10082930.24
#Sta/Elev= 30
  4547.8  137.04  4660.1  133.35    4800  127.39    4810  126.45    4870  124.86
    4900  122.93    4910  121.47  4930.1  119.76  4958.1  112.33  4963.1  107.96
  4967.7  106.13  4972.5  106.13  4980.1  108.42  4990.1  110.03  5003.7   109.7
  5009.7  108.63    5017  110.44  5023.9  110.46 5029.57 112.452    5038  114.28
  5066.3  115.08  5073.6  116.84  5087.7  118.46  5115.8  120.46  5129.9  120.69
  5207.9  128.63  5271.4  133.97  5285.5  134.13  5313.9  136.07  5317.3  137.08
#Mann= 3 , 0 , 0
  4547.8     .12       0  4958.1     .07       0 5029.57     .12       0
Bank Sta=4958.1,5029.57
XS Rating Curve= 0 ,0
Exp/Cntr=0.3,0.1

Type RM Length L Ch R = 1 ,1208    ,649,649,649
BEGIN DESCRIPTION:
CRYSTAL CREEK TRIBUTARY NO 10 1.0
END DESCRIPTION:
XS GIS Cut Line= 3
      3859187.67     10082236.44      3858848.24     10082686.86
      3858982.23     10083107.85
#Sta/Elev= 30
    4436  138.45  4595.9  133.82  4731.3  127.14    4775  123.28  4854.1  119.98
  4860.3  121.24  4874.9  118.97  4924.9  116.58  4931.1  113.35  4945.7  111.37
  4974.8   110.4  4993.2  103.81  4998.1  103.81  4999.5  106.75  5004.8  106.75
 5010.65 110.422  5012.4  111.52  5017.7  108.92  5025.4  112.63  5035.9  113.08
  5056.9   111.2  5076.9   112.3  5082.1  110.31  5109.1   113.5  5114.4  111.46
  5130.3  114.12  5184.7  117.42  5224.8  115.98  5377.4  127.55  5441.8  130.14
#Mann= 4 ,-1 , 0
    4436     .12       0  4974.8     .07       0 5010.65     .12       0
  5184.7     .05       0
Bank Sta=4974.8,5010.65
XS Rating Curve= 0 ,0
Exp/Cntr=0.3,0.1

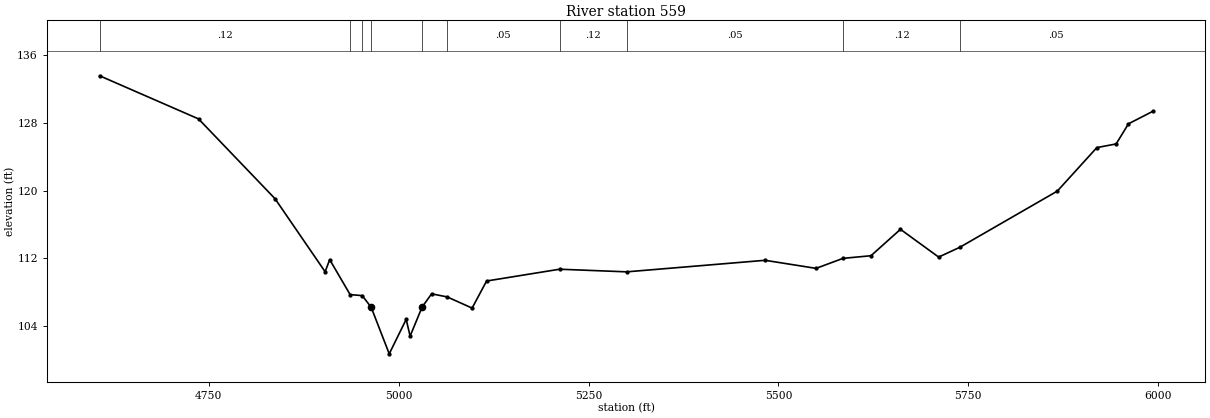
Type RM Length L Ch R = 1 ,559     ,0,0,0
BEGIN DESCRIPTION:
CRYSTAL CREEK TRIBUTARY NO 10 1.5
END DESCRIPTION:
XS GIS Cut Line= 3
      3858925.74      10081977.7      3858599.61     10082198.24
      3858876.45     10083151.76
#Sta/Elev= 30
  4606.3  133.52  4736.5  128.44  4837.3  119.03  4903.2  110.43  4909.2  111.86
  4936.1  107.74    4952  107.62 4963.82 106.249  4987.6  100.76  5009.9  104.82
  5015.1  102.85 5030.92 106.282  5043.4  107.83  5063.8  107.47  5096.7  106.15
  5115.8  109.34  5211.9  110.73  5300.2  110.42  5482.5  111.78  5549.6  110.83
  5585.1  112.01  5621.9  112.32  5660.7  115.43    5711  112.16    5739  113.32
  5867.2  119.93  5919.3  125.06  5944.7  125.49  5960.9  127.86  5992.9  129.33
#Mann= 10 ,-1 , 0
  4606.3     .12       0  4936.1     .05       0    4952      .1       0
 4963.82     .07       0 5030.92      .1       0  5063.8     .05       0
  5211.9     .12       0  5300.2     .05       0  5585.1     .12       0
    5739     .05       0
Bank Sta=4963.82,5030.92
XS Rating Curve= 0 ,0
Exp/Cntr=0.3,0.1