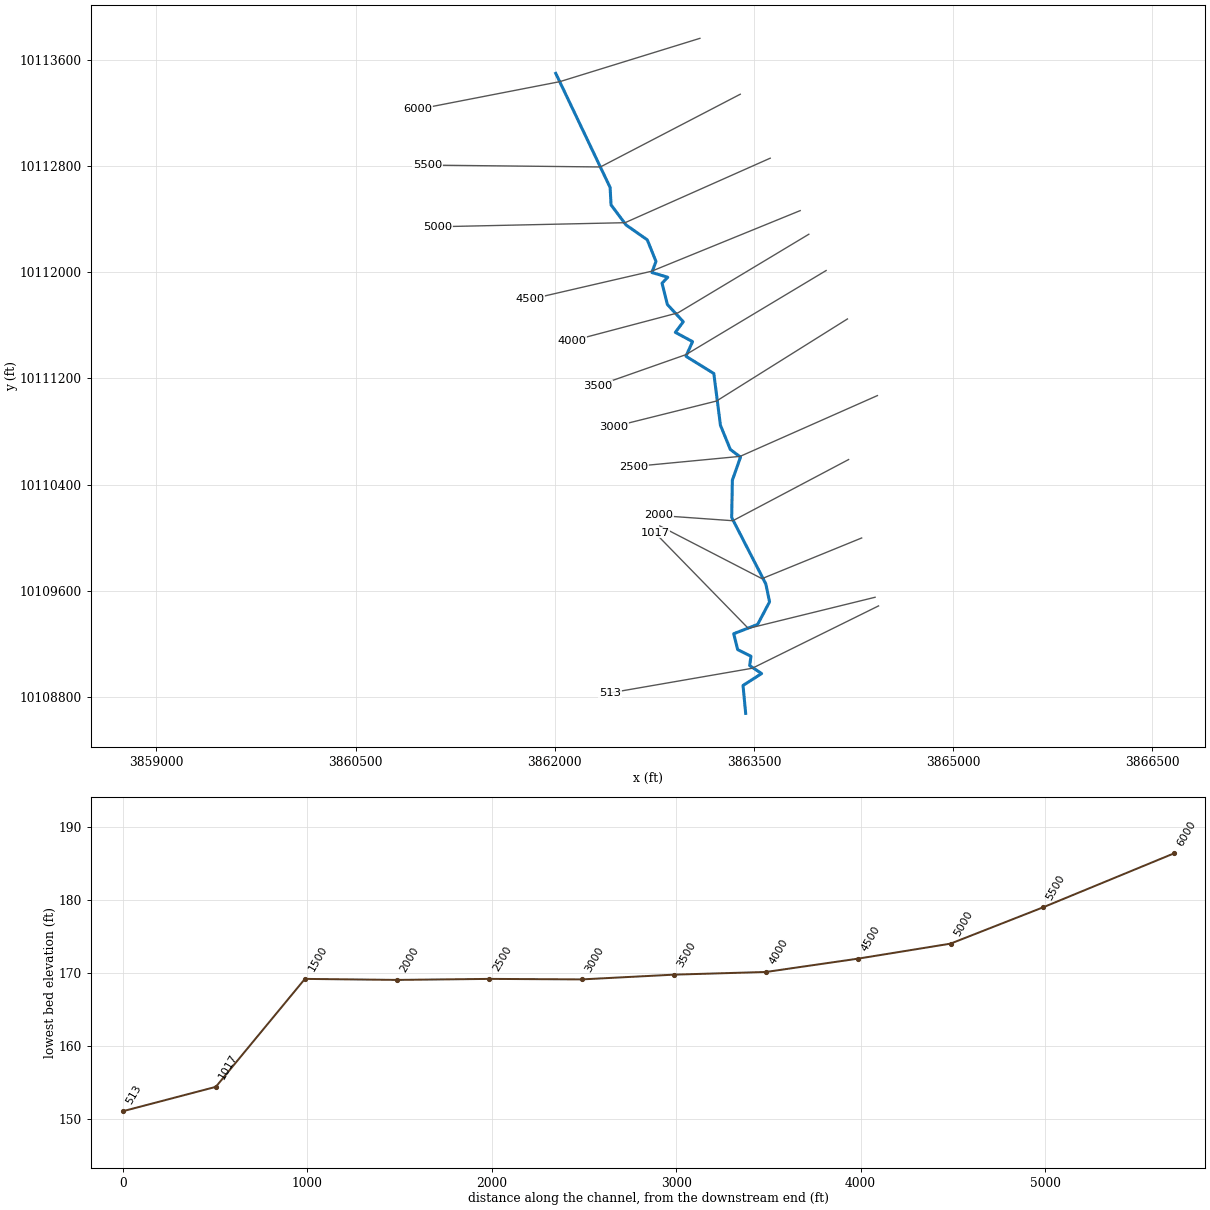
--- CRYSTAL CREEK TRIBUTARY NO 2.prj (project) ---

Proj Title=CRYSTAL CREEK TRIBUTARY NO 2 Base Level Engineering
Current Plan=p01
Default Exp/Contr=0.3,0.1
English Units
Geom File=g01
Flow File=f01
Plan File=p01
Y Axis Title=Elevation
X Axis Title(PF)=Main Channel Distance
X Axis Title(XS)=Station
BEGIN DESCRIPTION:
CRYSTAL CREEK TRIBUTARY NO 2
END DESCRIPTION:
DSS Export Rating Curves= 0
DSS Export Rating Curve Sorted= 0
DSS Export Volume Flow Curves= 0
DXF OffsetX= 0
DXF OffsetY= 0
DXF ScaleX= 1
DXF ScaleY= 10

--- CRYSTAL CREEK TRIBUTARY NO 2.p01 (plan) ---

Plan Title=Multiple Run
Short Identifier=Multiple
Geom File=g01
Flow File=f01
Subcritical Flow
K Sum by GR= 0
Std Step Tol= 0.01
Critical Tol= 0.01
Num of Std Step Trials= 20
Max Error Tol= 0.3
Flow Tol Ratio= 0.001
Split Flow NTrial= 30
Split Flow Tol= 0.02
Split Flow Ratio= 0.02
Log Output Level= 0
Friction Slope Method= 1
Unsteady Friction Slope Method= 2
Unsteady Bridges Friction Slope Method= 1
Parabolic Critical Depth
Global Vel Dist=  1 , 1 , 1
Global Log Level= 0
CheckData=True
Encroach Param= -1, 0, 0, 0
BEGIN DESCRIPTION:
Multiple Run
END DESCRIPTION:

--- CRYSTAL CREEK TRIBUTARY NO 2.f01 (steady flow) ---

Flow Title=Multiple
Program Version=4.10
Number of Profiles= 7
Profile Names=10-year,25-year,50-year,1pct_min,100-year,1pct_plu,500-year
River Rch & RM=CRYSTAL CREEK TR,Reach-1         ,6000
     497     654     867     379    1145    3458    2057
River Rch & RM=CRYSTAL CREEK TR,Reach-1         ,513
    2368    3328    4609    2087    6304   19038   12202
Boundary for River Rch & Prof#=CRYSTAL CREEK TR,Reach-1         , 1
Up Type= 0
Dn Type= 3
Dn Slope=0.005
Boundary for River Rch & Prof#=CRYSTAL CREEK TR,Reach-1         , 2
Up Type= 0
Dn Type= 3
Dn Slope=0.005
Boundary for River Rch & Prof#=CRYSTAL CREEK TR,Reach-1         , 3
Up Type= 0
Dn Type= 3
Dn Slope=0.005
Boundary for River Rch & Prof#=CRYSTAL CREEK TR,Reach-1         , 4
Up Type= 0
Dn Type= 3
Dn Slope=0.005
Boundary for River Rch & Prof#=CRYSTAL CREEK TR,Reach-1         , 5
Up Type= 0
Dn Type= 3
Dn Slope=0.005
Boundary for River Rch & Prof#=CRYSTAL CREEK TR,Reach-1         , 6
Up Type= 0
Dn Type= 3
Dn Slope=0.005
Boundary for River Rch & Prof#=CRYSTAL CREEK TR,Reach-1         , 7
Up Type= 0
Dn Type= 3
Dn Slope=0.005
DSS Import GetInterval= 0
DSS Import GetPeak= 0
DSS Import FillOption= 0

--- CRYSTAL CREEK TRIBUTARY NO 2.g01 (geometry) ---

Geom Title=Existing Conditions
Program Version=4.10

River Reach=CRYSTAL CREEK TR,Reach-1
Reach XY= 30
      3862007.54     10113497.89       3862417.1     10112638.37
      3862424.22     10112506.94      3862536.66     10112356.28
      3862697.15     10112243.57      3862762.61      10112081.1
      3862731.97     10111997.69      3862851.13     10111961.94
      3862808.24     10111916.86      3862848.24     10111756.86
      3862968.24     10111626.86      3862908.24     10111546.86
      3863038.24     10111476.86      3862988.24     10111366.86
      3863198.24     10111236.86      3863248.24     10110846.86
      3863322.65     10110664.83      3863399.25     10110606.95
      3863337.97     10110433.32      3863332.86     10110152.45
       3863589.9     10109651.99      3863618.24     10109516.86
      3863528.24     10109346.86      3863348.24     10109276.86
      3863378.24     10109156.86      3863478.24     10109106.86
      3863468.24     10109036.86      3863558.24     10108976.86
      3863418.24     10108886.86      3863438.24     10108676.86

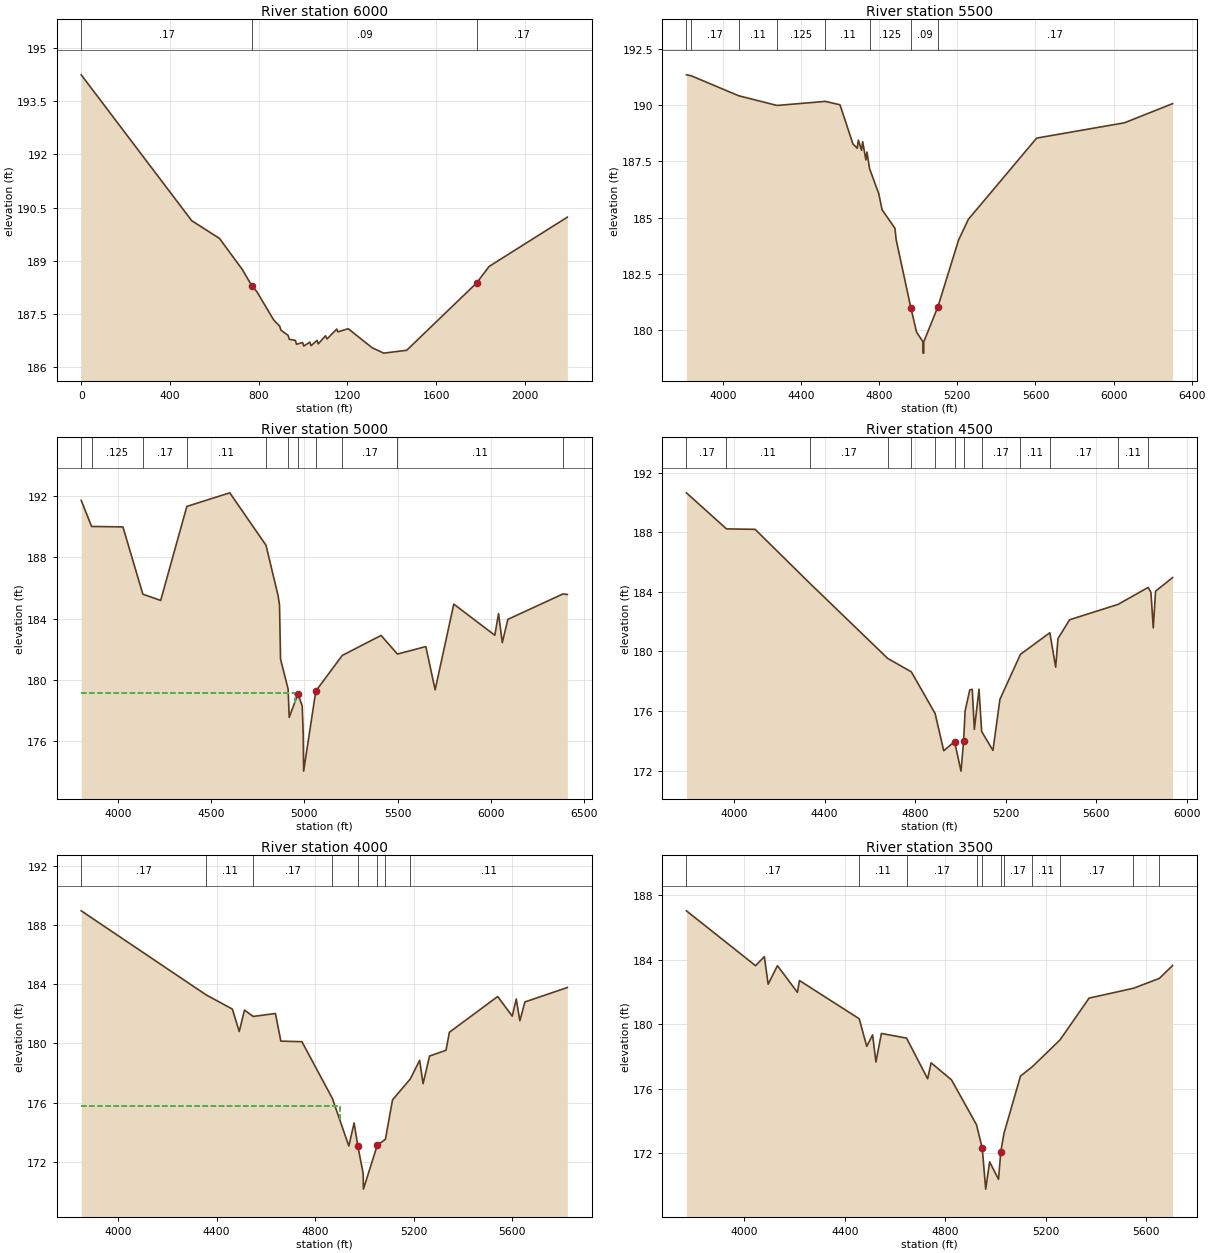
Type RM Length L Ch R = 1 ,6000    ,711,711,711
XS GIS Cut Line= 3
      3863093.61     10113761.53      3862037.53     10113435.01
      3860971.21     10113227.68
#Sta/Elev= 30
       0  194.25     498  190.13   623.1  189.63   726.2  188.75   770.1  188.28
   791.1  188.13   867.2  187.33   894.6  187.15   899.8  187.04   932.5  186.89
   937.7  186.78   965.1  186.75   970.3  186.64   997.7  186.69  1002.9  186.59
  1030.3   186.7  1035.6   186.6    1063  186.75  1068.2  186.65  1100.8  186.88
  1107.8  186.79  1151.6  187.07  1156.7  186.99  1203.2  187.08  1311.7  186.54
  1363.3  186.39  1466.7  186.47  1781.7  188.37  1838.6  188.84  2190.9  190.23
#Mann= 3 , 0 , 0
       0     .17       0   770.1     .09       0  1781.7     .17       0
Bank Sta=770.1,1781.7
XS Rating Curve= 0 ,0
Exp/Cntr=0.3,0.1

Type RM Length L Ch R = 1 ,5500    ,500,500,500
BEGIN DESCRIPTION:
CRYSTAL CREEK TRIBUTARY NO 2 11.0
END DESCRIPTION:
XS GIS Cut Line= 3
      3863397.44     10113340.53        3862344.     10112792.65
      3861041.77     10112806.66
#Sta/Elev= 30
  3812.6  191.34  3836.6   191.3  4080.2  190.41  4276.6  189.98    4524  190.16
    4599  190.01  4665.3  188.27  4687.4  188.08  4693.1  188.44  4709.5  187.99
  4715.2  188.37  4731.6  187.56  4737.3  187.91  4750.3  187.18    4798  186.05
  4814.4  185.35  4880.8  184.52  4886.4  184.03  4961.8     181  4991.3  179.91
  5024.1  179.48  5024.4  178.98  5027.9  178.98  5028.1  179.48 5100.75181.0474
  5206.2     184  5256.2  184.92  5606.2  188.53  6056.2  189.21  6302.3  190.06
#Mann= 8 ,-1 , 0
  3812.6     .11       0  3836.6     .17       0  4080.2     .11       0
  4276.6    .125       0    4524     .11       0  4750.3    .125       0
  4961.8     .09       0 5100.75     .17       0
Bank Sta=4961.8,5100.75
XS Rating Curve= 0 ,0
Exp/Cntr=0.3,0.1

Type RM Length L Ch R = 1 ,5000    ,500,500,500
BEGIN DESCRIPTION:
CRYSTAL CREEK TRIBUTARY NO 2 10.0
END DESCRIPTION:
XS GIS Cut Line= 3
      3863623.12     10112858.75      3862529.59      10112372.9
      3861118.82     10112342.26
#Sta/Elev= 30
  3803.4  191.74    3859  190.03  4027.1     190  4133.9   185.6  4229.6  185.19
    4370  191.34  4600.3  192.23  4794.6   188.8  4859.6  185.49  4867.1  184.89
  4872.6  181.35  4913.1   179.4  4919.1  177.54  4965.6  179.07  4988.8  178.29
  4994.3  176.42  4996.5  174.02  5061.8  179.26  5203.7  181.59  5411.8   182.9
  5499.5  181.68  5651.9  182.17  5701.9  179.34  5801.9  184.95    6022  182.91
    6042  184.33    6062  182.43    6092  183.95  6386.9  185.61  6411.1  185.58
#Mann= 11 ,-1 , 0
  3803.4     .11       0    3859    .125       0  4133.9     .17       0
    4370     .11       0  4794.6     .17       0  4913.1     .11       0
  4965.6     .09       0  5061.8     .11       0  5203.7     .17       0
  5499.5     .11       0  6386.9     .17       0
#XS Ineff= 2 , 0
       0  4947.8  179.15               0
Permanent Ineff=
       F       F
Bank Sta=4965.6,5061.8
XS Rating Curve= 0 ,0
Exp/Cntr=0.3,0.1

Type RM Length L Ch R = 1 ,4500    ,500,500,500
BEGIN DESCRIPTION:
CRYSTAL CREEK TRIBUTARY NO 2 9.0
END DESCRIPTION:
XS GIS Cut Line= 3
      3863848.82     10112463.79      3862728.27     10112006.95
      3861814.67     10111795.72
#Sta/Elev= 30
  3789.9  190.65  3966.8  188.23  4093.3   188.2    4335  184.58  4678.8  179.54
  4783.7  178.63  4888.6  175.84  4926.6  173.34  4974.6  173.95    5003  171.97
  5014.7174.0244    5021     176  5041.5  177.42  5052.6  177.46    5062  174.77
  5082.5  177.47  5094.2  174.63  5144.1  173.36  5174.9  176.79  5265.6  179.81
  5395.4  181.26  5421.2  178.95  5431.5  180.87  5482.8  182.13  5696.5  183.16
  5829.9   184.3  5842.1  183.97  5852.4  181.58  5862.6  184.05  5937.7  184.96
#Mann= 13 ,-1 , 0
  3789.9     .17       0  3966.8     .11       0    4335     .17       0
  4678.8     .11       0  4783.7     .17       0  4888.6     .15       0
  4974.6     .09       0  5014.7     .11       0  5094.2     .17       0
  5265.6     .11       0  5395.4     .17       0  5696.5     .11       0
  5829.9     .17       0
#XS Ineff= 2 , 0
       0                  5052.6       0  177.46
Permanent Ineff=
       F       F
Bank Sta=4974.6,5014.7
XS Rating Curve= 0 ,0
Exp/Cntr=0.3,0.1

Type RM Length L Ch R = 1 ,4000    ,500,500,500
BEGIN DESCRIPTION:
CRYSTAL CREEK TRIBUTARY NO 2 8.0
END DESCRIPTION:
XS GIS Cut Line= 3
      3863913.89     10112285.82      3862928.24     10111693.77
      3862131.48     10111483.26
#Sta/Elev= 30
  3850.2  188.98  4357.4  183.29  4463.8  182.33  4491.8  180.81  4513.2  182.26
  4548.4  181.83  4638.8  182.03  4660.8  180.16  4746.4  180.12    4870  176.28
  4936.8  173.06  4958.2  174.62  4973.7  173.03  4995.1  171.19    4996  170.14
  5052.1   173.1  5085.4  173.52  5114.2  176.18  5186.4   177.6  5224.3  178.86
  5238.3  177.28  5264.6  179.15  5331.4  179.54  5345.1  180.76  5541.2  183.18
  5600.3  181.85  5616.6  183.01  5631.3  181.54  5651.7  182.81  5824.1  183.79
#Mann= 8 ,-1 , 0
  3850.2     .17       0  4357.4     .11       0  4548.4     .17       0
    4870     .11       0  4973.7     .09       0  5052.1     .15       0
  5085.4     .17       0  5186.4     .11       0
#XS Ineff= 2 , 0
       0  4899.9  175.75               0
Permanent Ineff=
       F       F
Bank Sta=4973.7,5052.1
XS Rating Curve= 0 ,0
Exp/Cntr=0.3,0.1

Type RM Length L Ch R = 1 ,3500    ,500,500,500
BEGIN DESCRIPTION:
CRYSTAL CREEK TRIBUTARY NO 2 7.0
END DESCRIPTION:
XS GIS Cut Line= 3
      3864044.14     10112012.41      3862988.24     10111379.04
      3862321.95     10111144.67
#Sta/Elev= 30
  3768.7  187.02  4044.2  183.62  4079.2  184.18  4094.4  182.47  4131.3  183.62
    4211  181.97  4219.2   182.7  4457.3  180.33  4487.4  178.62  4510.7  179.33
    4524  177.65  4545.7  179.42  4646.1  179.13    4730  176.61  4743.9   177.6
  4825.3  176.54  4924.8  173.76  4947.7  172.31  4961.5  169.77  4977.1  171.46
  5012.6  170.38  5021.6   172.1  5034.3  173.22  5100.2  176.78  5147.5  177.36
  5257.7  179.02  5373.6  181.61  5550.3  182.22  5653.5  182.83  5706.3  183.63
#Mann= 11 ,-1 , 0
  3768.7     .17       0  4457.3     .11       0  4646.1     .17       0
  4924.8     .11       0  4947.7     .09       0  5021.6     .11       0
  5034.3     .17       0  5147.5     .11       0  5257.7     .17       0
  5550.3     .11       0  5653.5     .17       0
Bank Sta=4947.7,5021.6
XS Rating Curve= 0 ,0
Exp/Cntr=0.3,0.1

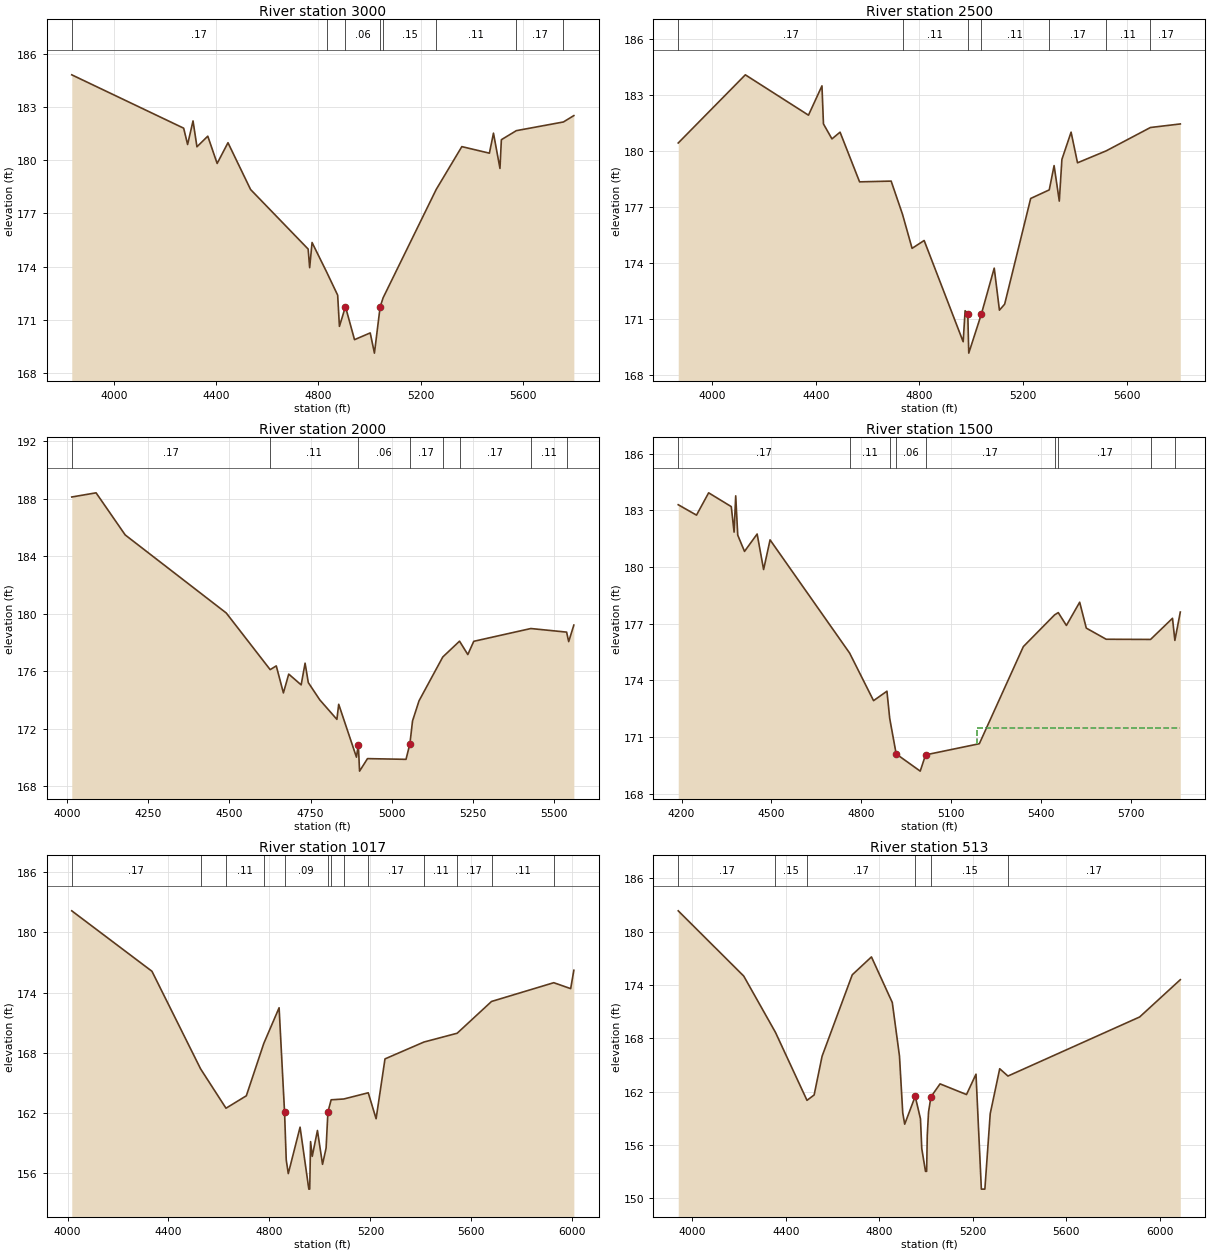
Type RM Length L Ch R = 1 ,3000    ,500,500,500
BEGIN DESCRIPTION:
CRYSTAL CREEK TRIBUTARY NO 2 6.0
END DESCRIPTION:
XS GIS Cut Line= 3
      3864204.74     10111647.83      3863218.24     10111029.45
      3862442.89     10110836.08
#Sta/Elev= 30
  3835.7  184.82  4273.3  181.81  4288.7  180.89  4309.9  182.22  4325.2  180.76
  4367.6  181.36  4404.2  179.82  4446.6  180.99    4535  178.35  4760.1  174.99
    4766  173.94  4775.4  175.36  4832.6  173.69  4875.5  172.39  4882.4  170.63
    4906  171.74  4941.4  169.88  5002.8  170.26  5019.3  169.12  5041.6  171.73
  5053.2  172.24  5261.1  178.36  5361.1  180.77  5468.9   180.4  5484.8  181.53
  5510.2  179.54  5515.7  181.16  5574.1  181.67  5758.3  182.16  5799.1  182.52
#Mann= 8 ,-1 , 0
  3835.7     .17       0  4832.6     .15       0    4906     .06       0
  5041.6     .08       0  5053.2     .15       0  5261.1     .11       0
  5574.1     .17       0  5758.3     .11       0
#XS Ineff= 2 , 0
       0  4775.4  175.36               0
Permanent Ineff=
       F       F
Bank Sta=4906,5041.6
XS Rating Curve= 0 ,0
Exp/Cntr=0.3,0.1

Type RM Length L Ch R = 1 ,2500    ,500,500,500
BEGIN DESCRIPTION:
CRYSTAL CREEK TRIBUTARY NO 2 5.0
END DESCRIPTION:
XS GIS Cut Line= 3
      3864430.44     10111070.57      3863396.37     10110612.71
      3862592.82     10110536.07
#Sta/Elev= 30
  3869.1  180.44  4128.1  184.09  4371.9  181.93  4423.9   183.5  4429.7  181.46
  4462.5  180.66  4493.8  181.02  4569.1  178.36    4691   178.4  4734.9  176.62
  4771.8   174.8  4818.4  175.22    4969   169.8  4976.5  171.46  4986.8  171.31
  4990.6  169.19  5039.4171.2869  5088.9  173.74    5109  171.49  5129.1  171.81
  5229.6  177.47  5301.3  177.93    5320  179.23  5340.1  177.33  5350.1  179.56
  5385.6  181.02  5410.4  179.38  5521.2  180.02  5691.9  181.27  5807.2  181.46
#Mann= 7 ,-1 , 0
  3869.1     .17       0  4734.9     .11       0  4986.8     .09       0
  5039.4     .11       0  5301.3     .17       0  5521.2     .11       0
  5691.9     .17       0
#XS Ineff= 2 , 0
       0                  5088.9       0  173.74
Permanent Ineff=
       F       F
Bank Sta=4986.8,5039.4
XS Rating Curve= 0 ,0
Exp/Cntr=0.3,0.1

Type RM Length L Ch R = 1 ,2000    ,500,500,500
BEGIN DESCRIPTION:
CRYSTAL CREEK TRIBUTARY NO 2 4.0
END DESCRIPTION:
XS GIS Cut Line= 3
      3864213.44     10110588.81      3863341.78     10110127.93
      3862781.99     10110167.72
#Sta/Elev= 30
    4014  188.12  4088.9  188.41  4178.7  185.48  4490.1  180.05  4625.4  176.11
  4644.2  176.37  4666.2  174.49  4682.6   175.8  4720.9  175.05    4733  176.56
  4742.9  175.21  4778.2  174.01    4831  172.65  4836.6   173.7  4891.3  170.02
    4897   170.9  4900.9  169.05  4925.3  169.92    5044  169.87    5056170.9524
  5064.1  172.54  5084.1  173.94  5157.3  176.99  5208.9  178.09  5234.5  177.16
  5252.7  178.08  5428.7  178.97  5538.9  178.72  5545.3  178.06  5561.2  179.21
#Mann= 8 ,-1 , 0
    4014     .17       0  4625.4     .11       0    4897     .06       0
    5056     .17       0  5157.3     .11       0  5208.9     .17       0
  5428.7     .11       0  5538.9     .17       0
#XS Ineff= 2 , 0
       0  4836.6   173.7               0
Permanent Ineff=
       F       F
Bank Sta=4897,5056
XS Rating Curve= 0 ,0
Exp/Cntr=0.3,0.1

Type RM Length L Ch R = 1 ,1500    ,483,483,483
BEGIN DESCRIPTION:
CRYSTAL CREEK TRIBUTARY NO 2 3.0
END DESCRIPTION:
XS GIS Cut Line= 3
      3864311.95     10109998.07      3863560.88     10109691.56
       3862791.3     10110088.88
#Sta/Elev= 30
  4188.8  183.29  4249.8  182.74  4290.4  183.92    4366  183.19  4375.4  181.84
  4380.8  183.76  4387.6  181.68  4410.2  180.82  4452.4  181.74    4474  179.86
  4495.6  181.43  4761.3  175.44  4841.3  172.92    4886  173.42  4895.3  171.98
  4916.9   170.1  4997.2  169.19  5015.1  170.05  5194.7  170.64  5341.7  175.78
  5446.1  177.46  5458.4  177.58  5485.6   176.9  5529.9  178.13    5552  176.76
  5618.5  176.17  5766.7  176.16    5840  177.28  5847.9  176.11  5866.1  177.61
#Mann= 9 ,-1 , 0
  4188.8     .17       0  4761.3     .11       0  4895.3     .08       0
  4916.9     .06       0  5015.1     .17       0  5446.1     .11       0
  5458.4     .17       0  5766.7     .11       0  5847.9     .17       0
#XS Ineff= 2 , 0
       0                  5186.7       0  171.47
Permanent Ineff=
       F       F
Bank Sta=4916.9,5015.1
XS Rating Curve= 0 ,0
Exp/Cntr=0.3,0.1

Type RM Length L Ch R = 1 ,1017    ,504,504,504
BEGIN DESCRIPTION:
CRYSTAL CREEK TRIBUTARY NO 2 2.0
END DESCRIPTION:
XS GIS Cut Line= 3
      3864413.04     10109551.46      3863458.24     10109316.86
      3862755.77     10110036.85
#Sta/Elev= 30
  4016.8  182.15  4334.5  176.12  4527.1  166.39  4627.8  162.46  4708.4   163.7
  4777.5  168.92  4838.2  172.48 4859.72  162.11  4866.5   157.3  4874.6  155.94
  4921.3  160.57    4956  154.39  4959.5  154.39  4962.9  159.13  4969.5  157.66
  4990.1  160.24  5010.3  156.86  5024.4  158.49  5031.6  162.08  5044.4   163.3
  5094.2  163.38  5191.4     164  5222.5  161.41  5257.7  167.38  5411.8  169.06
  5543.7  169.94  5679.8  173.11  5926.4  174.98  5993.3  174.39  6005.9  176.22
#Mann= 13 ,-1 , 0
  4016.8     .17       0  4527.1     .15       0  4627.8     .11       0
  4777.5     .17       0 4859.72     .09       0  5031.6     .15       0
  5044.4     .17       0  5094.2     .15       0  5191.4     .17       0
  5411.8     .11       0  5543.7     .17       0  5679.8     .11       0
  5926.4     .17       0
#XS Ineff= 2 , 0
       0  4838.2  172.48               0
Permanent Ineff=
       F       F
Bank Sta=4859.72,5031.6
XS Rating Curve= 0 ,0
Exp/Cntr=0.3,0.1

Type RM Length L Ch R = 1 ,513     ,0,0,0
BEGIN DESCRIPTION:
CRYSTAL CREEK TRIBUTARY NO 2 1.0
END DESCRIPTION:
XS GIS Cut Line= 3
      3864439.14     10109486.38      3863488.24     10109016.86
      3862416.54     10108830.98
#Sta/Elev= 30
  3939.5  182.33  4219.7     175  4355.5  168.67  4490.4  161.03  4520.9  161.63
    4555  165.99  4684.1  175.14  4766.2  177.15  4855.4  172.02  4886.1  166.01
  4900.1  159.62  4908.5  158.35  4953.4  161.48  4975.9  158.96  4981.5  155.61
  4997.4  153.05  5002.3  153.05    5005  157.09  5010.5  159.72  5020.7  161.42
  5059.7  162.88  5172.9  161.68  5213.5  163.97  5236.5  151.05  5251.5  151.05
  5274.4  159.53    5315  164.58  5350.2  163.76  5913.8   170.4  6087.7  174.59
#Mann= 6 ,-1 , 0
  3939.5     .17       0  4355.5     .15       0  4490.4     .17       0
  4953.4     .09       0  5020.7     .15       0  5350.2     .17       0
#XS Ineff= 2 , 0
       0  4766.2  177.15               0
Permanent Ineff=
       F       F
Bank Sta=4953.4,5020.7
XS Rating Curve= 0 ,0
Exp/Cntr=0.3,0.1

Chan Stop Cuts=-1
Use User Specified Reach Order=0
Composite Channel Slope=5

--- CRYSTAL CREEK TRIBUTARY NO 2.g10 (geometry) ---

Geom Title=Existing Conditions
Program Version=4.10

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
River Reach=CRYSTAL CREEK TR,Reach-1

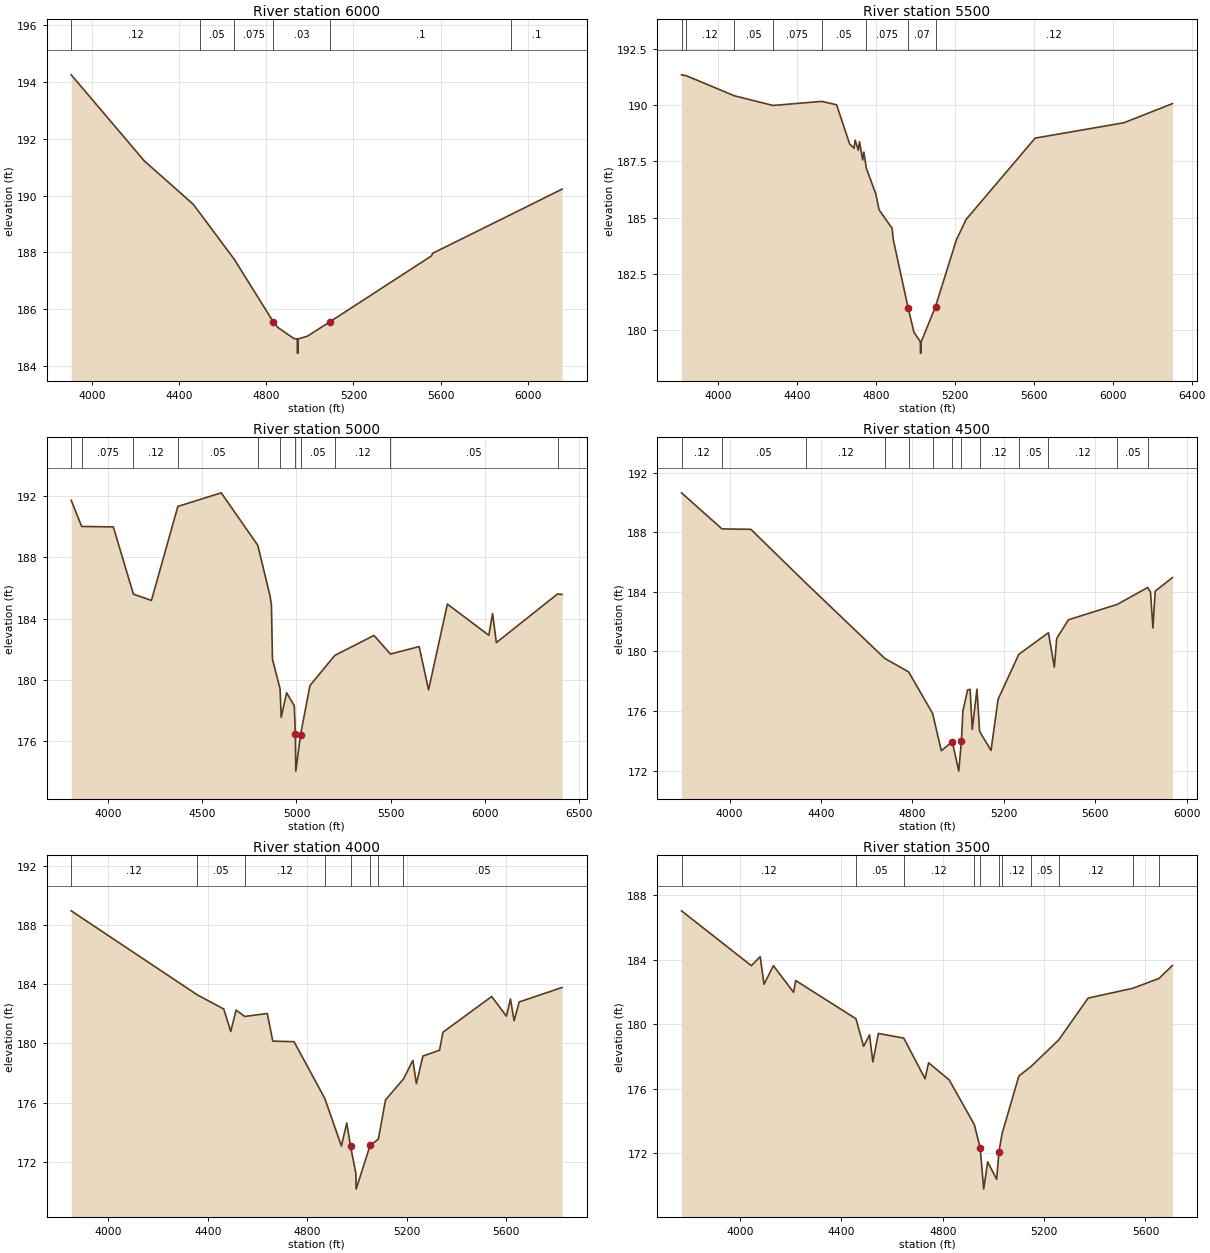
Type RM Length L Ch R = 1 ,6000    ,500,500,500
BEGIN DESCRIPTION:
CRYSTAL CREEK TRIBUTARY NO 2 12.0
END DESCRIPTION:
XS GIS Cut Line= 3
      3863093.63     10113761.54       3862128.7     10113243.92
      3860972.01     10113227.69
#Sta/Elev= 18
    3905  194.25  4240.6  191.22  4464.3   189.7  4494.8  189.39    4654  187.75
  4831.3  185.57  4853.4  185.36  4927.3  184.97  4942.2  184.96  4942.5  184.46
    4946  184.46  4946.2  184.96  4989.6  185.06 5092.13 185.564  5557.7  187.88
  5562.7  187.97  5920.9  189.33  6156.8  190.23
#Mann= 6 ,-1 , 0
    3905     .12       0  4494.8     .05       0    4654    .075       0
  4831.3     .03       0 5092.13      .1       0  5920.9      .1       0
Bank Sta=4831.3,5092.13
XS Rating Curve= 0 ,0
Exp/Cntr=0.3,0.1

Type RM Length L Ch R = 1 ,5500    ,500,500,500
BEGIN DESCRIPTION:
CRYSTAL CREEK TRIBUTARY NO 2 11.0
END DESCRIPTION:
XS GIS Cut Line= 3
      3863397.44     10113340.53        3862344.     10112792.65
      3861041.77     10112806.66
#Sta/Elev= 30
  3812.6  191.34  3836.6   191.3  4080.2  190.41  4276.6  189.98    4524  190.16
    4599  190.01  4665.3  188.27  4687.4  188.08  4693.1  188.44  4709.5  187.99
  4715.2  188.37  4731.6  187.56  4737.3  187.91  4750.3  187.18    4798  186.05
  4814.4  185.35  4880.8  184.52  4886.4  184.03  4961.8     181  4991.3  179.91
  5024.1  179.48  5024.4  178.98  5027.9  178.98  5028.1  179.48 5100.75 181.047
  5206.2     184  5256.2  184.92  5606.2  188.53  6056.2  189.21  6302.3  190.06
#Mann= 8 ,-1 , 0
  3812.6     .05       0  3836.6     .12       0  4080.2     .05       0
  4276.6    .075       0    4524     .05       0  4750.3    .075       0
  4961.8     .07       0 5100.75     .12       0
Bank Sta=4961.8,5100.75
XS Rating Curve= 0 ,0
Exp/Cntr=0.3,0.1

Type RM Length L Ch R = 1 ,5000    ,500,500,500
BEGIN DESCRIPTION:
CRYSTAL CREEK TRIBUTARY NO 2 10.0
END DESCRIPTION:
XS GIS Cut Line= 3
      3863623.12     10112858.75      3862529.59      10112372.9
      3861118.82     10112342.26
#Sta/Elev= 30
  3803.4  191.74    3859  190.03  4027.1     190  4133.9   185.6  4229.6  185.19
    4370  191.34  4600.3  192.23  4794.6   188.8  4859.6  185.49  4867.1  184.89
  4872.6  181.35  4913.1   179.4  4919.1  177.54  4947.8  179.15  4988.8  178.29
  4994.3  176.42  4996.5  174.02  5021.7   176.4  5071.8  179.62  5203.7  181.59
  5411.8   182.9  5499.5  181.68  5651.9  182.17  5701.9  179.34  5801.9  184.95
    6022  182.91    6042  184.33    6062  182.43  6386.9  185.61  6411.1  185.58
#Mann= 11 ,-1 , 0
  3803.4     .05       0    3859    .075       0  4133.9     .12       0
    4370     .05       0  4794.6     .12       0  4913.1     .05       0
  4994.3     .07       0  5021.7     .05       0  5203.7     .12       0
  5499.5     .05       0  6386.9     .12       0
Bank Sta=4994.3,5021.7
XS Rating Curve= 0 ,0
Exp/Cntr=0.3,0.1

Type RM Length L Ch R = 1 ,4500    ,500,500,500
BEGIN DESCRIPTION:
CRYSTAL CREEK TRIBUTARY NO 2 9.0
END DESCRIPTION:
XS GIS Cut Line= 3
      3863848.82     10112463.79      3862728.27     10112006.95
      3861814.67     10111795.72
#Sta/Elev= 30
  3789.9  190.65  3966.8  188.23  4093.3   188.2    4335  184.58  4678.8  179.54
  4783.7  178.63  4888.6  175.84  4926.6  173.34  4974.6  173.95    5003  171.97
  5014.7 174.024    5021     176  5041.5  177.42  5052.6  177.46    5062  174.77
  5082.5  177.47  5094.2  174.63  5144.1  173.36  5174.9  176.79  5265.6  179.81
  5395.4  181.26  5421.2  178.95  5431.5  180.87  5482.8  182.13  5696.5  183.16
  5829.9   184.3  5842.1  183.97  5852.4  181.58  5862.6  184.05  5937.7  184.96
#Mann= 13 ,-1 , 0
  3789.9     .12       0  3966.8     .05       0    4335     .12       0
  4678.8     .05       0  4783.7     .12       0  4888.6      .1       0
  4974.6     .07       0  5014.7     .05       0  5094.2     .12       0
  5265.6     .05       0  5395.4     .12       0  5696.5     .05       0
  5829.9     .12       0
Bank Sta=4974.6,5014.7
XS Rating Curve= 0 ,0
Exp/Cntr=0.3,0.1

Type RM Length L Ch R = 1 ,4000    ,500,500,500
BEGIN DESCRIPTION:
CRYSTAL CREEK TRIBUTARY NO 2 8.0
END DESCRIPTION:
XS GIS Cut Line= 3
      3863913.89     10112285.82      3862928.24     10111693.77
      3862131.48     10111483.26
#Sta/Elev= 30
  3850.2  188.98  4357.4  183.29  4463.8  182.33  4491.8  180.81  4513.2  182.26
  4548.4  181.83  4638.8  182.03  4660.8  180.16  4746.4  180.12    4870  176.28
  4936.8  173.06  4958.2  174.62  4973.7  173.03  4995.1  171.19    4996  170.14
  5052.1   173.1  5085.4  173.52  5114.2  176.18  5186.4   177.6  5224.3  178.86
  5238.3  177.28  5264.6  179.15  5331.4  179.54  5345.1  180.76  5541.2  183.18
  5600.3  181.85  5616.6  183.01  5631.3  181.54  5651.7  182.81  5824.1  183.79
#Mann= 8 ,-1 , 0
  3850.2     .12       0  4357.4     .05       0  4548.4     .12       0
    4870     .05       0  4973.7     .07       0  5052.1      .1       0
  5085.4     .12       0  5186.4     .05       0
Bank Sta=4973.7,5052.1
XS Rating Curve= 0 ,0
Exp/Cntr=0.3,0.1

Type RM Length L Ch R = 1 ,3500    ,500,500,500
BEGIN DESCRIPTION:
CRYSTAL CREEK TRIBUTARY NO 2 7.0
END DESCRIPTION:
XS GIS Cut Line= 3
      3864044.14     10112012.41      3862988.24     10111379.04
      3862321.95     10111144.67
#Sta/Elev= 30
  3768.7  187.02  4044.2  183.62  4079.2  184.18  4094.4  182.47  4131.3  183.62
    4211  181.97  4219.2   182.7  4457.3  180.33  4487.4  178.62  4510.7  179.33
    4524  177.65  4545.7  179.42  4646.1  179.13    4730  176.61  4743.9   177.6
  4825.3  176.54  4924.8  173.76  4947.7  172.31  4961.5  169.77  4977.1  171.46
  5012.6  170.38  5021.6   172.1  5034.3  173.22  5100.2  176.78  5147.5  177.36
  5257.7  179.02  5373.6  181.61  5550.3  182.22  5653.5  182.83  5706.3  183.63
#Mann= 11 ,-1 , 0
  3768.7     .12       0  4457.3     .05       0  4646.1     .12       0
  4924.8     .05       0  4947.7     .07       0  5021.6     .05       0
  5034.3     .12       0  5147.5     .05       0  5257.7     .12       0
  5550.3     .05       0  5653.5     .12       0
Bank Sta=4947.7,5021.6
XS Rating Curve= 0 ,0
Exp/Cntr=0.3,0.1

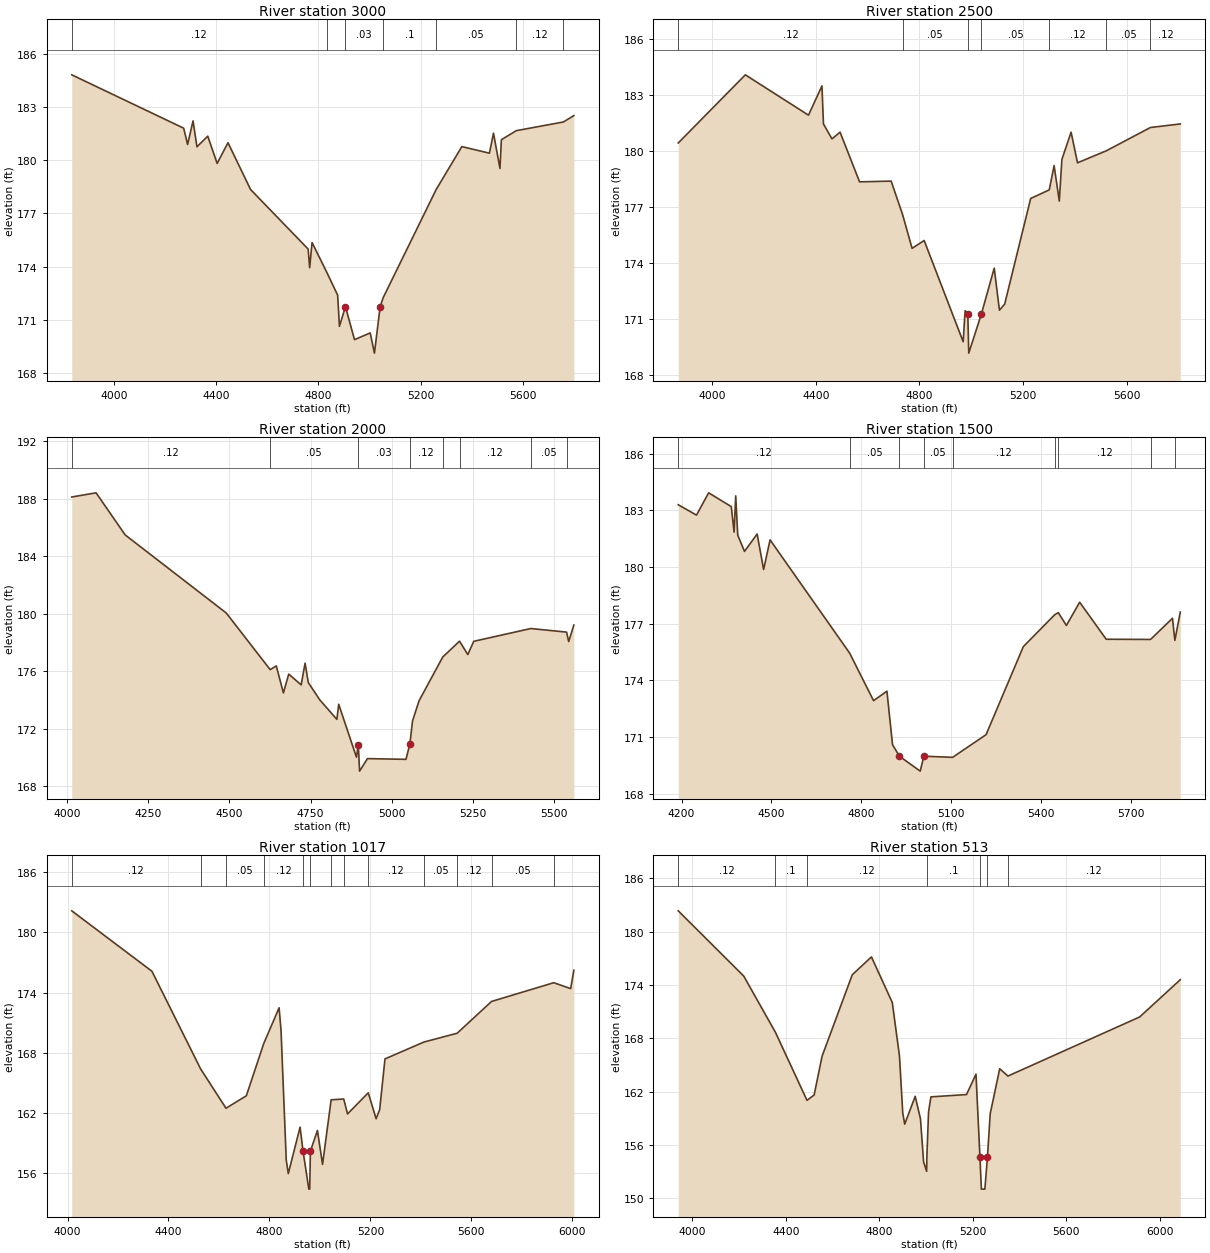
Type RM Length L Ch R = 1 ,3000    ,500,500,500
BEGIN DESCRIPTION:
CRYSTAL CREEK TRIBUTARY NO 2 6.0
END DESCRIPTION:
XS GIS Cut Line= 3
      3864204.74     10111647.83      3863218.24     10111029.45
      3862442.89     10110836.08
#Sta/Elev= 30
  3835.7  184.82  4273.3  181.81  4288.7  180.89  4309.9  182.22  4325.2  180.76
  4367.6  181.36  4404.2  179.82  4446.6  180.99    4535  178.35  4760.1  174.99
    4766  173.94  4775.4  175.36  4832.6  173.69  4875.5  172.39  4882.4  170.63
    4906  171.74  4941.4  169.88  5002.8  170.26  5019.3  169.12  5041.6  171.73
  5053.2  172.24  5261.1  178.36  5361.1  180.77  5468.9   180.4  5484.8  181.53
  5510.2  179.54  5515.7  181.16  5574.1  181.67  5758.3  182.16  5799.1  182.52
#Mann= 7 ,-1 , 0
  3835.7     .12       0  4832.6      .1       0    4906     .03       0
  5053.2      .1       0  5261.1     .05       0  5574.1     .12       0
  5758.3     .05       0
Bank Sta=4906,5041.6
XS Rating Curve= 0 ,0
Exp/Cntr=0.3,0.1

Type RM Length L Ch R = 1 ,2500    ,500,500,500
BEGIN DESCRIPTION:
CRYSTAL CREEK TRIBUTARY NO 2 5.0
END DESCRIPTION:
XS GIS Cut Line= 3
      3864430.44     10111070.57      3863396.37     10110612.71
      3862592.82     10110536.07
#Sta/Elev= 30
  3869.1  180.44  4128.1  184.09  4371.9  181.93  4423.9   183.5  4429.7  181.46
  4462.5  180.66  4493.8  181.02  4569.1  178.36    4691   178.4  4734.9  176.62
  4771.8   174.8  4818.4  175.22    4969   169.8  4976.5  171.46  4986.8  171.31
  4990.6  169.19  5039.4 171.287  5088.9  173.74    5109  171.49  5129.1  171.81
  5229.6  177.47  5301.3  177.93    5320  179.23  5340.1  177.33  5350.1  179.56
  5385.6  181.02  5410.4  179.38  5521.2  180.02  5691.9  181.27  5807.2  181.46
#Mann= 7 ,-1 , 0
  3869.1     .12       0  4734.9     .05       0  4986.8     .07       0
  5039.4     .05       0  5301.3     .12       0  5521.2     .05       0
  5691.9     .12       0
Bank Sta=4986.8,5039.4
XS Rating Curve= 0 ,0
Exp/Cntr=0.3,0.1

Type RM Length L Ch R = 1 ,2000    ,500,500,500
BEGIN DESCRIPTION:
CRYSTAL CREEK TRIBUTARY NO 2 4.0
END DESCRIPTION:
XS GIS Cut Line= 3
      3864213.44     10110588.81      3863341.78     10110127.93
      3862781.99     10110167.72
#Sta/Elev= 30
    4014  188.12  4088.9  188.41  4178.7  185.48  4490.1  180.05  4625.4  176.11
  4644.2  176.37  4666.2  174.49  4682.6   175.8  4720.9  175.05    4733  176.56
  4742.9  175.21  4778.2  174.01    4831  172.65  4836.6   173.7  4891.3  170.02
    4897   170.9  4900.9  169.05  4925.3  169.92    5044  169.87    5056 170.952
  5064.1  172.54  5084.1  173.94  5157.3  176.99  5208.9  178.09  5234.5  177.16
  5252.7  178.08  5428.7  178.97  5538.9  178.72  5545.3  178.06  5561.2  179.21
#Mann= 8 ,-1 , 0
    4014     .12       0  4625.4     .05       0    4897     .03       0
    5056     .12       0  5157.3     .05       0  5208.9     .12       0
  5428.7     .05       0  5538.9     .12       0
Bank Sta=4897,5056
XS Rating Curve= 0 ,0
Exp/Cntr=0.3,0.1

Type RM Length L Ch R = 1 ,1500    ,483,483,483
BEGIN DESCRIPTION:
CRYSTAL CREEK TRIBUTARY NO 2 3.0
END DESCRIPTION:
XS GIS Cut Line= 3
      3864311.95     10109998.07      3863560.88     10109691.56
       3862791.3     10110088.88
#Sta/Elev= 30
  4188.8  183.29  4249.8  182.74  4290.4  183.92    4366  183.19  4375.4  181.84
  4380.8  183.76  4387.6  181.68  4410.2  180.82  4452.4  181.74    4474  179.86
  4495.6  181.43  4761.3  175.44  4841.3  172.92    4886  173.42  4904.7  170.59
  4927.7  169.98  4997.2  169.19  5009.4  169.98  5105.5  169.92  5217.2  171.12
  5341.7  175.78  5446.1  177.46  5458.4  177.58  5485.6   176.9  5529.9  178.13
  5618.5  176.17  5766.7  176.16    5840  177.28  5847.9  176.11  5866.1  177.61
#Mann= 9 ,-1 , 0
  4188.8     .12       0  4761.3     .05       0  4927.7     .03       0
  5009.4     .05       0  5105.5     .12       0  5446.1     .05       0
  5458.4     .12       0  5766.7     .05       0  5847.9     .12       0
Bank Sta=4927.7,5009.4
XS Rating Curve= 0 ,0
Exp/Cntr=0.3,0.1

Type RM Length L Ch R = 1 ,1017    ,504,504,504
BEGIN DESCRIPTION:
CRYSTAL CREEK TRIBUTARY NO 2 2.0
END DESCRIPTION:
XS GIS Cut Line= 3
      3864413.04     10109551.46      3863458.24     10109316.86
      3862755.77     10110036.85
#Sta/Elev= 30
  4016.8  182.15  4334.5  176.12  4527.1  166.39  4627.8  162.46  4708.4   163.7
  4777.5  168.92  4838.2  172.48  4845.9   170.2  4866.5   157.3  4874.6  155.94
  4921.3  160.57  4933.2 158.156    4956  154.39  4959.5  154.39 4962.18 158.176
  4990.1  160.24  5010.3  156.86  5044.4   163.3  5094.2  163.38  5109.3  161.89
  5191.4     164  5222.5  161.41  5236.6  162.31  5257.7  167.38  5411.8  169.06
  5543.7  169.94  5679.8  173.11  5926.4  174.98  5993.3  174.39  6005.9  176.22
#Mann= 13 ,-1 , 0
  4016.8     .12       0  4527.1      .1       0  4627.8     .05       0
  4777.5     .12       0  4933.2     .07       0 4962.18      .1       0
  5044.4     .12       0  5094.2      .1       0  5191.4     .12       0
  5411.8     .05       0  5543.7     .12       0  5679.8     .05       0
  5926.4     .12       0
Bank Sta=4933.2,4962.18
XS Rating Curve= 0 ,0
Exp/Cntr=0.3,0.1

Type RM Length L Ch R = 1 ,513     ,0,0,0
BEGIN DESCRIPTION:
CRYSTAL CREEK TRIBUTARY NO 2 1.0
END DESCRIPTION:
XS GIS Cut Line= 3
      3864439.14     10109486.38      3863488.24     10109016.86
      3862416.54     10108830.98
#Sta/Elev= 30
  3939.5  182.33  4219.7     175  4355.5  168.67  4490.4  161.03  4520.9  161.63
    4555  165.99  4684.1  175.14  4766.2  177.15  4855.4  172.02  4886.1  166.01
  4900.1  159.62  4908.5  158.35  4953.4  161.48  4975.9  158.96  4989.3  154.11
  5002.3  153.05  5003.4   154.7  5010.5  159.72  5020.7  161.42  5172.9  161.68
  5213.5  163.97  5230.3 154.717  5236.5  151.05  5251.5  151.05 5262.53 154.659
  5274.4  159.53    5315  164.58  5350.2  163.76  5913.8   170.4  6087.7  174.59
#Mann= 7 ,-1 , 0
  3939.5     .12       0  4355.5      .1       0  4490.4     .12       0
  5003.4      .1       0  5230.3     .07       0 5262.53      .1       0
  5350.2     .12       0
Bank Sta=5230.3,5262.53
XS Rating Curve= 0 ,0
Exp/Cntr=0.3,0.1