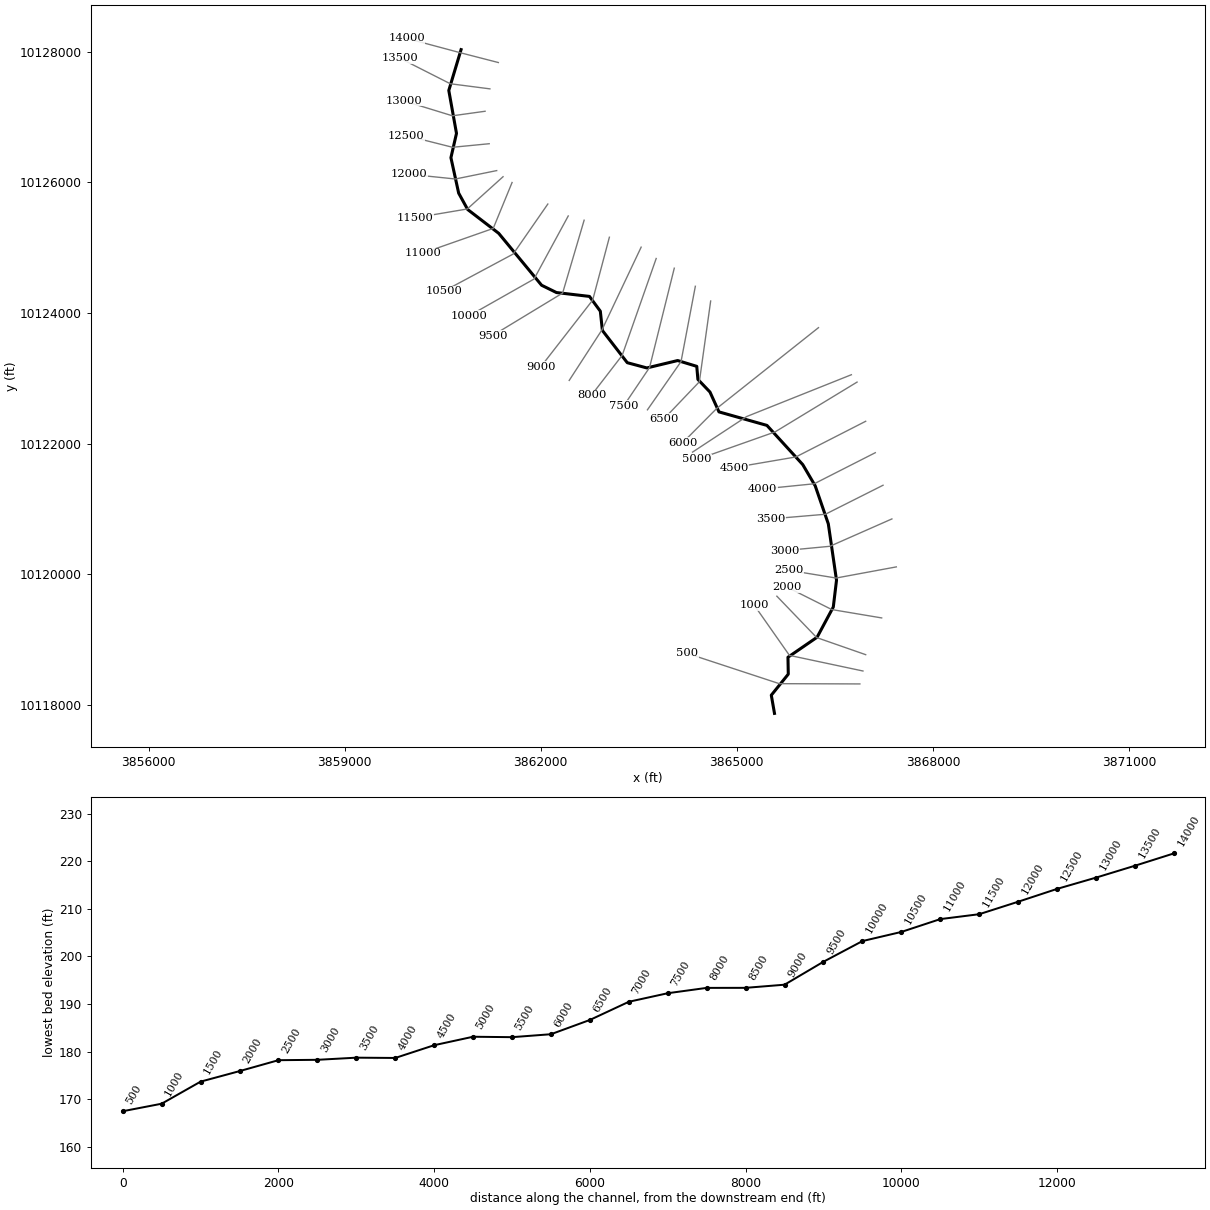
--- CRYSTAL CREEK TRIBUTARY NO 3.prj (project) ---

Proj Title=CRYSTAL CREEK TRIBUTARY NO 3 Base Level Engineering
Current Plan=p01
Default Exp/Contr=0.3,0.1
English Units
Geom File=g01
Flow File=f01
Plan File=p01
Y Axis Title=Elevation
X Axis Title(PF)=Main Channel Distance
X Axis Title(XS)=Station
BEGIN DESCRIPTION:
CRYSTAL CREEK TRIBUTARY NO 3
END DESCRIPTION:
DSS File=dss
DSS Export Rating Curves= 0
DSS Export Rating Curve Sorted= 0
DSS Export Volume Flow Curves= 0
DXF OffsetX= 0
DXF OffsetY= 0
DXF ScaleX= 1
DXF ScaleY= 10

--- CRYSTAL CREEK TRIBUTARY NO 3.p01 (plan) ---

Plan Title=Multiple Run
Program Version=4.10
Short Identifier=Multiple Run
Geom File=g01
Flow File=f01
Subcritical Flow
K Sum by GR= 0
Std Step Tol= 0.01
Critical Tol= 0.01
Num of Std Step Trials= 20
Max Error Tol= 0.3
Flow Tol Ratio= 0.001
Split Flow NTrial= 30
Split Flow Tol= 0.02
Split Flow Ratio= 0.02
Log Output Level= 0
Friction Slope Method= 1
Unsteady Friction Slope Method= 2
Unsteady Bridges Friction Slope Method= 1
Parabolic Critical Depth
Global Vel Dist= 1 , 1 , 1
Global Log Level= 0
CheckData=True
Encroach Param=-1 ,0,0, 0
BEGIN DESCRIPTION:
Multiple Run
END DESCRIPTION:
Computation Interval=1HOUR
Output Interval=1HOUR
Run HTab= 0
Run UNet= 0
Run PostProcess= 0
Run WQNet= 0
UNET Theta= 1
UNET Theta Warmup= 1
UNET ZTol= 0.02
UNET ZSATol= 0.05
UNET MxIter= 20
UNET MaxInSteps= 0
UNET DtIC= 0
UNET DtMin= 0
UNET MaxCRTS= 20
UNET WFStab= 2
UNET SFStab= 1
UNET WFX= 1
UNET SFX= 1
UNET DSS MLevel= 4
UNET DZMax Abort= 100
UNET Convert EG Bridges= 0
UNET Use Existing IB Tables=-1
UNET Froude Reduction=False
UNET Froude Limit= 1
UNET Froude Power= 10
UNET Time Slicing=0,0, 5
UNET Junction Losses=0
Instantaneous Interval=1HOUR
DSS File=dss
Write IC File= 0
Write IC File at Sim End=0
Echo Input=False
Echo Parameters=False
Echo Output=False
Write Detailed= 0
WQ AD Non Conservative
WQ ULTIMATE=-1
WQ Max Comp Step=1HOUR
WQ Output Interval=15MIN
WQ Output Selected Increments= 0
WQ Output face flow=0
WQ Output face velocity=0
WQ Output face area=0
WQ Output face dispersion=0
WQ Output cell volume=0
WQ Output cell surface area=0
WQ Output cell continuity=0
WQ Output cumulative cell continuity=0
WQ Output face conc=0
WQ Output face dconc_dx=0
WQ Output face courant=0
WQ Output face peclet=0
WQ Output face adv mass=0
WQ Output face disp mass=0
WQ Output cell mass=0
WQ Output cell source sink temp=0
WQ Output cell source sink nsm=0
WQ Output MaxMinRange=-1
WQ Daily Max Min Mean=-1
WQ Daily Range=0
WQ Daily Time=0
WQ Create Restart=0
WQ Fixed Restart=0
WQ System Summary=0
WQ Use Fixed Temperature=0
Sorting and Armoring Iterations= 10
XS Update Threshold= 0.02
Hydraulics Update Threshold= 0.02
Energy Slope Method= 1
Volume Change Method= 0
XS Weighting Method= 0
Number of US Weighted Cross Sections= 1
Number of DS Weighted Cross Sections= 1
Upstream XS Weight=0.25
Main XS Weight=0.5
Downstream XS Weight=0.25
Number of DS XS's Weighted with US Boundary= 1
Upstream Boundary Weight= 1
Weight of XSs Associated with US Boundary= 0
Number of US XS's Weighted with DS Boundary= 1
Downstream Boundary Weight= 0.5
Weight of XSs Associated with DS Boundary= 0.5
Sediment Output Level= 4
Mass or Volume Output= 0
Output Increment Type= 1
Profile and TS Output Increment= 10
XS Output Flag= 0
XS Output Increment= 10
Disregard all LS=0
Disregard all Conn=0
Disregard all Breaches=0
Disregard all Pumps=0

--- CRYSTAL CREEK TRIBUTARY NO 3.f01 (steady flow) ---

Flow Title=Multiple
Program Version=4.10
Number of Profiles= 7
Profile Names=10-year,25-year,50-year,1pct_min,100-year,1pct_plu,500-year
River Rch & RM=CRYSTAL CREEK TR,Reach-1         ,14000
     488     636     840     364    1100    3322    1949
River Rch & RM=CRYSTAL CREEK TR,Reach-1         ,6000
    1212    1667    2274    1017    3072    9277    5800
River Rch & RM=CRYSTAL CREEK TR,Reach-1         ,4500
    1212    1667    2274    1017    3072    9277    5800
River Rch & RM=CRYSTAL CREEK TR,Reach-1         ,2000
    1259    1733    2368    1060    3202    9670    6056
River Rch & RM=CRYSTAL CREEK TR,Reach-1         ,500
    4782    6866    9644    4422   13354   40328   26483
Boundary for River Rch & Prof#=CRYSTAL CREEK TR,Reach-1         , 1
Up Type= 0
Dn Type= 3
Dn Slope=0.009
Boundary for River Rch & Prof#=CRYSTAL CREEK TR,Reach-1         , 2
Up Type= 0
Dn Type= 3
Dn Slope=0.009
Boundary for River Rch & Prof#=CRYSTAL CREEK TR,Reach-1         , 3
Up Type= 0
Dn Type= 3
Dn Slope=0.009
Boundary for River Rch & Prof#=CRYSTAL CREEK TR,Reach-1         , 4
Up Type= 0
Dn Type= 3
Dn Slope=0.009
Boundary for River Rch & Prof#=CRYSTAL CREEK TR,Reach-1         , 5
Up Type= 0
Dn Type= 3
Dn Slope=0.009
Boundary for River Rch & Prof#=CRYSTAL CREEK TR,Reach-1         , 6
Up Type= 0
Dn Type= 3
Dn Slope=0.009
Boundary for River Rch & Prof#=CRYSTAL CREEK TR,Reach-1         , 7
Up Type= 0
Dn Type= 3
Dn Slope=0.009
DSS Import GetInterval= 0
DSS Import GetPeak= 0
DSS Import FillOption= 0

--- CRYSTAL CREEK TRIBUTARY NO 3.g01 (geometry) ---

Geom Title=Existing Conditions
Program Version=4.10

River Reach=CRYSTAL CREEK TR,Reach-1
Reach XY= 30
      3860781.12     10128031.75      3860593.25     10127406.81
      3860710.99     10126749.66      3860625.79     10126377.52
      3860744.38     10125834.53      3860881.77     10125584.51
      3861356.61     10125219.69        3862013.     10124424.79
       3862240.2     10124312.95      3862745.23     10124253.75
      3862911.63     10124027.12      3862942.95      10123732.3
      3863323.54     10123239.15      3863623.39     10123158.63
      3864094.58       10123272.      3864386.82     10123183.13
      3864403.84     10122983.74      3864588.75     10122789.98
      3864726.59     10122485.97      3865460.46     10122278.97
      3866007.97     10121679.25      3866198.82     10121353.67
      3866399.23     10120772.29      3866524.64       10119909.
       3866475.6     10119498.94      3866227.95     10119036.42
      3865781.99     10118729.92      3865786.76     10118470.93
      3865527.11     10118148.94      3865575.82     10117870.48

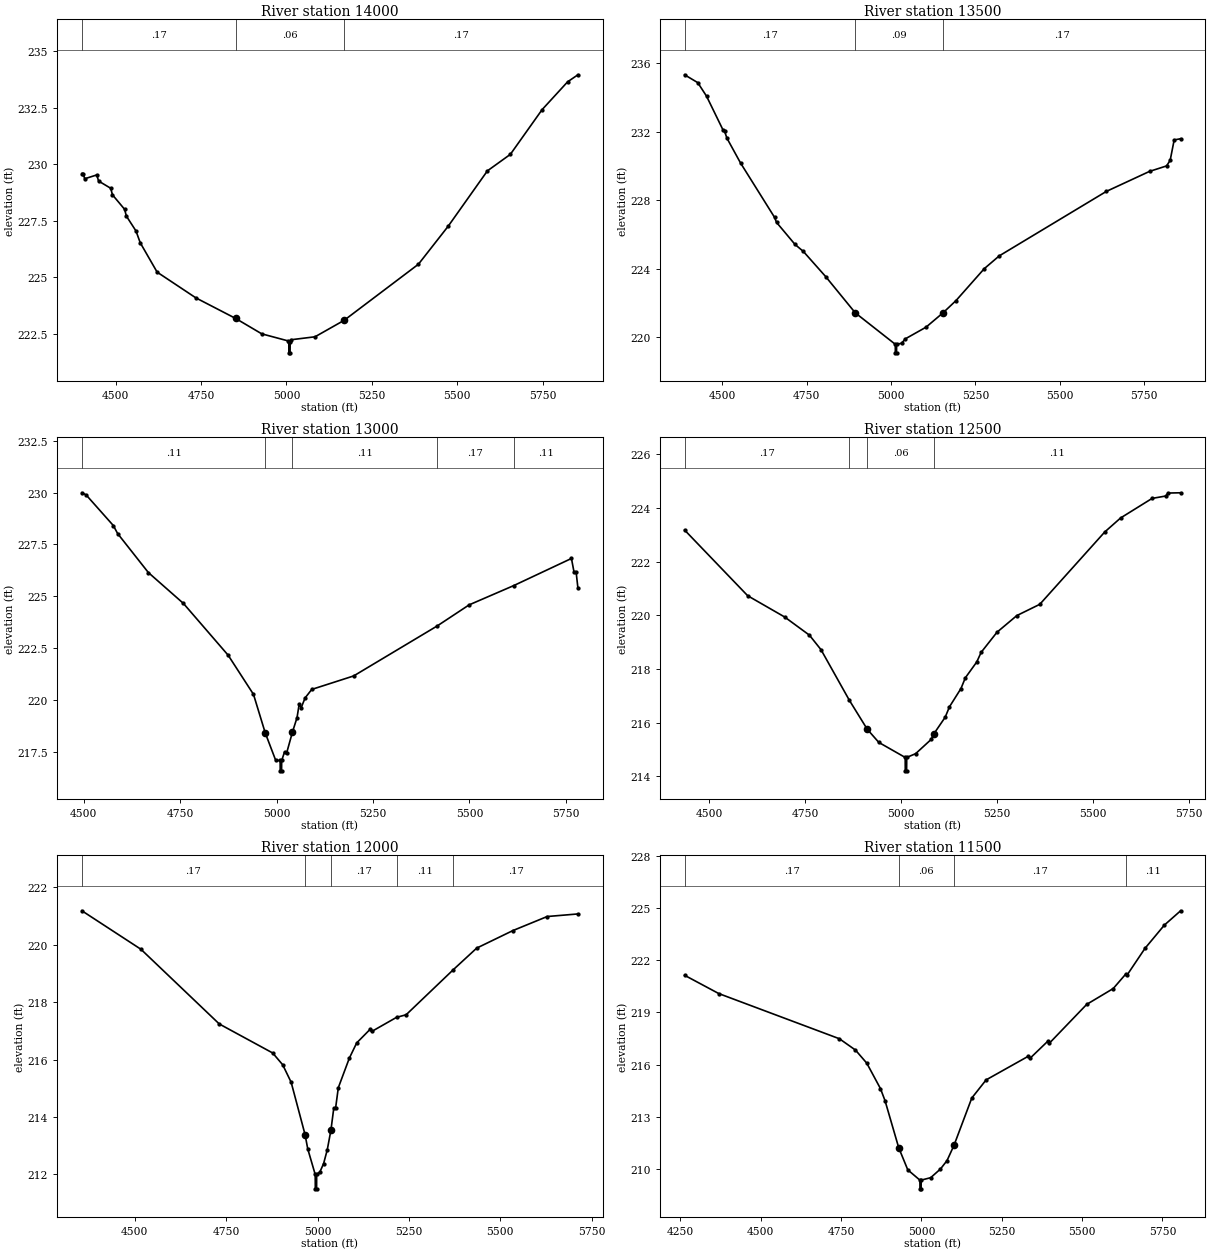
Type RM Length L Ch R = 1 ,14000   ,500,500,500
BEGIN DESCRIPTION:
CRYSTAL CREEK TRIBUTARY NO 3 28.0
END DESCRIPTION:
XS GIS Cut Line= 3
       3861351.2     10127834.18      3860771.07     10127983.74
      3859946.65     10128204.65
#Sta/Elev= 30
  4400.9  229.59  4404.7  229.59    4409  229.36  4444.5  229.53  4449.7  229.26
  4485.2  228.94  4490.4  228.65  4525.9  228.01  4531.1  227.71  4559.3  227.05
  4571.7  226.53  4621.2  225.23  4734.8  224.09  4851.3  223.18  4927.6   222.5
  5004.3  222.19  5006.8  222.16    5007  221.66  5010.5  221.66  5010.8  222.16
  5013.9  222.24  5083.6  222.37    5169   223.1  5386.4  225.58  5473.5  227.26
  5588.4  229.71  5655.6  230.44  5748.7  232.42  5823.4  233.65  5853.5  233.96
#Mann= 3 , 0 , 0
  4400.9     .17       0  4851.3     .06       0    5169     .17       0
Bank Sta=4851.3,5169
XS Rating Curve= 0 ,0
Exp/Cntr=0.3,0.1

Type RM Length L Ch R = 1 ,13500   ,500,500,500
BEGIN DESCRIPTION:
CRYSTAL CREEK TRIBUTARY NO 3 27.0
END DESCRIPTION:
XS GIS Cut Line= 3
      3861222.31      10127431.2      3860615.92     10127509.32
      3859850.78     10127897.78
#Sta/Elev= 30
  4388.6  235.33  4427.6  234.87  4453.6  234.08    4502  232.12    4507  232.03
  4514.1  231.62  4554.4  230.17  4655.2  226.99  4660.9   226.7  4715.7  225.41
  4740.4     225  4806.5  223.53  4894.2  221.41  5012.8  219.57    5013  219.07
  5016.5  219.07  5016.8  219.57  5031.4  219.63  5042.7  219.89  5103.8  220.57
  5154.8  221.42  5192.9  222.13  5276.3  223.99  5320.8  224.74  5638.1  228.51
    5766  229.68  5816.5     230  5827.2  230.33    5839  231.52  5858.1  231.59
#Mann= 3 , 0 , 0
  4388.6     .17       0  4894.2     .09       0  5154.8     .17       0
Bank Sta=4894.2,5154.8
XS Rating Curve= 0 ,0
Exp/Cntr=0.3,0.1

Type RM Length L Ch R = 1 ,13000   ,500,500,500
BEGIN DESCRIPTION:
CRYSTAL CREEK TRIBUTARY NO 3 26.0
END DESCRIPTION:
XS GIS Cut Line= 3
       3861148.5     10127088.32      3860648.52     10127018.76
      3859901.78     10127248.57
#Sta/Elev= 30
  4495.2  229.99    4506  229.89  4576.6  228.41  4587.9  228.02  4667.5  226.14
  4758.4  224.65  4874.4  222.15  4940.1  220.26  4970.4  218.41  4997.8  217.07
  5009.2  217.07  5009.4  216.57  5012.9  216.57  5013.2  217.07  5020.6  217.48
  5025.9  217.42 5040.93218.4297    5053  219.14  5058.5  219.78  5063.8  219.62
  5073.9  220.09  5091.2   220.5  5199.8  221.15  5416.2  223.56  5499.2  224.58
  5614.8  225.51  5764.5  226.82  5771.3  226.15  5776.5  226.18  5781.3  225.39
#Mann= 5 ,-1 , 0
  4495.2     .11       0  4970.4     .09       0 5040.93     .11       0
  5416.2     .17       0  5614.8     .11       0
#XS Ineff= 2 , 0
       0                  5058.5       0  219.78
Permanent Ineff=
       F       F
Bank Sta=4970.4,5040.93
XS Rating Curve= 0 ,0
Exp/Cntr=0.3,0.1

Type RM Length L Ch R = 1 ,12500   ,500,500,500
BEGIN DESCRIPTION:
CRYSTAL CREEK TRIBUTARY NO 3 25.0
END DESCRIPTION:
XS GIS Cut Line= 3
      3861211.49     10126591.36      3860650.74     10126536.77
      3859944.08     10126715.06
#Sta/Elev= 30
  4436.6  223.18    4601  220.73    4697  219.94  4761.8  219.26  4791.9  218.72
  4865.9  216.83  4912.5  215.75  4942.6  215.26  5011.3   214.7  5011.5   214.2
    5015   214.2  5015.3   214.7  5038.5  214.84  5079.6  215.38  5085.5  215.57
  5115.5   216.2  5126.7  216.59  5156.6  217.27    5168  217.67  5197.7  218.26
  5209.2  218.62  5250.5  219.37  5302.1  219.99  5361.9  220.41  5531.3  223.11
  5572.4  223.63  5654.5  224.36  5690.4  224.45  5695.6  224.56  5728.8  224.57
#Mann= 4 ,-1 , 0
  4436.6     .17       0  4865.9     .11       0  4912.5     .06       0
  5085.5     .11       0
Bank Sta=4912.5,5085.5
XS Rating Curve= 0 ,0
Exp/Cntr=0.3,0.1

Type RM Length L Ch R = 1 ,12000   ,500,500,500
BEGIN DESCRIPTION:
CRYSTAL CREEK TRIBUTARY NO 3 24.0
END DESCRIPTION:
XS GIS Cut Line= 3
      3861326.08     10126179.91      3860694.46     10126051.21
      3859985.72     10126124.35
#Sta/Elev= 30
  4355.4  221.18  4516.9  219.84  4731.2  217.24  4877.3  216.23  4904.7  215.82
  4927.9  215.21  4965.9  213.39  4973.3  212.89  4993.7     212    4994   211.5
  4997.5   211.5  4997.7     212  5006.6  212.09  5016.7  212.38  5026.7  212.86
  5036.8  213.55  5044.6  214.32  5049.6  214.32  5056.9  215.02  5087.1  216.05
  5107.2  216.58  5143.6  217.05  5148.6  216.98  5216.2  217.47  5242.5  217.56
  5371.6  219.13  5435.5  219.88  5534.4  220.49  5628.4  220.98  5712.5  221.07
#Mann= 5 ,-1 , 0
  4355.4     .17       0  4965.9     .09       0  5036.8     .17       0
  5216.2     .11       0  5371.6     .17       0
Bank Sta=4965.9,5036.8
XS Rating Curve= 0 ,0
Exp/Cntr=0.3,0.1

Type RM Length L Ch R = 1 ,11500   ,500,500,500
BEGIN DESCRIPTION:
CRYSTAL CREEK TRIBUTARY NO 3 23.0
END DESCRIPTION:
XS GIS Cut Line= 3
      3861423.28     10126086.17      3860876.29     10125592.38
      3860081.18     10125457.96
#Sta/Elev= 30
  4263.1  221.13  4369.6  220.08  4744.7  217.49  4794.8  216.84  4829.9  216.09
  4872.5  214.63  4886.7  213.94  4929.3  211.24  4957.5  209.97  4995.2  209.38
  4995.5  208.88    4999  208.88  4999.2  209.38  5028.8  209.52  5059.3  210.02
  5079.6   210.5  5101.4  211.38  5156.7  214.09  5201.3  215.13  5332.9  216.49
    5338  216.37  5393.3  217.35  5398.4  217.24  5514.2  219.46  5596.8  220.37
  5636.2  221.21  5640.1  221.15  5695.4  222.67  5755.9  224.01  5806.4  224.83
#Mann= 4 ,-1 , 0
  4263.1     .17       0  4929.3     .06       0  5101.4     .17       0
  5636.2     .11       0
Bank Sta=4929.3,5101.4
XS Rating Curve= 0 ,0
Exp/Cntr=0.3,0.1

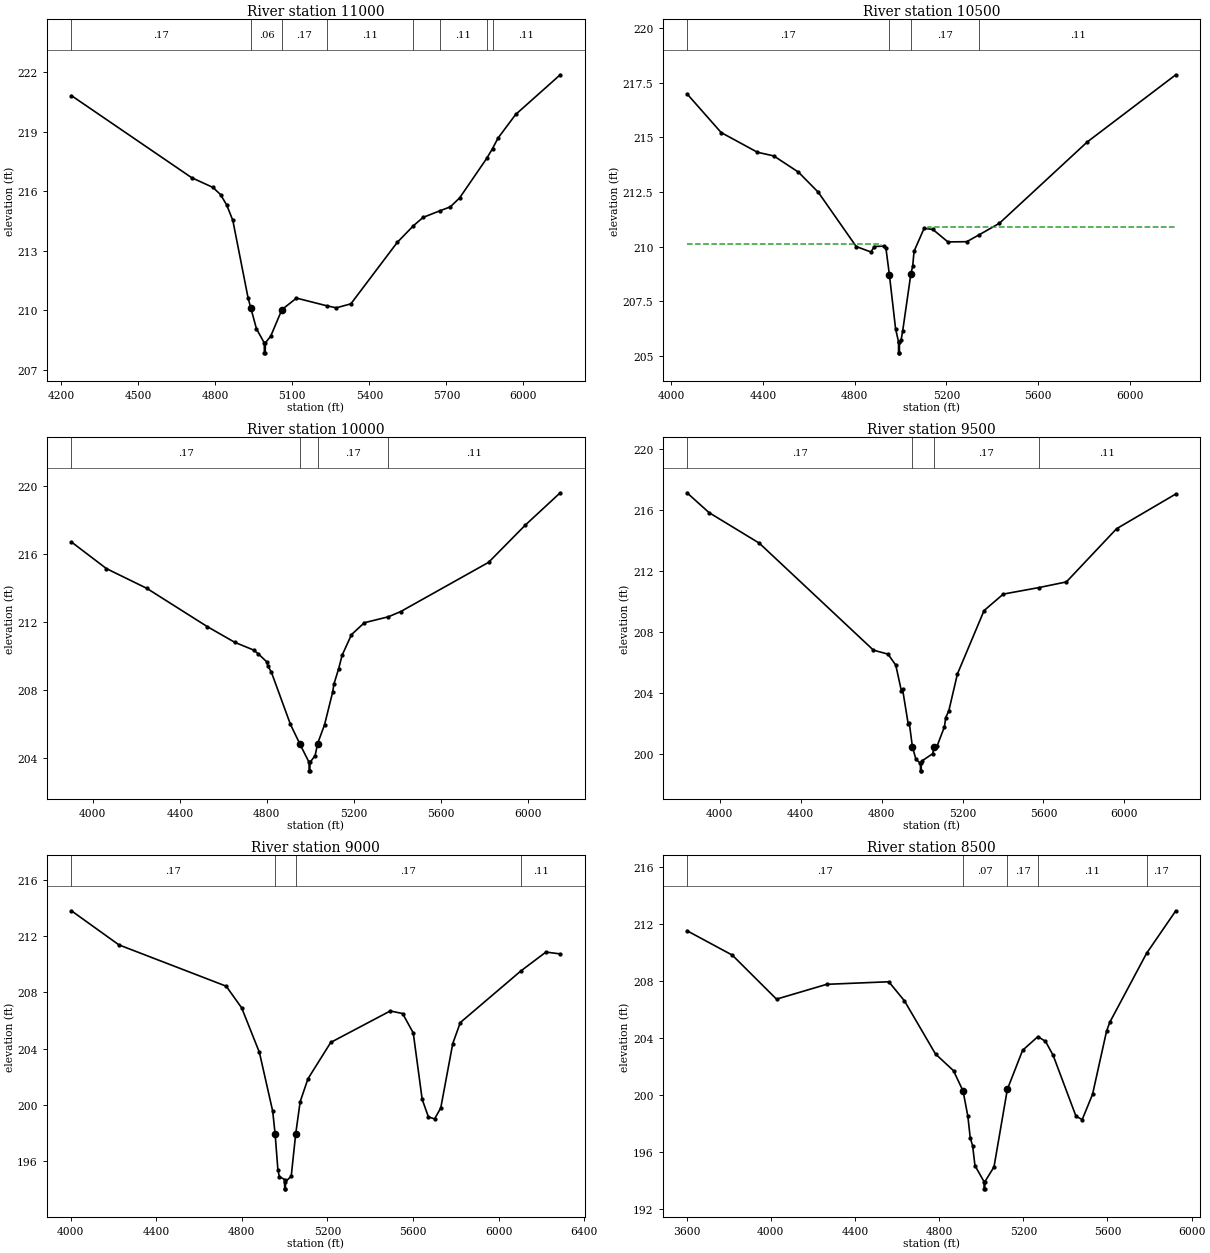
Type RM Length L Ch R = 1 ,11000   ,500,500,500
BEGIN DESCRIPTION:
CRYSTAL CREEK TRIBUTARY NO 3 22.0
END DESCRIPTION:
XS GIS Cut Line= 3
       3861561.3     10125997.64      3861272.84     10125294.51
      3860194.21     10124916.05
#Sta/Elev= 30
    4240  220.82  4708.3  216.68  4791.1  216.19  4820.5  215.83  4844.4  215.31
  4868.4  214.53  4928.1   210.6  4938.9  210.09  4960.5  209.06  4990.9  208.35
  4991.2  207.85  4994.7  207.85  4994.9  208.35  5015.9  208.69  5059.6  210.03
  5116.3  210.61    5235  210.22  5271.3  210.12    5328  210.32  5508.7  213.42
  5571.7  214.26  5609.4  214.68  5674.3  215.01  5715.1  215.21  5751.4  215.66
  5856.7  217.65  5879.6  218.15  5901.1  218.68  5969.7  219.87  6143.1  221.87
#Mann= 8 ,-1 , 0
    4240     .17       0  4938.9     .06       0  5059.6     .17       0
    5235     .11       0  5571.7     .17       0  5674.3     .11       0
  5856.7     .17       0  5879.6     .11       0
Bank Sta=4938.9,5059.6
XS Rating Curve= 0 ,0
Exp/Cntr=0.3,0.1

Type RM Length L Ch R = 1 ,10500   ,500,500,500
BEGIN DESCRIPTION:
CRYSTAL CREEK TRIBUTARY NO 3 21.0
END DESCRIPTION:
XS GIS Cut Line= 3
      3862108.17     10125667.76      3861577.98     10124902.35
      3860519.63     10124335.28
#Sta/Elev= 30
  4068.9  216.99  4217.8  215.22  4375.9  214.32  4447.5  214.15    4555  213.41
  4641.5  212.49  4806.9  210.01  4871.2  209.76    4886  210.01  4928.6  210.03
  4936.7  209.92  4951.6  208.72  4978.6  206.25  4991.5  205.65  4991.7  205.15
  4995.2  205.15  4995.5  205.65  5002.9  205.75  5009.6  206.15  5045.5  208.77
  5053.4  209.12  5059.1  209.79    5103  210.84  5141.2  210.79  5206.9  210.22
    5289  210.23  5343.8  210.55  5431.2  211.07  5814.6  214.79  6200.7  217.86
#Mann= 4 ,-1 , 0
  4068.9     .17       0  4951.6     .09       0  5045.5     .17       0
  5343.8     .11       0
#XS Ineff= 2 , 0
       0  4915.8  210.12  5119.2       0  210.91
Permanent Ineff=
       F       F
Bank Sta=4951.6,5045.5
XS Rating Curve= 0 ,0
Exp/Cntr=0.3,0.1

Type RM Length L Ch R = 1 ,10000   ,500,500,500
BEGIN DESCRIPTION:
CRYSTAL CREEK TRIBUTARY NO 3 20.0
END DESCRIPTION:
XS GIS Cut Line= 3
      3862420.68     10125485.49      3861897.21     10124519.74
      3860897.18     10123953.31
#Sta/Elev= 30
  3901.5  216.72  4062.5  215.15  4247.8  213.99  4526.5  211.73    4652  210.81
  4739.4  210.35  4761.3  210.12  4799.4  209.66  4805.1  209.41  4821.2  209.04
  4908.7  205.97    4953  204.79  4994.4  203.73  4994.6  203.23  4998.1  203.23
  4998.4  203.73  5022.1  204.12  5033.7  204.84  5065.4  205.94  5102.7  207.86
  5108.7  208.35  5130.3  209.24  5146.2  210.04  5189.5  211.26  5248.6  211.96
  5359.1  212.31    5416  212.62    5820  215.52  5987.6   217.7  6149.3  219.62
#Mann= 4 ,-1 , 0
  3901.5     .17       0    4953     .09       0  5033.7     .17       0
  5359.1     .11       0
Bank Sta=4953,5033.7
XS Rating Curve= 0 ,0
Exp/Cntr=0.3,0.1

Type RM Length L Ch R = 1 ,9500    ,500,500,500
BEGIN DESCRIPTION:
CRYSTAL CREEK TRIBUTARY NO 3 19.0
END DESCRIPTION:
XS GIS Cut Line= 3
      3862663.72     10125420.37      3862334.87     10124305.25
      3861262.32     10123654.17
#Sta/Elev= 30
  3837.4  217.14  3946.3  215.84  4195.2  213.83  4759.5  206.81  4831.3  206.55
  4869.9  205.83    4898  204.12  4903.2  204.27  4931.3  201.97  4936.5  202.06
  4952.2  200.46  4969.8  199.64  4991.9  199.39  4992.2  198.89  4995.7  198.89
  4995.9  199.39  4999.6  199.54  5052.7  200.02  5058.5  200.43    5074  200.51
  5110.8  201.79  5116.7  202.38  5132.2  202.83  5174.8  205.25  5306.6  209.41
  5401.6  210.49  5578.6  210.92  5713.7  211.29  5961.8  214.78  6254.7  217.06
#Mann= 4 ,-1 , 0
  3837.4     .17       0  4952.2     .06       0  5058.5     .17       0
  5578.6     .11       0
Bank Sta=4952.2,5058.5
XS Rating Curve= 0 ,0
Exp/Cntr=0.3,0.1

Type RM Length L Ch R = 1 ,9000    ,500,500,500
BEGIN DESCRIPTION:
CRYSTAL CREEK TRIBUTARY NO 3 18.0
END DESCRIPTION:
XS GIS Cut Line= 3
        3863050.     10125159.95      3862794.46     10124197.29
      3862003.99     10123180.76
#Sta/Elev= 30
    4004  213.79    4226  211.37  4727.1  208.44  4799.5   206.9  4882.3  203.74
  4944.4  199.57  4955.6197.9739  4968.7  195.41  4975.4  194.93    5000  194.72
  5000.3  194.06  5003.8  194.06  5004.1  194.56    5031  194.96  5051.8  197.95
  5072.7  200.24  5109.2  201.87  5215.6  204.45  5493.5  206.68  5551.4   206.5
  5601.1  205.12  5642.8  200.41  5671.7  199.17  5700.7  199.02  5729.6   199.8
  5785.7  204.37    5821  205.86  6103.8  209.52    6221  210.86  6287.7  210.73
#Mann= 4 ,-1 , 0
    4004     .17       0  4955.6     .09       0  5051.8     .17       0
  6103.8     .11       0
#XS Ineff= 2 , 0
       0                  5493.5       0  206.68
Permanent Ineff=
       F       F
Bank Sta=4955.6,5051.8
XS Rating Curve= 0 ,0
Exp/Cntr=0.3,0.1

Type RM Length L Ch R = 1 ,8500    ,500,500,500
BEGIN DESCRIPTION:
CRYSTAL CREEK TRIBUTARY NO 3 17.0
END DESCRIPTION:
XS GIS Cut Line= 3
      3863536.12     10125008.04      3862937.81     10123743.88
      3862435.43     10122967.67
#Sta/Elev= 30
  3601.4  211.51  3816.6   209.8  4026.9  206.71  4265.5  207.75  4560.6  207.93
    4635  206.59  4782.6  202.86  4868.1  201.69  4913.6  200.26  4936.3  198.49
  4947.8  196.96  4958.9  196.43  4970.1  195.03  5013.3   193.9  5013.5   193.4
    5017   193.4  5017.3   193.9  5060.6  194.94    5124  200.38  5196.5  203.12
  5269.1  204.08  5305.3  203.75  5341.6  202.77  5450.4  198.49  5479.8  198.26
  5528.9  200.03  5595.5  204.46  5610.7  205.08  5785.6  209.92  5924.6  212.91
#Mann= 5 ,-1 , 0
  3601.4     .17       0  4913.6     .07       0    5124     .17       0
  5269.1     .11       0  5785.6     .17       0
#XS Ineff= 2 , 0
       0                  5269.1       0  204.08
Permanent Ineff=
       F       F
Bank Sta=4913.6,5124
XS Rating Curve= 0 ,0
Exp/Cntr=0.3,0.1

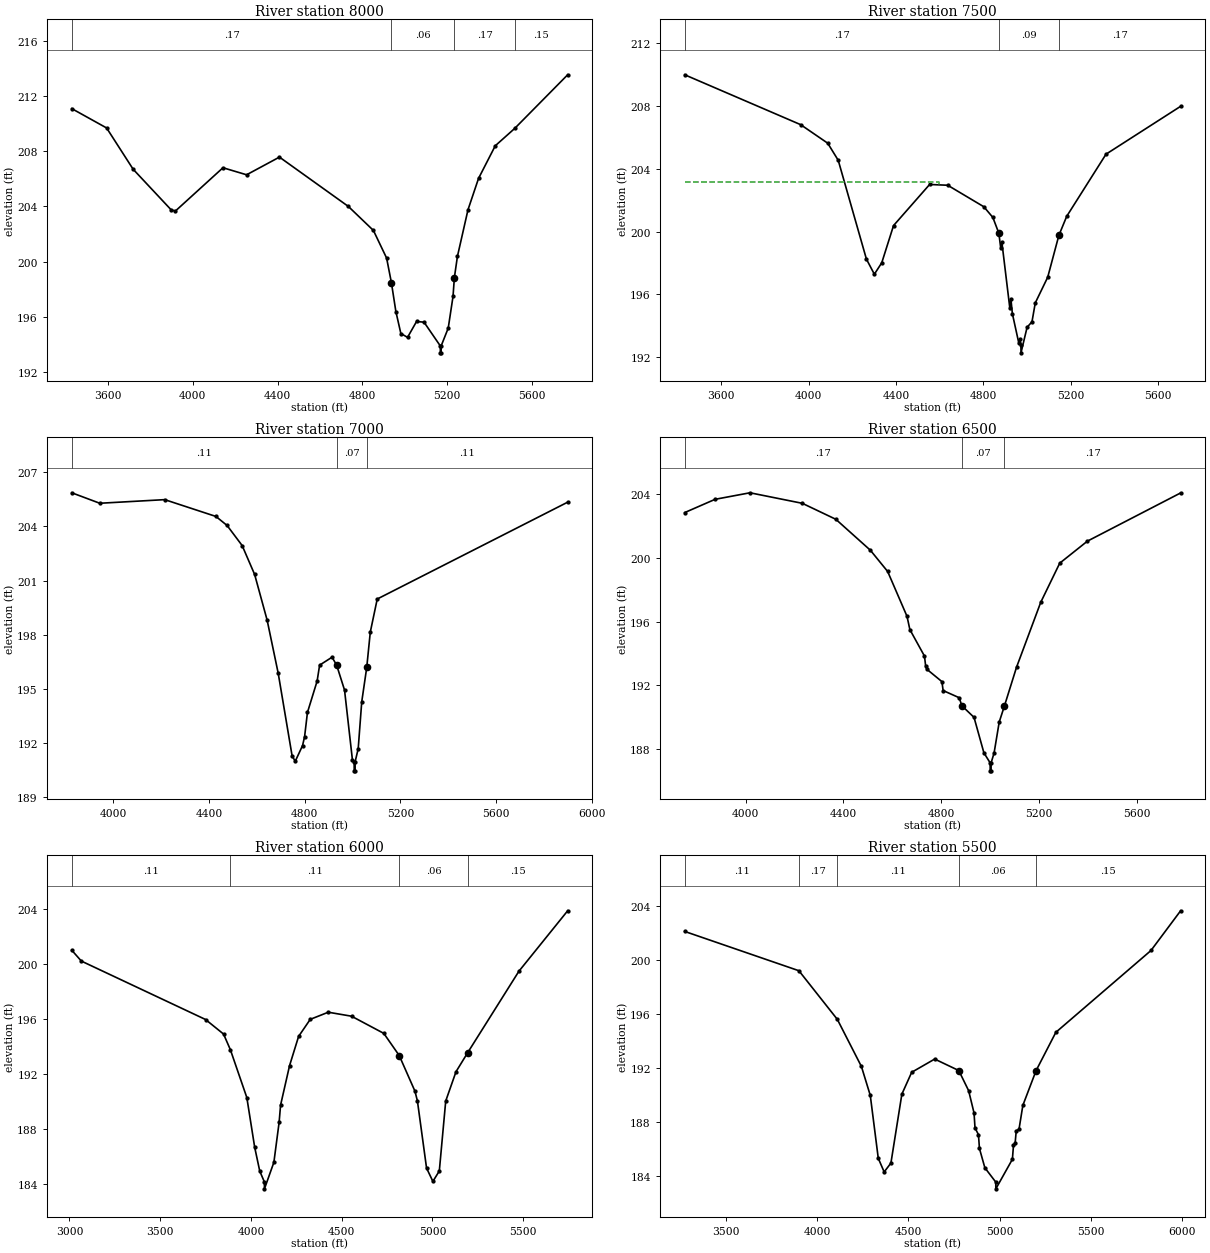
Type RM Length L Ch R = 1 ,8000    ,500,500,500
BEGIN DESCRIPTION:
CRYSTAL CREEK TRIBUTARY NO 3 16.0
END DESCRIPTION:
XS GIS Cut Line= 3
      3863766.14      10124834.4      3863245.83     10123351.64
      3862776.57     10122742.41
#Sta/Elev= 30
  3428.6  211.07    3593  209.67  3718.3  206.68  3898.4  203.73    3918  203.66
  4142.2  206.79  4253.7  206.28  4408.7  207.56  4733.8  203.99  4852.2  202.25
  4914.5  200.25    4937  198.48  4958.2  196.38  4981.7  194.79  5013.3  194.51
  5055.8  195.66  5091.1  195.61  5167.9  193.89  5168.2  193.39  5171.7  193.39
  5171.9  193.89  5205.3  195.18  5227.9  197.47  5234.3  198.84  5248.8  200.38
  5298.6  203.75  5348.4  206.02  5427.3  208.38  5519.3  209.64    5769  213.52
#Mann= 4 ,-1 , 0
  3428.6     .17       0    4937     .06       0  5234.3     .17       0
  5519.3     .15       0
Bank Sta=4937,5234.3
XS Rating Curve= 0 ,0
Exp/Cntr=0.3,0.1

Type RM Length L Ch R = 1 ,7500    ,500,500,500
BEGIN DESCRIPTION:
CRYSTAL CREEK TRIBUTARY NO 3 15.0
END DESCRIPTION:
XS GIS Cut Line= 3
      3864042.86      10124686.1      3863664.51     10123165.26
      3863272.11     10122582.93
#Sta/Elev= 30
  3432.8  209.99  3963.5  206.81  4087.2  205.63  4135.3  204.54  4264.4  198.24
  4300.6  197.28  4334.5  198.01  4388.4  200.38  4553.6     203  4636.3  202.95
  4801.6  201.58  4842.9   200.9  4870.4  199.89  4879.1  198.93  4884.2  199.32
  4920.4  195.14  4925.5  195.71  4932.2  194.77  4961.7  192.89  4966.8  193.16
  4971.4  192.77  4971.7  192.27  4999.6   193.9    5022  194.25    5037  195.45
    5094  197.09  5144.9  199.75  5180.9  200.97  5360.8  204.93  5702.2  207.98
#Mann= 3 , 0 , 0
  3432.8     .17       0  4870.4     .09       0  5144.9     .17       0
#XS Ineff= 2 , 0
       0    4595  203.13               0
Permanent Ineff=
       F       F
Bank Sta=4870.4,5144.9
XS Rating Curve= 0 ,0
Exp/Cntr=0.3,0.1

Type RM Length L Ch R = 1 ,7000    ,500,500,500
BEGIN DESCRIPTION:
CRYSTAL CREEK TRIBUTARY NO 3 14.0
END DESCRIPTION:
XS GIS Cut Line= 3
       3864365.1     10124409.06      3864146.16     10123255.96
      3863632.23     10122517.61
#Sta/Elev= 30
  3826.3  205.86  3943.4  205.28  4214.9  205.48    4429  204.55  4475.7  204.05
  4538.6  202.94  4590.8  201.34  4643.1  198.81  4689.4  195.87  4747.6  191.29
  4760.7     191  4791.2  191.87  4799.8  192.37  4811.6   193.7  4852.1  195.44
  4862.5  196.32  4914.5  196.76  4933.7  196.32  4966.7  194.94  4999.9  191.05
  5006.9  190.97  5007.2  190.47  5010.7  190.47  5010.9  190.97  5023.8  191.69
  5038.6  194.29  5059.5  196.19  5074.4  198.15  5103.4  199.98  5899.6  205.34
#Mann= 3 , 0 , 0
  3826.3     .11       0  4933.7     .07       0  5059.5     .11       0
Bank Sta=4933.7,5059.5
XS Rating Curve= 0 ,0
Exp/Cntr=0.3,0.1

Type RM Length L Ch R = 1 ,6500    ,500,500,500
BEGIN DESCRIPTION:
CRYSTAL CREEK TRIBUTARY NO 3 13.0
END DESCRIPTION:
XS GIS Cut Line= 3
      3864599.47     10124183.33       3864426.3      10122946.7
      3863887.65     10122382.13
#Sta/Elev= 30
  3751.3  202.83  3875.5  203.66  4018.3  204.07  4232.4  203.41  4369.5  202.41
  4510.9  200.47  4581.6  199.14  4660.8  196.33  4672.5   195.5  4732.2  193.84
  4737.3  193.19  4743.1     193  4803.6  192.24  4808.6  191.68  4874.4  191.23
  4885.1  190.73    4935     190  4975.4  187.78  5000.9  187.15  5001.2  186.65
  5004.7  186.65  5004.9  187.15  5017.1  187.77  5038.1  189.71  5059.5  190.72
  5108.9  193.14    5208  197.21  5285.7  199.66  5398.9  201.04  5780.3  204.06
#Mann= 3 , 0 , 0
  3751.3     .17       0  4885.1     .07       0  5059.5     .17       0
Bank Sta=4885.1,5059.5
XS Rating Curve= 0 ,0
Exp/Cntr=0.3,0.1

Type RM Length L Ch R = 1 ,6000    ,500,500,500
BEGIN DESCRIPTION:
CRYSTAL CREEK TRIBUTARY NO 3 12.0
END DESCRIPTION:
XS GIS Cut Line= 3
      3866248.75     10123775.36      3864693.03     10122539.42
      3864167.83     10122011.05
#Sta/Elev= 30
  3013.1  201.01  3065.9  200.22    3750  195.97  3849.3  194.91  3886.9  193.77
  3977.5  190.29  4020.8  186.67  4048.7  184.94  4074.2  184.15  4074.6  183.65
  4126.5  185.58  4155.3  188.48  4163.4  189.74    4213  192.62  4262.7  194.74
  4326.8  195.98  4426.1   196.5  4554.2  196.21  4732.1  194.96    4817  193.35
  4903.5  190.76  4917.2  190.05  4967.6  185.16  5002.5  184.19  5037.9  184.95
  5073.2  190.04  5129.8  192.17  5193.4  193.54  5476.3  199.48    5745  203.88
#Mann= 4 ,-1 , 0
  3013.1     .11       0  3886.9     .11       0    4817     .06       0
  5193.4     .15       0
#XS Ineff= 2 , 0
       0  4432.5  196.46               0
Permanent Ineff=
       F       F
Bank Sta=4817,5193.4
XS Rating Curve= 0 ,0
Exp/Cntr=0.3,0.1

Type RM Length L Ch R = 1 ,5500    ,500,500,500
BEGIN DESCRIPTION:
CRYSTAL CREEK TRIBUTARY NO 3 11.0
END DESCRIPTION:
XS GIS Cut Line= 3
      3866752.23     10123054.89      3865150.01     10122414.67
      3864322.24     10121870.35
#Sta/Elev= 30
  3274.6  202.09    3900  199.18  4110.4  195.58  4242.4  192.09  4290.9  189.95
  4334.7  185.29    4367  184.28    4404  184.94  4463.9  190.04  4517.7  191.66
  4643.7  192.64  4775.7  191.79  4829.6   190.3  4859.2  188.65  4864.6  187.54
  4883.5  187.04  4888.8  186.02  4918.5  184.59  4978.2  183.53  4978.6  183.03
  5069.3  185.22  5075.3  186.25  5084.4  186.43  5090.4  187.33  5105.5  187.44
  5126.6  189.21  5198.9  191.78  5307.3  194.62  5828.4  200.68  5990.7  203.62
#Mann= 5 ,-1 , 0
  3274.6     .11       0    3900     .17       0  4110.4     .11       0
  4775.7     .06       0  5198.9     .15       0
#XS Ineff= 2 , 0
       0  4643.7  192.64               0
Permanent Ineff=
       F       F
Bank Sta=4775.7,5198.9
XS Rating Curve= 0 ,0
Exp/Cntr=0.3,0.1

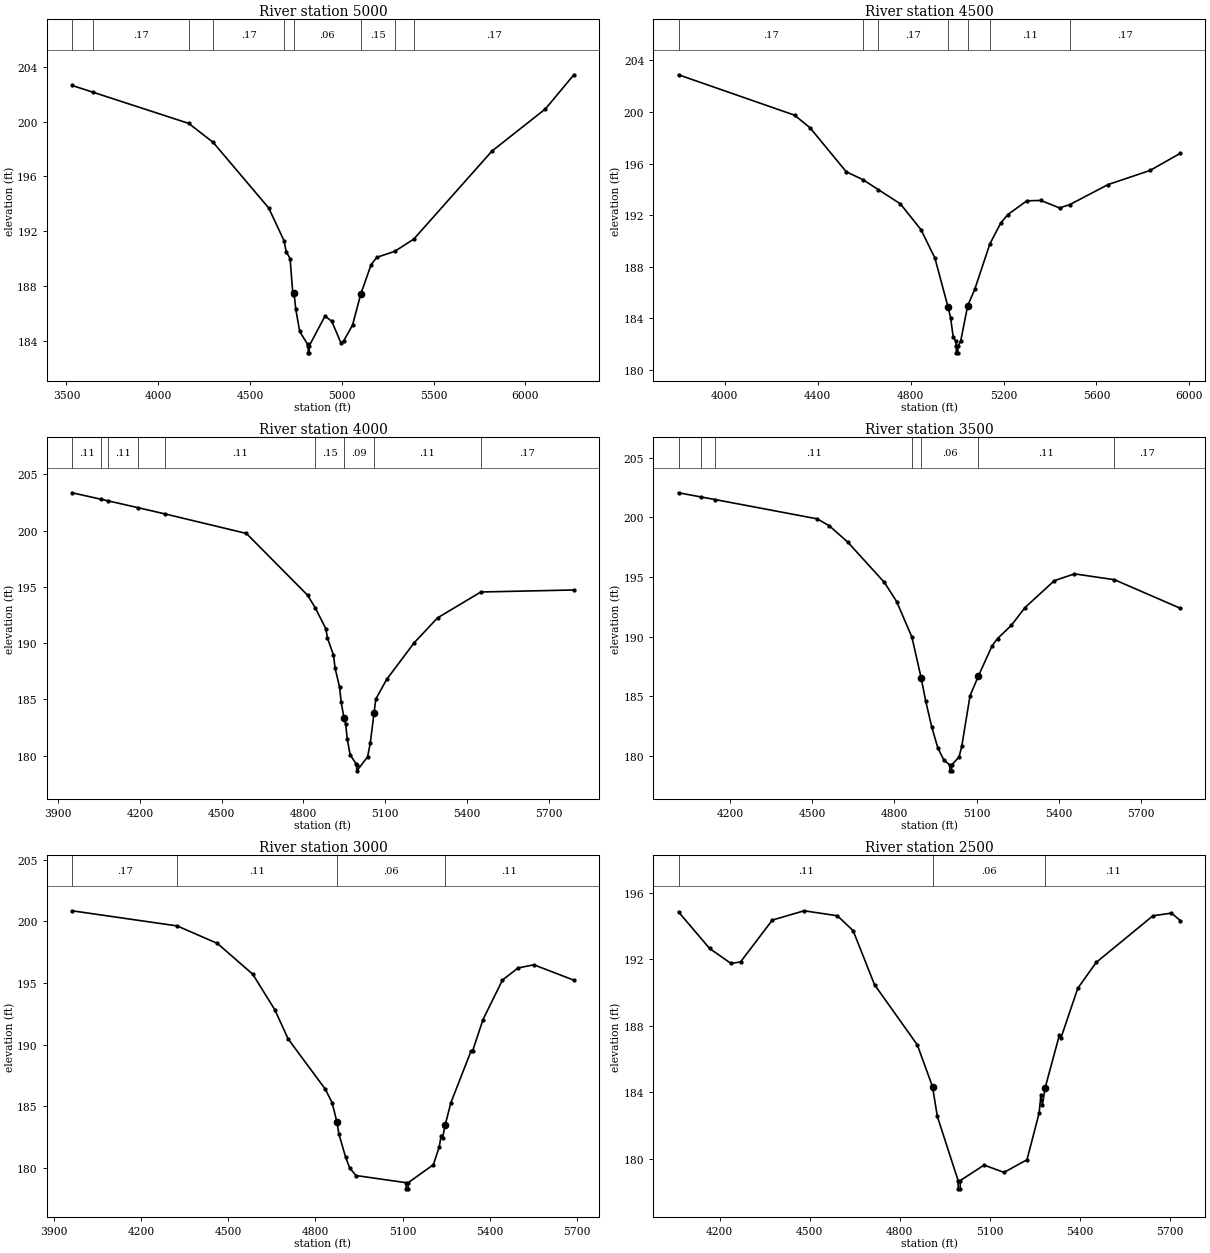
Type RM Length L Ch R = 1 ,5000    ,500,500,500
BEGIN DESCRIPTION:
CRYSTAL CREEK TRIBUTARY NO 3 10.0
END DESCRIPTION:
XS GIS Cut Line= 3
      3866839.07     10122942.05       3865583.8     10122178.99
      3864392.05     10121757.47
#Sta/Elev= 30
    3531  202.64  3644.2  202.15  4166.4  199.87  4299.8  198.48  4602.3  193.69
  4685.6   191.3  4697.2  190.51  4718.5     190    4734  187.35  4739.9  187.51
  4749.5   186.3  4770.8  184.68  4813.5  183.75  4817.1  183.62  4817.5  183.12
    4822  183.12  4822.4  183.62  4908.4   185.8  4945.2  185.43  4994.7  183.87
  5010.2  183.98  5059.3  185.17  5102.9  187.39  5159.4  189.54  5190.3  190.09
  5288.7  190.53    5392  191.42  5818.1  197.85  6109.4  200.93  6264.1  203.42
#Mann= 9 ,-1 , 0
    3531     .11       0  3644.2     .17       0  4166.4     .11       0
  4299.8     .17       0  4685.6     .15       0  4739.9     .06       0
  5102.9     .15       0  5288.7     .11       0    5392     .17       0
Bank Sta=4739.9,5102.9
XS Rating Curve= 0 ,0
Exp/Cntr=0.3,0.1

Type RM Length L Ch R = 1 ,4500    ,500,500,500
BEGIN DESCRIPTION:
CRYSTAL CREEK TRIBUTARY NO 3 9.0
END DESCRIPTION:
XS GIS Cut Line= 3
      3866970.97     10122342.16      3865903.01     10121796.04
      3864955.29      10121633.8
#Sta/Elev= 30
  3800.5  202.87  4300.4  199.74  4367.1  198.76  4522.8  195.36  4595.6  194.74
  4661.3  193.97  4755.7  192.88  4844.6  190.88  4904.7  188.67  4961.2  184.88
  4972.1  184.07  4983.5  182.55  4994.4  182.24  4996.4  181.84  4996.9  181.34
    5003  181.34  5003.5  181.84  5015.4  182.23  5045.8  184.99  5076.2  186.26
  5141.2  189.77  5187.8  191.38  5218.3  192.04  5300.3  193.11  5360.4  193.14
  5441.5  192.56  5485.7  192.82  5650.6  194.37  5830.8  195.46  5961.5  196.79
#Mann= 7 ,-1 , 0
  3800.5     .17       0  4595.6     .11       0  4661.3     .17       0
  4961.2     .09       0  5045.8     .15       0  5141.2     .11       0
  5485.7     .17       0
Bank Sta=4961.2,5045.8
XS Rating Curve= 0 ,0
Exp/Cntr=0.3,0.1

Type RM Length L Ch R = 1 ,4000    ,500,500,500
BEGIN DESCRIPTION:
CRYSTAL CREEK TRIBUTARY NO 3 8.0
END DESCRIPTION:
XS GIS Cut Line= 3
       3867117.9     10121861.09      3866183.37     10121385.47
      3865394.77     10121305.88
#Sta/Elev= 30
  3951.4  203.35  4058.8  202.77  4084.1  202.63  4192.8  202.03  4293.1  201.47
    4591  199.74  4815.4  194.26  4844.4  193.11  4882.8  191.26  4888.4  190.45
  4910.6  188.94  4916.4  187.79  4932.9  186.09  4938.9  184.75  4949.5  183.32
  4955.1  182.84  4961.3  181.46  4971.8  180.08    4994  179.27  4995.7  179.16
  4996.2  178.66  5035.7   179.9  5045.7  181.13 5059.23183.7552  5065.8  185.03
  5106.1  186.79  5206.6  190.03  5292.4  192.24  5451.2  194.54  5792.6  194.72
#Mann= 9 ,-1 , 0
  3951.4     .11       0  4058.8     .17       0  4084.1     .11       0
  4192.8     .17       0  4293.1     .11       0  4844.4     .15       0
  4949.5     .09       0 5059.23     .11       0  5451.2     .17       0
Bank Sta=4949.5,5059.23
XS Rating Curve= 0 ,0
Exp/Cntr=0.3,0.1

Type RM Length L Ch R = 1 ,3500    ,500,500,500
BEGIN DESCRIPTION:
CRYSTAL CREEK TRIBUTARY NO 3 7.0
END DESCRIPTION:
XS GIS Cut Line= 3
      3867236.58     10121362.98      3866353.99     10120918.71
      3865512.71     10120847.36
#Sta/Elev= 30
  4011.9  202.07  4093.8  201.72  4145.6   201.5  4518.2  199.88  4562.8  199.29
  4629.8  197.93  4763.7  194.54  4808.3  192.94    4864  189.96  4897.6  186.55
  4914.3   184.6  4936.6  182.39  4958.9  180.64  4981.3   179.6  5002.5  179.22
    5003  178.72  5009.3  178.72  5009.8  179.22  5036.3  179.89  5046.3   180.8
  5076.4  185.03  5106.5  186.66  5156.7  189.21  5176.8  189.83  5226.9  190.93
  5277.1  192.43  5384.3  194.69  5457.8  195.26  5603.8  194.77  5844.3  192.37
#Mann= 7 ,-1 , 0
  4011.9     .15       0  4093.8     .17       0  4145.6     .11       0
    4864     .17       0  4897.6     .06       0  5106.5     .11       0
  5603.8     .17       0
Bank Sta=4897.6,5106.5
XS Rating Curve= 0 ,0
Exp/Cntr=0.3,0.1

Type RM Length L Ch R = 1 ,3000    ,500,500,500
BEGIN DESCRIPTION:
CRYSTAL CREEK TRIBUTARY NO 3 6.0
END DESCRIPTION:
XS GIS Cut Line= 3
      3867371.94     10120847.33      3866423.16     10120428.27
      3865736.56     10120362.97
#Sta/Elev= 30
  3962.8  200.87  4324.2  199.64  4462.8  198.22  4584.8  195.71  4660.2  192.84
  4706.8  190.44  4834.3  186.37  4857.6  185.28  4874.6  183.67  4880.9  182.75
  4904.2  180.84  4918.3  179.96  4940.2  179.35  5112.1  178.77  5112.6  178.27
    5119  178.27  5119.5  178.77  5206.2  180.23  5226.3  181.67  5232.9  182.58
  5237.9  182.42  5246.4  183.42  5266.5  185.27    5336  189.48    5341  189.46
    5377  192.03    5444  195.24  5497.5  196.22  5552.1  196.48  5689.7  195.23
#Mann= 4 ,-1 , 0
  3962.8     .17       0  4324.2     .11       0  4874.6     .06       0
  5246.4     .11       0
Bank Sta=4874.6,5246.4
XS Rating Curve= 0 ,0
Exp/Cntr=0.3,0.1

Type RM Length L Ch R = 1 ,2500    ,500,500,500
BEGIN DESCRIPTION:
CRYSTAL CREEK TRIBUTARY NO 3 5.0
END DESCRIPTION:
XS GIS Cut Line= 3
      3867439.66     10120112.97       3866518.2     10119942.46
      3865793.82     10120060.89
#Sta/Elev= 30
  4062.9  194.86  4166.4  192.66  4237.6  191.76  4269.4  191.85  4375.3  194.37
  4481.1  194.93    4592  194.63  4644.4  193.73  4715.6  190.48    4858  186.86
  4908.8  184.34  4924.6  182.56  4993.9  178.69  4994.4  178.19  5000.8  178.19
  5001.3  178.69  5080.4  179.62  5146.8  179.18  5223.3  179.94  5263.8  182.75
  5269.6  183.83  5274.7  183.26  5284.1  184.29    5331  187.43    5336  187.25
  5392.4  190.26  5453.7  191.82    5643  194.63  5704.4  194.79    5734  194.34
#Mann= 3 , 0 , 0
  4062.9     .11       0  4908.8     .06       0  5284.1     .11       0
Bank Sta=4908.8,5284.1
XS Rating Curve= 0 ,0
Exp/Cntr=0.3,0.1

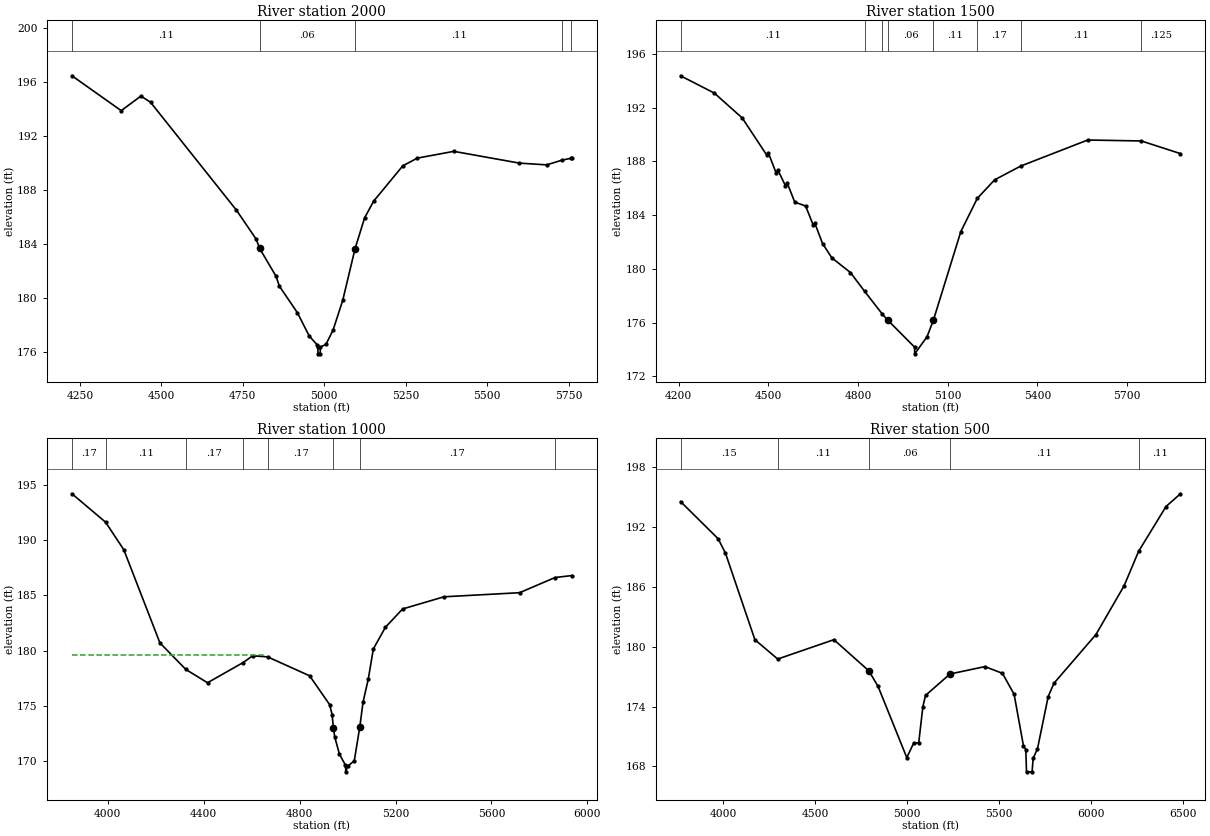
Type RM Length L Ch R = 1 ,2000    ,500,500,500
BEGIN DESCRIPTION:
CRYSTAL CREEK TRIBUTARY NO 3 4.0
END DESCRIPTION:
XS GIS Cut Line= 3
      3867215.76     10119331.72      3866452.14     10119459.87
      3865772.97     10119800.49
#Sta/Elev= 30
  4225.7  196.46  4376.8  193.88  4437.4  194.96  4466.9   194.5  4730.4  186.52
  4791.1  184.37  4801.6  183.69  4851.7  181.64  4862.4  180.89  4917.4  178.94
  4953.6  177.22    4978  176.56  4980.3  176.39  4980.8  175.89  4987.4  175.89
  4987.9  176.39  5005.2  176.59  5027.2  177.66  5056.8  179.86  5094.3  183.65
  5123.8  185.95  5151.7  187.19  5241.1   189.8  5285.8  190.37  5397.5  190.87
  5598.6     190  5682.3  189.87    5730  190.22  5755.8  190.35  5759.8  190.35
#Mann= 5 ,-1 , 0
  4225.7     .11       0  4801.6     .06       0  5094.3     .11       0
    5730    .125       0  5755.8     .11       0
Bank Sta=4801.6,5094.3
XS Rating Curve= 0 ,0
Exp/Cntr=0.3,0.1

Type RM Length L Ch R = 1 ,1500    ,500,500,500
BEGIN DESCRIPTION:
CRYSTAL CREEK TRIBUTARY NO 3 3.0
END DESCRIPTION:
XS GIS Cut Line= 3
      3866970.93     10118769.22      3866221.25      10119030.8
      3865612.23     10119664.35
#Sta/Elev= 30
    4206  194.37  4319.2  193.08  4412.4  191.23    4495  188.45  4500.2  188.61
    4526  187.13  4531.3  187.38  4557.1  186.18  4562.4  186.42  4588.1  184.97
  4624.5  184.68  4650.3  183.24  4655.6  183.39  4681.3  181.88  4712.4  180.82
  4774.5  179.73    4822  178.33  4881.8  176.62  4898.8   176.2  4989.1  174.18
  4989.6  173.68  5030.8  174.95  5052.2  176.19    5144  182.78  5199.1  185.25
  5257.2  186.63  5344.2  187.65  5568.5  189.59  5747.9  189.52  5878.8  188.58
#Mann= 8 ,-1 , 0
    4206     .11       0    4822     .17       0  4881.8     .11       0
  4898.8     .06       0  5052.2     .11       0  5199.1     .17       0
  5344.2     .11       0  5747.9    .125       0
Bank Sta=4898.8,5052.2
XS Rating Curve= 0 ,0
Exp/Cntr=0.3,0.1

Type RM Length L Ch R = 1 ,1000    ,500,500,500
BEGIN DESCRIPTION:
CRYSTAL CREEK TRIBUTARY NO 3 2.0
END DESCRIPTION:
XS GIS Cut Line= 3
      3866929.23     10118519.23      3865804.64     10118758.24
      3865267.83      10119524.4
#Sta/Elev= 30
  3850.3  194.17  3990.2  191.61  4066.4  189.12  4217.3  180.69  4325.1   178.3
  4415.7  177.09  4564.6  178.92  4603.9  179.53  4666.3  179.43  4841.7  177.72
  4925.2  175.11  4935.4  174.22    4941  173.02  4946.1  172.22  4966.1  170.63
  4990.6  169.67  4991.9  169.54  4992.4  169.04  4999.7  169.54  5027.9  170.03
  5050.8  173.08  5064.5  175.33  5086.5  177.44  5107.5  180.15    5158  182.11
  5229.5  183.76  5402.1  184.86  5717.7  185.23  5865.2   186.6  5935.5  186.78
#Mann= 8 ,-1 , 0
  3850.3     .17       0  3990.2     .11       0  4325.1     .17       0
  4564.6     .11       0  4666.3     .17       0    4941     .09       0
  5050.8     .17       0  5865.2     .11       0
#XS Ineff= 2 , 0
       0  4648.4  179.63               0
Permanent Ineff=
       F       F
Bank Sta=4941,5050.8
XS Rating Curve= 0 ,0
Exp/Cntr=0.3,0.1

Type RM Length L Ch R = 1 ,500     ,0,0,0
BEGIN DESCRIPTION:
CRYSTAL CREEK TRIBUTARY NO 3 1.0
END DESCRIPTION:
XS GIS Cut Line= 3
      3866882.37     10118321.31      3865649.67     10118325.23
      3864236.56     10118790.05
#Sta/Elev= 30
  3767.3  194.56  3971.8  190.83  4011.8  189.38  4171.8  180.71    4296  178.77
  4601.8  180.71  4791.8  177.59  4841.8  176.04  4998.4  168.89  5036.7  170.37
  5063.3  170.36  5086.1  174.01  5100.3  175.12  5233.5  177.27  5423.5  178.01
  5518.9  177.34  5582.5  175.24  5633.5  170.06  5646.1  169.69    5650  167.46
  5680.3  167.46  5686.2  168.82  5709.6  169.76    5768  175.01  5799.7  176.35
  6027.6  181.22    6181  186.11  6260.1  189.57  6409.1  194.06  6487.6  195.34
#Mann= 5 ,-1 , 0
  3767.3     .15       0    4296     .11       0  4791.8     .06       0
  5233.5     .11       0  6260.1     .11       0
Bank Sta=4791.8,5233.5
XS Rating Curve= 0 ,0
Exp/Cntr=0.3,0.1

Chan Stop Cuts=-1
Use User Specified Reach Order=0
Composite Channel Slope=5

--- CRYSTAL CREEK TRIBUTARY NO 3.g10 (geometry) ---

Geom Title=Existing Conditions
Program Version=4.10

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
River Reach=CRYSTAL CREEK TR,Reach-1