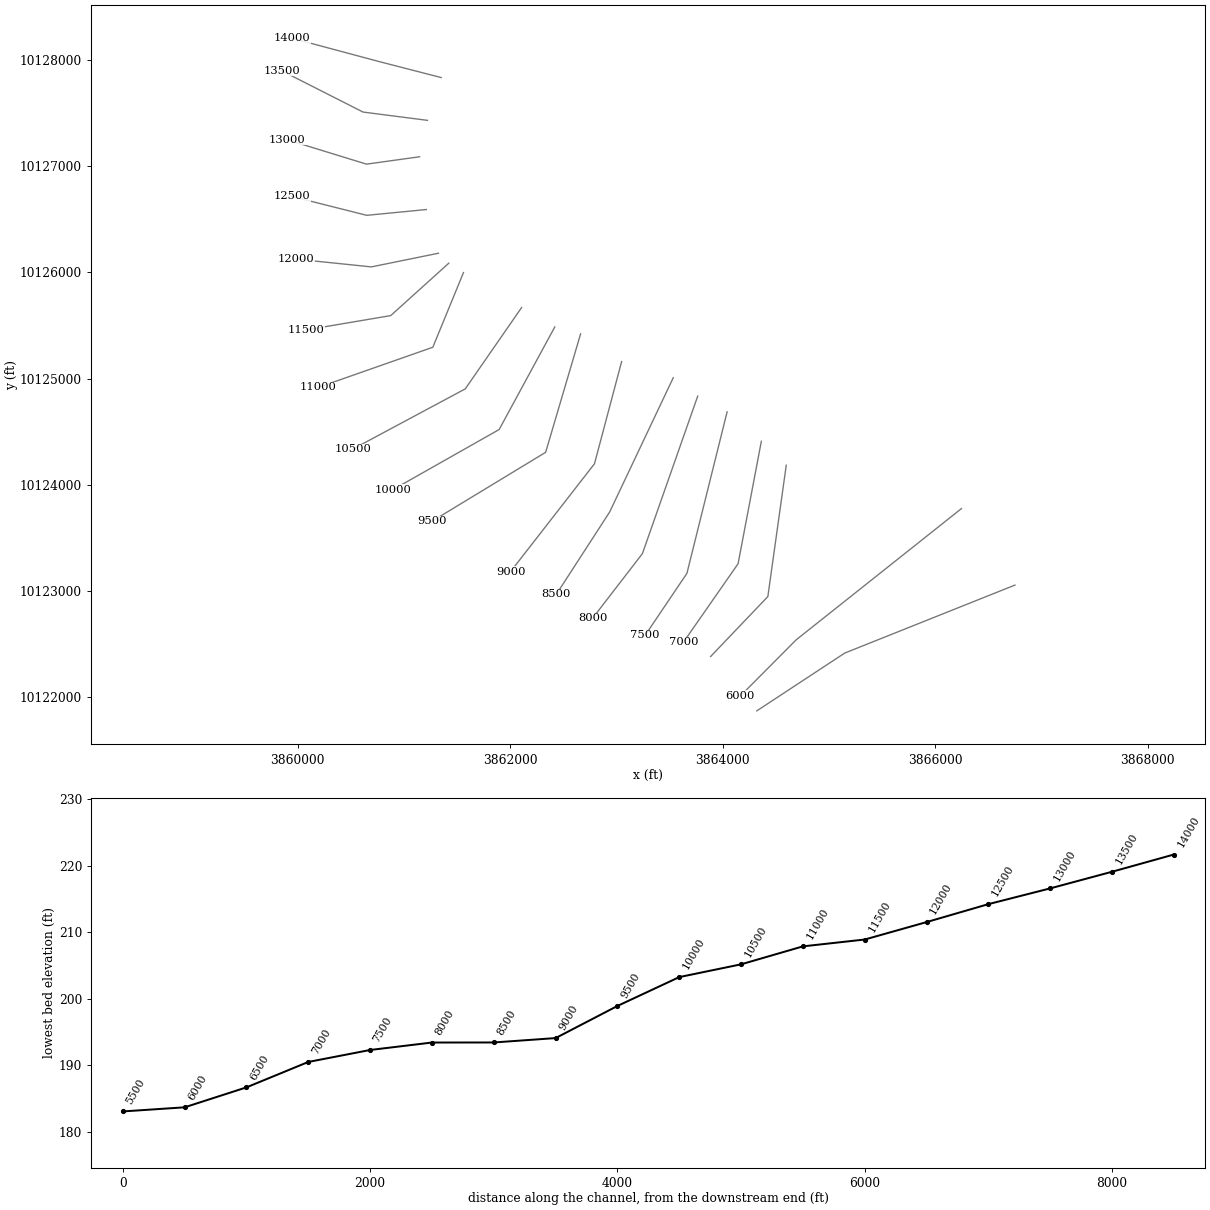
HEC-RAS study CRYSTAL CREEK TRIBUTARY NO 3.prj: CRYSTAL CREEK TRIBUTARY NO 3 Base Level Engineering

--- CRYSTAL CREEK TRIBUTARY NO 3.g10 (geometry) --- (continued)

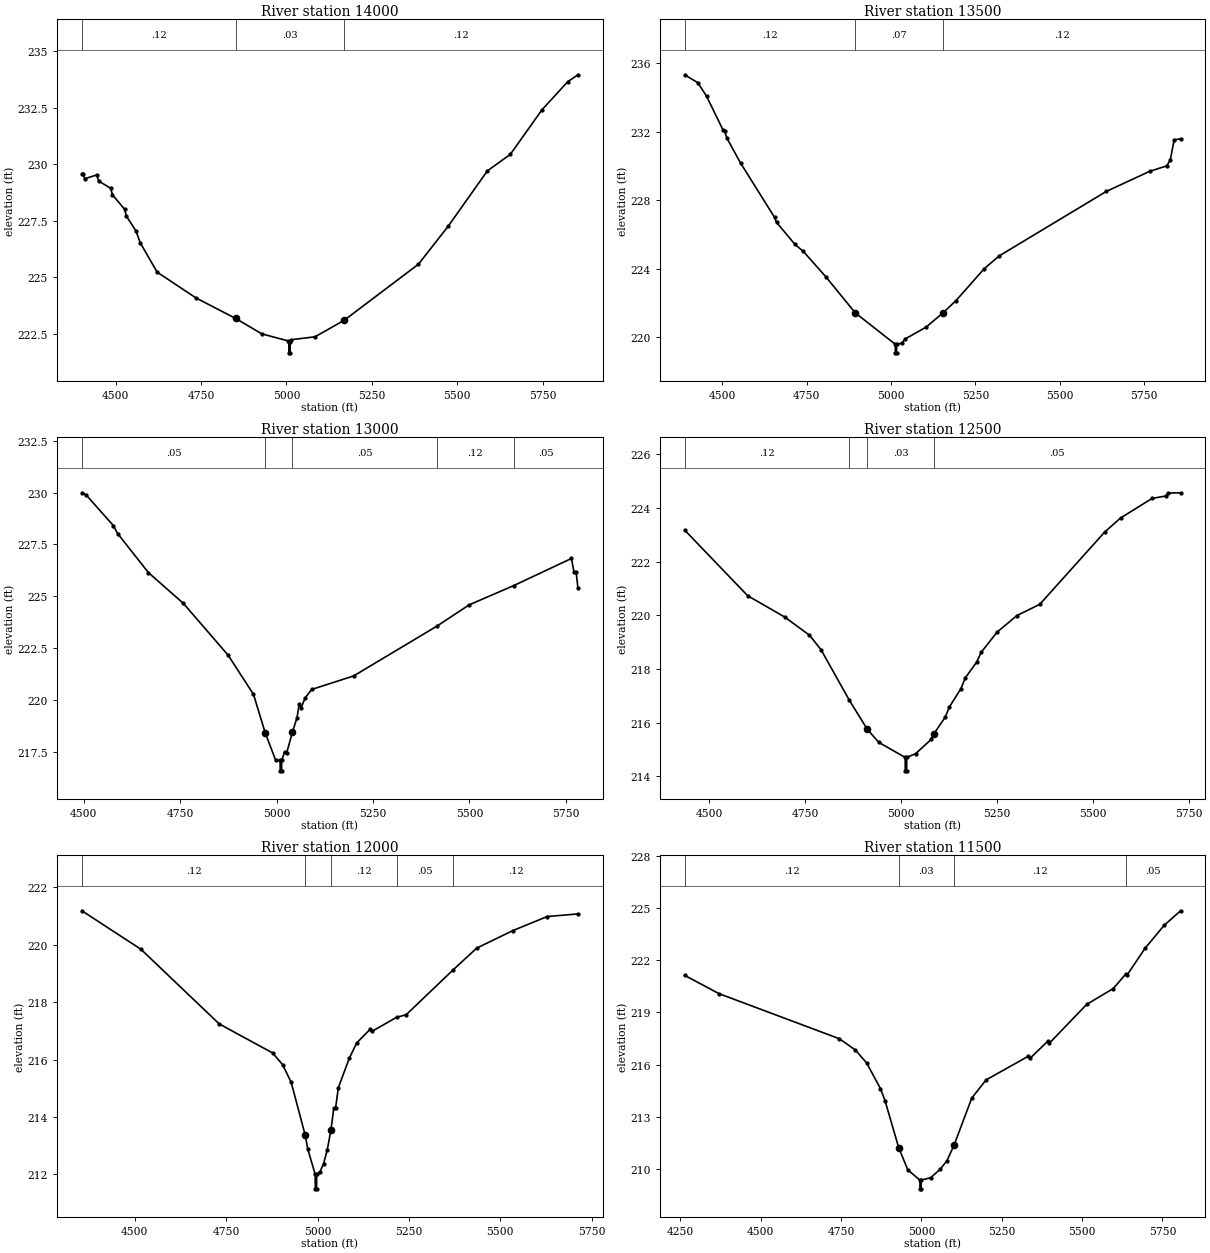
Type RM Length L Ch R = 1 ,14000   ,500,500,500
BEGIN DESCRIPTION:
CRYSTAL CREEK TRIBUTARY NO 3 28.0
END DESCRIPTION:
XS GIS Cut Line= 3
       3861351.2     10127834.18      3860771.07     10127983.74
      3859946.65     10128204.65
#Sta/Elev= 30
  4400.9  229.59  4404.7  229.59    4409  229.36  4444.5  229.53  4449.7  229.26
  4485.2  228.94  4490.4  228.65  4525.9  228.01  4531.1  227.71  4559.3  227.05
  4571.7  226.53  4621.2  225.23  4734.8  224.09  4851.3  223.18  4927.6   222.5
  5004.3  222.19  5006.8  222.16    5007  221.66  5010.5  221.66  5010.8  222.16
  5013.9  222.24  5083.6  222.37    5169   223.1  5386.4  225.58  5473.5  227.26
  5588.4  229.71  5655.6  230.44  5748.7  232.42  5823.4  233.65  5853.5  233.96
#Mann= 3 , 0 , 0
  4400.9     .12       0  4851.3     .03       0    5169     .12       0
Bank Sta=4851.3,5169
XS Rating Curve= 0 ,0
Exp/Cntr=0.3,0.1

Type RM Length L Ch R = 1 ,13500   ,500,500,500
BEGIN DESCRIPTION:
CRYSTAL CREEK TRIBUTARY NO 3 27.0
END DESCRIPTION:
XS GIS Cut Line= 3
      3861222.31      10127431.2      3860615.92     10127509.32
      3859850.78     10127897.78
#Sta/Elev= 30
  4388.6  235.33  4427.6  234.87  4453.6  234.08    4502  232.12    4507  232.03
  4514.1  231.62  4554.4  230.17  4655.2  226.99  4660.9   226.7  4715.7  225.41
  4740.4     225  4806.5  223.53  4894.2  221.41  5012.8  219.57    5013  219.07
  5016.5  219.07  5016.8  219.57  5031.4  219.63  5042.7  219.89  5103.8  220.57
  5154.8  221.42  5192.9  222.13  5276.3  223.99  5320.8  224.74  5638.1  228.51
    5766  229.68  5816.5     230  5827.2  230.33    5839  231.52  5858.1  231.59
#Mann= 3 , 0 , 0
  4388.6     .12       0  4894.2     .07       0  5154.8     .12       0
Bank Sta=4894.2,5154.8
XS Rating Curve= 0 ,0
Exp/Cntr=0.3,0.1

Type RM Length L Ch R = 1 ,13000   ,500,500,500
BEGIN DESCRIPTION:
CRYSTAL CREEK TRIBUTARY NO 3 26.0
END DESCRIPTION:
XS GIS Cut Line= 3
       3861148.5     10127088.32      3860648.52     10127018.76
      3859901.78     10127248.57
#Sta/Elev= 30
  4495.2  229.99    4506  229.89  4576.6  228.41  4587.9  228.02  4667.5  226.14
  4758.4  224.65  4874.4  222.15  4940.1  220.26  4970.4  218.41  4997.8  217.07
  5009.2  217.07  5009.4  216.57  5012.9  216.57  5013.2  217.07  5020.6  217.48
  5025.9  217.42 5040.93  218.43    5053  219.14  5058.5  219.78  5063.8  219.62
  5073.9  220.09  5091.2   220.5  5199.8  221.15  5416.2  223.56  5499.2  224.58
  5614.8  225.51  5764.5  226.82  5771.3  226.15  5776.5  226.18  5781.3  225.39
#Mann= 5 ,-1 , 0
  4495.2     .05       0  4970.4     .07       0 5040.93     .05       0
  5416.2     .12       0  5614.8     .05       0
Bank Sta=4970.4,5040.93
XS Rating Curve= 0 ,0
Exp/Cntr=0.3,0.1

Type RM Length L Ch R = 1 ,12500   ,500,500,500
BEGIN DESCRIPTION:
CRYSTAL CREEK TRIBUTARY NO 3 25.0
END DESCRIPTION:
XS GIS Cut Line= 3
      3861211.49     10126591.36      3860650.74     10126536.77
      3859944.08     10126715.06
#Sta/Elev= 30
  4436.6  223.18    4601  220.73    4697  219.94  4761.8  219.26  4791.9  218.72
  4865.9  216.83  4912.5  215.75  4942.6  215.26  5011.3   214.7  5011.5   214.2
    5015   214.2  5015.3   214.7  5038.5  214.84  5079.6  215.38  5085.5  215.57
  5115.5   216.2  5126.7  216.59  5156.6  217.27    5168  217.67  5197.7  218.26
  5209.2  218.62  5250.5  219.37  5302.1  219.99  5361.9  220.41  5531.3  223.11
  5572.4  223.63  5654.5  224.36  5690.4  224.45  5695.6  224.56  5728.8  224.57
#Mann= 4 ,-1 , 0
  4436.6     .12       0  4865.9     .05       0  4912.5     .03       0
  5085.5     .05       0
Bank Sta=4912.5,5085.5
XS Rating Curve= 0 ,0
Exp/Cntr=0.3,0.1

Type RM Length L Ch R = 1 ,12000   ,500,500,500
BEGIN DESCRIPTION:
CRYSTAL CREEK TRIBUTARY NO 3 24.0
END DESCRIPTION:
XS GIS Cut Line= 3
      3861326.08     10126179.91      3860694.46     10126051.21
      3859985.72     10126124.35
#Sta/Elev= 30
  4355.4  221.18  4516.9  219.84  4731.2  217.24  4877.3  216.23  4904.7  215.82
  4927.9  215.21  4965.9  213.39  4973.3  212.89  4993.7     212    4994   211.5
  4997.5   211.5  4997.7     212  5006.6  212.09  5016.7  212.38  5026.7  212.86
  5036.8  213.55  5044.6  214.32  5049.6  214.32  5056.9  215.02  5087.1  216.05
  5107.2  216.58  5143.6  217.05  5148.6  216.98  5216.2  217.47  5242.5  217.56
  5371.6  219.13  5435.5  219.88  5534.4  220.49  5628.4  220.98  5712.5  221.07
#Mann= 5 ,-1 , 0
  4355.4     .12       0  4965.9     .07       0  5036.8     .12       0
  5216.2     .05       0  5371.6     .12       0
Bank Sta=4965.9,5036.8
XS Rating Curve= 0 ,0
Exp/Cntr=0.3,0.1

Type RM Length L Ch R = 1 ,11500   ,500,500,500
BEGIN DESCRIPTION:
CRYSTAL CREEK TRIBUTARY NO 3 23.0
END DESCRIPTION:
XS GIS Cut Line= 3
      3861423.28     10126086.17      3860876.29     10125592.38
      3860081.18     10125457.96
#Sta/Elev= 30
  4263.1  221.13  4369.6  220.08  4744.7  217.49  4794.8  216.84  4829.9  216.09
  4872.5  214.63  4886.7  213.94  4929.3  211.24  4957.5  209.97  4995.2  209.38
  4995.5  208.88    4999  208.88  4999.2  209.38  5028.8  209.52  5059.3  210.02
  5079.6   210.5  5101.4  211.38  5156.7  214.09  5201.3  215.13  5332.9  216.49
    5338  216.37  5393.3  217.35  5398.4  217.24  5514.2  219.46  5596.8  220.37
  5636.2  221.21  5640.1  221.15  5695.4  222.67  5755.9  224.01  5806.4  224.83
#Mann= 4 ,-1 , 0
  4263.1     .12       0  4929.3     .03       0  5101.4     .12       0
  5636.2     .05       0
Bank Sta=4929.3,5101.4
XS Rating Curve= 0 ,0
Exp/Cntr=0.3,0.1

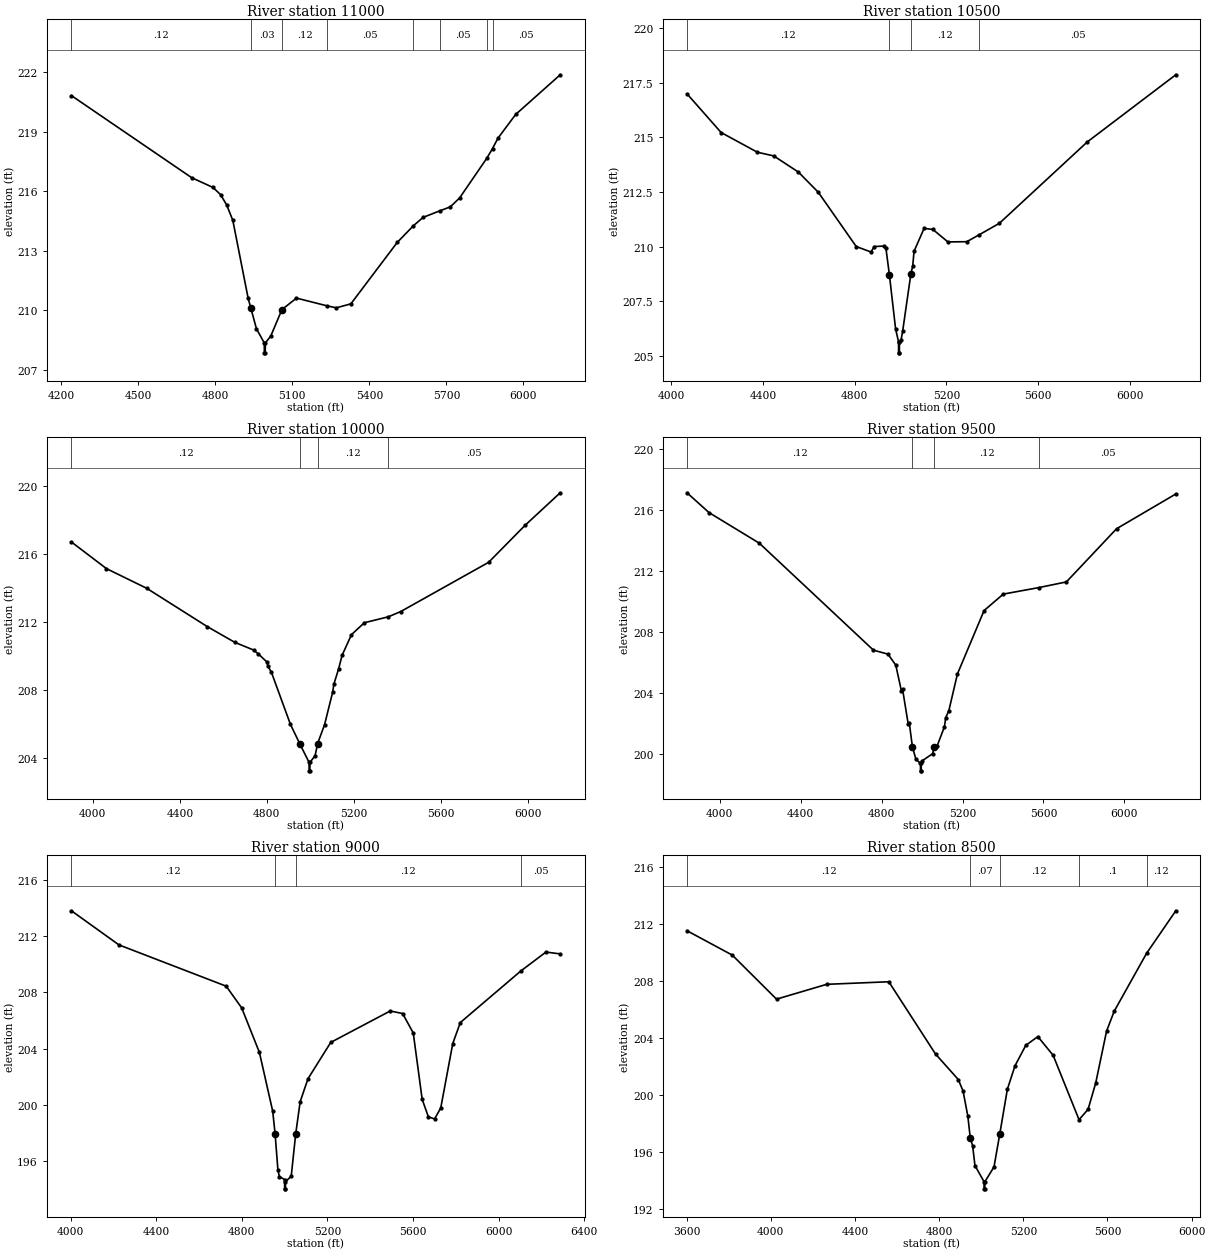
Type RM Length L Ch R = 1 ,11000   ,500,500,500
BEGIN DESCRIPTION:
CRYSTAL CREEK TRIBUTARY NO 3 22.0
END DESCRIPTION:
XS GIS Cut Line= 3
       3861561.3     10125997.64      3861272.84     10125294.51
      3860194.21     10124916.05
#Sta/Elev= 30
    4240  220.82  4708.3  216.68  4791.1  216.19  4820.5  215.83  4844.4  215.31
  4868.4  214.53  4928.1   210.6  4938.9  210.09  4960.5  209.06  4990.9  208.35
  4991.2  207.85  4994.7  207.85  4994.9  208.35  5015.9  208.69  5059.6  210.03
  5116.3  210.61    5235  210.22  5271.3  210.12    5328  210.32  5508.7  213.42
  5571.7  214.26  5609.4  214.68  5674.3  215.01  5715.1  215.21  5751.4  215.66
  5856.7  217.65  5879.6  218.15  5901.1  218.68  5969.7  219.87  6143.1  221.87
#Mann= 8 ,-1 , 0
    4240     .12       0  4938.9     .03       0  5059.6     .12       0
    5235     .05       0  5571.7     .12       0  5674.3     .05       0
  5856.7     .12       0  5879.6     .05       0
Bank Sta=4938.9,5059.6
XS Rating Curve= 0 ,0
Exp/Cntr=0.3,0.1

Type RM Length L Ch R = 1 ,10500   ,500,500,500
BEGIN DESCRIPTION:
CRYSTAL CREEK TRIBUTARY NO 3 21.0
END DESCRIPTION:
XS GIS Cut Line= 3
      3862108.17     10125667.76      3861577.98     10124902.35
      3860519.63     10124335.28
#Sta/Elev= 30
  4068.9  216.99  4217.8  215.22  4375.9  214.32  4447.5  214.15    4555  213.41
  4641.5  212.49  4806.9  210.01  4871.2  209.76    4886  210.01  4928.6  210.03
  4936.7  209.92  4951.6  208.72  4978.6  206.25  4991.5  205.65  4991.7  205.15
  4995.2  205.15  4995.5  205.65  5002.9  205.75  5009.6  206.15  5045.5  208.77
  5053.4  209.12  5059.1  209.79    5103  210.84  5141.2  210.79  5206.9  210.22
    5289  210.23  5343.8  210.55  5431.2  211.07  5814.6  214.79  6200.7  217.86
#Mann= 4 ,-1 , 0
  4068.9     .12       0  4951.6     .07       0  5045.5     .12       0
  5343.8     .05       0
Bank Sta=4951.6,5045.5
XS Rating Curve= 0 ,0
Exp/Cntr=0.3,0.1

Type RM Length L Ch R = 1 ,10000   ,500,500,500
BEGIN DESCRIPTION:
CRYSTAL CREEK TRIBUTARY NO 3 20.0
END DESCRIPTION:
XS GIS Cut Line= 3
      3862420.68     10125485.49      3861897.21     10124519.74
      3860897.18     10123953.31
#Sta/Elev= 30
  3901.5  216.72  4062.5  215.15  4247.8  213.99  4526.5  211.73    4652  210.81
  4739.4  210.35  4761.3  210.12  4799.4  209.66  4805.1  209.41  4821.2  209.04
  4908.7  205.97    4953  204.79  4994.4  203.73  4994.6  203.23  4998.1  203.23
  4998.4  203.73  5022.1  204.12  5033.7  204.84  5065.4  205.94  5102.7  207.86
  5108.7  208.35  5130.3  209.24  5146.2  210.04  5189.5  211.26  5248.6  211.96
  5359.1  212.31    5416  212.62    5820  215.52  5987.6   217.7  6149.3  219.62
#Mann= 4 ,-1 , 0
  3901.5     .12       0    4953     .07       0  5033.7     .12       0
  5359.1     .05       0
Bank Sta=4953,5033.7
XS Rating Curve= 0 ,0
Exp/Cntr=0.3,0.1

Type RM Length L Ch R = 1 ,9500    ,500,500,500
BEGIN DESCRIPTION:
CRYSTAL CREEK TRIBUTARY NO 3 19.0
END DESCRIPTION:
XS GIS Cut Line= 3
      3862663.72     10125420.37      3862334.87     10124305.25
      3861262.32     10123654.17
#Sta/Elev= 30
  3837.4  217.14  3946.3  215.84  4195.2  213.83  4759.5  206.81  4831.3  206.55
  4869.9  205.83    4898  204.12  4903.2  204.27  4931.3  201.97  4936.5  202.06
  4952.2  200.46  4969.8  199.64  4991.9  199.39  4992.2  198.89  4995.7  198.89
  4995.9  199.39  4999.6  199.54  5052.7  200.02  5058.5  200.43    5074  200.51
  5110.8  201.79  5116.7  202.38  5132.2  202.83  5174.8  205.25  5306.6  209.41
  5401.6  210.49  5578.6  210.92  5713.7  211.29  5961.8  214.78  6254.7  217.06
#Mann= 4 ,-1 , 0
  3837.4     .12       0  4952.2     .03       0  5058.5     .12       0
  5578.6     .05       0
Bank Sta=4952.2,5058.5
XS Rating Curve= 0 ,0
Exp/Cntr=0.3,0.1

Type RM Length L Ch R = 1 ,9000    ,500,500,500
BEGIN DESCRIPTION:
CRYSTAL CREEK TRIBUTARY NO 3 18.0
END DESCRIPTION:
XS GIS Cut Line= 3
        3863050.     10125159.95      3862794.46     10124197.29
      3862003.99     10123180.76
#Sta/Elev= 30
    4004  213.79    4226  211.37  4727.1  208.44  4799.5   206.9  4882.3  203.74
  4944.4  199.57  4955.6 197.974  4968.7  195.41  4975.4  194.93    5000  194.72
  5000.3  194.06  5003.8  194.06  5004.1  194.56    5031  194.96  5051.8  197.95
  5072.7  200.24  5109.2  201.87  5215.6  204.45  5493.5  206.68  5551.4   206.5
  5601.1  205.12  5642.8  200.41  5671.7  199.17  5700.7  199.02  5729.6   199.8
  5785.7  204.37    5821  205.86  6103.8  209.52    6221  210.86  6287.7  210.73
#Mann= 4 ,-1 , 0
    4004     .12       0  4955.6     .07       0  5051.8     .12       0
  6103.8     .05       0
Bank Sta=4955.6,5051.8
XS Rating Curve= 0 ,0
Exp/Cntr=0.3,0.1

Type RM Length L Ch R = 1 ,8500    ,500,500,500
BEGIN DESCRIPTION:
CRYSTAL CREEK TRIBUTARY NO 3 17.0
END DESCRIPTION:
XS GIS Cut Line= 3
      3863536.12     10125008.04      3862937.81     10123743.88
      3862435.43     10122967.67
#Sta/Elev= 30
  3601.4  211.51  3816.6   209.8  4026.9  206.71  4265.5  207.75  4560.6  207.93
  4782.6  202.86  4890.8  201.07  4913.6  200.26  4936.3  198.49  4947.8  196.96
  4958.9  196.43  4970.1  195.03  5013.3   193.9  5013.5   193.4    5017   193.4
  5017.3   193.9  5060.6  194.94  5087.7  197.22    5124  200.38  5160.3  202.03
  5211.7  203.47  5269.1  204.08  5341.6  202.77  5464.8  198.25  5507.8  198.98
  5544.1  200.83  5595.5  204.46  5631.8  205.86  5785.6  209.92  5924.6  212.91
#Mann= 5 ,-1 , 0
  3601.4     .12       0  4947.8     .07       0  5087.7     .12       0
  5464.8      .1       0  5785.6     .12       0
Bank Sta=4947.8,5087.7
XS Rating Curve= 0 ,0
Exp/Cntr=0.3,0.1

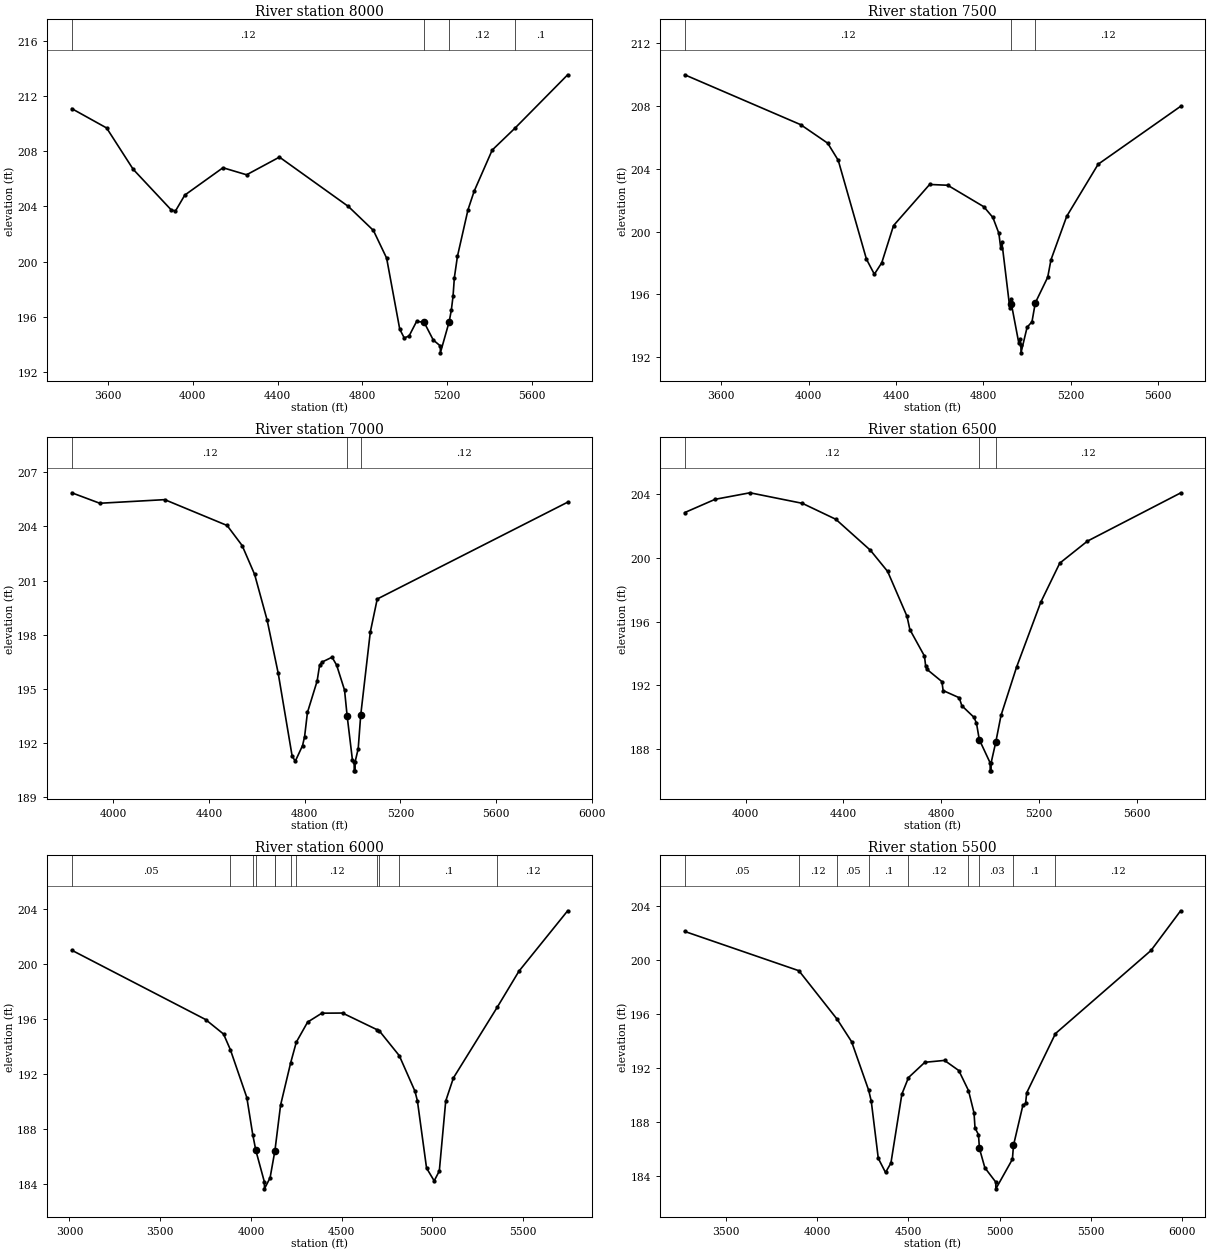
Type RM Length L Ch R = 1 ,8000    ,500,500,500
BEGIN DESCRIPTION:
CRYSTAL CREEK TRIBUTARY NO 3 16.0
END DESCRIPTION:
XS GIS Cut Line= 3
      3863766.14      10124834.4      3863245.83     10123351.64
      3862776.57     10122742.41
#Sta/Elev= 30
  3428.6  211.07    3593  209.67  3718.3  206.68  3898.4  203.73    3918  203.66
    3962  204.81  4142.2  206.79  4253.7  206.28  4408.7  207.56  4733.8  203.99
  4852.2  202.25  4914.5  200.25  4976.5   195.1  4997.7  194.47  5020.5  194.61
  5055.8  195.66  5091.1  195.61  5134.6  194.32  5167.9  193.89  5168.2  193.39
 5209.67 195.638  5219.8  196.47  5227.9  197.47  5234.3  198.84  5248.8  200.38
  5298.6  203.75  5327.6  205.09  5412.8  208.07  5519.3  209.64    5769  213.52
#Mann= 4 ,-1 , 0
  3428.6     .12       0  5091.1     .03       0 5209.67     .12       0
  5519.3      .1       0
Bank Sta=5091.1,5209.67
XS Rating Curve= 0 ,0
Exp/Cntr=0.3,0.1

Type RM Length L Ch R = 1 ,7500    ,500,500,500
BEGIN DESCRIPTION:
CRYSTAL CREEK TRIBUTARY NO 3 15.0
END DESCRIPTION:
XS GIS Cut Line= 3
      3864042.86      10124686.1      3863664.51     10123165.26
      3863272.11     10122582.93
#Sta/Elev= 30
  3432.8  209.99  3963.5  206.81  4087.2  205.63  4135.3  204.54  4264.4  198.24
  4300.6  197.28  4334.5  198.01  4388.4  200.38  4553.6     203  4636.3  202.95
  4801.6  201.58  4842.9   200.9  4870.4  199.89  4879.1  198.93  4884.2  199.32
  4920.4  195.14  4925.5  195.71 4927.94 195.368  4961.7  192.89  4966.8  193.16
  4971.4  192.77  4971.7  192.27  4999.6   193.9    5022  194.25    5037  195.45
    5094  197.09  5108.9   198.2  5180.9  200.97  5324.8  204.29  5702.2  207.98
#Mann= 3 , 0 , 0
  3432.8     .12       0 4927.94     .07       0    5037     .12       0
Bank Sta=4927.94,5037
XS Rating Curve= 0 ,0
Exp/Cntr=0.3,0.1

Type RM Length L Ch R = 1 ,7000    ,500,500,500
BEGIN DESCRIPTION:
CRYSTAL CREEK TRIBUTARY NO 3 14.0
END DESCRIPTION:
XS GIS Cut Line= 3
       3864365.1     10124409.06      3864146.16     10123255.96
      3863632.23     10122517.61
#Sta/Elev= 30
  3826.3  205.86  3943.4  205.28  4214.9  205.48  4475.7  204.05  4538.6  202.94
  4590.8  201.34  4643.1  198.81  4689.4  195.87  4747.6  191.29  4760.7     191
  4791.2  191.87  4799.8  192.37  4811.6   193.7  4852.1  195.44  4862.5  196.32
  4872.7  196.49  4914.5  196.76  4933.7  196.32  4966.7  194.94 4977.52 193.518
  4999.9  191.05  5006.9  190.97  5007.2  190.47  5010.7  190.47  5010.9  190.97
  5023.8  191.69 5034.27 193.544  5074.4  198.15  5103.4  199.98  5899.6  205.34
#Mann= 3 , 0 , 0
  3826.3     .12       0 4977.52     .07       0 5034.27     .12       0
Bank Sta=4977.52,5034.27
XS Rating Curve= 0 ,0
Exp/Cntr=0.3,0.1

Type RM Length L Ch R = 1 ,6500    ,500,500,500
BEGIN DESCRIPTION:
CRYSTAL CREEK TRIBUTARY NO 3 13.0
END DESCRIPTION:
XS GIS Cut Line= 3
      3864599.47     10124183.33       3864426.3      10122946.7
      3863887.65     10122382.13
#Sta/Elev= 30
  3751.3  202.83  3875.5  203.66  4018.3  204.07  4232.4  203.41  4369.5  202.41
  4510.9  200.47  4581.6  199.14  4660.8  196.33  4672.5   195.5  4732.2  193.84
  4737.3  193.19  4743.1     193  4803.6  192.24  4808.6  191.68  4874.4  191.23
  4885.1  190.73    4935     190  4945.1  189.63  4956.5  188.61  5000.9  187.15
  5001.2  186.65  5004.7  186.65  5004.9  187.15    5024  188.45  5045.4  190.12
  5108.9  193.14    5208  197.21  5285.7  199.66  5398.9  201.04  5780.3  204.06
#Mann= 3 , 0 , 0
  3751.3     .12       0  4956.5     .07       0    5024     .12       0
Bank Sta=4956.5,5024
XS Rating Curve= 0 ,0
Exp/Cntr=0.3,0.1

Type RM Length L Ch R = 1 ,6000    ,500,500,500
BEGIN DESCRIPTION:
CRYSTAL CREEK TRIBUTARY NO 3 12.0
END DESCRIPTION:
XS GIS Cut Line= 3
      3866248.75     10123775.36      3864693.03     10122539.42
      3864167.83     10122011.05
#Sta/Elev= 30
  3013.1  201.01    3750  195.97  3849.3  194.91  3886.9  193.77  3977.5  190.29
    4010   187.6  4027.2  186.44  4074.2  184.15  4074.6  183.65  4105.7  184.46
  4132.3  186.43  4163.4  189.74    4219  192.82    4250  194.32  4312.3  195.78
  4390.8  196.43  4504.6  196.44    4693  195.24  4707.6  195.14  4817.3  193.34
  4903.5  190.76  4917.2  190.05  4967.6  185.16  5009.6  184.23  5037.9  184.95
  5073.2  190.04  5115.6  191.72  5358.3  196.89  5476.3  199.48    5745  203.88
#Mann= 12 ,-1 , 0
  3013.1     .05       0  3886.9     .12       0    4010     .05       0
  4027.2     .03       0  4132.3     .05       0  4132.3     .12       0
    4219      .1       0    4250     .12       0    4693      .1       0
  4707.6     .12       0  4817.3      .1       0  5358.3     .12       0
Bank Sta=4027.2,4132.3
XS Rating Curve= 0 ,0
Exp/Cntr=0.3,0.1

Type RM Length L Ch R = 1 ,5500    ,500,500,500
BEGIN DESCRIPTION:
CRYSTAL CREEK TRIBUTARY NO 3 11.0
END DESCRIPTION:
XS GIS Cut Line= 3
      3866752.23     10123054.89      3865150.01     10122414.67
      3864322.24     10121870.35
#Sta/Elev= 30
  3274.6  202.09    3900  199.18  4109.3  195.59  4188.5  193.93  4282.1  190.33
  4296.2  189.53  4334.7  185.29  4374.4  184.24    4404  184.94  4463.9  190.04
  4500.2  191.27  4589.8   192.4  4697.6  192.54  4775.7  191.79  4828.8  190.31
  4859.2  188.65  4864.6  187.54  4883.5  187.04  4888.8  186.02  4918.5  184.59
  4978.2  183.53  4978.6  183.03  5069.3  185.22  5075.3  186.25  5126.6  189.21
  5141.6  189.36  5147.6  190.14  5305.3  194.53  5828.4  200.68  5990.7  203.62
#Mann= 9 ,-1 , 0
  3274.6     .05       0    3900     .12       0  4109.3     .05       0
  4282.1      .1       0  4500.2     .12       0  4828.8      .1       0
  4888.8     .03       0  5075.3      .1       0  5305.3     .12       0
Bank Sta=4888.8,5075.3
XS Rating Curve= 0 ,0
Exp/Cntr=0.3,0.1