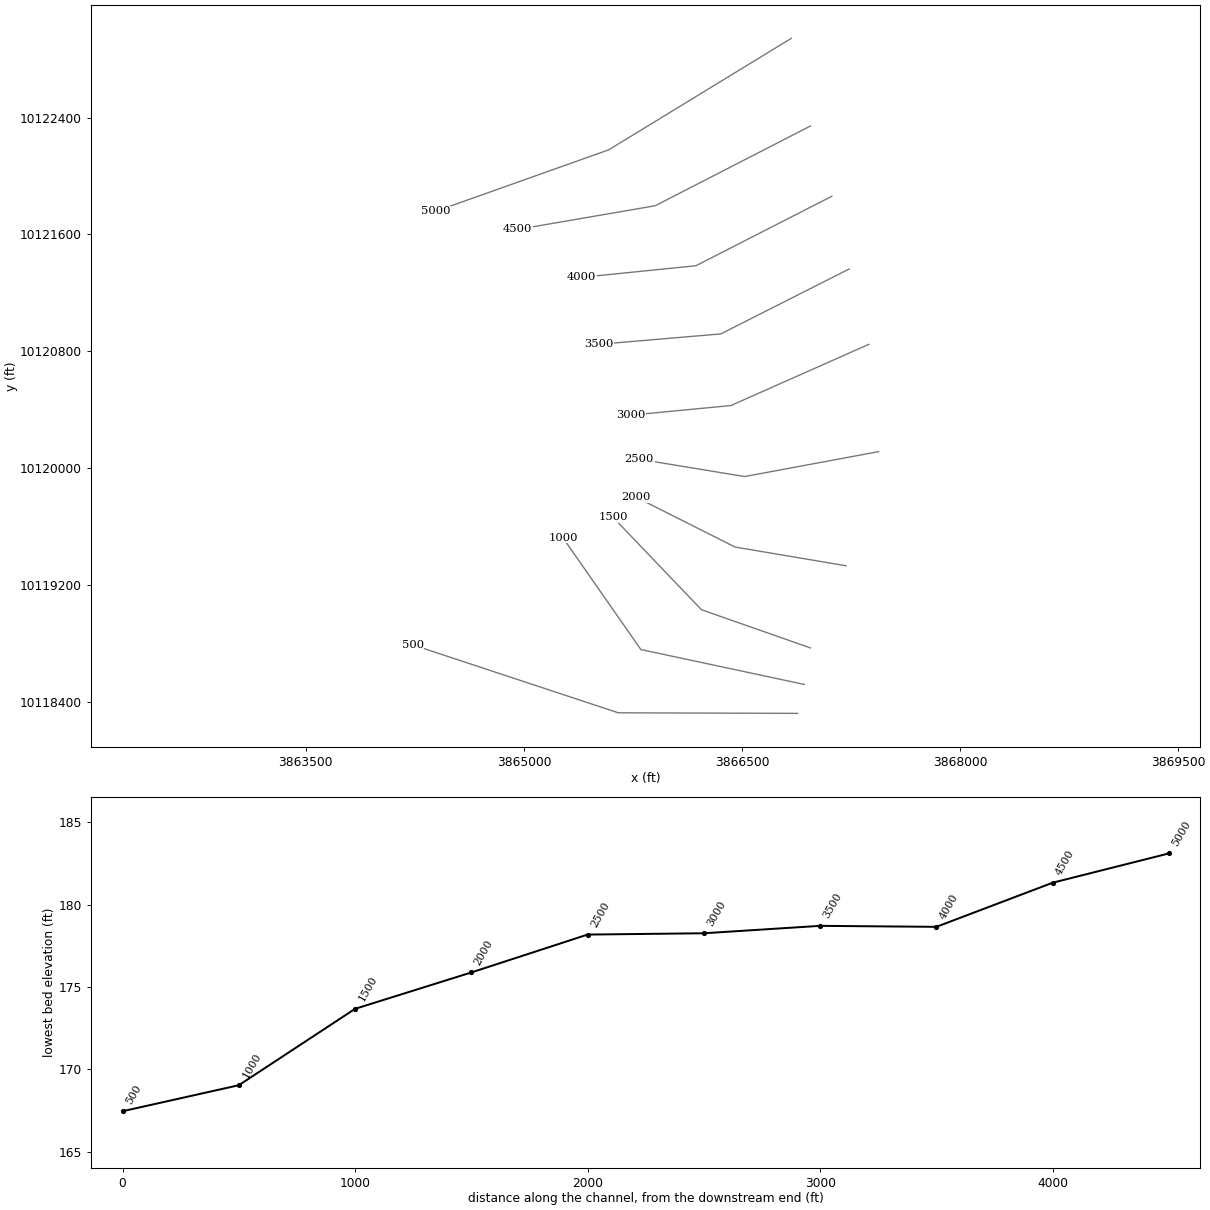
HEC-RAS study CRYSTAL CREEK TRIBUTARY NO 3.prj: CRYSTAL CREEK TRIBUTARY NO 3 Base Level Engineering

--- CRYSTAL CREEK TRIBUTARY NO 3.g10 (geometry) --- (continued)

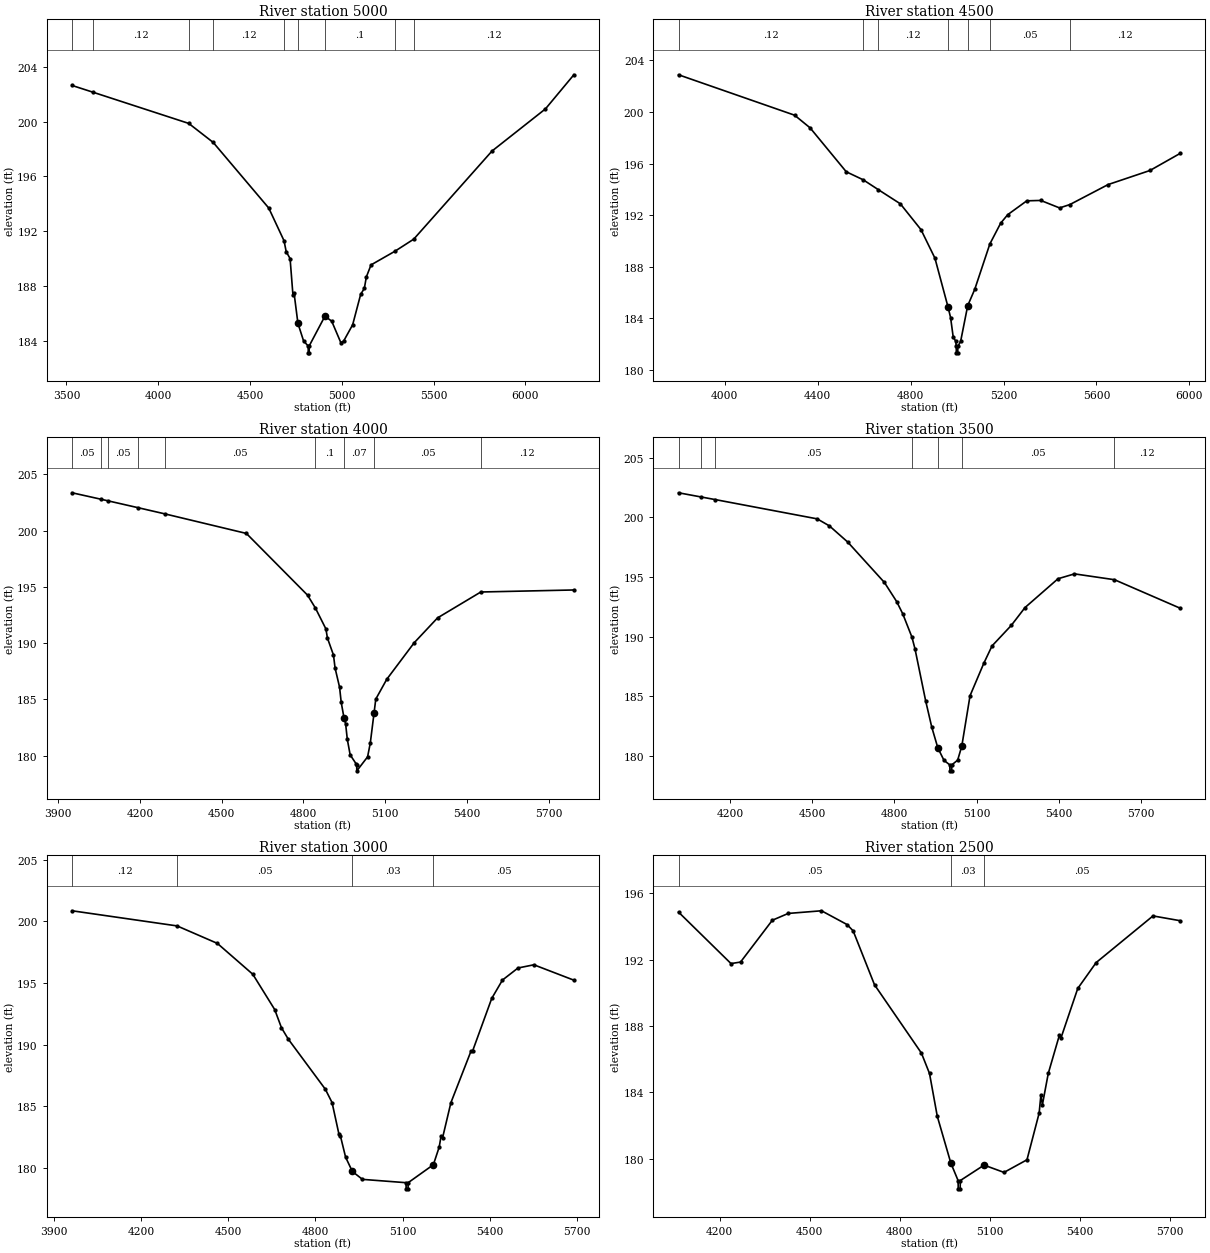
Type RM Length L Ch R = 1 ,5000    ,500,500,500
BEGIN DESCRIPTION:
CRYSTAL CREEK TRIBUTARY NO 3 10.0
END DESCRIPTION:
XS GIS Cut Line= 3
      3866839.07     10122942.05       3865583.8     10122178.99
      3864392.05     10121757.47
#Sta/Elev= 30
    3531  202.64  3644.2  202.15  4166.4  199.87  4299.8  198.48  4602.3  193.69
  4685.6   191.3  4697.2  190.51  4718.5     190    4734  187.35  4739.9  187.51
  4761.2  185.27  4792.2  183.98  4817.1  183.62  4817.5  183.12    4822  183.12
  4822.4  183.62  4908.4   185.8  4945.2  185.43  4994.7  183.87  5010.2  183.98
  5059.3  185.17  5102.9  187.39    5123  187.83  5133.8  188.66  5159.4  189.54
  5288.7  190.53    5392  191.42  5818.1  197.85  6109.4  200.93  6264.1  203.42
#Mann= 9 ,-1 , 0
    3531     .05       0  3644.2     .12       0  4166.4     .05       0
  4299.8     .12       0  4685.6      .1       0  4761.2     .03       0
  4908.4      .1       0  5288.7     .05       0    5392     .12       0
Bank Sta=4761.2,4908.4
XS Rating Curve= 0 ,0
Exp/Cntr=0.3,0.1

Type RM Length L Ch R = 1 ,4500    ,500,500,500
BEGIN DESCRIPTION:
CRYSTAL CREEK TRIBUTARY NO 3 9.0
END DESCRIPTION:
XS GIS Cut Line= 3
      3866970.97     10122342.16      3865903.01     10121796.04
      3864955.29      10121633.8
#Sta/Elev= 30
  3800.5  202.87  4300.4  199.74  4367.1  198.76  4522.8  195.36  4595.6  194.74
  4661.3  193.97  4755.7  192.88  4844.6  190.88  4904.7  188.67  4961.2  184.88
  4972.1  184.07  4983.5  182.55  4994.4  182.24  4996.4  181.84  4996.9  181.34
    5003  181.34  5003.5  181.84  5015.4  182.23  5045.8  184.99  5076.2  186.26
  5141.2  189.77  5187.8  191.38  5218.3  192.04  5300.3  193.11  5360.4  193.14
  5441.5  192.56  5485.7  192.82  5650.6  194.37  5830.8  195.46  5961.5  196.79
#Mann= 7 ,-1 , 0
  3800.5     .12       0  4595.6     .05       0  4661.3     .12       0
  4961.2     .07       0  5045.8      .1       0  5141.2     .05       0
  5485.7     .12       0
Bank Sta=4961.2,5045.8
XS Rating Curve= 0 ,0
Exp/Cntr=0.3,0.1

Type RM Length L Ch R = 1 ,4000    ,500,500,500
BEGIN DESCRIPTION:
CRYSTAL CREEK TRIBUTARY NO 3 8.0
END DESCRIPTION:
XS GIS Cut Line= 3
       3867117.9     10121861.09      3866183.37     10121385.47
      3865394.77     10121305.88
#Sta/Elev= 30
  3951.4  203.35  4058.8  202.77  4084.1  202.63  4192.8  202.03  4293.1  201.47
    4591  199.74  4815.4  194.26  4844.4  193.11  4882.8  191.26  4888.4  190.45
  4910.6  188.94  4916.4  187.79  4932.9  186.09  4938.9  184.75  4949.5  183.32
  4955.1  182.84  4961.3  181.46  4971.8  180.08    4994  179.27  4995.7  179.16
  4996.2  178.66  5035.7   179.9  5045.7  181.13 5059.23 183.755  5065.8  185.03
  5106.1  186.79  5206.6  190.03  5292.4  192.24  5451.2  194.54  5792.6  194.72
#Mann= 9 ,-1 , 0
  3951.4     .05       0  4058.8     .12       0  4084.1     .05       0
  4192.8     .12       0  4293.1     .05       0  4844.4      .1       0
  4949.5     .07       0 5059.23     .05       0  5451.2     .12       0
Bank Sta=4949.5,5059.23
XS Rating Curve= 0 ,0
Exp/Cntr=0.3,0.1

Type RM Length L Ch R = 1 ,3500    ,500,500,500
BEGIN DESCRIPTION:
CRYSTAL CREEK TRIBUTARY NO 3 7.0
END DESCRIPTION:
XS GIS Cut Line= 3
      3867236.58     10121362.98      3866353.99     10120918.71
      3865512.71     10120847.36
#Sta/Elev= 30
  4011.9  202.07  4093.8  201.72  4145.6   201.5  4518.2  199.88  4562.8  199.29
  4629.8  197.93  4763.7  194.54  4808.3  192.94  4830.6  191.91    4864  189.96
  4875.3  188.97  4914.3   184.6  4936.6  182.39  4958.9  180.64  4981.3   179.6
  5002.5  179.22    5003  178.72  5009.3  178.72  5009.8  179.22  5031.2  179.62
  5046.3   180.8  5076.4  185.03  5126.6  187.75  5156.7  189.21  5226.9  190.93
  5277.1  192.43  5397.6  194.85  5457.8  195.26  5603.8  194.77  5844.3  192.37
#Mann= 7 ,-1 , 0
  4011.9      .1       0  4093.8     .12       0  4145.6     .05       0
    4864     .12       0  4958.9     .03       0  5046.3     .05       0
  5603.8     .12       0
Bank Sta=4958.9,5046.3
XS Rating Curve= 0 ,0
Exp/Cntr=0.3,0.1

Type RM Length L Ch R = 1 ,3000    ,500,500,500
BEGIN DESCRIPTION:
CRYSTAL CREEK TRIBUTARY NO 3 6.0
END DESCRIPTION:
XS GIS Cut Line= 3
      3867371.94     10120847.33      3866423.16     10120428.27
      3865736.56     10120362.97
#Sta/Elev= 30
  3962.8  200.87  4324.2  199.64  4462.8  198.22  4584.8  195.71  4660.2  192.84
  4683.5  191.36  4706.8  190.44  4834.3  186.37  4857.6  185.28  4880.9  182.75
  4886.4  182.56  4904.2  180.84  4927.5  179.68  4962.1  179.04  5112.1  178.77
  5112.6  178.27    5119  178.27  5119.5  178.77  5206.2  180.23  5226.3  181.67
  5232.9  182.58  5237.9  182.42  5266.5  185.27    5336  189.48    5341  189.46
  5407.1  193.75    5444  195.24  5497.5  196.22  5552.1  196.48  5689.7  195.23
#Mann= 4 ,-1 , 0
  3962.8     .12       0  4324.2     .05       0  4927.5     .03       0
  5206.2     .05       0
Bank Sta=4927.5,5206.2
XS Rating Curve= 0 ,0
Exp/Cntr=0.3,0.1

Type RM Length L Ch R = 1 ,2500    ,500,500,500
BEGIN DESCRIPTION:
CRYSTAL CREEK TRIBUTARY NO 3 5.0
END DESCRIPTION:
XS GIS Cut Line= 3
      3867439.66     10120112.97       3866518.2     10119942.46
      3865793.82     10120060.89
#Sta/Elev= 30
  4062.9  194.86  4237.6  191.76  4269.4  191.85  4375.3  194.37  4428.2  194.78
    4539  194.94  4624.1  194.11  4644.4  193.73  4715.6  190.48  4871.7  186.37
  4898.7  185.14  4924.6  182.56  4969.8  179.74  4993.9  178.69  4994.4  178.19
  5000.8  178.19  5001.3  178.69  5080.4  179.62  5146.8  179.18  5223.3  179.94
  5263.8  182.75  5269.6  183.83  5274.7  183.26  5294.2  185.14    5331  187.43
    5336  187.25  5392.4  190.26  5453.7  191.82    5643  194.63    5734  194.34
#Mann= 3 , 0 , 0
  4062.9     .05       0  4969.8     .03       0  5080.4     .05       0
Bank Sta=4969.8,5080.4
XS Rating Curve= 0 ,0
Exp/Cntr=0.3,0.1

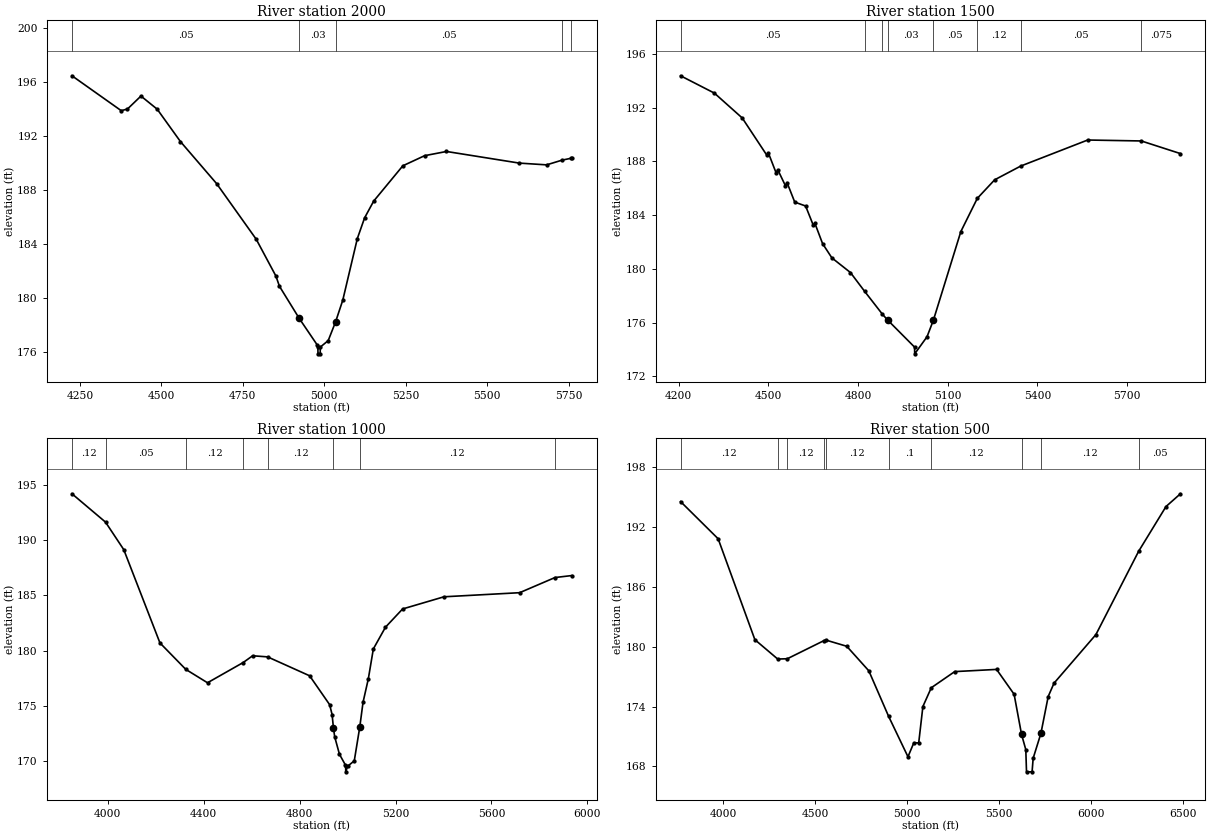
Type RM Length L Ch R = 1 ,2000    ,500,500,500
BEGIN DESCRIPTION:
CRYSTAL CREEK TRIBUTARY NO 3 4.0
END DESCRIPTION:
XS GIS Cut Line= 3
      3867215.76     10119331.72      3866452.14     10119459.87
      3865772.97     10119800.49
#Sta/Elev= 30
  4225.7  196.46  4376.8  193.88    4396     194  4437.4  194.96  4487.2  193.99
  4558.7  191.59  4669.7  188.48  4791.1  184.37  4851.7  181.64  4862.4  180.89
  4923.2  178.51    4978  176.56  4980.3  176.39  4980.8  175.89  4987.4  175.89
  4987.9  176.39  5012.1  176.87  5034.5  178.24  5056.8  179.86  5101.5  184.42
  5123.8  185.95  5151.7  187.19  5241.1   189.8  5308.1  190.55  5375.1  190.86
  5598.6     190  5682.3  189.87    5730  190.22  5755.8  190.35  5759.8  190.35
#Mann= 5 ,-1 , 0
  4225.7     .05       0  4923.2     .03       0  5034.5     .05       0
    5730    .075       0  5755.8     .05       0
Bank Sta=4923.2,5034.5
XS Rating Curve= 0 ,0
Exp/Cntr=0.3,0.1

Type RM Length L Ch R = 1 ,1500    ,500,500,500
BEGIN DESCRIPTION:
CRYSTAL CREEK TRIBUTARY NO 3 3.0
END DESCRIPTION:
XS GIS Cut Line= 3
      3866970.93     10118769.22      3866221.25      10119030.8
      3865612.23     10119664.35
#Sta/Elev= 30
    4206  194.37  4319.2  193.08  4412.4  191.23    4495  188.45  4500.2  188.61
    4526  187.13  4531.3  187.38  4557.1  186.18  4562.4  186.42  4588.1  184.97
  4624.5  184.68  4650.3  183.24  4655.6  183.39  4681.3  181.88  4712.4  180.82
  4774.5  179.73    4822  178.33  4881.8  176.62  4898.8   176.2  4989.1  174.18
  4989.6  173.68  5030.8  174.95  5052.2  176.19    5144  182.78  5199.1  185.25
  5257.2  186.63  5344.2  187.65  5568.5  189.59  5747.9  189.52  5878.8  188.58
#Mann= 8 ,-1 , 0
    4206     .05       0    4822     .12       0  4881.8     .05       0
  4898.8     .03       0  5052.2     .05       0  5199.1     .12       0
  5344.2     .05       0  5747.9    .075       0
Bank Sta=4898.8,5052.2
XS Rating Curve= 0 ,0
Exp/Cntr=0.3,0.1

Type RM Length L Ch R = 1 ,1000    ,500,500,500
BEGIN DESCRIPTION:
CRYSTAL CREEK TRIBUTARY NO 3 2.0
END DESCRIPTION:
XS GIS Cut Line= 3
      3866929.23     10118519.23      3865804.64     10118758.24
      3865267.83      10119524.4
#Sta/Elev= 30
  3850.3  194.17  3990.2  191.61  4066.4  189.12  4217.3  180.69  4325.1   178.3
  4415.7  177.09  4564.6  178.92  4603.9  179.53  4666.3  179.43  4841.7  177.72
  4925.2  175.11  4935.4  174.22    4941  173.02  4946.1  172.22  4966.1  170.63
  4990.6  169.67  4991.9  169.54  4992.4  169.04  4999.7  169.54  5027.9  170.03
  5050.8  173.08  5064.5  175.33  5086.5  177.44  5107.5  180.15    5158  182.11
  5229.5  183.76  5402.1  184.86  5717.7  185.23  5865.2   186.6  5935.5  186.78
#Mann= 8 ,-1 , 0
  3850.3     .12       0  3990.2     .05       0  4325.1     .12       0
  4564.6     .05       0  4666.3     .12       0    4941     .07       0
  5050.8     .12       0  5865.2     .05       0
Bank Sta=4941,5050.8
XS Rating Curve= 0 ,0
Exp/Cntr=0.3,0.1

Type RM Length L Ch R = 1 ,500     ,0,0,0
BEGIN DESCRIPTION:
CRYSTAL CREEK TRIBUTARY NO 3 1.0
END DESCRIPTION:
XS GIS Cut Line= 3
      3866882.37     10118321.31      3865649.67     10118325.23
      3864236.56     10118790.05
#Sta/Elev= 30
  3767.3  194.56  3971.8  190.83  4171.8  180.71    4296  178.77  4348.4   178.8
  4548.1  180.62  4560.2  180.66  4671.8  180.05  4791.8  177.59  4899.4  173.03
  5004.9  168.97  5036.7  170.37  5063.3  170.36  5086.1  174.01  5131.7  175.89
  5259.3  177.51  5487.1  177.73  5582.5  175.24    5623  171.21  5646.1  169.69
    5650  167.46  5680.3  167.46  5686.2  168.82  5728.3  171.31    5768  175.01
  5799.7  176.35  6027.6  181.22  6260.1  189.57  6409.1  194.06  6487.6  195.34
#Mann= 10 ,-1 , 0
  3767.3     .12       0    4296      .1       0  4348.4     .12       0
  4548.1     .05       0  4560.2     .12       0  4899.4      .1       0
  5131.7     .12       0    5623     .07       0  5728.3     .12       0
  6260.1     .05       0
Bank Sta=5623,5728.3
XS Rating Curve= 0 ,0
Exp/Cntr=0.3,0.1