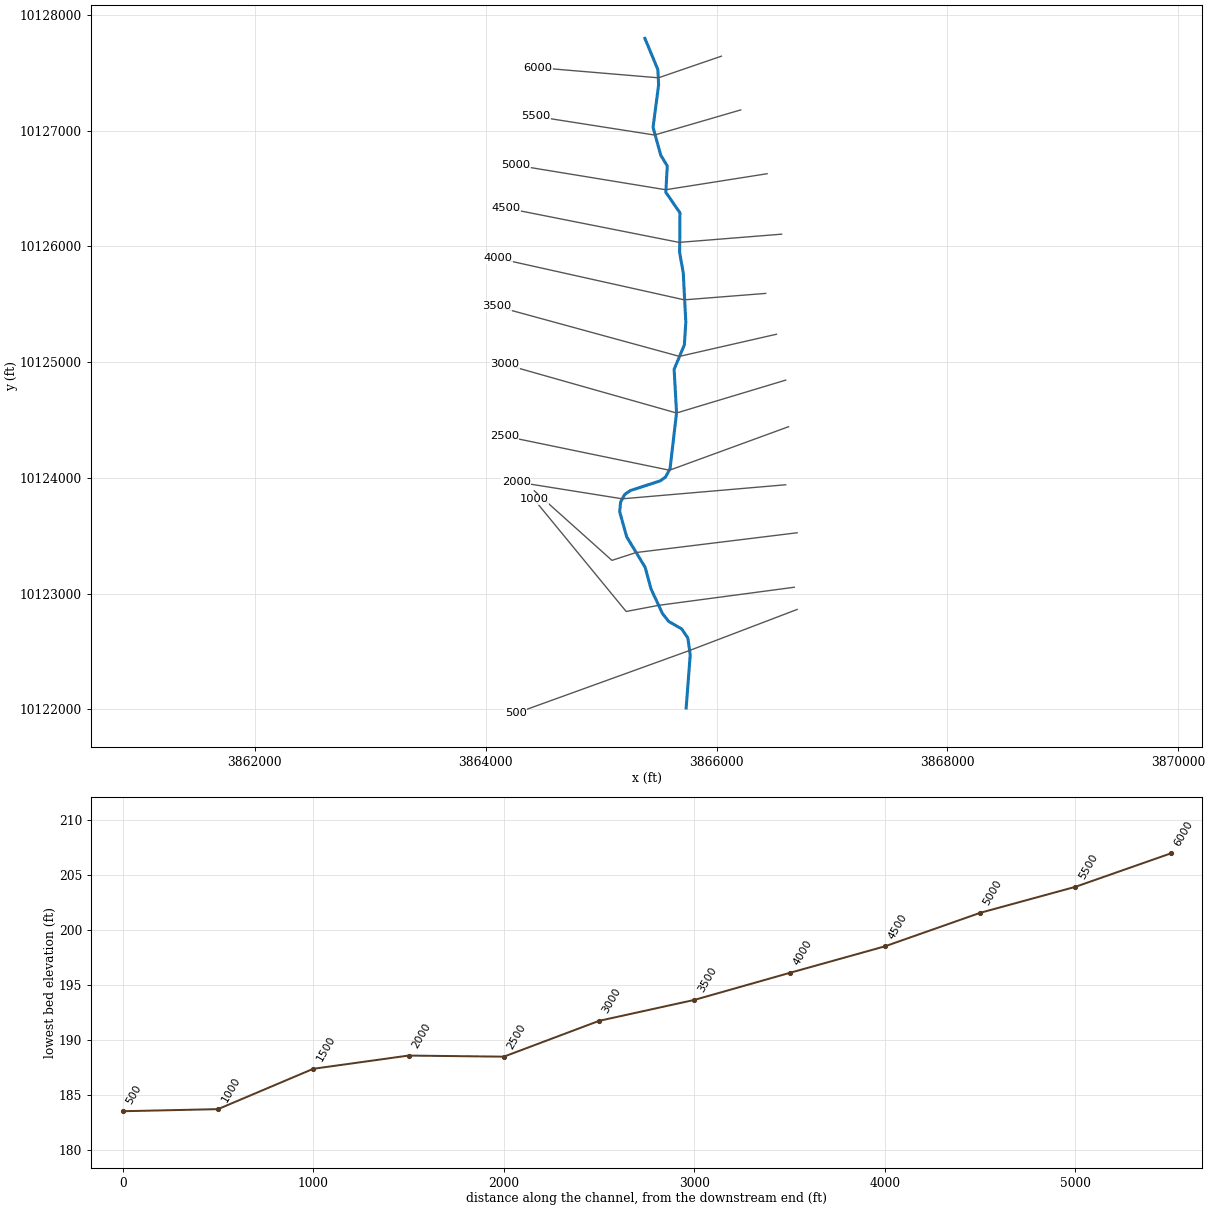
--- CRYSTAL CREEK TRIBUTARY NO 3_1.prj (project) ---

Proj Title=CRYSTAL CREEK TRIBUTARY NO 3_1 Base Level Engineering
Current Plan=p01
Default Exp/Contr=0.3,0.1
English Units
Geom File=g01
Flow File=f01
Plan File=p01
Y Axis Title=Elevation
X Axis Title(PF)=Main Channel Distance
X Axis Title(XS)=Station
BEGIN DESCRIPTION:
CRYSTAL CREEK TRIBUTARY NO 3_1
END DESCRIPTION:
DSS Export Rating Curves= 0
DSS Export Rating Curve Sorted= 0
DSS Export Volume Flow Curves= 0
DXF OffsetX= 0
DXF OffsetY= 0
DXF ScaleX= 1
DXF ScaleY= 10

--- CRYSTAL CREEK TRIBUTARY NO 3_1.p01 (plan) ---

Plan Title=Multiple Run
Short Identifier=Multiple
Geom File=g01
Flow File=f01
Subcritical Flow
K Sum by GR= 0
Std Step Tol= 0.01
Critical Tol= 0.01
Num of Std Step Trials= 20
Max Error Tol= 0.3
Flow Tol Ratio= 0.001
Split Flow NTrial= 30
Split Flow Tol= 0.02
Split Flow Ratio= 0.02
Log Output Level= 0
Friction Slope Method= 1
Unsteady Friction Slope Method= 2
Unsteady Bridges Friction Slope Method= 1
Parabolic Critical Depth
Global Vel Dist=  1 , 1 , 1
Global Log Level= 0
CheckData=True
Encroach Param= -1, 0, 0, 0
BEGIN DESCRIPTION:
Multiple Run
END DESCRIPTION:

--- CRYSTAL CREEK TRIBUTARY NO 3_1.f01 (steady flow) ---

Flow Title=Multiple
Program Version=4.10
Number of Profiles= 7
Profile Names=10-year,25-year,50-year,1pct_min,100-year,1pct_plu,500-year
River Rch & RM=CRYSTAL CREEK TR,Reach-1         ,6000
     925    1259    1705     759    2291    6919    4276
River Rch & RM=CRYSTAL CREEK TR,Reach-1         ,1500
    1212    1667    2274    1017    3072    9277    5800
River Rch & RM=CRYSTAL CREEK TR,Reach-1         ,1000
    1212    1667    2274    1017    3072    9277    5800
River Rch & RM=CRYSTAL CREEK TR,Reach-1         ,500
    1212    1667    2274    1017    3072    9277    5800
Boundary for River Rch & Prof#=CRYSTAL CREEK TR,Reach-1         , 1
Up Type= 0
Dn Type= 3
Dn Slope=0.007
Boundary for River Rch & Prof#=CRYSTAL CREEK TR,Reach-1         , 2
Up Type= 0
Dn Type= 3
Dn Slope=0.007
Boundary for River Rch & Prof#=CRYSTAL CREEK TR,Reach-1         , 3
Up Type= 0
Dn Type= 3
Dn Slope=0.007
Boundary for River Rch & Prof#=CRYSTAL CREEK TR,Reach-1         , 4
Up Type= 0
Dn Type= 3
Dn Slope=0.007
Boundary for River Rch & Prof#=CRYSTAL CREEK TR,Reach-1         , 5
Up Type= 0
Dn Type= 3
Dn Slope=0.007
Boundary for River Rch & Prof#=CRYSTAL CREEK TR,Reach-1         , 6
Up Type= 0
Dn Type= 3
Dn Slope=0.007
Boundary for River Rch & Prof#=CRYSTAL CREEK TR,Reach-1         , 7
Up Type= 0
Dn Type= 3
Dn Slope=0.007
DSS Import GetInterval= 0
DSS Import GetPeak= 0
DSS Import FillOption= 0

--- CRYSTAL CREEK TRIBUTARY NO 3_1.g01 (geometry) ---

Geom Title=Existing Conditions
Program Version=4.10

River Reach=CRYSTAL CREEK TR,Reach-1
Reach XY= 30
      3865379.09     10127797.32      3865491.55     10127527.21
      3865498.06      10127395.7      3865449.88     10127028.51
      3865516.82     10126786.84      3865573.01      10126695.3
      3865560.56     10126467.32      3865682.95     10126290.23
      3865680.35     10125945.18      3865711.47     10125772.46
      3865733.74     10125345.76      3865720.98     10125148.86
      3865632.42     10124938.69      3865653.39     10124563.37
      3865597.21     10124080.45      3865558.38     10124008.67
      3865511.91     10123974.56      3865254.57     10123891.79
      3865203.79     10123856.64      3865168.63     10123791.53
      3865160.82      10123708.2      3865221.56     10123491.06
       3865381.5     10123228.09      3865431.99     10123042.26
      3865531.69      10122828.6      3865584.78     10122760.93
      3865697.78       10122696.      3865751.43     10122616.37
      3865771.92     10122473.19      3865736.68     10122013.25

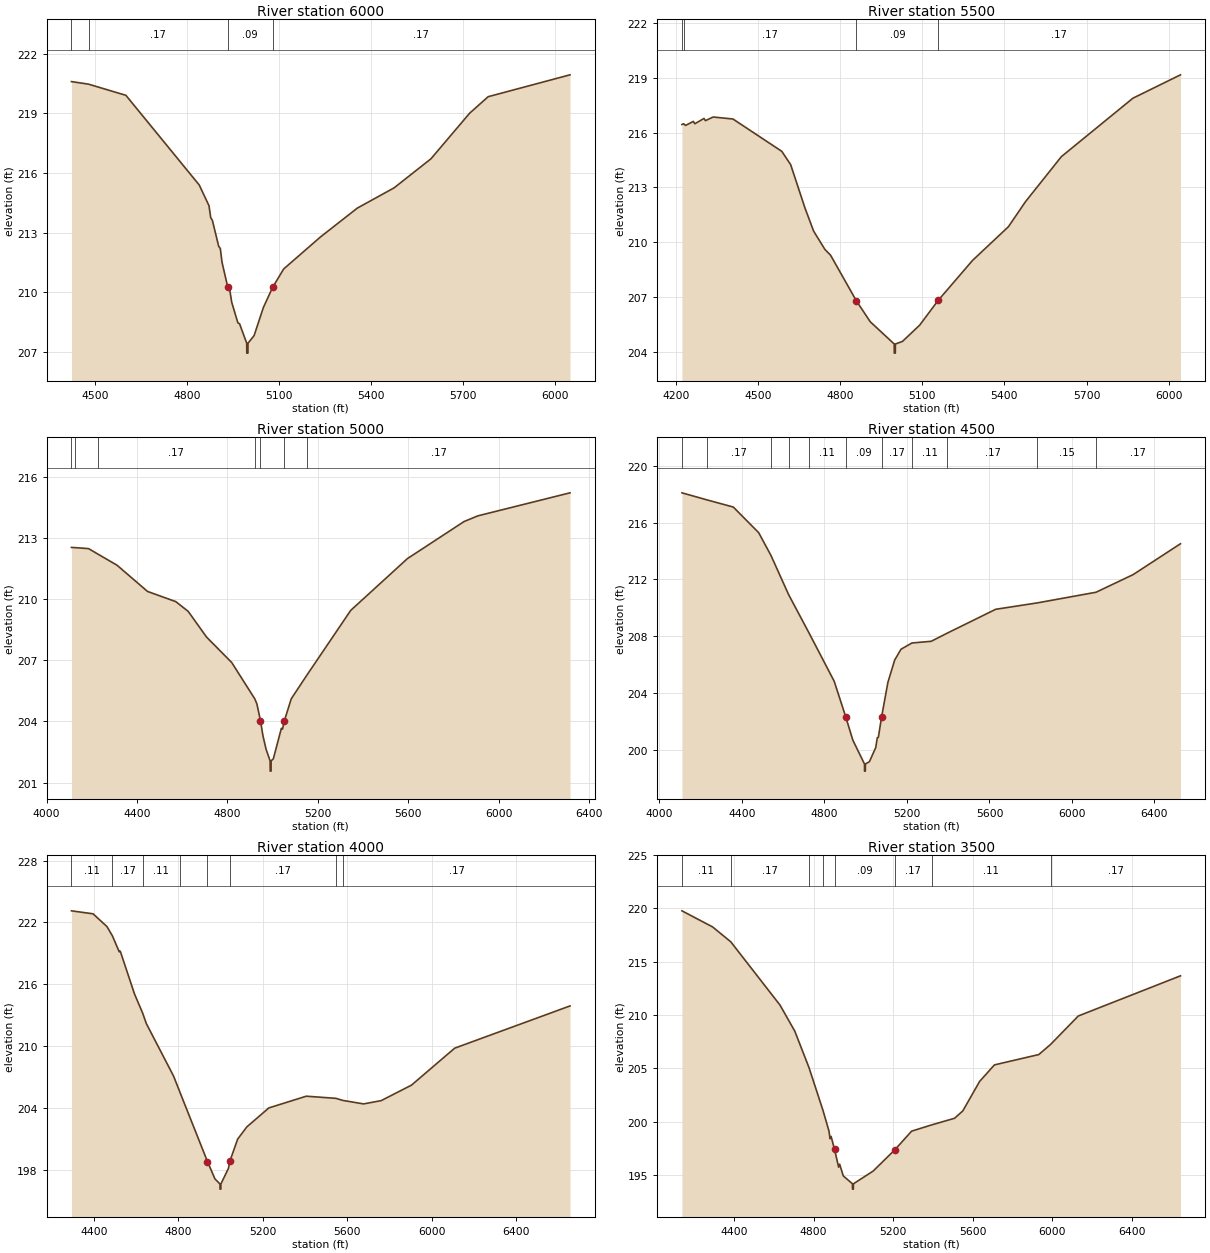
Type RM Length L Ch R = 1 ,6000    ,500,500,500
BEGIN DESCRIPTION:
CRYSTAL CREEK TRIBUTARY NO 3_1 12.0
END DESCRIPTION:
XS GIS Cut Line= 3
       3866041.9     10127643.11      3865496.27     10127456.39
      3864451.94     10127543.98
#Sta/Elev= 30
  4423.3   220.6    4479  220.47  4600.7  219.91  4839.8   215.4  4871.5  214.36
  4877.1  213.76  4882.4  213.63  4903.1  212.32  4908.4  212.21  4913.8  211.53
 4932.29210.2913  4939.7  210.08  4945.5  209.51  4965.7  208.47    4971  208.43
  4994.4  207.45  4994.7  206.95  4998.4  206.95  4998.6  207.45  5018.5  207.83
  5048.6  209.24  5078.7  210.25  5114.8  211.18  5234.8  212.79  5354.9  214.24
  5474.9  215.26  5594.9  216.72  5720.9  219.01  5781.2  219.84    6048  220.94
#Mann= 4 ,-1 , 0
  4423.3     .11       0    4479     .17       0 4932.29     .09       0
  5078.7     .17       0
Bank Sta=4932.29,5078.7
XS Rating Curve= 0 ,0
Exp/Cntr=0.3,0.1

Type RM Length L Ch R = 1 ,5500    ,500,500,500
BEGIN DESCRIPTION:
CRYSTAL CREEK TRIBUTARY NO 3_1 11.0
END DESCRIPTION:
XS GIS Cut Line= 3
        3866209.     10127178.82      3865462.82     10126962.16
      3864432.61     10127123.08
#Sta/Elev= 30
    4223  216.44  4228.7  216.48  4236.3  216.39  4264.7  216.61  4269.9  216.48
  4303.4  216.77  4308.6  216.65    4337  216.85  4409.3  216.74  4587.5  214.97
  4619.9  214.24    4672  211.87  4703.7   210.6  4744.8   209.6  4765.6  209.28
 4859.91206.7782  4910.2  205.64  4997.8  204.42  4998.1  203.92  5001.8  203.92
  5002.1  204.42  5027.8  204.56  5090.6  205.45  5158.4  206.81  5283.9     209
  5414.5  210.84  5477.3  212.22  5607.9  214.68  5869.1  217.88  6042.7  219.16
#Mann= 4 ,-1 , 0
    4223     .11       0  4228.7     .17       0 4859.91     .09       0
  5158.4     .17       0
Bank Sta=4859.91,5158.4
XS Rating Curve= 0 ,0
Exp/Cntr=0.3,0.1

Type RM Length L Ch R = 1 ,5000    ,500,500,500
BEGIN DESCRIPTION:
CRYSTAL CREEK TRIBUTARY NO 3_1 10.0
END DESCRIPTION:
XS GIS Cut Line= 3
       3866438.1     10126627.88      3865558.81     10126489.57
      3864260.96     10126701.85
#Sta/Elev= 30
  4109.9  212.54  4126.4  212.53    4186  212.48  4225.7  212.22  4311.1  211.67
  4446.3  210.38  4571.4  209.88  4626.4   209.4  4707.4  208.14  4818.8  206.89
  4920.7  205.11  4930.1  204.86 4945.87204.0443  4956.8   203.3  4970.6  202.64
  4988.7  202.06    4989  201.56  4992.7  201.56    4993  202.06    5003  202.17
  5038.3  203.66  5043.4  203.62  5051.6  204.03    5082  205.11  5153.6  206.31
  5345.2  209.45  5595.8  211.99  5846.4  213.81  5907.7  214.09  6315.1  215.22
#Mann= 7 ,-1 , 0
  4109.9     .17       0  4126.4     .11       0  4225.7     .17       0
  4920.7     .11       0 4945.87     .09       0  5051.6     .11       0
  5153.6     .17       0
Bank Sta=4945.87,5051.6
XS Rating Curve= 0 ,0
Exp/Cntr=0.3,0.1

Type RM Length L Ch R = 1 ,4500    ,500,500,500
BEGIN DESCRIPTION:
CRYSTAL CREEK TRIBUTARY NO 3_1 9.0
END DESCRIPTION:
XS GIS Cut Line= 3
      3866563.65     10126105.73      3865675.78     10126034.68
      3864178.57     10126330.73
#Sta/Elev= 30
  4109.3  218.09  4231.4  217.59  4358.3  217.09  4481.2  215.29  4540.8  213.69
  4626.2  210.94  4724.9  208.25  4847.4  204.84  4904.2   202.3  4937.7   200.7
  4994.3  199.02  4994.6  198.52  4998.4  198.52  4998.7  199.02  5018.3  199.19
  5048.9  200.18  5056.3  200.87  5061.4  200.89 5077.01202.3131  5107.6  204.75
  5140.6  206.33  5171.2  207.09  5224.1  207.53  5317.7  207.65  5396.4  208.23
  5630.4   209.9  5832.2  210.35    6117   211.1  6296.8  212.34  6526.2  214.51
#Mann= 11 ,-1 , 0
  4109.3     .11       0  4231.4     .17       0  4540.8     .11       0
  4626.2     .17       0  4724.9     .11       0  4904.2     .09       0
 5077.01     .17       0  5224.1     .11       0  5396.4     .17       0
  5832.2     .15       0    6117     .17       0
Bank Sta=4904.2,5077.01
XS Rating Curve= 0 ,0
Exp/Cntr=0.3,0.1

Type RM Length L Ch R = 1 ,4000    ,500,500,500
BEGIN DESCRIPTION:
CRYSTAL CREEK TRIBUTARY NO 3_1 8.0
END DESCRIPTION:
XS GIS Cut Line= 3
      3866425.69     10125594.07      3865720.78     10125538.47
      3864104.25     10125897.41
#Sta/Elev= 30
  4292.9  223.12  4395.3  222.83  4461.3  221.59  4487.2  220.68  4519.1  219.15
  4524.1  219.21  4591.7  215.05    4630  213.21  4647.9  212.17  4776.7  207.09
  4808.5  205.44 4937.47198.7889  4972.8  197.11  4996.8  196.61  4997.1  196.11
  5000.9  196.11  5001.2  196.61    5037  198.13    5044  198.84  5080.5  200.96
  5124.1  202.15  5228.4  203.99  5405.9  205.13  5546.6  204.92  5579.1  204.72
  5677.4  204.38    5761   204.7  5904.4   206.2  6109.3  209.79  6655.9  213.89
#Mann= 8 ,-1 , 0
  4292.9     .11       0  4487.2     .17       0    4630     .11       0
  4808.5     .15       0 4937.47     .09       0    5044     .17       0
  5546.6     .11       0  5579.1     .17       0
Bank Sta=4937.47,5044
XS Rating Curve= 0 ,0
Exp/Cntr=0.3,0.1

Type RM Length L Ch R = 1 ,3500    ,500,500,500
BEGIN DESCRIPTION:
CRYSTAL CREEK TRIBUTARY NO 3_1 7.0
END DESCRIPTION:
XS GIS Cut Line= 3
       3866518.6     10125241.22      3865678.36     10125050.09
      3864092.36     10125482.52
#Sta/Elev= 30
  4138.3  219.78  4292.3  218.27  4383.9  216.87  4631.3  210.93  4705.4  208.49
    4777  205.06  4847.5  201.03  4877.5  199.09  4882.7  198.39  4887.9  198.61
 4905.18197.3959  4925.8  195.72  4930.9     196  4949.2   194.9  4995.3  194.16
  4995.6  193.66  4999.7  193.66  5000.1  194.16  5098.9  195.35  5207.7  197.34
  5292.4   199.1  5393.7  199.69  5508.4  200.31  5549.8     201  5634.5  203.77
  5708.8  205.32  5931.7  206.29    5991  207.24  6130.3  209.91  6643.9  213.68
#Mann= 8 ,-1 , 0
  4138.3     .11       0  4383.9     .17       0    4777     .15       0
  4847.5     .17       0 4905.18     .09       0  5207.7     .17       0
  5393.7     .11       0    5991     .17       0
Bank Sta=4905.18,5207.7
XS Rating Curve= 0 ,0
Exp/Cntr=0.3,0.1

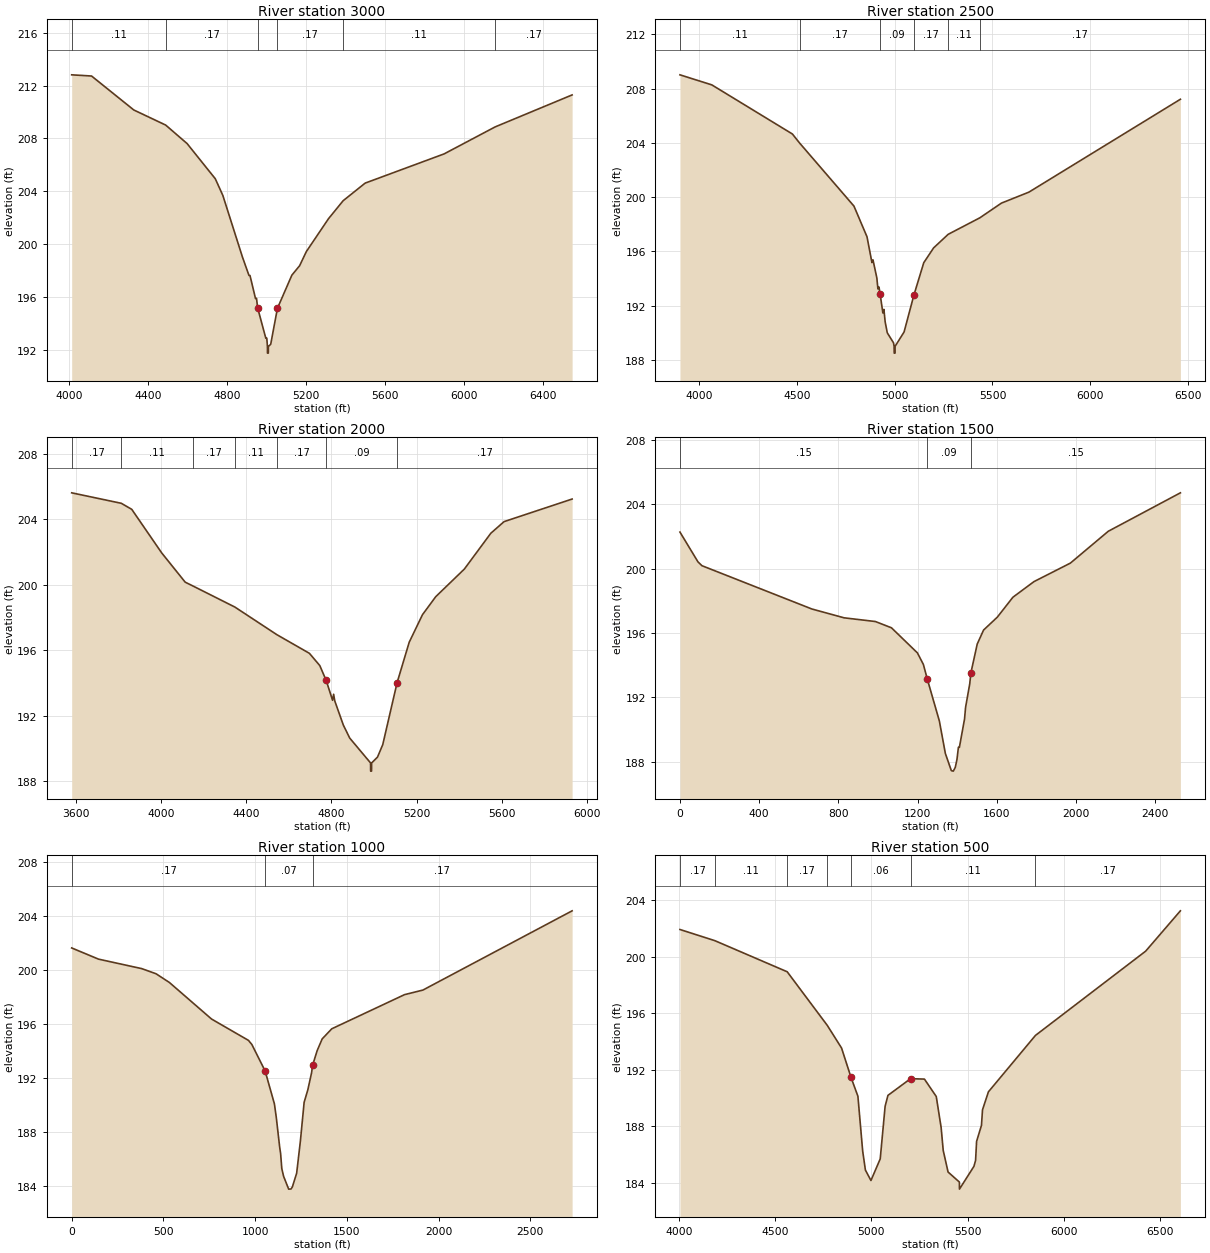
Type RM Length L Ch R = 1 ,3000    ,500,500,500
BEGIN DESCRIPTION:
CRYSTAL CREEK TRIBUTARY NO 3_1 6.0
END DESCRIPTION:
XS GIS Cut Line= 3
      3866599.06     10124845.03      3865653.27     10124561.06
      3864166.18     10124981.22
#Sta/Elev= 30
  4012.5  212.81  4113.1  212.72    4327  210.15  4488.2  209.01  4596.6  207.61
  4739.3  204.95  4777.5  203.69  4876.7  199.03  4909.7  197.64    4915  197.63
  4942.8  195.89    4948   195.9  4953.4   195.2    4995  192.89    5000  192.89
  5003.2  192.26  5003.6  191.76  5007.7  191.76    5008  192.26  5019.8  192.43
  5053.8  195.15    5127  197.66  5166.1  198.37  5200.1  199.44  5312.4  201.93
  5386.6  203.29  5497.9  204.62  5897.6  206.83  6155.6  208.87  6545.3  211.29
#Mann= 6 ,-1 , 0
  4012.5     .11       0  4488.2     .17       0  4953.4     .09       0
  5053.8     .17       0  5386.6     .11       0  6155.6     .17       0
Bank Sta=4953.4,5053.8
XS Rating Curve= 0 ,0
Exp/Cntr=0.3,0.1

Type RM Length L Ch R = 1 ,2500    ,500,500,500
BEGIN DESCRIPTION:
CRYSTAL CREEK TRIBUTARY NO 3_1 5.0
END DESCRIPTION:
XS GIS Cut Line= 3
      3866623.77     10124442.63      3865592.21      10124066.8
      3864161.42     10124361.88
#Sta/Elev= 30
  3902.1  209.01    4065  208.27  4477.1  204.65  4513.6  203.99  4791.8  199.34
  4858.5  197.08  4883.8  195.18  4889.1  195.38  4908.8  194.05  4914.3  193.24
  4919.7  193.38  4925.6192.8638  4939.6  191.47  4944.9  191.73  4951.4  190.81
  4962.1  190.01    4994  189.27  4997.2  189.01  4997.6  188.51  5001.8  188.51
  5002.1  189.01  5048.1  190.07  5098.4  192.79  5148.7  195.17    5199  196.26
  5273.4  197.26  5435.8  198.48  5545.8  199.56  5686.5  200.37  6460.9  207.21
#Mann= 6 ,-1 , 0
  3902.1     .11       0  4513.6     .17       0  4925.6     .09       0
  5098.4     .17       0  5273.4     .11       0  5435.8     .17       0
Bank Sta=4925.6,5098.4
XS Rating Curve= 0 ,0
Exp/Cntr=0.3,0.1

Type RM Length L Ch R = 1 ,2000    ,500,500,500
BEGIN DESCRIPTION:
CRYSTAL CREEK TRIBUTARY NO 3_1 4.0
END DESCRIPTION:
XS GIS Cut Line= 3
      3866598.99     10123941.21      3865183.89     10123819.79
      3864265.25     10123965.98
#Sta/Elev= 30
  3579.7  205.62  3812.8  204.98  3861.9  204.61  4002.4  201.95  4112.8  200.16
  4148.6  199.93    4346  198.64  4543.4  196.95  4696.3  195.81  4745.1  195.06
  4775.2  194.15    4805  192.94    4810  193.31  4815.4   192.9  4855.5  191.43
  4885.6  190.63  4983.5  189.11  4983.8  188.61  4988.1  188.61  4988.5  189.11
  5016.2  189.47  5040.8  190.23    5108  194.01  5165.1  196.49  5227.3  198.17
  5289.5  199.27    5424  200.96  5548.4  203.15  5610.6  203.86  5930.2  205.24
#Mann= 7 ,-1 , 0
  3579.7     .17       0  3812.8     .11       0  4148.6     .17       0
    4346     .11       0  4543.4     .17       0  4775.2     .09       0
    5108     .17       0
Bank Sta=4775.2,5108
XS Rating Curve= 0 ,0
Exp/Cntr=0.3,0.1

Type RM Length L Ch R = 1 ,1500    ,500,500,500
XS GIS Cut Line= 4
      3866698.09     10123526.46      3865302.43     10123355.61
      3865093.51     10123288.11      3864421.24     10123888.71
#Sta/Elev= 30
       0  202.27    90.9  200.42   111.1  200.18   665.9  197.49   828.8  196.94
   986.7  196.71  1068.1  196.32  1199.1  194.76  1229.3  194.04  1249.5  193.11
  1309.9  190.53  1340.2  188.51  1370.4  187.44  1380.5  187.41  1390.5  187.65
  1398.9  188.14  1406.1  188.89  1411.1  188.89  1437.1  190.65  1442.4  191.38
  1463.4  192.84  1469.2  193.52  1501.2  195.31  1533.2  196.18  1602.5  196.98
  1681.4  198.22  1787.6  199.19  1971.5  200.34  2162.9  202.32  2527.1  204.71
#Mann= 3 , 0 , 0
       0     .15       0  1249.5     .09       0  1469.2     .15       0
Bank Sta=1249.5,1469.2
XS Rating Curve= 0 ,0
Exp/Cntr=0.3,0.1

Type RM Length L Ch R = 1 ,1000    ,500,500,500
XS GIS Cut Line= 4
      3866673.33     10123055.98      3865498.46     10122899.81
      3865216.87      10122846.7      3864417.65     10123817.01
#Sta/Elev= 30
       0  201.62   146.4  200.79   381.3  200.09   459.6  199.71   532.8  199.06
   762.7  196.35   963.9  194.77   982.5  194.46  1054.7   192.5  1105.1  190.07
  1115.2  189.09    1134  186.85    1139  186.39  1145.5  185.27  1155.5  184.69
    1183  183.75    1196  183.76  1203.2  183.92  1226.5  184.93  1246.9  187.32
  1267.2  190.18  1287.6  191.12  1307.9  192.38  1313.2  192.92  1338.5  194.02
  1365.6  194.88    1418  195.63  1814.6  198.16    1915   198.5  2728.2  204.37
#Mann= 3 , 0 , 0
       0     .17       0  1054.7     .07       0  1313.2     .17       0
Bank Sta=1054.7,1313.2
XS Rating Curve= 0 ,0
Exp/Cntr=0.3,0.1

Type RM Length L Ch R = 1 ,500     ,0,0,0
BEGIN DESCRIPTION:
CRYSTAL CREEK TRIBUTARY NO 3_1 1.0
END DESCRIPTION:
XS GIS Cut Line= 3
      3866698.05     10122864.06      3865769.07     10122510.75
      3864259.07     10121966.47
#Sta/Elev= 30
  4006.1  201.92  4187.3  201.13  4563.1  198.93  4771.2  195.14  4845.3  193.54
  4894.3  191.47  4930.3  190.13    4955  186.26  4969.2  184.91    4998  184.17
  5046.2   185.7  5071.6  189.42  5086.3  190.19  5203.7  191.37  5275.8  191.34
  5337.2  190.11  5362.5  187.92  5373.3   186.3  5398.5  184.77  5457.3  184.06
  5457.7  183.56  5532.8  185.17  5541.4  185.59  5546.7  186.94    5572  188.07
  5577.4  189.17  5608.1  190.44  5852.4  194.43  6424.9  200.39  6605.1  203.24
#Mann= 7 ,-1 , 0
  4006.1     .17       0  4187.3     .11       0  4563.1     .17       0
  4771.2     .11       0  4894.3     .06       0  5203.7     .11       0
  5852.4     .17       0
Bank Sta=4894.3,5203.7
XS Rating Curve= 0 ,0
Exp/Cntr=0.3,0.1

Chan Stop Cuts=-1
Use User Specified Reach Order=0
Composite Channel Slope=5

--- CRYSTAL CREEK TRIBUTARY NO 3_1.g10 (geometry) ---

Geom Title=Existing Conditions
Program Version=4.10

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
River Reach=CRYSTAL CREEK TR,Reach-1

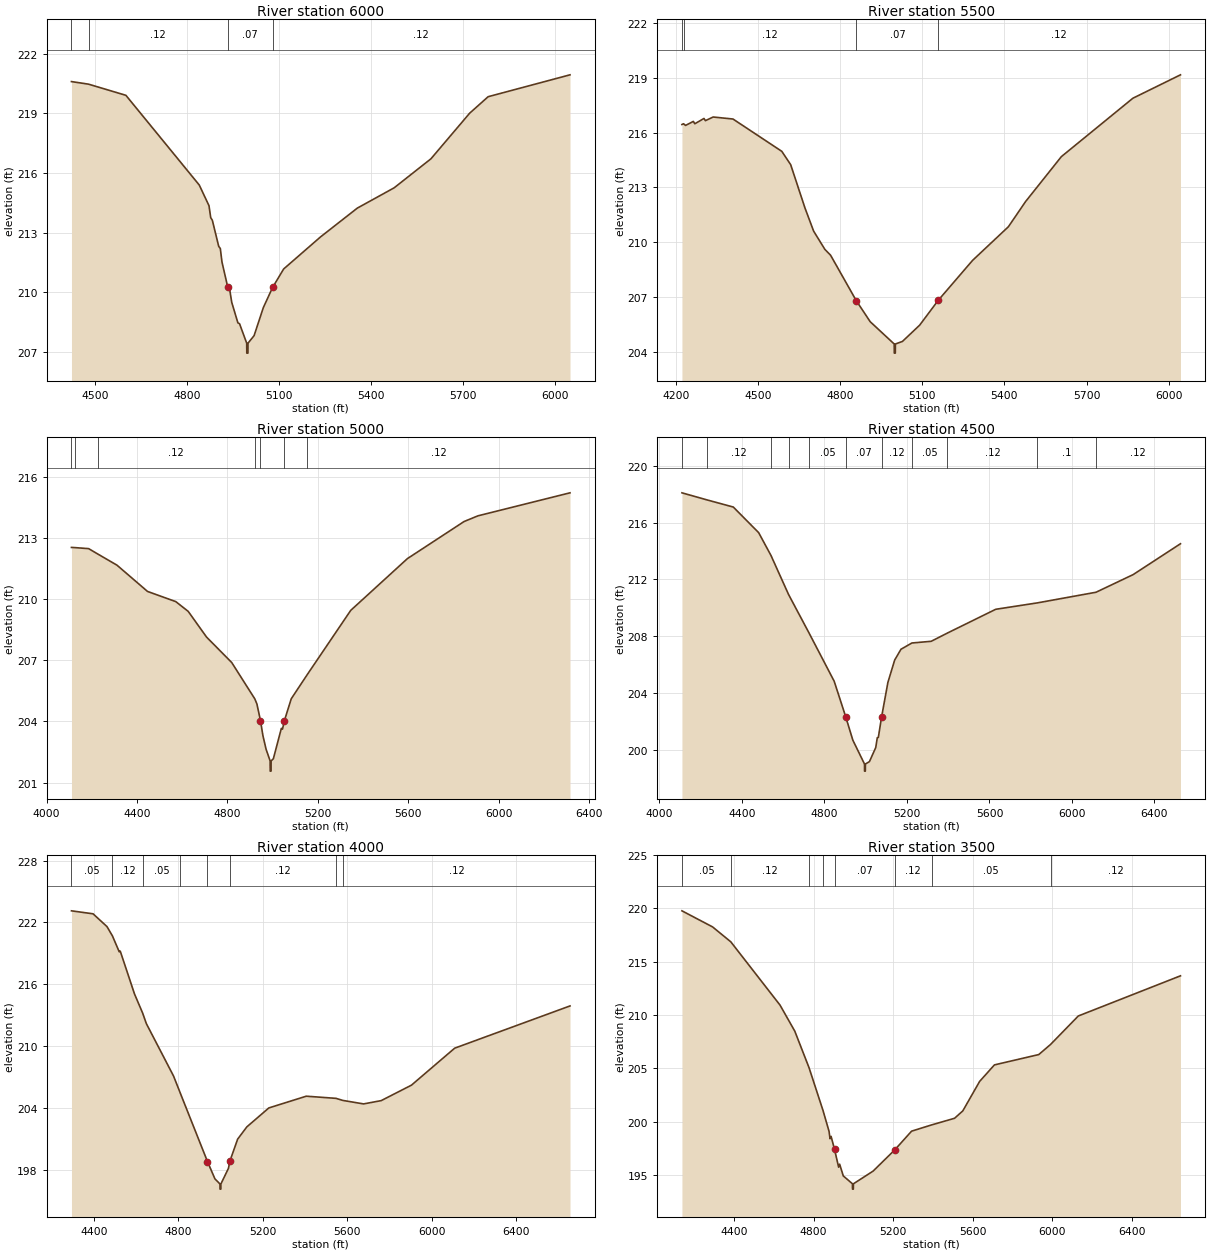
Type RM Length L Ch R = 1 ,6000    ,500,500,500
BEGIN DESCRIPTION:
CRYSTAL CREEK TRIBUTARY NO 3_1 12.0
END DESCRIPTION:
XS GIS Cut Line= 3
       3866041.9     10127643.11      3865496.27     10127456.39
      3864451.94     10127543.98
#Sta/Elev= 30
  4423.3   220.6    4479  220.47  4600.7  219.91  4839.8   215.4  4871.5  214.36
  4877.1  213.76  4882.4  213.63  4903.1  212.32  4908.4  212.21  4913.8  211.53
 4932.29 210.291  4939.7  210.08  4945.5  209.51  4965.7  208.47    4971  208.43
  4994.4  207.45  4994.7  206.95  4998.4  206.95  4998.6  207.45  5018.5  207.83
  5048.6  209.24  5078.7  210.25  5114.8  211.18  5234.8  212.79  5354.9  214.24
  5474.9  215.26  5594.9  216.72  5720.9  219.01  5781.2  219.84    6048  220.94
#Mann= 4 ,-1 , 0
  4423.3     .05       0    4479     .12       0 4932.29     .07       0
  5078.7     .12       0
Bank Sta=4932.29,5078.7
XS Rating Curve= 0 ,0
Exp/Cntr=0.3,0.1

Type RM Length L Ch R = 1 ,5500    ,500,500,500
BEGIN DESCRIPTION:
CRYSTAL CREEK TRIBUTARY NO 3_1 11.0
END DESCRIPTION:
XS GIS Cut Line= 3
        3866209.     10127178.82      3865462.82     10126962.16
      3864432.61     10127123.08
#Sta/Elev= 30
    4223  216.44  4228.7  216.48  4236.3  216.39  4264.7  216.61  4269.9  216.48
  4303.4  216.77  4308.6  216.65    4337  216.85  4409.3  216.74  4587.5  214.97
  4619.9  214.24    4672  211.87  4703.7   210.6  4744.8   209.6  4765.6  209.28
 4859.91 206.778  4910.2  205.64  4997.8  204.42  4998.1  203.92  5001.8  203.92
  5002.1  204.42  5027.8  204.56  5090.6  205.45  5158.4  206.81  5283.9     209
  5414.5  210.84  5477.3  212.22  5607.9  214.68  5869.1  217.88  6042.7  219.16
#Mann= 4 ,-1 , 0
    4223     .05       0  4228.7     .12       0 4859.91     .07       0
  5158.4     .12       0
Bank Sta=4859.91,5158.4
XS Rating Curve= 0 ,0
Exp/Cntr=0.3,0.1

Type RM Length L Ch R = 1 ,5000    ,500,500,500
BEGIN DESCRIPTION:
CRYSTAL CREEK TRIBUTARY NO 3_1 10.0
END DESCRIPTION:
XS GIS Cut Line= 3
       3866438.1     10126627.88      3865558.81     10126489.57
      3864260.96     10126701.85
#Sta/Elev= 30
  4109.9  212.54  4126.4  212.53    4186  212.48  4225.7  212.22  4311.1  211.67
  4446.3  210.38  4571.4  209.88  4626.4   209.4  4707.4  208.14  4818.8  206.89
  4920.7  205.11  4930.1  204.86 4945.87 204.044  4956.8   203.3  4970.6  202.64
  4988.7  202.06    4989  201.56  4992.7  201.56    4993  202.06    5003  202.17
  5038.3  203.66  5043.4  203.62  5051.6  204.03    5082  205.11  5153.6  206.31
  5345.2  209.45  5595.8  211.99  5846.4  213.81  5907.7  214.09  6315.1  215.22
#Mann= 7 ,-1 , 0
  4109.9     .12       0  4126.4     .05       0  4225.7     .12       0
  4920.7     .05       0 4945.87     .07       0  5051.6     .05       0
  5153.6     .12       0
Bank Sta=4945.87,5051.6
XS Rating Curve= 0 ,0
Exp/Cntr=0.3,0.1

Type RM Length L Ch R = 1 ,4500    ,500,500,500
BEGIN DESCRIPTION:
CRYSTAL CREEK TRIBUTARY NO 3_1 9.0
END DESCRIPTION:
XS GIS Cut Line= 3
      3866563.65     10126105.73      3865675.78     10126034.68
      3864178.57     10126330.73
#Sta/Elev= 30
  4109.3  218.09  4231.4  217.59  4358.3  217.09  4481.2  215.29  4540.8  213.69
  4626.2  210.94  4724.9  208.25  4847.4  204.84  4904.2   202.3  4937.7   200.7
  4994.3  199.02  4994.6  198.52  4998.4  198.52  4998.7  199.02  5018.3  199.19
  5048.9  200.18  5056.3  200.87  5061.4  200.89 5077.01 202.313  5107.6  204.75
  5140.6  206.33  5171.2  207.09  5224.1  207.53  5317.7  207.65  5396.4  208.23
  5630.4   209.9  5832.2  210.35    6117   211.1  6296.8  212.34  6526.2  214.51
#Mann= 11 ,-1 , 0
  4109.3     .05       0  4231.4     .12       0  4540.8     .05       0
  4626.2     .12       0  4724.9     .05       0  4904.2     .07       0
 5077.01     .12       0  5224.1     .05       0  5396.4     .12       0
  5832.2      .1       0    6117     .12       0
Bank Sta=4904.2,5077.01
XS Rating Curve= 0 ,0
Exp/Cntr=0.3,0.1

Type RM Length L Ch R = 1 ,4000    ,500,500,500
BEGIN DESCRIPTION:
CRYSTAL CREEK TRIBUTARY NO 3_1 8.0
END DESCRIPTION:
XS GIS Cut Line= 3
      3866425.69     10125594.07      3865720.78     10125538.47
      3864104.25     10125897.41
#Sta/Elev= 30
  4292.9  223.12  4395.3  222.83  4461.3  221.59  4487.2  220.68  4519.1  219.15
  4524.1  219.21  4591.7  215.05    4630  213.21  4647.9  212.17  4776.7  207.09
  4808.5  205.44 4937.47 198.789  4972.8  197.11  4996.8  196.61  4997.1  196.11
  5000.9  196.11  5001.2  196.61    5037  198.13    5044  198.84  5080.5  200.96
  5124.1  202.15  5228.4  203.99  5405.9  205.13  5546.6  204.92  5579.1  204.72
  5677.4  204.38    5761   204.7  5904.4   206.2  6109.3  209.79  6655.9  213.89
#Mann= 8 ,-1 , 0
  4292.9     .05       0  4487.2     .12       0    4630     .05       0
  4808.5      .1       0 4937.47     .07       0    5044     .12       0
  5546.6     .05       0  5579.1     .12       0
Bank Sta=4937.47,5044
XS Rating Curve= 0 ,0
Exp/Cntr=0.3,0.1

Type RM Length L Ch R = 1 ,3500    ,500,500,500
BEGIN DESCRIPTION:
CRYSTAL CREEK TRIBUTARY NO 3_1 7.0
END DESCRIPTION:
XS GIS Cut Line= 3
       3866518.6     10125241.22      3865678.36     10125050.09
      3864092.36     10125482.52
#Sta/Elev= 30
  4138.3  219.78  4292.3  218.27  4383.9  216.87  4631.3  210.93  4705.4  208.49
    4777  205.06  4847.5  201.03  4877.5  199.09  4882.7  198.39  4887.9  198.61
 4905.18 197.396  4925.8  195.72  4930.9     196  4949.2   194.9  4995.3  194.16
  4995.6  193.66  4999.7  193.66  5000.1  194.16  5098.9  195.35  5207.7  197.34
  5292.4   199.1  5393.7  199.69  5508.4  200.31  5549.8     201  5634.5  203.77
  5708.8  205.32  5931.7  206.29    5991  207.24  6130.3  209.91  6643.9  213.68
#Mann= 8 ,-1 , 0
  4138.3     .05       0  4383.9     .12       0    4777      .1       0
  4847.5     .12       0 4905.18     .07       0  5207.7     .12       0
  5393.7     .05       0    5991     .12       0
Bank Sta=4905.18,5207.7
XS Rating Curve= 0 ,0
Exp/Cntr=0.3,0.1

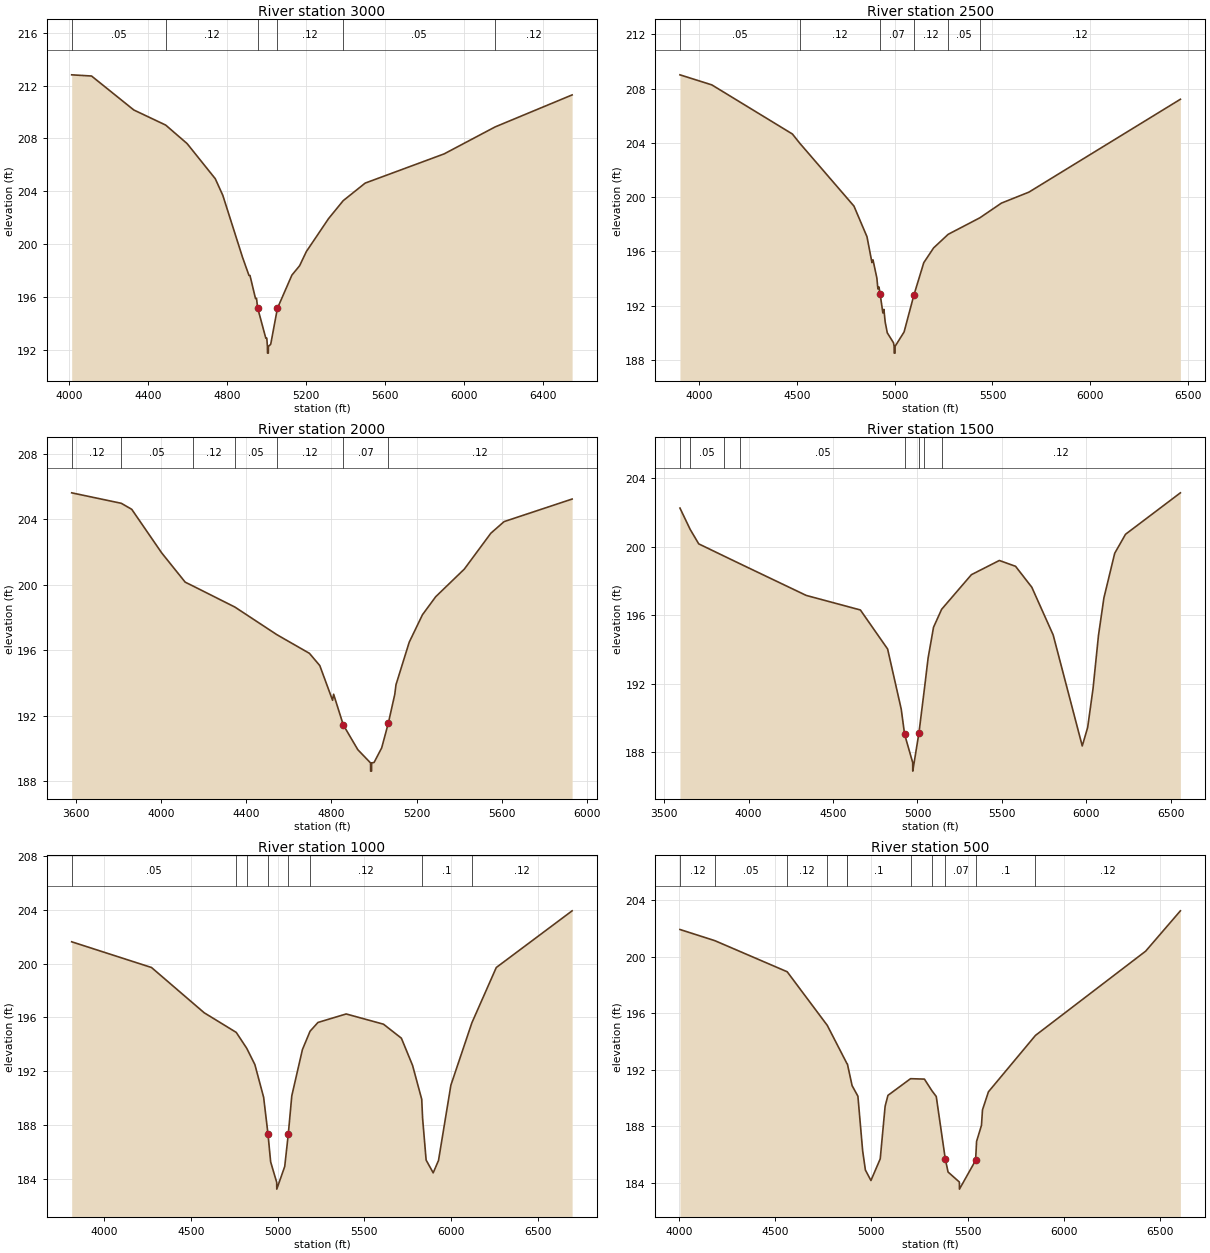
Type RM Length L Ch R = 1 ,3000    ,500,500,500
BEGIN DESCRIPTION:
CRYSTAL CREEK TRIBUTARY NO 3_1 6.0
END DESCRIPTION:
XS GIS Cut Line= 3
      3866599.06     10124845.03      3865653.27     10124561.06
      3864166.18     10124981.22
#Sta/Elev= 30
  4012.5  212.81  4113.1  212.72    4327  210.15  4488.2  209.01  4596.6  207.61
  4739.3  204.95  4777.5  203.69  4876.7  199.03  4909.7  197.64    4915  197.63
  4942.8  195.89    4948   195.9  4953.4   195.2    4995  192.89    5000  192.89
  5003.2  192.26  5003.6  191.76  5007.7  191.76    5008  192.26  5019.8  192.43
  5053.8  195.15    5127  197.66  5166.1  198.37  5200.1  199.44  5312.4  201.93
  5386.6  203.29  5497.9  204.62  5897.6  206.83  6155.6  208.87  6545.3  211.29
#Mann= 6 ,-1 , 0
  4012.5     .05       0  4488.2     .12       0  4953.4     .07       0
  5053.8     .12       0  5386.6     .05       0  6155.6     .12       0
Bank Sta=4953.4,5053.8
XS Rating Curve= 0 ,0
Exp/Cntr=0.3,0.1

Type RM Length L Ch R = 1 ,2500    ,500,500,500
BEGIN DESCRIPTION:
CRYSTAL CREEK TRIBUTARY NO 3_1 5.0
END DESCRIPTION:
XS GIS Cut Line= 3
      3866623.77     10124442.63      3865592.21      10124066.8
      3864161.42     10124361.88
#Sta/Elev= 30
  3902.1  209.01    4065  208.27  4477.1  204.65  4513.6  203.99  4791.8  199.34
  4858.5  197.08  4883.8  195.18  4889.1  195.38  4908.8  194.05  4914.3  193.24
  4919.7  193.38  4925.6 192.864  4939.6  191.47  4944.9  191.73  4951.4  190.81
  4962.1  190.01    4994  189.27  4997.2  189.01  4997.6  188.51  5001.8  188.51
  5002.1  189.01  5048.1  190.07  5098.4  192.79  5148.7  195.17    5199  196.26
  5273.4  197.26  5435.8  198.48  5545.8  199.56  5686.5  200.37  6460.9  207.21
#Mann= 6 ,-1 , 0
  3902.1     .05       0  4513.6     .12       0  4925.6     .07       0
  5098.4     .12       0  5273.4     .05       0  5435.8     .12       0
Bank Sta=4925.6,5098.4
XS Rating Curve= 0 ,0
Exp/Cntr=0.3,0.1

Type RM Length L Ch R = 1 ,2000    ,500,500,500
BEGIN DESCRIPTION:
CRYSTAL CREEK TRIBUTARY NO 3_1 4.0
END DESCRIPTION:
XS GIS Cut Line= 3
      3866598.99     10123941.21      3865183.89     10123819.79
      3864265.25     10123965.98
#Sta/Elev= 30
  3579.7  205.62  3812.8  204.98  3861.9  204.61  4002.4  201.95  4112.8  200.16
  4148.6  199.93    4346  198.64  4543.4  196.95  4696.3  195.81  4745.1  195.06
    4805  192.94    4810  193.31  4855.5  191.43  4923.7  189.92  4983.5  189.11
  4983.8  188.61  4988.1  188.61  4988.5  189.11    5000  189.14  5035.7  190.03
  5066.9  191.54  5097.2   193.3  5102.9  193.89  5165.1  196.49  5227.3  198.17
  5289.5  199.27    5424  200.96  5548.4  203.15  5610.6  203.86  5930.2  205.24
#Mann= 7 ,-1 , 0
  3579.7     .12       0  3812.8     .05       0  4148.6     .12       0
    4346     .05       0  4543.4     .12       0  4855.5     .07       0
  5066.9     .12       0
Bank Sta=4855.5,5066.9
XS Rating Curve= 0 ,0
Exp/Cntr=0.3,0.1

Type RM Length L Ch R = 1 ,1500    ,500,500,500
BEGIN DESCRIPTION:
CRYSTAL CREEK TRIBUTARY NO 3_1 3.0
END DESCRIPTION:
XS GIS Cut Line= 3
      3866698.11     10123526.46      3865302.43     10123355.61
      3863821.23     10122877.01
#Sta/Elev= 30
  3593.9  202.27  3654.1  201.03    3705  200.18    3852  199.48  3950.9  199.01
  4341.3  197.17    4662  196.32  4823.3  194.04  4903.9  190.53    4924  189.05
  4971.8  187.41  4972.2  186.91 5008.87 189.151  5040.7  191.68  5063.1  193.52
  5095.1  195.31  5143.1  196.36  5319.3  198.38  5484.7  199.21  5580.7  198.87
  5676.8  197.65  5803.5  194.86  5975.6  188.38  6007.6  189.46  6039.6  191.74
  6071.6  194.83  6103.7  197.02  6167.7  199.63  6231.8  200.74  6556.6  203.16
#Mann= 8 ,-1 , 0
  3593.9     .12       0  3654.1     .05       0    3852     .12       0
  3950.9     .05       0    4924     .07       0 5008.87     .05       0
  5040.7      .1       0  5143.1     .12       0
Bank Sta=4924,5008.87
XS Rating Curve= 0 ,0
Exp/Cntr=0.3,0.1

Type RM Length L Ch R = 1 ,1000    ,500,500,500
BEGIN DESCRIPTION:
CRYSTAL CREEK TRIBUTARY NO 3_1 2.0
END DESCRIPTION:
XS GIS Cut Line= 3
      3866673.33     10123055.98      3865498.46     10122899.81
      3863831.94     10122585.51
#Sta/Elev= 30
  3814.8  201.62  4274.4  199.71  4577.5  196.35  4762.3  194.89  4822.6  193.71
  4869.5   192.5  4919.9  190.07 4945.03 187.335  4960.3  185.27  4995.2  183.75
  4995.6  183.25  5041.3  184.93  5061.7  187.32    5082  190.18  5143.1  193.61
  5187.3  194.98  5232.8  195.63  5395.1  196.26  5609.9   195.5    5713  194.46
  5777.3  192.44  5830.1  189.92  5835.1  188.51  5855.4  185.41  5896.1  184.46
  5926.7  185.38  5997.9  190.97  6118.7   195.6  6259.3  199.71  6695.9  203.92
#Mann= 8 ,-1 , 0
  3814.8     .05       0  4762.3     .12       0  4822.6      .1       0
 4945.03     .07       0  5061.7      .1       0  5187.3     .12       0
  5830.1      .1       0  6118.7     .12       0
Bank Sta=4945.03,5061.7
XS Rating Curve= 0 ,0
Exp/Cntr=0.3,0.1

Type RM Length L Ch R = 1 ,500     ,0,0,0
BEGIN DESCRIPTION:
CRYSTAL CREEK TRIBUTARY NO 3_1 1.0
END DESCRIPTION:
XS GIS Cut Line= 3
      3866698.05     10122864.06      3865769.07     10122510.75
      3864259.07     10121966.47
#Sta/Elev= 30
  4006.1  201.92  4187.3  201.13  4563.1  198.93  4771.2  195.14  4873.3  192.44
  4875.7  192.41  4900.1  190.88  4930.3  190.13    4955  186.26  4969.2  184.91
    4998  184.17  5046.2   185.7  5071.6  189.42  5086.3  190.19  5203.7  191.37
  5275.8  191.34    5314  190.53  5337.2  190.11    5384   185.7  5398.5  184.77
  5457.3  184.06  5457.7  183.56  5541.4  185.59  5546.7  186.94    5572  188.07
  5577.4  189.17  5608.1  190.44  5852.4  194.43  6424.9  200.39  6605.1  203.24
#Mann= 11 ,-1 , 0
  4006.1     .12       0  4187.3     .05       0  4563.1     .12       0
  4771.2     .05       0  4873.3     .12       0  4875.7      .1       0
  5203.7     .12       0    5314      .1       0    5384     .07       0
  5541.4      .1       0  5852.4     .12       0
Bank Sta=5384,5541.4
XS Rating Curve= 0 ,0
Exp/Cntr=0.3,0.1