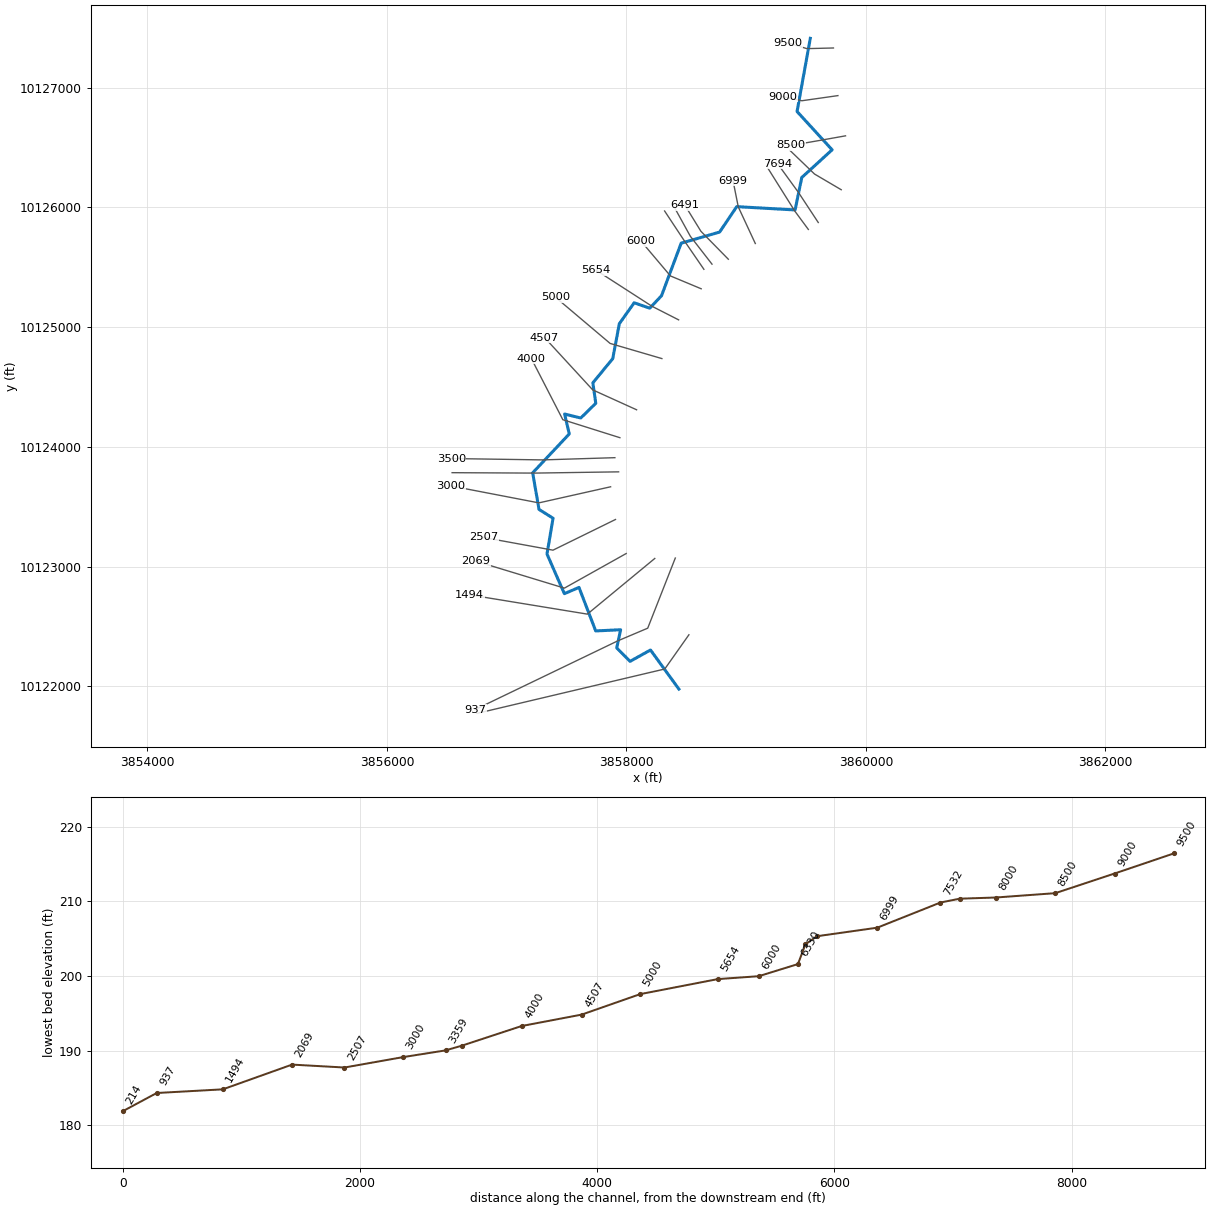
--- CRYSTAL CREEK TRIBUTARY NO 4.prj (project) ---

Proj Title=CRYSTAL CREEK TRIBUTARY NO 4 Base Level Engineering
Current Plan=p01
Default Exp/Contr=0.3,0.1
English Units
Geom File=g01
Flow File=f01
Plan File=p01
Y Axis Title=Elevation
X Axis Title(PF)=Main Channel Distance
X Axis Title(XS)=Station
BEGIN DESCRIPTION:
CRYSTAL CREEK TRIBUTARY NO 4
END DESCRIPTION:
DSS Export Rating Curves= 0
DSS Export Rating Curve Sorted= 0
DSS Export Volume Flow Curves= 0
DXF OffsetX= 0
DXF OffsetY= 0
DXF ScaleX= 1
DXF ScaleY= 10

--- CRYSTAL CREEK TRIBUTARY NO 4.p01 (plan) ---

Plan Title=Multiple Run
Short Identifier=Multiple
Geom File=g01
Flow File=f01
Subcritical Flow
K Sum by GR= 0
Std Step Tol= 0.01
Critical Tol= 0.01
Num of Std Step Trials= 20
Max Error Tol= 0.3
Flow Tol Ratio= 0.001
Split Flow NTrial= 30
Split Flow Tol= 0.02
Split Flow Ratio= 0.02
Log Output Level= 0
Friction Slope Method= 1
Unsteady Friction Slope Method= 2
Unsteady Bridges Friction Slope Method= 1
Parabolic Critical Depth
Global Vel Dist=  1 , 1 , 1
Global Log Level= 0
CheckData=True
Encroach Param= -1, 0, 0, 0
BEGIN DESCRIPTION:
Multiple Run
END DESCRIPTION:

--- CRYSTAL CREEK TRIBUTARY NO 4.f01 (steady flow) ---

Flow Title=Multiple
Program Version=4.10
Number of Profiles= 7
Profile Names=10-year,25-year,50-year,1pct_min,100-year,1pct_plu,500-year
River Rch & RM=CRYSTAL CREEK TR,Reach-1         ,9500
     559     740     984     431    1301    3929    2351
River Rch & RM=CRYSTAL CREEK TR,Reach-1         ,3500
     984    1352    1843     827    2496    7538    4725
River Rch & RM=CRYSTAL CREEK TR,Reach-1         ,3359
     984    1352    1843     827    2496    7538    4725
River Rch & RM=CRYSTAL CREEK TR,Reach-1         ,937
    4391    6297    8841    4053   12240   36964   24257
River Rch & RM=CRYSTAL CREEK TR,Reach-1         ,214
    4391    6297    8841    4053   12240   36964   24257
Boundary for River Rch & Prof#=CRYSTAL CREEK TR,Reach-1         , 1
Up Type= 0
Dn Type= 3
Dn Slope=0.006
Boundary for River Rch & Prof#=CRYSTAL CREEK TR,Reach-1         , 2
Up Type= 0
Dn Type= 3
Dn Slope=0.006
Boundary for River Rch & Prof#=CRYSTAL CREEK TR,Reach-1         , 3
Up Type= 0
Dn Type= 3
Dn Slope=0.006
Boundary for River Rch & Prof#=CRYSTAL CREEK TR,Reach-1         , 4
Up Type= 0
Dn Type= 3
Dn Slope=0.006
Boundary for River Rch & Prof#=CRYSTAL CREEK TR,Reach-1         , 5
Up Type= 0
Dn Type= 3
Dn Slope=0.006
Boundary for River Rch & Prof#=CRYSTAL CREEK TR,Reach-1         , 6
Up Type= 0
Dn Type= 3
Dn Slope=0.006
Boundary for River Rch & Prof#=CRYSTAL CREEK TR,Reach-1         , 7
Up Type= 0
Dn Type= 3
Dn Slope=0.006
DSS Import GetInterval= 0
DSS Import GetPeak= 0
DSS Import FillOption= 0

--- CRYSTAL CREEK TRIBUTARY NO 4.g01 (geometry) ---

Geom Title=Existing Conditions
Program Version=4.10

River Reach=CRYSTAL CREEK TR,Reach-1
Reach XY= 30
      3859535.96     10127411.79      3859425.31     10126800.66
      3859718.26     10126480.78      3859464.54      10126249.2
       3859409.2     10125978.45      3858921.48     10126006.09
      3858778.56     10125793.77      3858457.44     10125700.83
      3858293.36     10125262.09      3858195.07     10125157.82
      3858064.94     10125202.98      3857941.12     10125028.56
      3857885.75     10124736.01      3857719.68     10124534.37
      3857744.31     10124363.68      3857618.78      10124240.7
      3857483.74     10124273.97      3857522.88     10124107.62
      3857217.22     10123782.76      3857270.08     10123477.47
      3857387.34     10123403.49      3857336.69     10123104.66
      3857482.13     10122773.46      3857604.01     10122825.79
      3857743.54     10122462.38      3857951.87     10122472.14
      3857919.23     10122320.15      3858030.74      10122208.3
       3858201.3     10122303.04      3858438.24     10121976.86

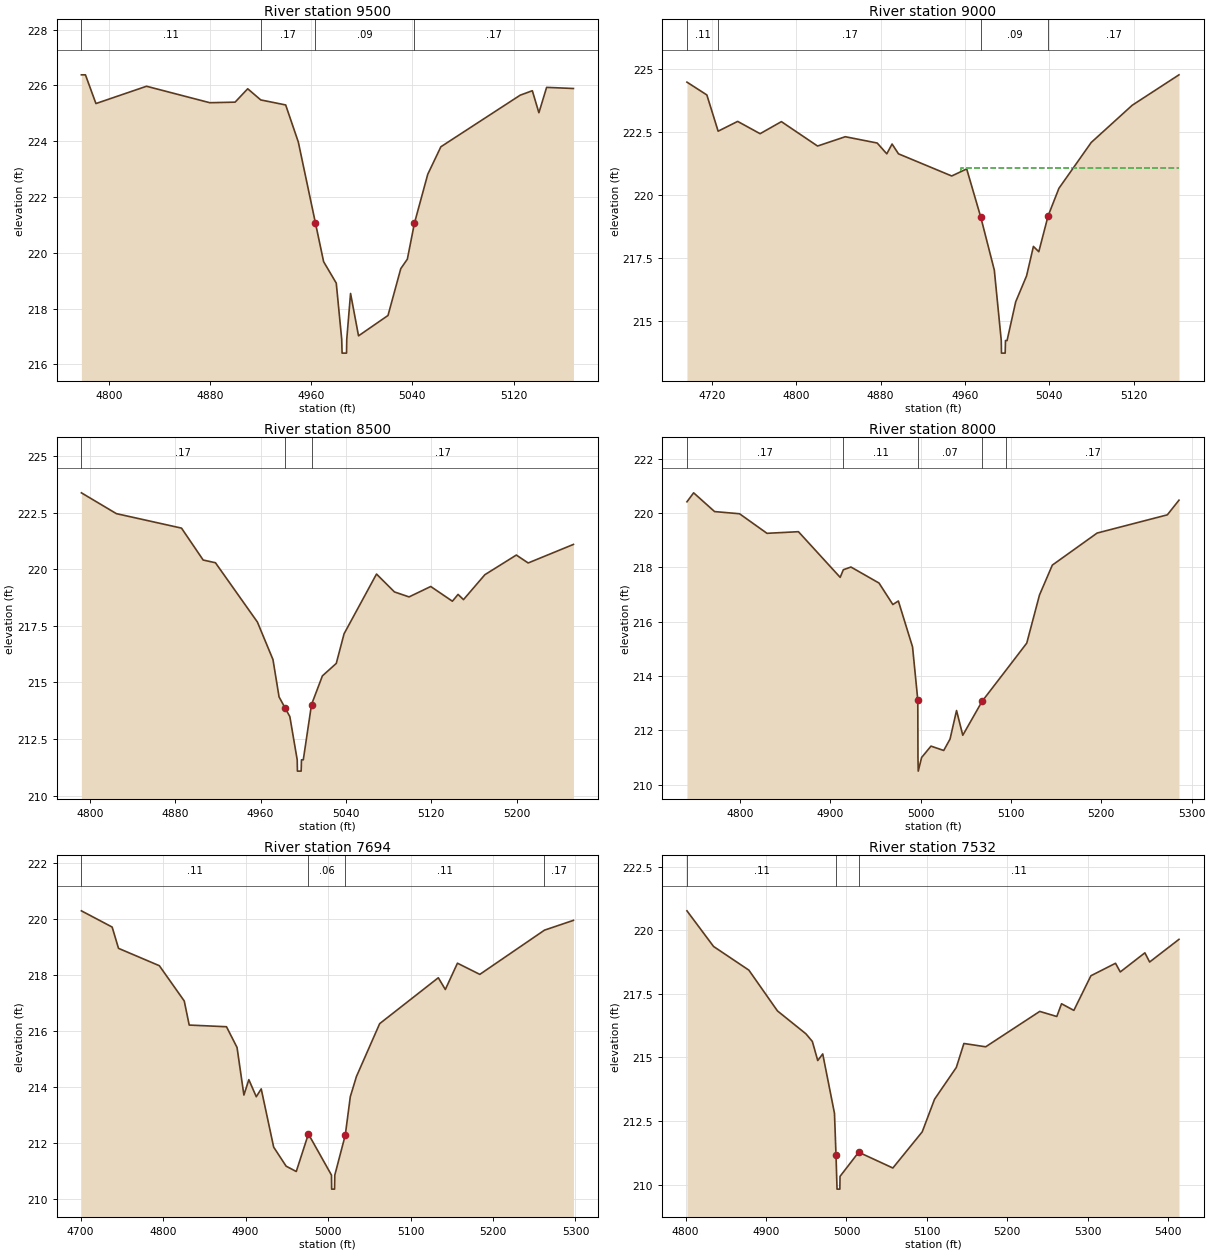
Type RM Length L Ch R = 1 ,9500    ,500,500,500
BEGIN DESCRIPTION:
CRYSTAL CREEK TRIBUTARY NO 4 19.0
END DESCRIPTION:
XS GIS Cut Line= 3
      3859729.31     10127331.21      3859507.67     10127325.76
      3859347.54      10127374.2
#Sta/Elev= 30
  4778.3  226.38  4781.5  226.38  4789.8  225.35  4829.8  225.97  4879.8  225.38
  4899.8   225.4  4909.8  225.88  4920.1  225.48  4939.8   225.3  4949.8  223.97
 4963.31221.0721  4969.8  219.68  4979.8  218.91  4984.1   216.9  4984.4   216.4
  4987.9   216.4  4988.1   216.9  4991.1  218.54  4997.4  217.02  5020.7  217.75
  5030.8  219.43    5036  219.77  5041.6  221.06  5052.1  222.81  5062.5   223.8
  5125.2  225.65  5134.8  225.81    5140  225.02  5146.1  225.93  5167.3  225.89
#Mann= 4 ,-1 , 0
  4778.3     .11       0  4920.1     .17       0 4963.31     .09       0
  5041.6     .17       0
Bank Sta=4963.31,5041.6
XS Rating Curve= 0 ,0
Exp/Cntr=0.3,0.1

Type RM Length L Ch R = 1 ,9000    ,500,500,500
BEGIN DESCRIPTION:
CRYSTAL CREEK TRIBUTARY NO 4 18.0
END DESCRIPTION:
XS GIS Cut Line= 3
      3859766.57     10126933.41      3859465.91     10126890.53
      3859306.44     10126924.73
#Sta/Elev= 30
  4696.3  224.48  4715.2  223.97  4725.9  222.53  4744.4  222.92  4765.7  222.43
  4785.9  222.91  4820.2  221.94  4846.5  222.31  4876.8  222.06  4885.9  221.63
  4890.9  222.02    4897  221.63  4947.5  220.75  4961.7  221.03 4975.12219.1041
  4987.9  217.01  4994.5  214.21  4994.7  213.71  4998.2  213.71  4998.5  214.21
    5000  214.21  5008.2  215.75  5018.5  216.78    5025  217.95  5030.1  217.74
  5038.9  219.16  5049.2  220.26  5079.8  222.08  5118.7  223.56  5163.1  224.77
#Mann= 4 ,-1 , 0
  4696.3     .11       0  4725.9     .17       0 4975.12     .09       0
  5038.9     .17       0
#XS Ineff= 2 ,-1
  4956.7  4927.3  221.07  4890.9  4846.5  222.02
Permanent Ineff=
       F       F
Bank Sta=4975.12,5038.9
XS Rating Curve= 0 ,0
Exp/Cntr=0.3,0.1

Type RM Length L Ch R = 1 ,8500    ,500,500,500
BEGIN DESCRIPTION:
CRYSTAL CREEK TRIBUTARY NO 4 17.0
END DESCRIPTION:
XS GIS Cut Line= 3
      3859830.15     10126597.47      3859625.48     10126560.97
      3859376.13      10126517.6
#Sta/Elev= 30
  4792.1  223.38  4824.9  222.46  4885.9  221.82  4906.2  220.41  4917.7  220.29
    4957  217.67  4971.6  216.01  4977.3  214.36 4982.75213.8905  4987.4  213.49
  4994.3  211.58  4994.5  211.08    4998  211.08  4998.3  211.58    5000  211.58
  5007.7  214.02  5017.9  215.29  5030.9  215.84  5038.2  217.15  5068.6  219.79
  5085.4     219  5099.1  218.78  5119.4  219.24  5139.7  218.59    5145  218.89
  5150.1  218.66  5170.1  219.76  5199.6  220.63  5210.7  220.28  5253.1   221.1
#Mann= 3 , 0 , 0
  4792.1     .17       0 4982.75     .09       0  5007.7     .17       0
Bank Sta=4982.75,5007.7
XS Rating Curve= 0 ,0
Exp/Cntr=0.3,0.1

Type RM Length L Ch R = 1 ,8000    ,306,306,306
BEGIN DESCRIPTION:
CRYSTAL CREEK TRIBUTARY NO 4 16.0
END DESCRIPTION:
XS GIS Cut Line= 3
      3859794.26     10126147.25      3859571.35     10126278.35
      3859365.17     10126476.55
#Sta/Elev= 30
  4741.4  220.41  4748.8  220.74    4772  220.05  4799.6  219.97    4830  219.25
  4864.8  219.31    4911  217.63  4914.5  217.91  4922.9  218.01    4954  217.42
  4969.3  216.63  4975.4  216.76  4991.1  215.07  4996.9  213.12  4997.1     211
  4997.4   210.5  5001.1     211  5011.5  211.42  5025.6  211.26  5032.6  211.68
  5039.8  212.73  5046.7  211.82  5068.1  213.07  5094.7  214.22  5117.5  215.21
  5131.6  216.98  5145.8  218.08  5195.4  219.26  5273.1  219.93    5286  220.47
#Mann= 5 ,-1 , 0
  4741.4     .17       0  4914.5     .11       0  4996.9     .07       0
  5068.1     .11       0  5094.7     .17       0
Bank Sta=4996.9,5068.1
XS Rating Curve= 0 ,0
Exp/Cntr=0.3,0.1

Type RM Length L Ch R = 1 ,7694    ,162,162,162
BEGIN DESCRIPTION:
Mapping XS 8659c133
END DESCRIPTION:
XS GIS Cut Line= 3
      3859602.42     10125873.47      3859437.38     10126124.19
      3859263.35     10126364.04
#Sta/Elev= 30
    4701  220.28  4738.3   219.7    4746  218.94  4795.5  218.32  4825.7  217.06
  4831.7   216.2  4876.9  216.14  4889.7   215.4    4898   213.7    4904  214.25
    4913  213.64    4919  213.92  4934.1  211.84  4949.2  211.16  4961.5  210.97
  4976.2  212.31  5004.2  210.84  5004.4  210.34  5007.9  210.34  5008.2  210.84
  5020.9  212.27    5027  213.64  5034.4  214.36  5062.6  216.25  5133.7  217.89
  5142.2  217.47  5156.9  218.41    5184  218.01  5262.4  219.59  5297.5  219.94
#Mann= 4 ,-1 , 0
    4701     .11       0  4976.2     .06       0  5020.9     .11       0
  5262.4     .17       0
#XS Ineff= 2 , 0
       0    4904  214.25               0
Permanent Ineff=
       F       F
Bank Sta=4976.2,5020.9
XS Rating Curve= 0 ,0
Exp/Cntr=0.3,0.1

Type RM Length L Ch R = 1 ,7532    ,533,533,533
BEGIN DESCRIPTION:
CRYSTAL CREEK TRIBUTARY NO 4 15.0
END DESCRIPTION:
XS GIS Cut Line= 3
      3859519.63     10125815.61      3859407.06     10125968.25
      3859182.64     10126325.68
#Sta/Elev= 30
  4801.7  220.76  4834.8  219.36  4878.7  218.43  4914.2  216.83  4949.6  215.93
  4957.6  215.63  4964.3  214.88  4970.5  215.14  4985.1  212.81 4987.02211.1681
  4988.3  209.83  4991.8  209.83    4992  210.33  5015.2  211.28  5057.7  210.66
  5094.2  212.08  5109.5  213.36  5136.6  214.61    5146  215.55  5173.1  215.42
  5240.3  216.81  5261.5  216.61  5267.4  217.11  5282.7  216.85  5303.9  218.21
  5334.5   218.7  5340.4  218.36    5371  219.11  5376.9  218.75  5413.4  219.64
#Mann= 3 , 0 , 0
  4801.7     .11       0 4987.02     .06       0  5015.2     .11       0
Bank Sta=4987.02,5015.2
XS Rating Curve= 0 ,0
Exp/Cntr=0.3,0.1

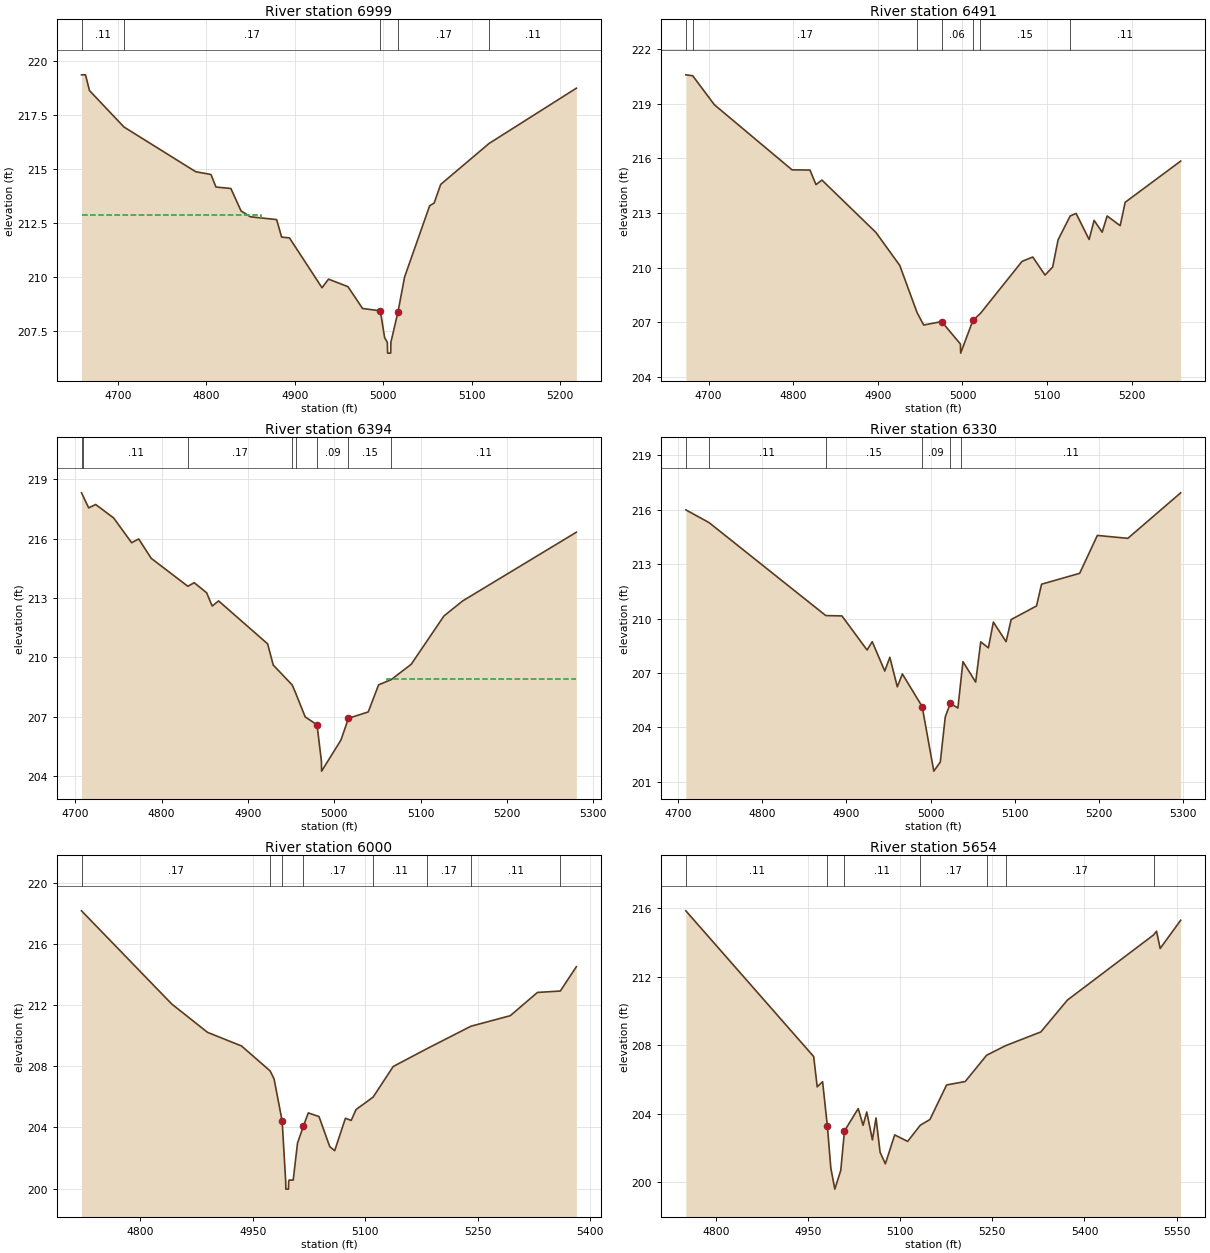
Type RM Length L Ch R = 1 ,6999    ,508,508,508
BEGIN DESCRIPTION:
CRYSTAL CREEK TRIBUTARY NO 4 14.0
END DESCRIPTION:
XS GIS Cut Line= 3
      3859076.65     10125697.96      3858934.37     10126004.25
      3858890.81      10126221.4
#Sta/Elev= 30
  4659.1  219.36  4663.6  219.36  4668.1  218.63  4707.1  216.94  4788.1  214.87
  4805.4  214.74    4811  214.16  4827.9  214.09  4839.4  213.05    4850  212.78
  4879.6  212.65  4885.2  211.84  4894.1   211.8  4930.9  209.49  4938.2  209.89
  4960.2  209.54  4976.7  208.53  4996.8  208.42  5001.6  207.18  5004.7  206.96
    5005  206.46  5008.5  206.46  5008.7  206.96 5016.77208.3802  5024.2  209.99
  5052.5  213.29  5057.6  213.42    5065  214.28  5119.7  216.18  5218.3  218.74
#Mann= 5 ,-1 , 0
  4659.1     .11       0  4707.1     .17       0  4996.8     .09       0
 5016.77     .17       0  5119.7     .11       0
#XS Ineff= 2 , 0
       0  4862.3  212.85               0
Permanent Ineff=
       F       F
Bank Sta=4996.8,5016.77
XS Rating Curve= 0 ,0
Exp/Cntr=0.3,0.1

Type RM Length L Ch R = 1 ,6491    ,97,97,97
BEGIN DESCRIPTION:
CRYSTAL CREEK TRIBUTARY NO 4 13.0
END DESCRIPTION:
XS GIS Cut Line= 3
      3858851.24     10125566.92      3858622.31     10125800.28
      3858487.25     10126019.99
#Sta/Elev= 30
  4673.1  220.58  4681.2  220.53  4706.8  218.94  4798.6  215.37  4819.8  215.36
  4826.9  214.56  4833.9  214.81  4897.7  211.94  4925.9  210.13  4946.4  207.54
  4954.2  206.86  4975.4  207.05  4997.6  205.82  4997.9  205.32  5012.4  207.12
  5021.3   207.5  5070.4  210.35  5083.1  210.59  5097.6   209.6  5106.6  210.04
    5113  211.53  5127.3  212.84  5134.3  212.98  5149.7  211.55  5155.6   212.6
  5165.1  211.95    5171  212.84  5186.4  212.31  5192.3  213.59  5257.9  215.85
#Mann= 7 ,-1 , 0
  4673.1     .11       0  4681.2     .17       0  4946.4     .11       0
  4975.4     .06       0  5012.4     .11       0  5021.3     .15       0
  5127.3     .11       0
#XS Ineff= 2 , 0
       0                  5083.1       0  210.59
Permanent Ineff=
       F       F
Bank Sta=4975.4,5012.4
XS Rating Curve= 0 ,0
Exp/Cntr=0.3,0.1

Type RM Length L Ch R = 1 ,6394    ,64,64,64
BEGIN DESCRIPTION:
Mapping XS a1dd1edb
END DESCRIPTION:
XS GIS Cut Line= 3
      3858714.94      10125525.7      3858533.97     10125758.74
      3858399.87      10126002.2
#Sta/Elev= 30
  4707.4  218.31  4709.6  218.11  4715.7  217.55  4723.8  217.72  4744.6  217.04
  4765.4  215.79  4773.6  215.98  4788.1     215  4830.5  213.59  4837.9  213.77
  4852.3  213.26  4858.7  212.59  4866.1  212.85  4922.9  210.68  4929.4  209.61
  4951.4   208.6  4955.5  208.18  4966.4  206.99  4980.1  206.59  4985.2  204.75
  4985.4  204.25  5007.8  205.82  5016.5  206.92  5039.4  207.24  5051.4  208.61
  5065.9  208.87  5089.2  209.65  5127.1  212.09  5148.8  212.85  5280.4  216.32
#Mann= 8 ,-1 , 0
  4707.4     .17       0  4709.6     .11       0  4830.5     .17       0
  4951.4     .11       0  4955.5     .15       0  4980.1     .09       0
  5016.5     .15       0  5065.9     .11       0
#XS Ineff= 2 , 0
       0                  5061.7       0  208.91
Permanent Ineff=
       F       F
Bank Sta=4980.1,5016.5
XS Rating Curve= 0 ,0
Exp/Cntr=0.3,0.1

Type RM Length L Ch R = 1 ,6330    ,330,330,330
BEGIN DESCRIPTION:
Mapping XS 610bbb70
END DESCRIPTION:
XS GIS Cut Line= 3
      3858647.27     10125482.68      3858479.28     10125727.49
      3858319.11     10125969.71
#Sta/Elev= 30
  4709.5     216    4737   215.3  4875.6  210.17  4894.8  210.15  4924.6  208.27
  4930.7  208.73  4945.6  207.11  4951.6  207.87  4960.5  206.24  4966.5  206.95
 4989.97205.1533  5003.8  201.59  5011.5  202.09  5017.4  204.58  5023.4  205.33
  5032.4  205.07  5036.1  206.65  5038.4  207.63  5053.5   206.5  5059.5  208.72
  5068.6  208.39  5074.5  209.81  5089.6  208.73  5095.6  209.95  5125.7   210.7
  5131.7   211.9  5176.9   212.5  5197.9  214.59  5234.1  214.43  5296.8  216.94
#Mann= 6 ,-1 , 0
  4709.5     .17       0    4737     .11       0  4875.6     .15       0
 4989.97     .09       0  5023.4     .15       0  5036.1     .11       0
#XS Ineff= 3 ,-1
  4930.7  4894.8  208.73  5059.5  5074.5  208.72  5074.5  5095.6  209.81
Permanent Ineff=
       F       F       F
Bank Sta=4989.97,5023.4
XS Rating Curve= 0 ,0
Exp/Cntr=0.3,0.1

Type RM Length L Ch R = 1 ,6000    ,346,346,346
BEGIN DESCRIPTION:
CRYSTAL CREEK TRIBUTARY NO 4 12.0
END DESCRIPTION:
XS GIS Cut Line= 3
      3858624.65     10125320.02      3858367.92      10125427.2
      3858121.75     10125718.38
#Sta/Elev= 30
  4721.8  218.15  4842.1  212.06  4889.8  210.21  4935.1  209.32  4973.2  207.69
  4978.4  207.17  4989.2  204.42  4993.9  200.47  4994.1  199.97  4997.6  199.97
  4997.9  200.47  4998.5  200.56  5003.9  200.56  5009.7  202.99  5017.5  204.08
    5024  204.95  5038.3  204.71  5052.6  202.75  5059.2  202.48  5073.5   204.6
  5081.2  204.46  5087.7  205.17  5110.4  205.98  5137.2  207.98  5181.6  209.13
  5240.7  210.61  5293.2   211.3  5329.5  212.82  5359.9  212.91  5381.3   214.5
#Mann= 8 ,-1 , 0
  4721.8     .17       0  4973.2     .15       0  4989.2     .09       0
  5017.5     .17       0  5110.4     .11       0  5181.6     .17       0
  5240.7     .11       0  5359.9     .17       0
Bank Sta=4989.2,5017.5
XS Rating Curve= 0 ,0
Exp/Cntr=0.3,0.1

Type RM Length L Ch R = 1 ,5654    ,654,654,654
BEGIN DESCRIPTION:
CRYSTAL CREEK TRIBUTARY NO 4 11.0
END DESCRIPTION:
XS GIS Cut Line= 3
      3858436.27     10125060.39      3858214.37     10125173.57
      3857746.51     10125475.26
#Sta/Elev= 30
  4750.9  215.85  4959.1  207.33  4964.8  205.56  4973.6  205.86  4981.4  203.25
    4987  200.81  4993.5  199.58  5003.2  200.68  5009.2  202.98  5031.6  204.29
  5039.5  203.31  5045.5  204.09  5054.7  202.46  5060.6  203.74  5067.2  201.74
  5075.8  201.06    5091  202.75  5112.1  202.37  5132.8  203.32  5148.4  203.65
  5175.5  205.67  5205.8  205.87  5240.8  207.41  5271.8  207.97    5329  208.77
  5372.2  210.63  5512.5  214.44  5517.4  214.66  5523.3  213.65  5556.7   215.3
#Mann= 7 ,-1 , 0
  4750.9     .11       0  4981.4     .07       0  5009.2     .11       0
  5132.8     .17       0  5240.8     .11       0  5271.8     .17       0
  5512.5     .11       0
#XS Ineff= 2 , 0
       0  4973.6  205.86               0
Permanent Ineff=
       F       F
Bank Sta=4981.4,5009.2
XS Rating Curve= 0 ,0
Exp/Cntr=0.3,0.1

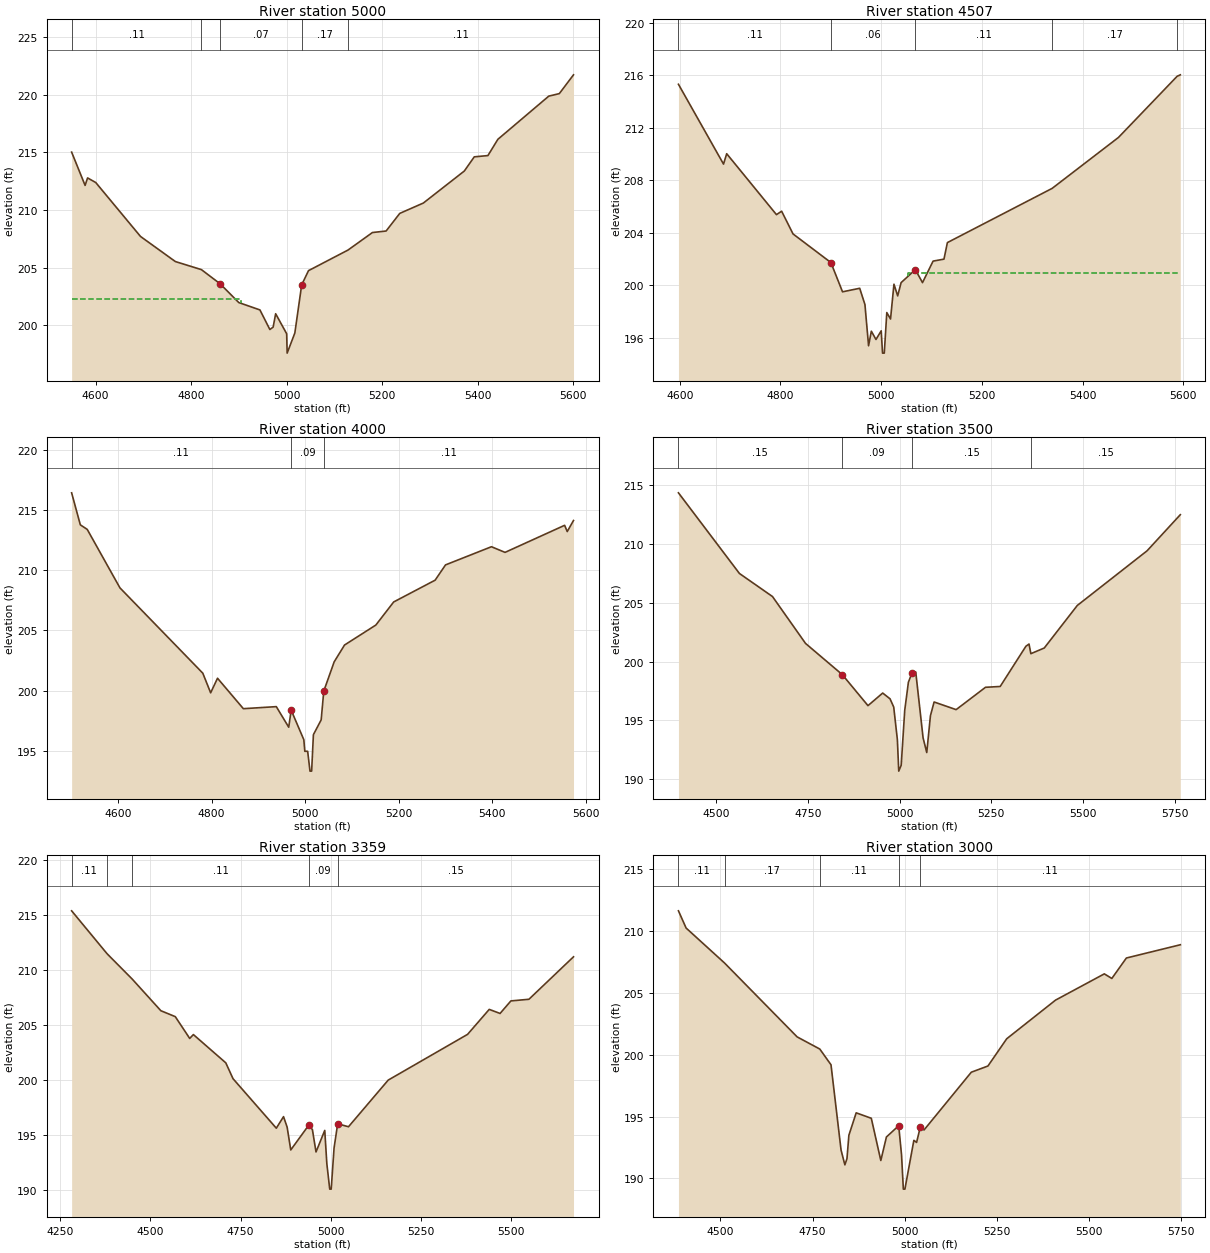
Type RM Length L Ch R = 1 ,5000    ,493,493,493
BEGIN DESCRIPTION:
CRYSTAL CREEK TRIBUTARY NO 4 10.0
END DESCRIPTION:
XS GIS Cut Line= 3
      3858296.28     10124737.09       3857864.1     10124863.53
      3857405.41     10125251.25
#Sta/Elev= 30
  4549.7  215.02  4577.9  212.13  4583.1  212.78  4600.2  212.38  4693.9   207.7
  4766.9  205.52  4821.4  204.82  4860.6  203.59  4899.7  201.96    4944  201.32
  4964.8  199.62  4971.7  199.83  4976.9  200.99    5000  199.25    5001  197.57
  5017.1  199.32  5031.4  203.49  5045.7  204.73  5128.5  206.52  5179.6  208.04
  5208.2  208.17  5236.8   209.7  5286.2   210.6    5372  213.38  5392.8  214.61
  5421.4  214.72  5442.2  216.13  5548.8  219.88  5570.9   220.1  5600.6  221.73
#Mann= 5 ,-1 , 0
  4549.7     .11       0  4821.4     .17       0  4860.6     .07       0
  5031.4     .17       0  5128.5     .11       0
#XS Ineff= 2 , 0
       0  4904.9  202.27               0
Permanent Ineff=
       F       F
Bank Sta=4860.6,5031.4
XS Rating Curve= 0 ,0
Exp/Cntr=0.3,0.1

Type RM Length L Ch R = 1 ,4507    ,507,507,507
BEGIN DESCRIPTION:
CRYSTAL CREEK TRIBUTARY NO 4 9.0
END DESCRIPTION:
XS GIS Cut Line= 3
      3858085.06     10124309.42      3857718.43     10124475.75
      3857316.25     10124912.76
#Sta/Elev= 30
  4597.4  215.31  4686.9  209.23  4693.2  210.02    4792  205.38  4802.3  205.64
  4824.9  203.91  4900.1  201.73  4923.2   199.5  4957.3  199.77  4967.7  198.53
  4974.9  195.39  4980.4   196.5  4989.6  195.87    5000  196.53  5002.6  194.83
  5006.1  194.83  5011.1  197.92  5018.5  197.43  5025.3  200.08  5032.7  199.19
  5039.5   200.2  5067.8  201.19    5082   200.2    5103  201.84  5124.6  201.99
  5131.4  203.25  5339.4  207.38  5471.1  211.26  5587.6  215.92  5593.9  216.03
#Mann= 5 ,-1 , 0
  4597.4     .11       0  4900.1     .06       0  5067.8     .11       0
  5339.4     .17       0  5587.6     .11       0
#XS Ineff= 2 , 0
       0                  5053.7       0  200.97
Permanent Ineff=
       F       F
Bank Sta=4900.1,5067.8
XS Rating Curve= 0 ,0
Exp/Cntr=0.3,0.1

Type RM Length L Ch R = 1 ,4000    ,500,500,500
BEGIN DESCRIPTION:
CRYSTAL CREEK TRIBUTARY NO 4 8.0
END DESCRIPTION:
XS GIS Cut Line= 3
      3857945.61      10124076.3      3857469.02     10124226.52
       3857206.3      10124737.2
#Sta/Elev= 30
  4500.3  216.43  4518.9  213.77  4533.7  213.39  4603.7  208.53    4781  201.44
  4797.8  199.81  4812.5  201.02  4867.8  198.49  4938.3  198.66  4964.9  196.95
  4970.1  198.37  4997.2  195.91  4999.3  194.95  5005.4  194.95  5010.4   193.3
  5013.9   193.3  5017.7  196.33  5034.3  197.56  5039.9  199.95  5062.1  202.38
  5084.3  203.78  5151.3  205.44  5189.5  207.36  5278.2  209.17  5300.4  210.44
  5398.7  211.95  5427.8  211.48  5555.3  213.73  5560.9  213.21  5574.3  214.13
#Mann= 3 , 0 , 0
  4500.3     .11       0  4970.1     .09       0  5039.9     .11       0
#XS Ineff= 2 , 0
       0  4812.5  201.02               0
Permanent Ineff=
       F       F
Bank Sta=4970.1,5039.9
XS Rating Curve= 0 ,0
Exp/Cntr=0.3,0.1

Type RM Length L Ch R = 1 ,3500    ,141,141,141
BEGIN DESCRIPTION:
CRYSTAL CREEK TRIBUTARY NO 4 7.0
END DESCRIPTION:
XS GIS Cut Line= 3
      3857903.85     10123909.42      3857301.94     10123890.78
      3856537.32     10123902.15
#Sta/Elev= 30
  4397.8  214.36  4563.9   207.5  4653.9  205.54    4744  201.55    4844   198.9
    4914  196.26  4954.1  197.33  4974.1  196.84  4984.1  196.14  4994.1  193.36
  4997.8  190.69  5004.5  191.19  5014.1  195.86  5024.1  198.25  5034.1  199.06
  5044.1  199.12  5064.1  193.52  5074.1  192.27  5084.1   195.4  5094.1  196.57
  5154.1  195.92  5234.1  197.82  5274.1  197.89  5344.1  201.31  5352.6   201.5
  5357.6  200.68  5394.1  201.16  5484.1  204.78  5674.2  209.43  5764.7   212.5
#Mann= 4 ,-1 , 0
  4397.8     .15       0    4844     .09       0  5034.1     .15       0
  5357.6     .15       0
Bank Sta=4844,5034.1
XS Rating Curve= 0 ,0
Exp/Cntr=0.3,0.1

Type RM Length L Ch R = 1 ,3359    ,359,359,359
BEGIN DESCRIPTION:
Mapping XS ced4b6e5
END DESCRIPTION:
XS GIS Cut Line= 3
        3857935.     10123791.01      3857233.66     10123780.59
      3856544.38     10123784.07
#Sta/Elev= 30
  4281.8  215.34    4380  211.44  4449.8  209.13    4529  206.26    4569  205.72
    4609  203.74  4619.2  204.09    4709  201.52    4729  200.08    4849  195.58
    4869  196.63    4879  195.67    4889   193.6    4939  195.86    4949  195.45
    4959  193.42  4983.2  195.38    4989  192.35    4997  190.04  5001.1  190.04
    5009  193.78    5019  195.98    5049  195.71    5159  199.95    5379  204.11
    5439  206.38    5469  206.01    5499  207.15    5549   207.3  5672.5  211.16
#Mann= 5 ,-1 , 0
  4281.8     .11       0    4380     .17       0  4449.8     .11       0
    4939     .09       0    5019     .15       0
Bank Sta=4939,5019
XS Rating Curve= 0 ,0
Exp/Cntr=0.3,0.1

Type RM Length L Ch R = 1 ,3000    ,493,493,493
BEGIN DESCRIPTION:
CRYSTAL CREEK TRIBUTARY NO 4 6.0
END DESCRIPTION:
XS GIS Cut Line= 3
      3857868.17     10123666.27      3857269.16     10123531.88
      3856535.51       10123673.
#Sta/Elev= 30
  4386.1  211.61  4406.9  210.22    4511   207.4    4708  201.43  4769.4  200.45
  4799.8  199.18  4827.1  192.29  4837.4   191.1  4843.1   191.6  4848.3  193.49
  4868.1   195.3  4909.1  194.86  4934.9  191.45  4950.1  193.35  4983.4  194.26
  4991.1  191.89    4996  189.14  5000.2  189.14  5024.5  193.08  5031.9  192.91
  5042.1  194.17  5052.2  193.92  5180.3  198.58  5225.4  199.08  5276.3  201.28
  5408.7   204.4    5541  206.52  5561.4  206.15  5600.8   207.8  5747.1  208.87
#Mann= 5 ,-1 , 0
  4386.1     .11       0    4511     .17       0  4769.4     .11       0
  4983.4     .09       0  5042.1     .11       0
Bank Sta=4983.4,5042.1
XS Rating Curve= 0 ,0
Exp/Cntr=0.3,0.1

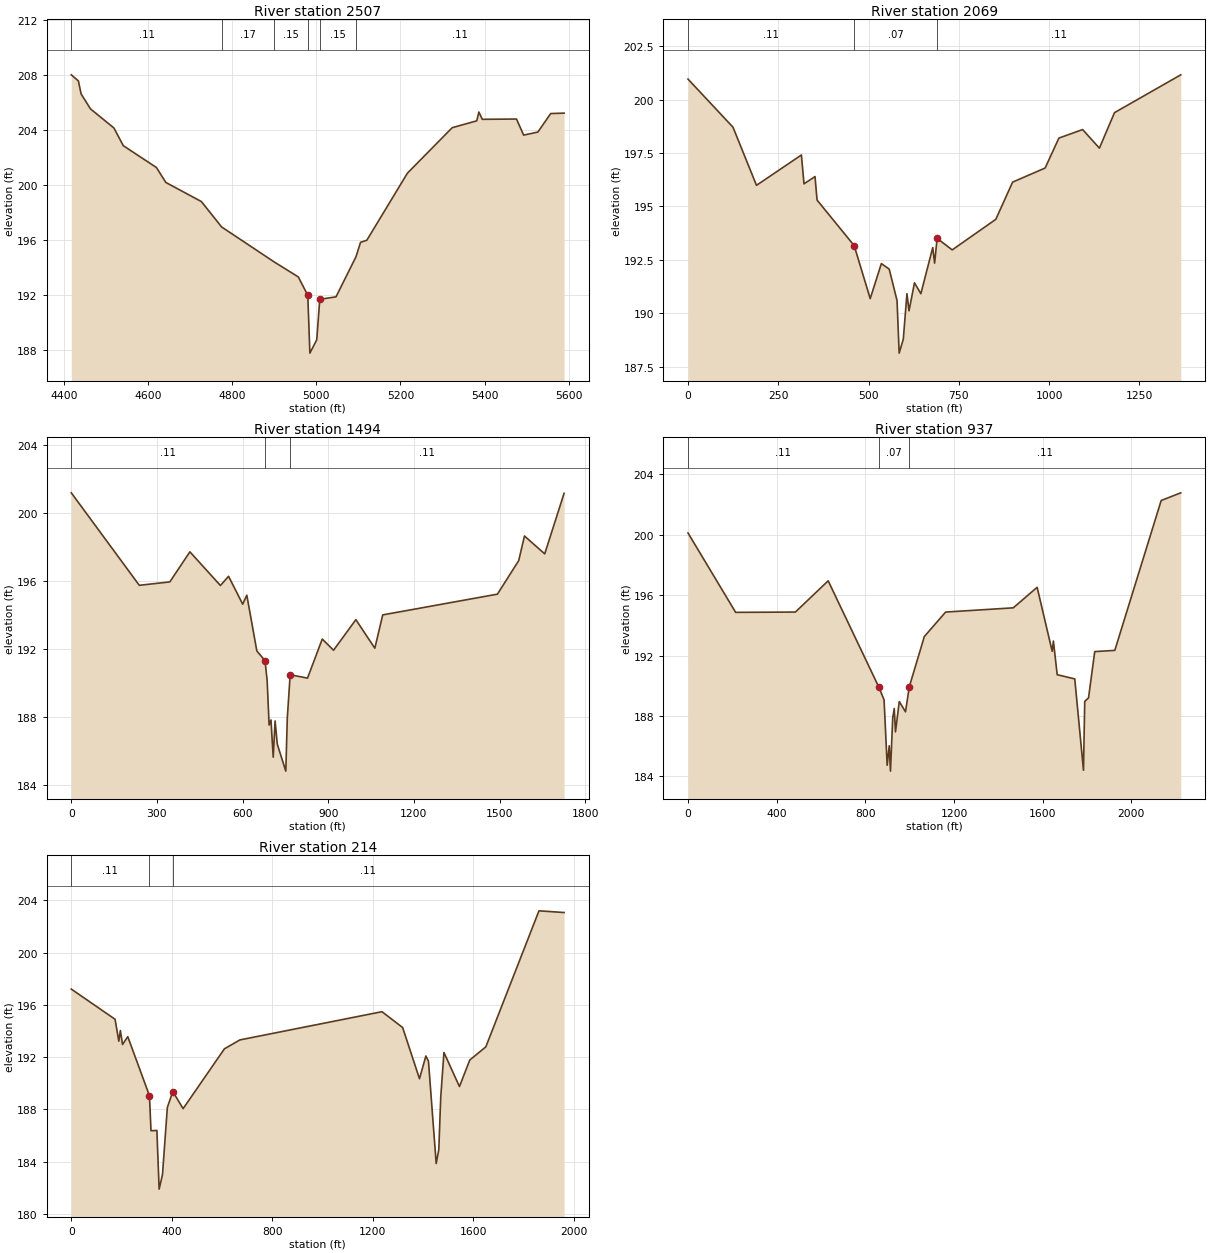
Type RM Length L Ch R = 1 ,2507    ,442,442,442
BEGIN DESCRIPTION:
CRYSTAL CREEK TRIBUTARY NO 4 5.0
END DESCRIPTION:
XS GIS Cut Line= 3
      3857908.79     10123393.08      3857386.86     10123136.92
      3856806.58     10123243.03
#Sta/Elev= 30
  4417.6  208.02  4434.4  207.58  4440.9  206.63  4463.2  205.54  4518.8  204.15
  4541.2  202.86  4619.9  201.27  4642.4  200.18  4726.8  198.79  4774.9  196.94
  4900.5  194.38  4957.2   193.3  4979.7  191.96  4984.7  187.75    5001  188.72
  5008.2  191.67  5046.8  191.85  5094.3  194.77  5105.1  195.82    5120  195.97
  5216.6  200.86    5323  204.17  5381.3  204.67  5386.4  205.31  5394.5  204.78
  5475.8   204.8  5492.8  203.63  5526.6  203.85  5557.1   205.2  5588.9  205.23
#Mann= 6 ,-1 , 0
  4417.6     .11       0  4774.9     .17       0  4900.5     .15       0
  4979.7     .09       0  5008.2     .15       0  5094.3     .11       0
Bank Sta=4979.7,5008.2
XS Rating Curve= 0 ,0
Exp/Cntr=0.3,0.1

Type RM Length L Ch R = 1 ,2069    ,584,584,584
XS GIS Cut Line= 3
      3857998.22     10123108.82      3857482.14     10122819.88
      3856741.51      10123045.3
#Sta/Elev= 30
       0  200.96   124.6  198.71   189.7  195.99   314.1  197.41   321.3  196.06
   351.8   196.4   357.5   195.3   460.3  193.17   504.7  190.69   535.6  192.33
   557.3  192.07     579   190.6   584.9  188.14   596.3  188.79   606.4  190.92
   612.2  190.12   627.3  191.43     645  190.92   677.9  193.08   683.1  192.35
     690  193.51   731.8  192.97   852.6   194.4   899.1  196.14   989.2   196.8
  1027.3   198.2    1093   198.6  1139.5  197.73  1181.3  199.39  1364.9  201.16
#Mann= 3 , 0 , 0
       0     .11       0   460.3     .07       0     690     .11       0
Bank Sta=460.3,690
XS Rating Curve= 0 ,0
Exp/Cntr=0.3,0.1

Type RM Length L Ch R = 1 ,1494    ,557,557,557
XS GIS Cut Line= 3
      3858236.92     10123067.46      3857673.85     10122602.65
      3856689.09     10122763.84
#Sta/Elev= 30
       0   201.2   238.2  195.76   345.1  195.96   415.4  197.73   522.3  195.75
   550.9  196.29   600.4  194.65   614.8  195.18   649.9   191.9   678.6  191.33
     686  190.16   692.9  187.54   699.4  187.84   707.3  185.65   713.8  187.78
   721.6  186.41   751.4  184.83   756.5  187.92   766.6   190.5   827.4   190.3
   879.1   192.6   918.6  191.94   996.8  193.74  1063.2  192.06  1090.9  194.02
  1492.7  195.24  1567.1  197.21  1587.4  198.66  1658.3  197.61  1726.1  201.17
#Mann= 3 , 0 , 0
       0     .11       0   678.6     .07       0   766.6     .11       0
Bank Sta=678.6,766.6
XS Rating Curve= 0 ,0
Exp/Cntr=0.3,0.1

Type RM Length L Ch R = 1 ,937     ,287,287,287
XS GIS Cut Line= 4
      3858408.43     10123071.19      3858178.08     10122485.32
      3857927.91     10122379.36      3856736.59     10121805.66
#Sta/Elev= 30
       0  200.12     215  194.86   484.4  194.88   632.4  196.95   860.8  189.91
   884.5  189.06   898.5  184.73   907.8  186.02   913.4  184.34   923.5  187.87
   930.4  188.49     936  186.94   953.1  188.95   981.2  188.27   998.3  189.93
  1066.2  193.26  1162.2  194.88  1467.4  195.16    1575  196.52  1642.9  192.28
  1648.4  192.96  1665.5  190.73  1744.8  190.45  1784.1   184.4  1789.7  188.96
  1806.8  189.19  1834.9  192.26  1925.4  192.34  2134.6  202.27    2223  202.78
#Mann= 3 , 0 , 0
       0     .11       0   860.8     .07       0   998.3     .11       0
Bank Sta=860.8,998.3
XS Rating Curve= 0 ,0
Exp/Cntr=0.3,0.1

Type RM Length L Ch R = 1 ,214     ,0,0,0
XS GIS Cut Line= 3
      3858522.06     10122430.18      3858320.66     10122144.54
      3856752.56     10121773.72
#Sta/Elev= 30
       0  197.21   174.2   194.9     189  193.22   195.2  194.04   203.8  192.97
   224.7  193.57     311  189.05   317.1  186.37   340.5  186.39   349.5   181.9
   362.7     183   382.2  188.15   403.8  189.37   444.9  188.06   609.3  192.64
   670.9  193.32  1236.1  195.48  1318.3  194.27  1385.4  190.35  1410.8  192.09
  1421.1  191.69  1451.9  183.86  1462.2  184.92    1470  188.96  1482.7  192.36
  1544.4  189.75  1585.5  191.78  1649.4  192.79  1860.8   203.2  1960.7  203.07
#Mann= 3 , 0 , 0
       0     .11       0     311     .07       0   403.8     .11       0
Bank Sta=311,403.8
XS Rating Curve= 0 ,0
Exp/Cntr=0.3,0.1

Chan Stop Cuts=-1
Use User Specified Reach Order=0
Composite Channel Slope=5

--- CRYSTAL CREEK TRIBUTARY NO 4.g10 (geometry) ---

Geom Title=Existing Conditions
Program Version=4.10

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
River Reach=CRYSTAL CREEK TR,Reach-1

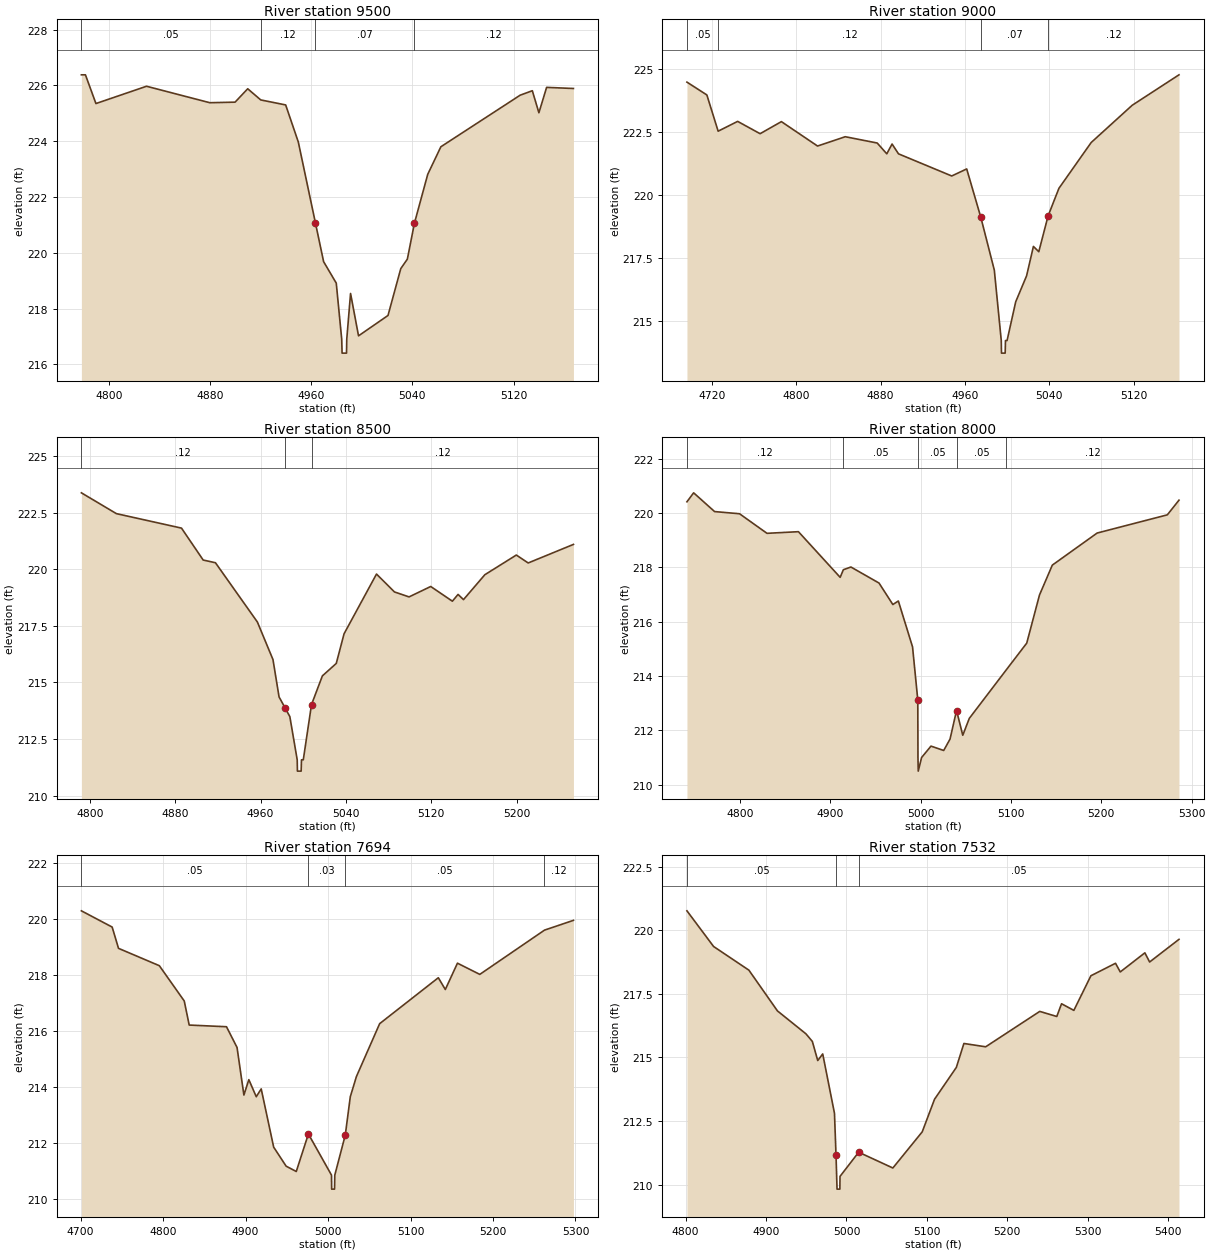
Type RM Length L Ch R = 1 ,9500    ,500,500,500
BEGIN DESCRIPTION:
CRYSTAL CREEK TRIBUTARY NO 4 19.0
END DESCRIPTION:
XS GIS Cut Line= 3
      3859729.31     10127331.21      3859507.67     10127325.76
      3859347.54      10127374.2
#Sta/Elev= 30
  4778.3  226.38  4781.5  226.38  4789.8  225.35  4829.8  225.97  4879.8  225.38
  4899.8   225.4  4909.8  225.88  4920.1  225.48  4939.8   225.3  4949.8  223.97
 4963.31 221.072  4969.8  219.68  4979.8  218.91  4984.1   216.9  4984.4   216.4
  4987.9   216.4  4988.1   216.9  4991.1  218.54  4997.4  217.02  5020.7  217.75
  5030.8  219.43    5036  219.77  5041.6  221.06  5052.1  222.81  5062.5   223.8
  5125.2  225.65  5134.8  225.81    5140  225.02  5146.1  225.93  5167.3  225.89
#Mann= 4 ,-1 , 0
  4778.3     .05       0  4920.1     .12       0 4963.31     .07       0
  5041.6     .12       0
Bank Sta=4963.31,5041.6
XS Rating Curve= 0 ,0
Exp/Cntr=0.3,0.1

Type RM Length L Ch R = 1 ,9000    ,500,500,500
BEGIN DESCRIPTION:
CRYSTAL CREEK TRIBUTARY NO 4 18.0
END DESCRIPTION:
XS GIS Cut Line= 3
      3859766.57     10126933.41      3859465.91     10126890.53
      3859306.44     10126924.73
#Sta/Elev= 30
  4696.3  224.48  4715.2  223.97  4725.9  222.53  4744.4  222.92  4765.7  222.43
  4785.9  222.91  4820.2  221.94  4846.5  222.31  4876.8  222.06  4885.9  221.63
  4890.9  222.02    4897  221.63  4947.5  220.75  4961.7  221.03 4975.12 219.104
  4987.9  217.01  4994.5  214.21  4994.7  213.71  4998.2  213.71  4998.5  214.21
    5000  214.21  5008.2  215.75  5018.5  216.78    5025  217.95  5030.1  217.74
  5038.9  219.16  5049.2  220.26  5079.8  222.08  5118.7  223.56  5163.1  224.77
#Mann= 4 ,-1 , 0
  4696.3     .05       0  4725.9     .12       0 4975.12     .07       0
  5038.9     .12       0
Bank Sta=4975.12,5038.9
XS Rating Curve= 0 ,0
Exp/Cntr=0.3,0.1

Type RM Length L Ch R = 1 ,8500    ,500,500,500
BEGIN DESCRIPTION:
CRYSTAL CREEK TRIBUTARY NO 4 17.0
END DESCRIPTION:
XS GIS Cut Line= 3
      3859830.15     10126597.47      3859625.48     10126560.97
      3859376.13      10126517.6
#Sta/Elev= 30
  4792.1  223.38  4824.9  222.46  4885.9  221.82  4906.2  220.41  4917.7  220.29
    4957  217.67  4971.6  216.01  4977.3  214.36 4982.75 213.891  4987.4  213.49
  4994.3  211.58  4994.5  211.08    4998  211.08  4998.3  211.58    5000  211.58
  5007.7  214.02  5017.9  215.29  5030.9  215.84  5038.2  217.15  5068.6  219.79
  5085.4     219  5099.1  218.78  5119.4  219.24  5139.7  218.59    5145  218.89
  5150.1  218.66  5170.1  219.76  5199.6  220.63  5210.7  220.28  5253.1   221.1
#Mann= 3 , 0 , 0
  4792.1     .12       0 4982.75     .07       0  5007.7     .12       0
Bank Sta=4982.75,5007.7
XS Rating Curve= 0 ,0
Exp/Cntr=0.3,0.1

Type RM Length L Ch R = 1 ,8000    ,306,306,306
BEGIN DESCRIPTION:
CRYSTAL CREEK TRIBUTARY NO 4 16.0
END DESCRIPTION:
XS GIS Cut Line= 3
      3859794.26     10126147.25      3859571.35     10126278.35
      3859365.17     10126476.55
#Sta/Elev= 30
  4741.4  220.41  4748.8  220.74    4772  220.05  4799.6  219.97    4830  219.25
  4864.8  219.31    4911  217.63  4914.5  217.91  4922.9  218.01    4954  217.42
  4969.3  216.63  4975.4  216.76  4991.1  215.07  4996.9  213.12  4997.1     211
  4997.4   210.5  5001.1     211  5011.5  211.42  5025.6  211.26  5032.6  211.68
  5039.8  212.73  5046.7  211.82  5053.9  212.44  5094.7  214.22  5117.5  215.21
  5131.6  216.98  5145.8  218.08  5195.4  219.26  5273.1  219.93    5286  220.47
#Mann= 5 ,-1 , 0
  4741.4     .12       0  4914.5     .05       0  4997.4     .05       0
  5039.8     .05       0  5094.7     .12       0
Bank Sta=4996.9,5039.8
XS Rating Curve= 0 ,0
Exp/Cntr=0.3,0.1

Type RM Length L Ch R = 1 ,7694    ,162,162,162
BEGIN DESCRIPTION:
Mapping XS 8659c133
END DESCRIPTION:
XS GIS Cut Line= 3
      3859602.42     10125873.47      3859437.38     10126124.19
      3859263.35     10126364.04
#Sta/Elev= 30
    4701  220.28  4738.3   219.7    4746  218.94  4795.5  218.32  4825.7  217.06
  4831.7   216.2  4876.9  216.14  4889.7   215.4    4898   213.7    4904  214.25
    4913  213.64    4919  213.92  4934.1  211.84  4949.2  211.16  4961.5  210.97
  4976.2  212.31  5004.2  210.84  5004.4  210.34  5007.9  210.34  5008.2  210.84
  5020.9  212.27    5027  213.64  5034.4  214.36  5062.6  216.25  5133.7  217.89
  5142.2  217.47  5156.9  218.41    5184  218.01  5262.4  219.59  5297.5  219.94
#Mann= 4 ,-1 , 0
    4701     .05       0  4976.2     .03       0  5020.9     .05       0
  5262.4     .12       0
Bank Sta=4976.2,5020.9
XS Rating Curve= 0 ,0
Exp/Cntr=0.3,0.1

Type RM Length L Ch R = 1 ,7532    ,533,533,533
BEGIN DESCRIPTION:
CRYSTAL CREEK TRIBUTARY NO 4 15.0
END DESCRIPTION:
XS GIS Cut Line= 3
      3859519.63     10125815.61      3859407.06     10125968.25
      3859182.64     10126325.68
#Sta/Elev= 30
  4801.7  220.76  4834.8  219.36  4878.7  218.43  4914.2  216.83  4949.6  215.93
  4957.6  215.63  4964.3  214.88  4970.5  215.14  4985.1  212.81 4987.02 211.168
  4988.3  209.83  4991.8  209.83    4992  210.33  5015.2  211.28  5057.7  210.66
  5094.2  212.08  5109.5  213.36  5136.6  214.61    5146  215.55  5173.1  215.42
  5240.3  216.81  5261.5  216.61  5267.4  217.11  5282.7  216.85  5303.9  218.21
  5334.5   218.7  5340.4  218.36    5371  219.11  5376.9  218.75  5413.4  219.64
#Mann= 3 , 0 , 0
  4801.7     .05       0 4987.02     .03       0  5015.2     .05       0
Bank Sta=4987.02,5015.2
XS Rating Curve= 0 ,0
Exp/Cntr=0.3,0.1