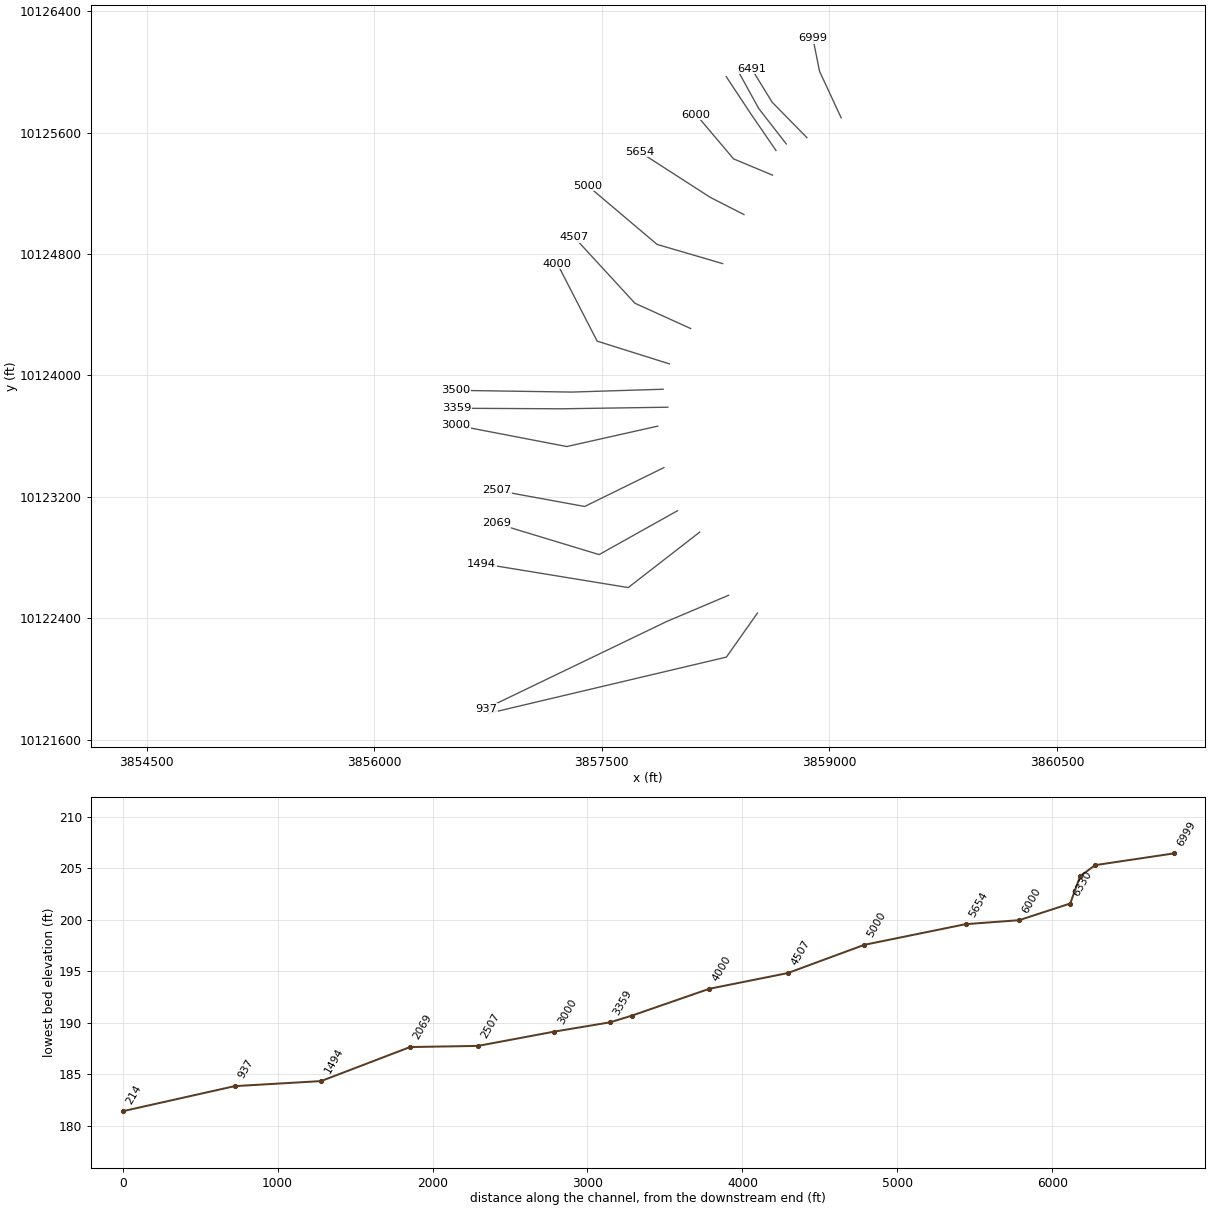
HEC-RAS study CRYSTAL CREEK TRIBUTARY NO 4.prj: CRYSTAL CREEK TRIBUTARY NO 4 Base Level Engineering

--- CRYSTAL CREEK TRIBUTARY NO 4.g10 (geometry) --- (continued)

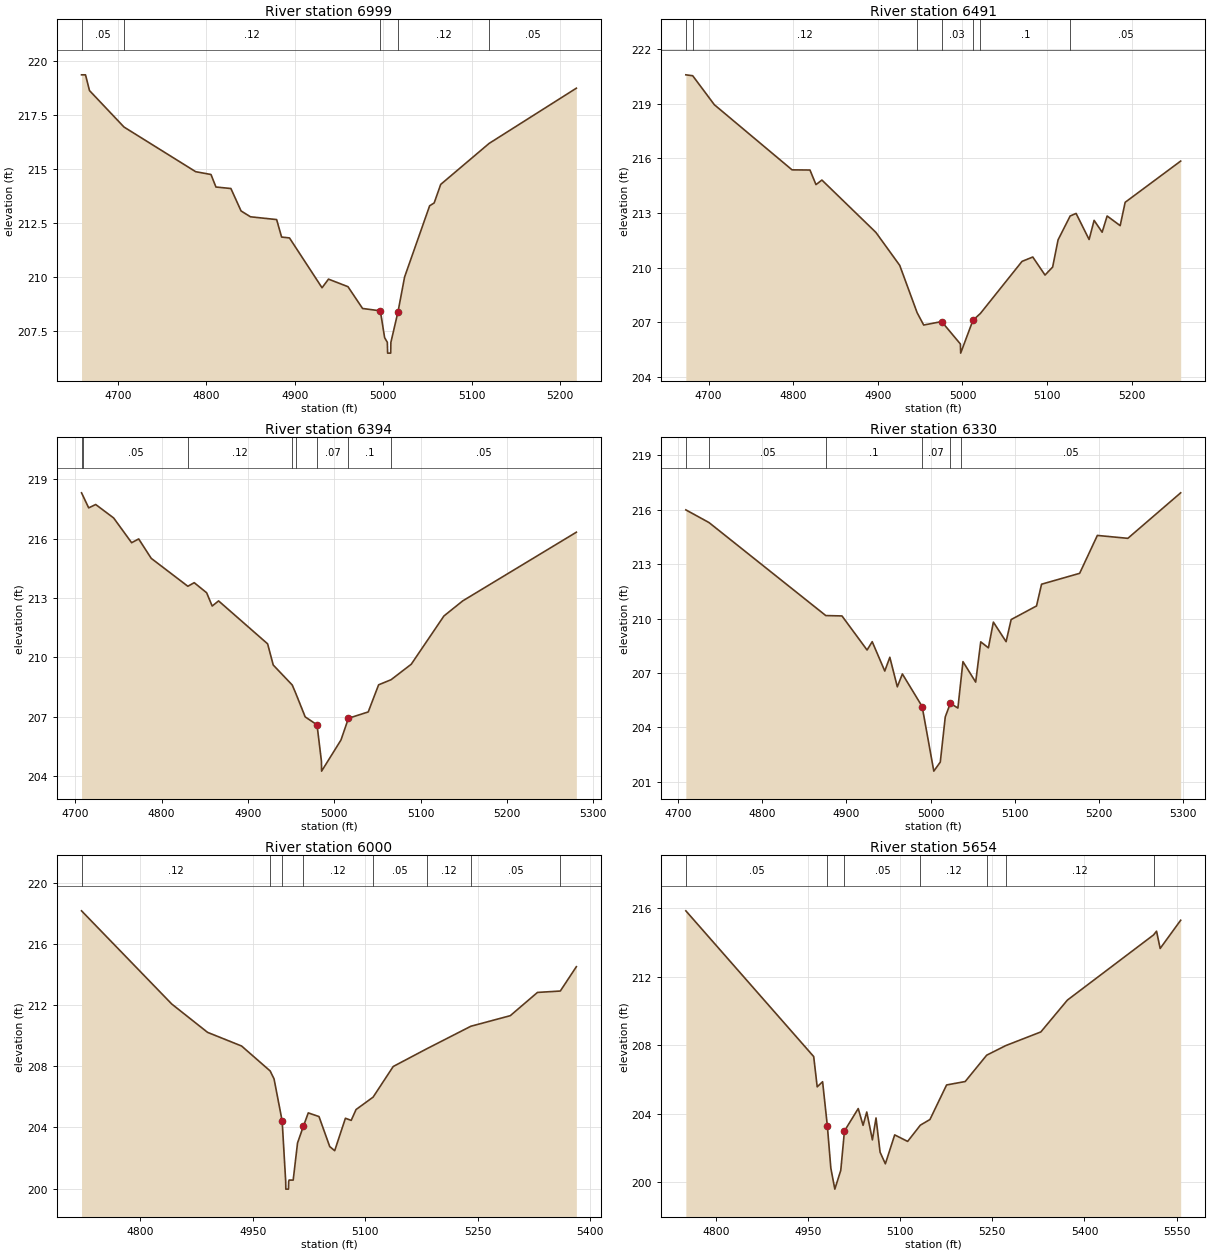
Type RM Length L Ch R = 1 ,6999    ,508,508,508
BEGIN DESCRIPTION:
CRYSTAL CREEK TRIBUTARY NO 4 14.0
END DESCRIPTION:
XS GIS Cut Line= 3
      3859076.65     10125697.96      3858934.37     10126004.25
      3858890.81      10126221.4
#Sta/Elev= 30
  4659.1  219.36  4663.6  219.36  4668.1  218.63  4707.1  216.94  4788.1  214.87
  4805.4  214.74    4811  214.16  4827.9  214.09  4839.4  213.05    4850  212.78
  4879.6  212.65  4885.2  211.84  4894.1   211.8  4930.9  209.49  4938.2  209.89
  4960.2  209.54  4976.7  208.53  4996.8  208.42  5001.6  207.18  5004.7  206.96
    5005  206.46  5008.5  206.46  5008.7  206.96 5016.77  208.38  5024.2  209.99
  5052.5  213.29  5057.6  213.42    5065  214.28  5119.7  216.18  5218.3  218.74
#Mann= 5 ,-1 , 0
  4659.1     .05       0  4707.1     .12       0  4996.8     .07       0
 5016.77     .12       0  5119.7     .05       0
Bank Sta=4996.8,5016.77
XS Rating Curve= 0 ,0
Exp/Cntr=0.3,0.1

Type RM Length L Ch R = 1 ,6491    ,97,97,97
BEGIN DESCRIPTION:
CRYSTAL CREEK TRIBUTARY NO 4 13.0
END DESCRIPTION:
XS GIS Cut Line= 3
      3858851.24     10125566.92      3858622.31     10125800.28
      3858487.25     10126019.99
#Sta/Elev= 30
  4673.1  220.58  4681.2  220.53  4706.8  218.94  4798.6  215.37  4819.8  215.36
  4826.9  214.56  4833.9  214.81  4897.7  211.94  4925.9  210.13  4946.4  207.54
  4954.2  206.86  4975.4  207.05  4997.6  205.82  4997.9  205.32  5012.4  207.12
  5021.3   207.5  5070.4  210.35  5083.1  210.59  5097.6   209.6  5106.6  210.04
    5113  211.53  5127.3  212.84  5134.3  212.98  5149.7  211.55  5155.6   212.6
  5165.1  211.95    5171  212.84  5186.4  212.31  5192.3  213.59  5257.9  215.85
#Mann= 7 ,-1 , 0
  4673.1     .05       0  4681.2     .12       0  4946.4     .05       0
  4975.4     .03       0  5012.4     .05       0  5021.3      .1       0
  5127.3     .05       0
Bank Sta=4975.4,5012.4
XS Rating Curve= 0 ,0
Exp/Cntr=0.3,0.1

Type RM Length L Ch R = 1 ,6394    ,64,64,64
BEGIN DESCRIPTION:
Mapping XS a1dd1edb
END DESCRIPTION:
XS GIS Cut Line= 3
      3858714.94      10125525.7      3858533.97     10125758.74
      3858399.87      10126002.2
#Sta/Elev= 30
  4707.4  218.31  4709.6  218.11  4715.7  217.55  4723.8  217.72  4744.6  217.04
  4765.4  215.79  4773.6  215.98  4788.1     215  4830.5  213.59  4837.9  213.77
  4852.3  213.26  4858.7  212.59  4866.1  212.85  4922.9  210.68  4929.4  209.61
  4951.4   208.6  4955.5  208.18  4966.4  206.99  4980.1  206.59  4985.2  204.75
  4985.4  204.25  5007.8  205.82  5016.5  206.92  5039.4  207.24  5051.4  208.61
  5065.9  208.87  5089.2  209.65  5127.1  212.09  5148.8  212.85  5280.4  216.32
#Mann= 8 ,-1 , 0
  4707.4     .12       0  4709.6     .05       0  4830.5     .12       0
  4951.4     .05       0  4955.5      .1       0  4980.1     .07       0
  5016.5      .1       0  5065.9     .05       0
Bank Sta=4980.1,5016.5
XS Rating Curve= 0 ,0
Exp/Cntr=0.3,0.1

Type RM Length L Ch R = 1 ,6330    ,330,330,330
BEGIN DESCRIPTION:
Mapping XS 610bbb70
END DESCRIPTION:
XS GIS Cut Line= 3
      3858647.27     10125482.68      3858479.28     10125727.49
      3858319.11     10125969.71
#Sta/Elev= 30
  4709.5     216    4737   215.3  4875.6  210.17  4894.8  210.15  4924.6  208.27
  4930.7  208.73  4945.6  207.11  4951.6  207.87  4960.5  206.24  4966.5  206.95
 4989.97 205.153  5003.8  201.59  5011.5  202.09  5017.4  204.58  5023.4  205.33
  5032.4  205.07  5036.1  206.65  5038.4  207.63  5053.5   206.5  5059.5  208.72
  5068.6  208.39  5074.5  209.81  5089.6  208.73  5095.6  209.95  5125.7   210.7
  5131.7   211.9  5176.9   212.5  5197.9  214.59  5234.1  214.43  5296.8  216.94
#Mann= 6 ,-1 , 0
  4709.5     .12       0    4737     .05       0  4875.6      .1       0
 4989.97     .07       0  5023.4      .1       0  5036.1     .05       0
Bank Sta=4989.97,5023.4
XS Rating Curve= 0 ,0
Exp/Cntr=0.3,0.1

Type RM Length L Ch R = 1 ,6000    ,346,346,346
BEGIN DESCRIPTION:
CRYSTAL CREEK TRIBUTARY NO 4 12.0
END DESCRIPTION:
XS GIS Cut Line= 3
      3858624.65     10125320.02      3858367.92      10125427.2
      3858121.75     10125718.38
#Sta/Elev= 30
  4721.8  218.15  4842.1  212.06  4889.8  210.21  4935.1  209.32  4973.2  207.69
  4978.4  207.17  4989.2  204.42  4993.9  200.47  4994.1  199.97  4997.6  199.97
  4997.9  200.47  4998.5  200.56  5003.9  200.56  5009.7  202.99  5017.5  204.08
    5024  204.95  5038.3  204.71  5052.6  202.75  5059.2  202.48  5073.5   204.6
  5081.2  204.46  5087.7  205.17  5110.4  205.98  5137.2  207.98  5181.6  209.13
  5240.7  210.61  5293.2   211.3  5329.5  212.82  5359.9  212.91  5381.3   214.5
#Mann= 8 ,-1 , 0
  4721.8     .12       0  4973.2      .1       0  4989.2     .07       0
  5017.5     .12       0  5110.4     .05       0  5181.6     .12       0
  5240.7     .05       0  5359.9     .12       0
Bank Sta=4989.2,5017.5
XS Rating Curve= 0 ,0
Exp/Cntr=0.3,0.1

Type RM Length L Ch R = 1 ,5654    ,654,654,654
BEGIN DESCRIPTION:
CRYSTAL CREEK TRIBUTARY NO 4 11.0
END DESCRIPTION:
XS GIS Cut Line= 3
      3858436.27     10125060.39      3858214.37     10125173.57
      3857746.51     10125475.26
#Sta/Elev= 30
  4750.9  215.85  4959.1  207.33  4964.8  205.56  4973.6  205.86  4981.4  203.25
    4987  200.81  4993.5  199.58  5003.2  200.68  5009.2  202.98  5031.6  204.29
  5039.5  203.31  5045.5  204.09  5054.7  202.46  5060.6  203.74  5067.2  201.74
  5075.8  201.06    5091  202.75  5112.1  202.37  5132.8  203.32  5148.4  203.65
  5175.5  205.67  5205.8  205.87  5240.8  207.41  5271.8  207.97    5329  208.77
  5372.2  210.63  5512.5  214.44  5517.4  214.66  5523.3  213.65  5556.7   215.3
#Mann= 7 ,-1 , 0
  4750.9     .05       0  4981.4     .07       0  5009.2     .05       0
  5132.8     .12       0  5240.8     .05       0  5271.8     .12       0
  5512.5     .05       0
Bank Sta=4981.4,5009.2
XS Rating Curve= 0 ,0
Exp/Cntr=0.3,0.1

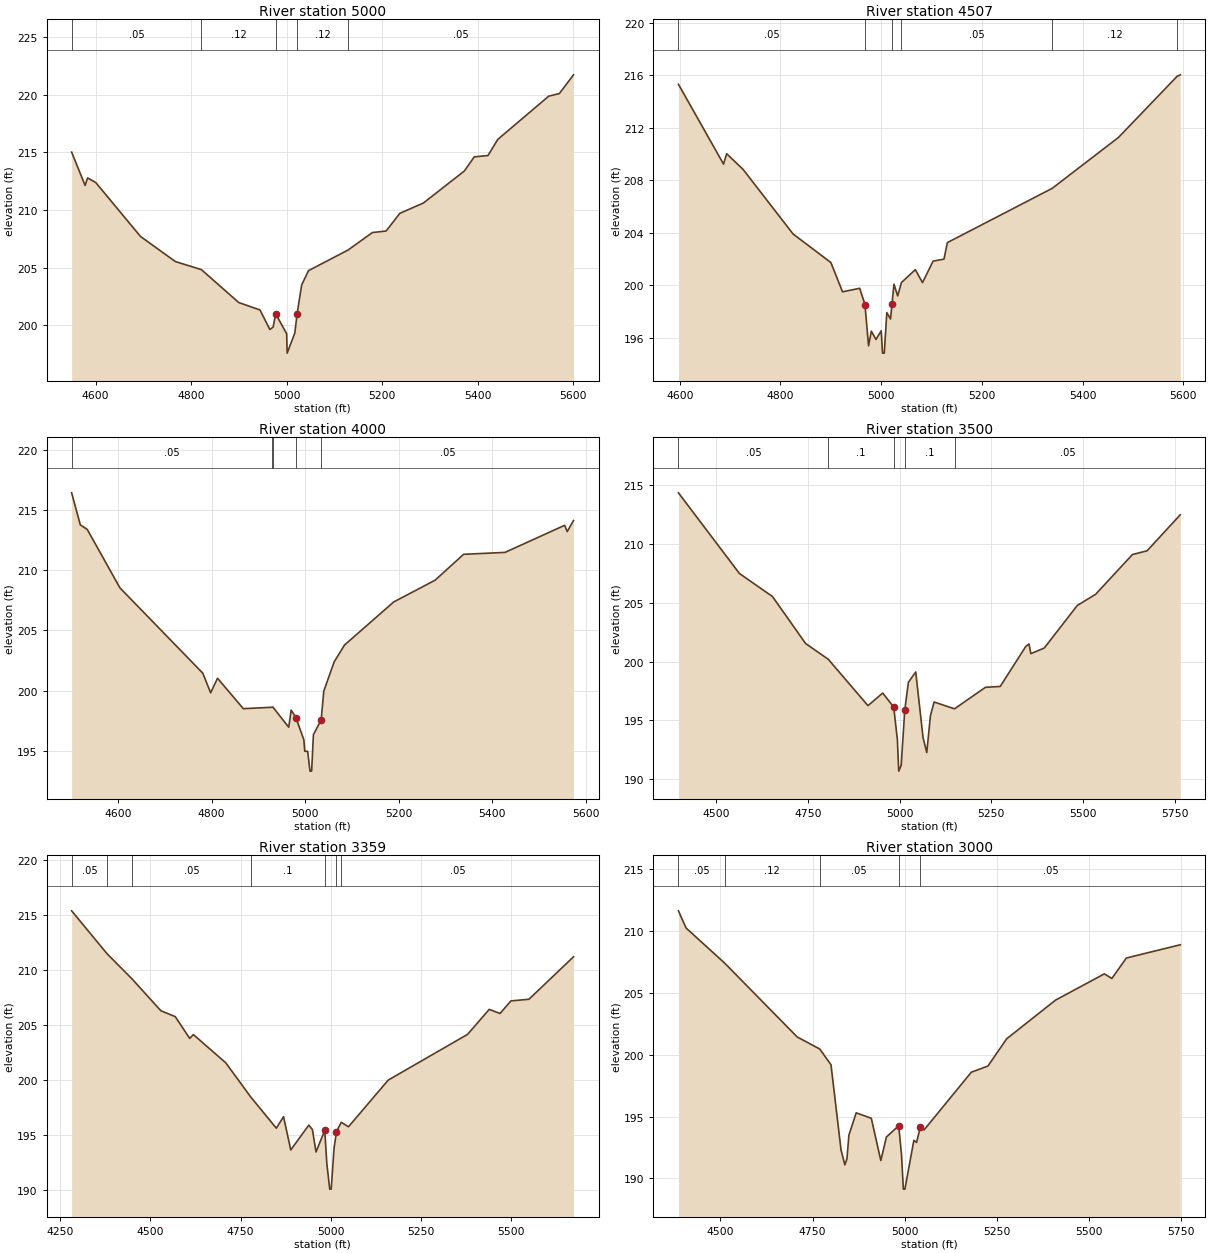
Type RM Length L Ch R = 1 ,5000    ,493,493,493
BEGIN DESCRIPTION:
CRYSTAL CREEK TRIBUTARY NO 4 10.0
END DESCRIPTION:
XS GIS Cut Line= 3
      3858296.28     10124737.09       3857864.1     10124863.53
      3857405.41     10125251.25
#Sta/Elev= 30
  4549.7  215.02  4577.9  212.13  4583.1  212.78  4600.2  212.38  4693.9   207.7
  4766.9  205.52  4821.4  204.82  4899.7  201.96    4944  201.32  4964.8  199.62
  4971.7  199.83  4976.9  200.99    5000  199.25    5001  197.57  5017.1  199.32
 5021.89 200.993  5031.4  203.49  5045.7  204.73  5128.5  206.52  5179.6  208.04
  5208.2  208.17  5236.8   209.7  5286.2   210.6    5372  213.38  5392.8  214.61
  5421.4  214.72  5442.2  216.13  5548.8  219.88  5570.9   220.1  5600.6  221.73
#Mann= 5 ,-1 , 0
  4549.7     .05       0  4821.4     .12       0  4976.9     .07       0
 5021.89     .12       0  5128.5     .05       0
Bank Sta=4976.9,5021.89
XS Rating Curve= 0 ,0
Exp/Cntr=0.3,0.1

Type RM Length L Ch R = 1 ,4507    ,507,507,507
BEGIN DESCRIPTION:
CRYSTAL CREEK TRIBUTARY NO 4 9.0
END DESCRIPTION:
XS GIS Cut Line= 3
      3858085.06     10124309.42      3857718.43     10124475.75
      3857316.25     10124912.76
#Sta/Elev= 30
  4597.4  215.31  4686.9  209.23  4693.2  210.02  4726.1  208.81  4824.9  203.91
  4900.1  201.73  4923.2   199.5  4957.3  199.77  4967.7  198.53  4974.9  195.39
  4980.4   196.5  4989.6  195.87    5000  196.53  5002.6  194.83  5006.1  194.83
  5011.1  197.92  5018.5  197.43 5021.46 198.584  5025.3  200.08  5032.7  199.19
  5040.2  200.21  5067.8  201.19    5082   200.2    5103  201.84  5124.6  201.99
  5131.4  203.25  5339.4  207.38  5471.1  211.26  5587.6  215.92  5593.9  216.03
#Mann= 6 ,-1 , 0
  4597.4     .05       0  4967.7     .03       0 5021.46     .05       0
  5040.2     .05       0  5339.4     .12       0  5587.6     .05       0
Bank Sta=4967.7,5021.46
XS Rating Curve= 0 ,0
Exp/Cntr=0.3,0.1

Type RM Length L Ch R = 1 ,4000    ,500,500,500
BEGIN DESCRIPTION:
CRYSTAL CREEK TRIBUTARY NO 4 8.0
END DESCRIPTION:
XS GIS Cut Line= 3
      3857945.61      10124076.3      3857469.02     10124226.52
       3857206.3      10124737.2
#Sta/Elev= 30
  4500.3  216.43  4518.9  213.77  4533.7  213.39  4603.7  208.53    4781  201.44
  4797.8  199.81  4812.5  201.02  4867.8  198.49  4929.3  198.61  4930.8  198.63
  4964.9  196.95  4970.1  198.37  4980.3  197.74  4997.2  195.91  4999.3  194.95
  5005.4  194.95  5010.4   193.3  5013.9   193.3  5017.7  196.33  5034.3  197.56
  5039.9  199.95  5062.1  202.38  5084.3  203.78  5189.5  207.36  5278.2  209.17
  5339.1  211.32  5427.8  211.48  5555.3  213.73  5560.9  213.21  5574.3  214.13
#Mann= 5 ,-1 , 0
  4500.3     .05       0  4929.3      .1       0  4930.8     .05       0
  4980.3     .07       0  5034.3     .05       0
Bank Sta=4980.3,5034.3
XS Rating Curve= 0 ,0
Exp/Cntr=0.3,0.1

Type RM Length L Ch R = 1 ,3500    ,141,141,141
BEGIN DESCRIPTION:
CRYSTAL CREEK TRIBUTARY NO 4 7.0
END DESCRIPTION:
XS GIS Cut Line= 3
      3857903.85     10123909.42      3857301.94     10123890.78
      3856537.32     10123902.15
#Sta/Elev= 30
  4397.8  214.36  4563.9   207.5  4653.9  205.54    4744  201.55  4805.9   200.2
    4914  196.26  4954.1  197.33  4984.1  196.14  4994.1  193.36  4997.8  190.69
  5004.5  191.19  5014.1  195.86  5024.1  198.25  5044.1  199.12  5064.1  193.52
  5074.1  192.27  5084.1   195.4  5094.1  196.57  5149.7  195.99  5234.1  197.82
  5274.1  197.89  5344.1  201.31  5352.6   201.5  5357.6  200.68  5394.1  201.16
  5484.1  204.78  5534.1  205.73  5634.2  209.11  5674.2  209.43  5764.7   212.5
#Mann= 5 ,-1 , 0
  4397.8     .05       0  4805.9      .1       0  4984.1     .07       0
  5014.1      .1       0  5149.7     .05       0
Bank Sta=4984.1,5014.1
XS Rating Curve= 0 ,0
Exp/Cntr=0.3,0.1

Type RM Length L Ch R = 1 ,3359    ,359,359,359
BEGIN DESCRIPTION:
Mapping XS ced4b6e5
END DESCRIPTION:
XS GIS Cut Line= 3
        3857935.     10123791.01      3857233.66     10123780.59
      3856544.38     10123784.07
#Sta/Elev= 30
  4281.8  215.34    4380  211.44  4449.8  209.13    4529  206.26    4569  205.72
    4609  203.74  4619.2  204.09    4709  201.52  4777.6  198.44    4849  195.58
    4869  196.63    4889   193.6    4939  195.86    4949  195.45    4959  193.42
  4983.2  195.38    4989  192.35    4997  190.04  5001.1  190.04    5009  193.78
 5015.71 195.256  5028.9  196.12    5049  195.71    5159  199.95    5379  204.11
    5439  206.38    5469  206.01    5499  207.15    5549   207.3  5672.5  211.16
#Mann= 7 ,-1 , 0
  4281.8     .05       0    4380     .12       0  4449.8     .05       0
  4777.6      .1       0  4983.2     .07       0 5015.71      .1       0
  5028.9     .05       0
Bank Sta=4983.2,5015.71
XS Rating Curve= 0 ,0
Exp/Cntr=0.3,0.1

Type RM Length L Ch R = 1 ,3000    ,493,493,493
BEGIN DESCRIPTION:
CRYSTAL CREEK TRIBUTARY NO 4 6.0
END DESCRIPTION:
XS GIS Cut Line= 3
      3857868.17     10123666.27      3857269.16     10123531.88
      3856535.51       10123673.
#Sta/Elev= 30
  4386.1  211.61  4406.9  210.22    4511   207.4    4708  201.43  4769.4  200.45
  4799.8  199.18  4827.1  192.29  4837.4   191.1  4843.1   191.6  4848.3  193.49
  4868.1   195.3  4909.1  194.86  4934.9  191.45  4950.1  193.35  4983.4  194.26
  4991.1  191.89    4996  189.14  5000.2  189.14  5024.5  193.08  5031.9  192.91
  5042.1  194.17  5052.2  193.92  5180.3  198.58  5225.4  199.08  5276.3  201.28
  5408.7   204.4    5541  206.52  5561.4  206.15  5600.8   207.8  5747.1  208.87
#Mann= 5 ,-1 , 0
  4386.1     .05       0    4511     .12       0  4769.4     .05       0
  4983.4     .07       0  5042.1     .05       0
Bank Sta=4983.4,5042.1
XS Rating Curve= 0 ,0
Exp/Cntr=0.3,0.1

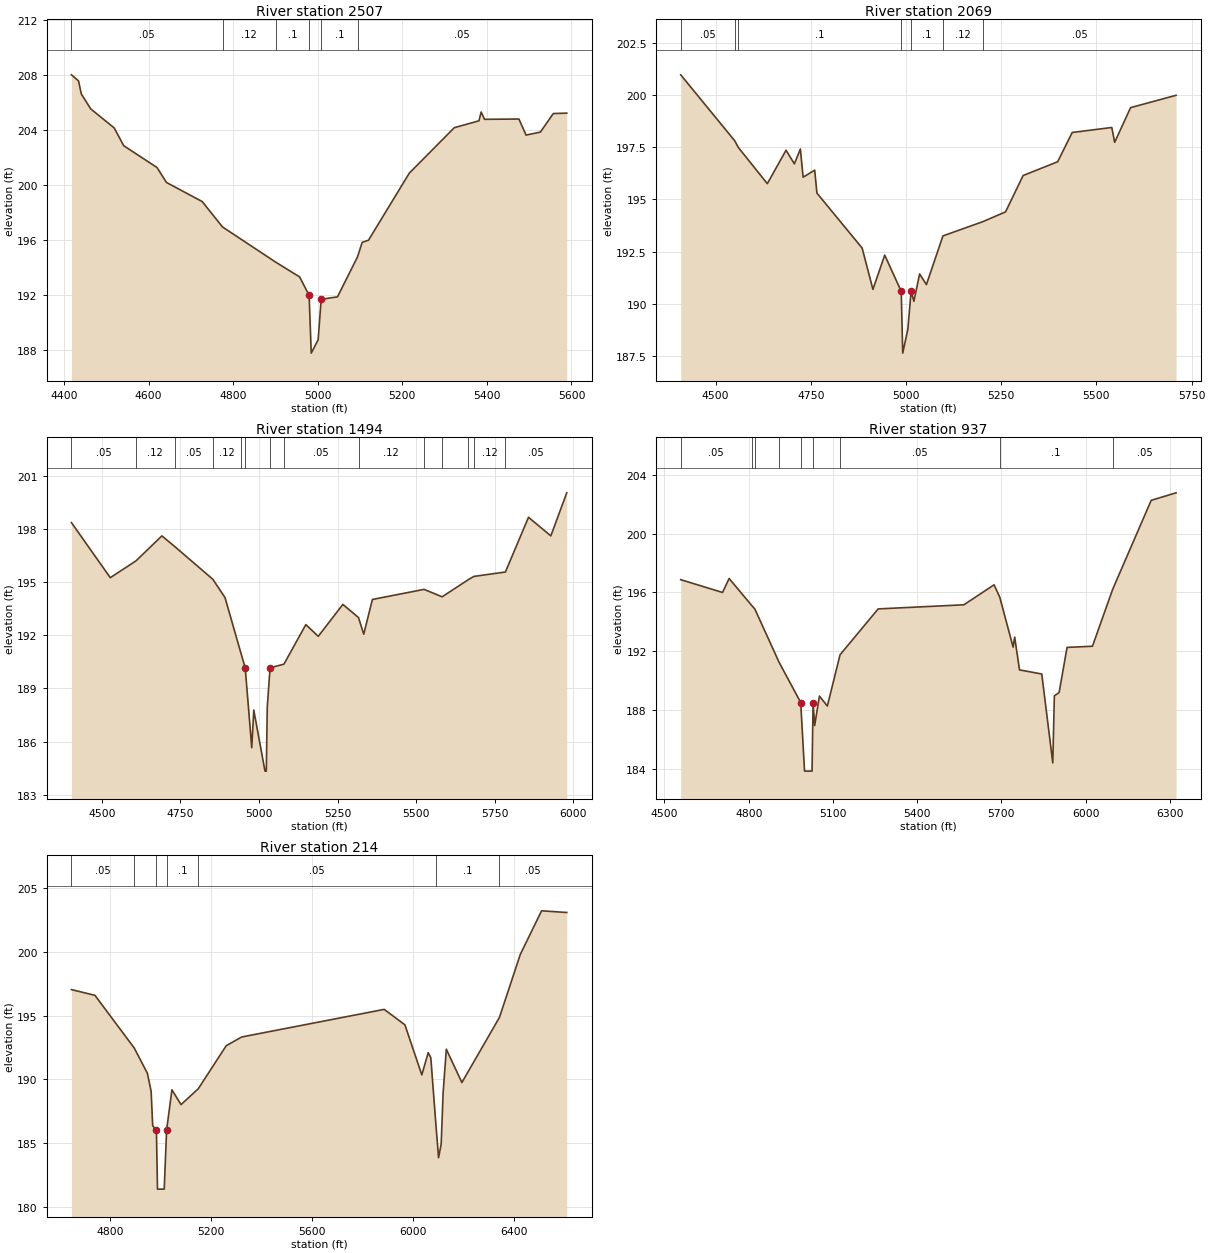
Type RM Length L Ch R = 1 ,2507    ,438,438,438
BEGIN DESCRIPTION:
CRYSTAL CREEK TRIBUTARY NO 4 5.0
END DESCRIPTION:
XS GIS Cut Line= 3
      3857908.79     10123393.08      3857386.86     10123136.92
      3856806.58     10123243.03
#Sta/Elev= 30
  4417.6  208.02  4434.4  207.58  4440.9  206.63  4463.2  205.54  4518.8  204.15
  4541.2  202.86  4619.9  201.27  4642.4  200.18  4726.8  198.79  4774.9  196.94
  4900.5  194.38  4957.2   193.3  4979.7  191.96  4984.7  187.75    5001  188.72
  5008.2  191.67  5046.8  191.85  5094.3  194.77  5105.1  195.82    5120  195.97
  5216.6  200.86    5323  204.17  5381.3  204.67  5386.4  205.31  5394.5  204.78
  5475.8   204.8  5492.8  203.63  5526.6  203.85  5557.1   205.2  5588.9  205.23
#Mann= 6 ,-1 , 0
  4417.6     .05       0  4774.9     .12       0  4900.5      .1       0
  4979.7     .07       0  5008.2      .1       0  5094.3     .05       0
Bank Sta=4979.7,5008.2
XS Rating Curve= 0 ,0
Exp/Cntr=0.3,0.1

Type RM Length L Ch R = 1 ,2069    ,575,575,575
BEGIN DESCRIPTION:
CRYSTAL CREEK TRIBUTARY NO 4 4.0
END DESCRIPTION:
XS GIS Cut Line= 3
      3857998.26     10123108.84      3857482.14     10122819.88
      3856803.69     10123025.76
#Sta/Elev= 30
  4408.5  200.96  4550.5   197.8  4559.5  197.49  4635.9  195.75    4685  197.35
  4706.9   196.7  4722.7  197.41  4729.9  196.06  4760.3   196.4  4766.1   195.3
  4884.8  192.67  4913.2  190.69  4944.1  192.33  4987.5   190.6  4991.4  187.64
  5004.9  188.79 5013.41 190.603  5020.7  190.12  5035.8  191.43  5053.6  190.92
    5097  193.25  5201.4  193.93  5261.4   194.4  5307.5  196.14  5398.2   196.8
  5436.4   198.2  5540.3  198.44  5547.9  197.73  5589.7  199.39    5709  199.98
#Mann= 7 ,-1 , 0
  4408.5     .05       0  4550.5     .12       0  4559.5      .1       0
  4987.5     .07       0 5013.41      .1       0    5097     .12       0
  5201.4     .05       0
Bank Sta=4987.5,5013.41
XS Rating Curve= 0 ,0
Exp/Cntr=0.3,0.1

Type RM Length L Ch R = 1 ,1494    ,557,557,557
BEGIN DESCRIPTION:
CRYSTAL CREEK TRIBUTARY NO 4 3.0
END DESCRIPTION:
XS GIS Cut Line= 3
      3858145.15     10122968.28      3857673.85     10122602.65
      3856707.89     10122760.66
#Sta/Elev= 30
  4403.5  198.36  4527.1  195.25  4608.9   196.2  4691.2  197.61  4731.9  197.01
  4853.2  195.16  4891.9  194.13  4941.6  191.05  4956.2  190.16    4977  185.65
  4983.4  187.78  5019.1  184.33  5023.3  184.33  5026.3  187.92 5035.15 190.159
  5079.4  190.37    5149   192.6  5188.5  191.94  5266.7  193.74  5316.5     193
  5333.2  192.06  5360.7  194.02  5525.1  194.59  5582.4  194.17  5665.1  195.13
  5683.1  195.32  5783.7  195.57  5857.2  198.66  5928.2  197.61  5978.8  200.04
#Mann= 14 ,-1 , 0
  4403.5     .05       0  4608.9     .12       0  4731.9     .05       0
  4853.2     .12       0  4941.6     .05       0  4956.2     .07       0
 5035.15      .1       0  5079.4     .05       0  5316.5     .12       0
  5525.1     .05       0  5582.4     .12       0  5665.1     .05       0
  5683.1     .12       0  5783.7     .05       0
Bank Sta=4956.2,5035.15
XS Rating Curve= 0 ,0
Exp/Cntr=0.3,0.1

Type RM Length L Ch R = 1 ,937     ,723,723,723
BEGIN DESCRIPTION:
CRYSTAL CREEK TRIBUTARY NO 4 2.0
END DESCRIPTION:
XS GIS Cut Line= 3
      3858335.09     10122551.82      3857927.91     10122379.36
        3856737.     10121805.86
#Sta/Elev= 30
  4557.8  196.87  4706.8     196  4730.2  196.95  4811.3   195.1  4821.4  194.89
  4908.1  191.25 4985.17 188.509  4998.8  183.84  5025.5  183.84  5029.2  188.49
  5034.8  186.94  5051.8  188.95    5080  188.27  5125.3  191.76    5261  194.88
  5566.2  195.16  5673.8  196.52  5694.2  195.67  5741.6  192.28  5747.2  192.96
  5764.3  190.73  5843.6  190.45  5882.9   184.4  5888.5  188.96  5905.5  189.19
  5933.7  192.26  6024.2  192.34  6096.1  196.21  6233.4  202.27  6321.8  202.78
#Mann= 9 ,-1 , 0
  4557.8     .05       0  4811.3      .1       0  4821.4     .05       0
  4908.1      .1       0 4985.17     .07       0  5029.2      .1       0
  5125.3     .05       0  5694.2      .1       0  6096.1     .05       0
Bank Sta=4985.17,5029.2
XS Rating Curve= 0 ,0
Exp/Cntr=0.3,0.1

Type RM Length L Ch R = 1 ,214     ,0,0,0
BEGIN DESCRIPTION:
CRYSTAL CREEK TRIBUTARY NO 4 1.0
END DESCRIPTION:
XS GIS Cut Line= 3
      3858525.17     10122434.59      3858320.66     10122144.54
      3856752.71     10121773.76
#Sta/Elev= 30
  4645.1  197.03  4738.5  196.58  4894.5  192.45  4946.7  190.47  4961.5  189.05
  4967.6  186.37  4982.4  186.01  4986.7   181.4  5013.4   181.4  5022.9 186.021
    5044  189.18  5080.1  188.02  5148.5  189.26  5259.8  192.64  5321.4  193.32
  5886.6  195.48  5968.8  194.27  6035.9  190.35  6061.3  192.09  6071.6  191.69
  6091.7  186.49  6102.4  183.86  6112.7  184.92  6120.5  188.96  6133.2  192.36
  6194.9  189.75    6344  194.85  6426.7  199.78  6511.3   203.2  6611.2  203.07
#Mann= 7 ,-1 , 0
  4645.1     .05       0  4894.5      .1       0  4982.4     .07       0
  5022.9      .1       0  5148.5     .05       0  6091.7      .1       0
    6344     .05       0
Bank Sta=4982.4,5022.9
XS Rating Curve= 0 ,0
Exp/Cntr=0.3,0.1