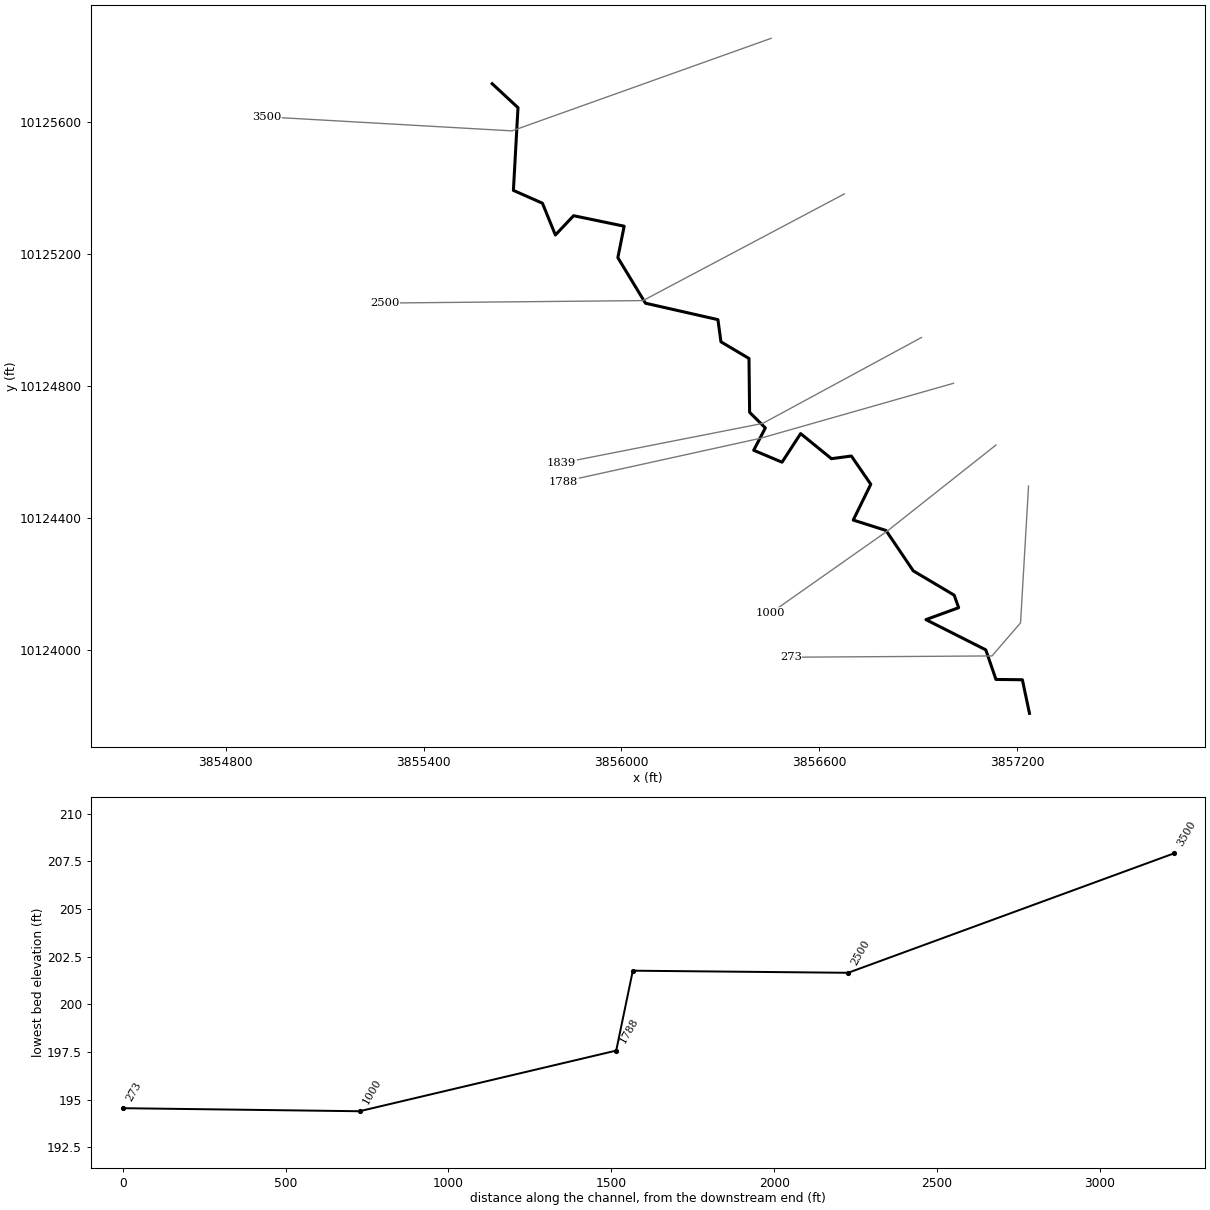
--- CRYSTAL CREEK TRIBUTARY NO 5.prj (project) ---

Proj Title=CRYSTAL CREEK TRIBUTARY NO 5 Base Level Engineering
Current Plan=p01
Default Exp/Contr=0.3,0.1
English Units
Geom File=g01
Flow File=f01
Plan File=p01
Y Axis Title=Elevation
X Axis Title(PF)=Main Channel Distance
X Axis Title(XS)=Station
BEGIN DESCRIPTION:
CRYSTAL CREEK TRIBUTARY NO 5
END DESCRIPTION:
DSS Export Rating Curves= 0
DSS Export Rating Curve Sorted= 0
DSS Export Volume Flow Curves= 0
DXF OffsetX= 0
DXF OffsetY= 0
DXF ScaleX= 1
DXF ScaleY= 10

--- CRYSTAL CREEK TRIBUTARY NO 5.p01 (plan) ---

Plan Title=Multiple Run
Short Identifier=Multiple
Geom File=g01
Flow File=f01
Subcritical Flow
K Sum by GR= 0
Std Step Tol= 0.01
Critical Tol= 0.01
Num of Std Step Trials= 20
Max Error Tol= 0.3
Flow Tol Ratio= 0.001
Split Flow NTrial= 30
Split Flow Tol= 0.02
Split Flow Ratio= 0.02
Log Output Level= 0
Friction Slope Method= 1
Unsteady Friction Slope Method= 2
Unsteady Bridges Friction Slope Method= 1
Parabolic Critical Depth
Global Vel Dist=  1 , 1 , 1
Global Log Level= 0
CheckData=True
Encroach Param= -1, 0, 0, 0
BEGIN DESCRIPTION:
Multiple Run
END DESCRIPTION:

--- CRYSTAL CREEK TRIBUTARY NO 5.f01 (steady flow) ---

Flow Title=Multiple
Program Version=4.10
Number of Profiles= 7
Profile Names=10-year,25-year,50-year,1pct_min,100-year,1pct_plu,500-year
River Rch & RM=CRYSTAL CREEK TR,Reach-1         ,3500
     467     611     807     351    1060    3201    1887
Boundary for River Rch & Prof#=CRYSTAL CREEK TR,Reach-1         , 1
Up Type= 0
Dn Type= 3
Dn Slope=0.008
Boundary for River Rch & Prof#=CRYSTAL CREEK TR,Reach-1         , 2
Up Type= 0
Dn Type= 3
Dn Slope=0.008
Boundary for River Rch & Prof#=CRYSTAL CREEK TR,Reach-1         , 3
Up Type= 0
Dn Type= 3
Dn Slope=0.008
Boundary for River Rch & Prof#=CRYSTAL CREEK TR,Reach-1         , 4
Up Type= 0
Dn Type= 3
Dn Slope=0.008
Boundary for River Rch & Prof#=CRYSTAL CREEK TR,Reach-1         , 5
Up Type= 0
Dn Type= 3
Dn Slope=0.008
Boundary for River Rch & Prof#=CRYSTAL CREEK TR,Reach-1         , 6
Up Type= 0
Dn Type= 3
Dn Slope=0.008
Boundary for River Rch & Prof#=CRYSTAL CREEK TR,Reach-1         , 7
Up Type= 0
Dn Type= 3
Dn Slope=0.008
DSS Import GetInterval= 0
DSS Import GetPeak= 0
DSS Import FillOption= 0

--- CRYSTAL CREEK TRIBUTARY NO 5.g01 (geometry) ---

Geom Title=Existing Conditions
Program Version=4.10

River Reach=CRYSTAL CREEK TR,Reach-1
Reach XY= 30
      3855608.23     10125717.03      3855686.55     10125644.41
      3855672.63     10125393.39      3855760.69     10125354.55
      3855799.96     10125258.11      3855855.19     10125316.63
      3856008.65     10125284.79      3855989.44     10125189.34
      3856073.26     10125051.19      3856293.05     10125001.32
      3856302.29     10124934.02      3856387.31     10124883.55
      3856389.19     10124720.16      3856436.91     10124672.83
      3856401.61     10124605.04      3856487.55     10124568.81
      3856543.94     10124655.59      3856637.48     10124579.52
      3856697.89     10124587.59       3856756.8     10124501.84
      3856703.57     10124393.34      3856802.97     10124361.73
      3856885.64     10124239.25      3857009.81     10124165.49
      3857023.38     10124127.48       3856924.1     10124091.26
      3857105.64     10123999.59      3857136.55     10123909.82
      3857216.64     10123908.84      3857238.24     10123806.86

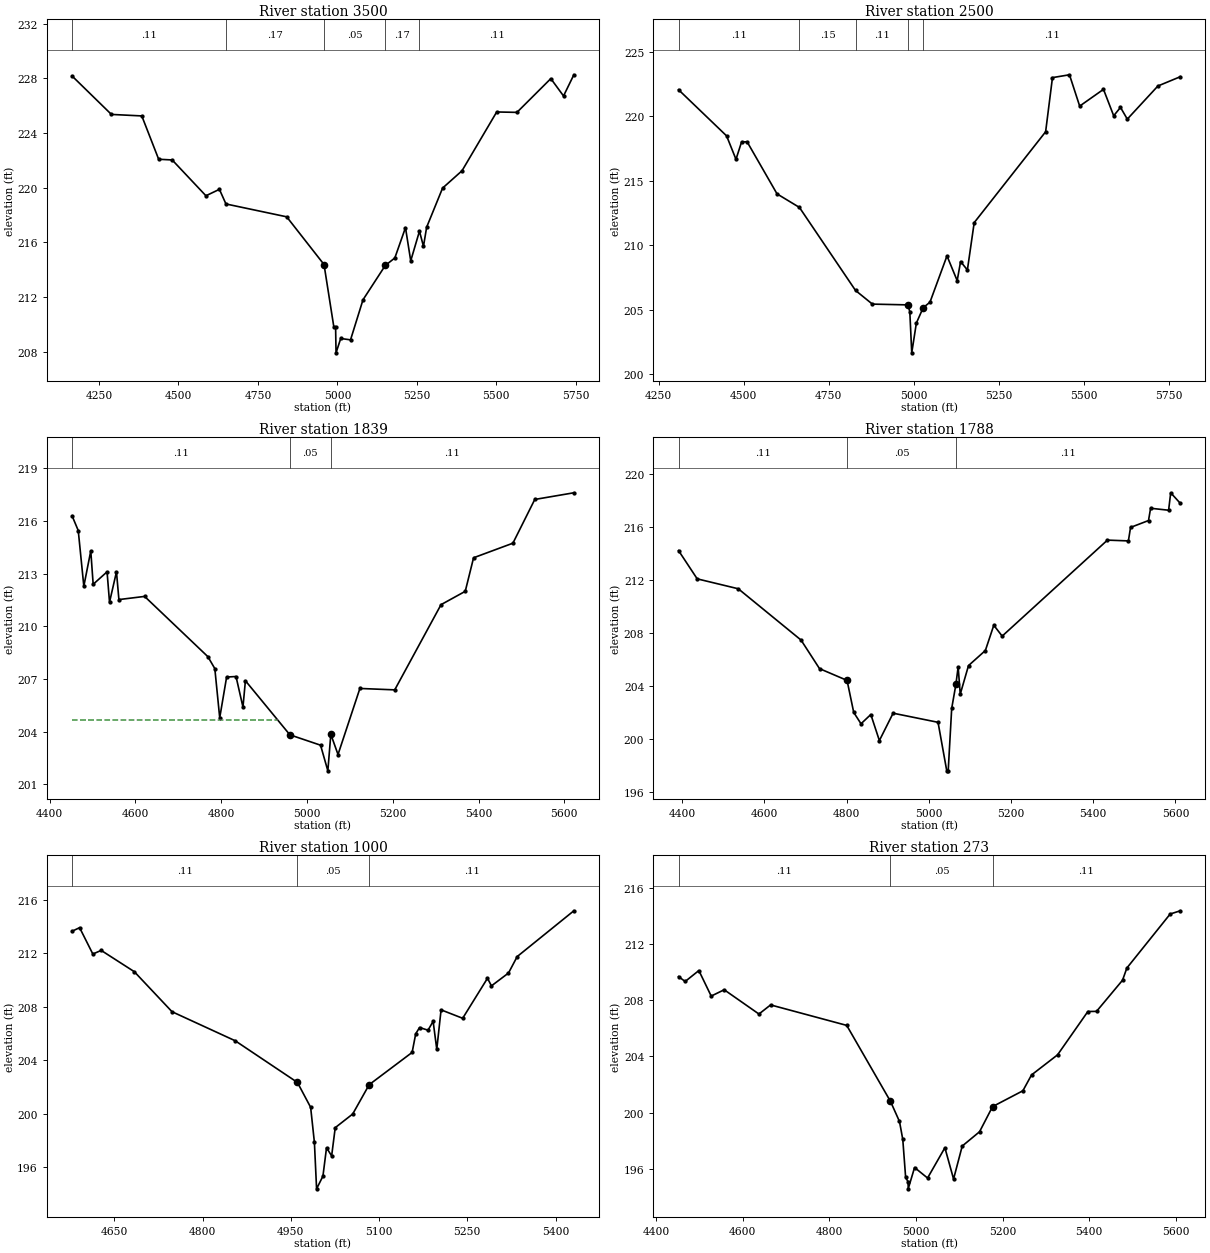
Type RM Length L Ch R = 1 ,3500    ,1000,1000,1000
BEGIN DESCRIPTION:
CRYSTAL CREEK TRIBUTARY NO 5 6.0
END DESCRIPTION:
XS GIS Cut Line= 3
      3856454.49      10125854.7      3855668.31     10125573.95
      3854925.42     10125616.36
#Sta/Elev= 30
  4165.2  228.17    4289  225.36  4384.6  225.25  4437.7  222.08  4480.2  222.03
  4586.4  219.41  4628.8  219.88  4649.4  218.81  4840.5  217.87    4958  214.38
  4989.1  209.78  4994.4  209.83  4995.8  207.92  5010.5  208.97  5041.4  208.87
  5080.6   211.8  5150.7  214.31  5180.8  214.86  5214.3  217.08  5230.8  214.65
  5258.3  216.82  5270.9  215.71  5280.9  217.11    5331  219.97  5392.2  221.24
  5501.3  225.54    5565  225.51  5671.6  227.98  5711.6  226.71  5744.1  228.26
#Mann= 5 ,-1 , 0
  4165.2     .11       0  4649.4     .17       0    4958     .05       0
  5150.7     .17       0  5258.3     .11       0
Bank Sta=4958,5150.7
XS Rating Curve= 0 ,0
Exp/Cntr=0.3,0.1

Type RM Length L Ch R = 1 ,2500    ,661,661,661
BEGIN DESCRIPTION:
CRYSTAL CREEK TRIBUTARY NO 5 5.0
END DESCRIPTION:
XS GIS Cut Line= 3
      3856676.64     10125382.76      3856065.78      10125059.1
      3855281.92     10125051.65
#Sta/Elev= 30
  4308.7  222.07    4450  218.49  4477.6  216.67    4494  218.02  4510.3  218.03
  4598.3  213.99  4664.1  212.94    4829   206.5  4878.6  205.44  4982.9  205.38
  4988.6  204.85  4994.3  201.66  5007.9  203.97  5027.9  205.16  5047.9  205.59
  5097.9  209.18  5127.9  207.26  5137.9  208.74  5157.9  208.09  5177.9  211.76
  5387.9  218.81    5408  223.01    5458  223.23    5488   220.8    5558   222.1
    5588  220.05    5608   220.7    5628  219.79    5718  222.36  5783.9  223.08
#Mann= 5 ,-1 , 0
  4308.7     .11       0  4664.1     .15       0    4829     .11       0
  4982.9     .05       0  5027.9     .11       0
Bank Sta=4982.9,5027.9
XS Rating Curve= 0 ,0
Exp/Cntr=0.3,0.1

Type RM Length L Ch R = 1 ,1839    ,51,51,51
BEGIN DESCRIPTION:
CRYSTAL CREEK TRIBUTARY NO 5 4.0
END DESCRIPTION:
XS GIS Cut Line= 3
      3856910.53     10124947.14      3856428.93      10124686.5
      3855818.44      10124566.4
#Sta/Elev= 30
  4452.4  216.29  4466.8  215.45  4479.8  212.28    4496  214.29  4501.6  212.39
    4534   213.1  4539.7  211.37  4555.9   213.1  4561.6  211.52  4621.5   211.7
    4769  208.27  4785.2  207.59  4796.6  204.79  4812.7  207.11  4834.6  207.14
  4850.8   205.4  4856.5   206.9  4960.2  203.82  5031.7  203.23  5048.7  201.77
  5055.6  203.85  5072.4   202.7  5123.4  206.46  5204.6  206.38  5312.5  211.23
    5369  211.99  5388.4   213.9  5480.1  214.73  5531.1  217.22  5622.2   217.6
#Mann= 3 , 0 , 0
  4452.4     .11       0  4960.2     .05       0  5055.6     .11       0
#XS Ineff= 2 , 0
       0  4932.6  204.64               0
Permanent Ineff=
       F       F
Bank Sta=4960.2,5055.6
XS Rating Curve= 0 ,0
Exp/Cntr=0.3,0.1

Type RM Length L Ch R = 1 ,1788    ,788,788,788
BEGIN DESCRIPTION:
CRYSTAL CREEK TRIBUTARY NO 5 3.0
END DESCRIPTION:
XS GIS Cut Line= 3
      3857007.64     10124808.21      3856422.31     10124641.51
      3855824.71     10124509.99
#Sta/Elev= 30
  4391.4  214.24  4436.8   212.1  4536.7  211.35  4689.4  207.47  4734.3  205.31
  4801.3  204.42  4817.5     202  4835.2  201.14  4859.1  201.84  4879.9  199.87
  4913.3  201.94  5022.6  201.25  5043.8  197.58  5047.3  197.58  5055.8   202.3
    5066  204.11  5071.5  205.44  5076.6  203.38  5096.7  205.54  5137.7  206.68
  5158.2  208.59  5178.6  207.77  5434.6  215.03  5485.6  214.97  5490.8  215.99
  5534.5  216.51  5539.6  217.44  5583.4  217.29  5588.5  218.61  5611.9  217.81
#Mann= 3 , 0 , 0
  4391.4     .11       0  4801.3     .05       0    5066     .11       0
Bank Sta=4801.3,5066
XS Rating Curve= 0 ,0
Exp/Cntr=0.3,0.1

Type RM Length L Ch R = 1 ,1000    ,727,727,727
BEGIN DESCRIPTION:
Mapping XS cb3f8720
END DESCRIPTION:
XS GIS Cut Line= 3
      3857136.63     10124621.05      3856805.98     10124359.31
      3856453.24      10124111.3
#Sta/Elev= 30
  4578.3  213.64  4591.1  213.91  4613.6  211.94  4627.8  212.21  4684.1  210.62
  4748.2  207.63  4855.6  205.46  4961.3  202.35  4983.8  200.49  4990.2  197.87
  4993.9   194.4  5004.7  195.35  5010.8  197.47  5019.5  196.86  5025.6  198.97
  5055.3  199.99  5083.3  202.18  5156.3  204.59  5162.4  205.98  5168.9  206.45
  5183.3  206.25    5192  206.91  5198.2  204.82  5205.5  207.77  5242.2  207.14
  5284.4  210.13  5291.1  209.56  5320.1  210.52  5334.9  211.75  5431.2  215.17
#Mann= 3 , 0 , 0
  4578.3     .11       0  4961.3     .05       0  5083.3     .11       0
Bank Sta=4961.3,5083.3
XS Rating Curve= 0 ,0
Exp/Cntr=0.3,0.1

Type RM Length L Ch R = 1 ,273     ,0,0,0
BEGIN DESCRIPTION:
CRYSTAL CREEK TRIBUTARY NO 5 2.0
END DESCRIPTION:
XS GIS Cut Line= 4
      3857235.39     10124496.32      3857211.09     10124081.38
      3857124.55     10123981.12      3856514.46     10123977.21
#Sta/Elev= 30
  4451.9  209.69  4467.2  209.34  4498.8  210.12  4527.3   208.3  4557.3  208.75
  4637.5  207.02  4664.4  207.67  4840.1  206.21    4941   200.8  4961.9  199.36
  4969.5  198.08  4976.1  195.37  4981.8  195.06    4982  194.56  4996.7  196.08
  5026.7  195.33  5066.7  197.49  5086.7  195.26  5106.7  197.61  5146.7  198.63
  5176.7  200.42  5246.7  201.55  5266.7  202.68  5326.7  204.11  5396.7   207.2
  5416.7  207.21  5476.7  209.43  5486.7   210.3  5586.7  214.15  5610.1  214.38
#Mann= 3 , 0 , 0
  4451.9     .11       0    4941     .05       0  5176.7     .11       0
Bank Sta=4941,5176.7
XS Rating Curve= 0 ,0
Exp/Cntr=0.3,0.1

Chan Stop Cuts=-1
Use User Specified Reach Order=0
Composite Channel Slope=5

--- CRYSTAL CREEK TRIBUTARY NO 5.g10 (geometry) ---

Geom Title=Existing Conditions
Program Version=4.10

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
River Reach=CRYSTAL CREEK TR,Reach-1

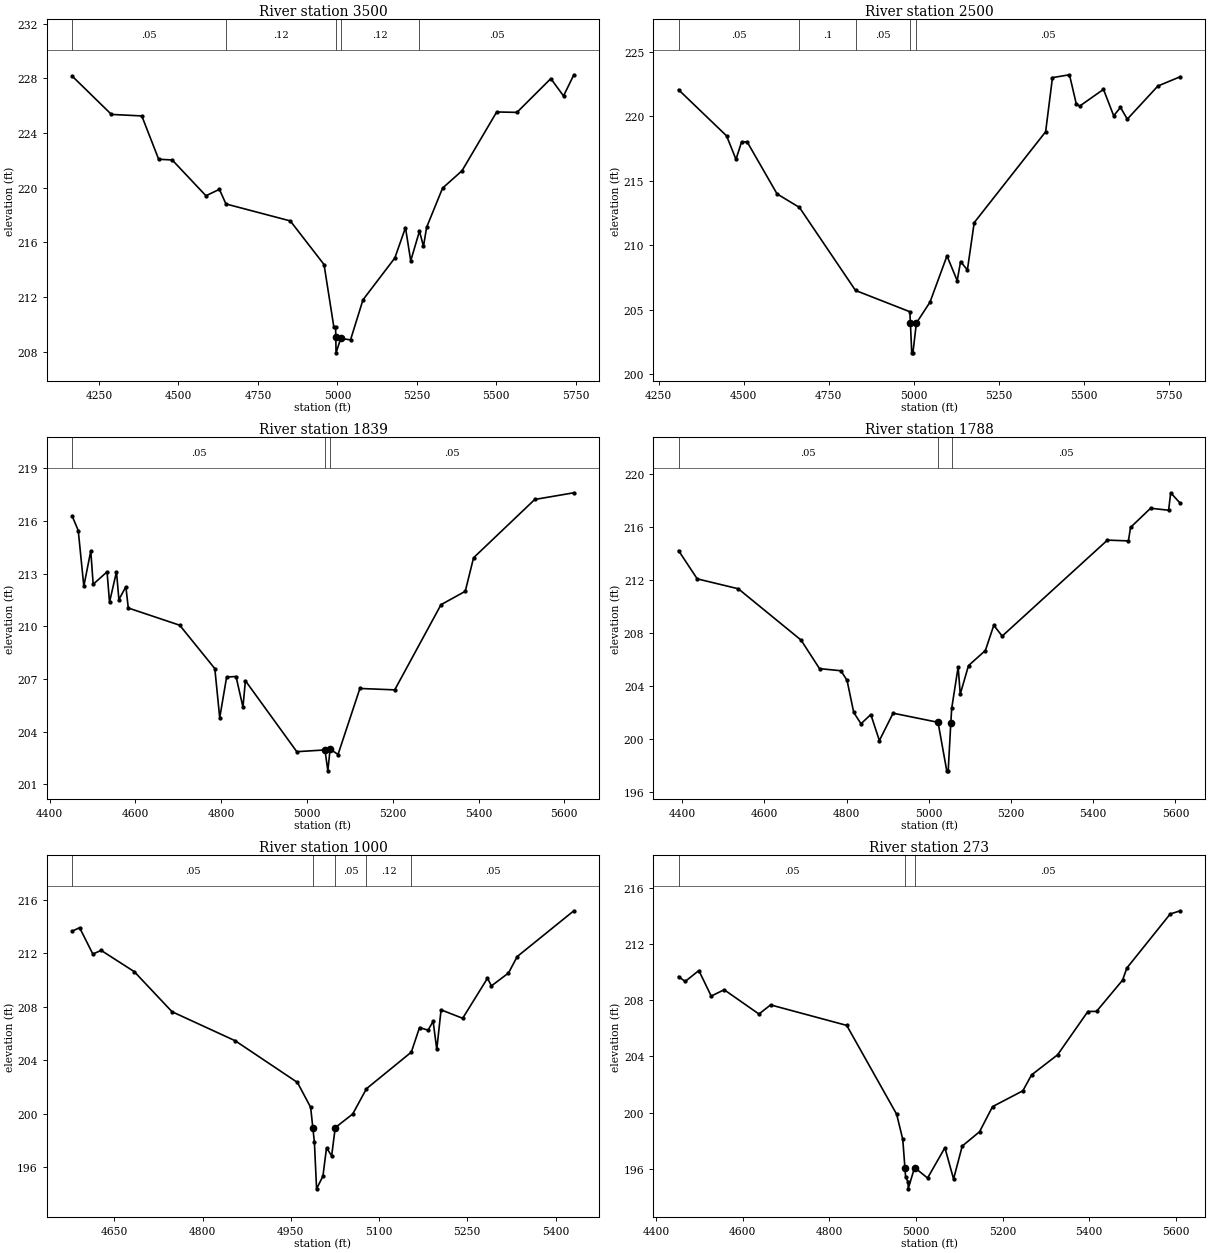
Type RM Length L Ch R = 1 ,3500    ,1000,1000,1000
BEGIN DESCRIPTION:
CRYSTAL CREEK TRIBUTARY NO 5 6.0
END DESCRIPTION:
XS GIS Cut Line= 3
      3856454.49      10125854.7      3855668.31     10125573.95
      3854925.42     10125616.36
#Sta/Elev= 30
  4165.2  228.17    4289  225.36  4384.6  225.25  4437.7  222.08  4480.2  222.03
  4586.4  219.41  4628.8  219.88  4649.4  218.81  4851.8  217.57    4958  214.38
  4989.1  209.78  4994.4  209.83 4995.07 209.043  4995.8  207.92  5010.5  208.97
  5041.4  208.87  5080.6   211.8  5180.8  214.86  5214.3  217.08  5230.8  214.65
  5258.3  216.82  5270.9  215.71  5280.9  217.11    5331  219.97  5392.2  221.24
  5501.3  225.54    5565  225.51  5671.6  227.98  5711.6  226.71  5744.1  228.26
#Mann= 5 ,-1 , 0
  4165.2     .05       0  4649.4     .12       0 4995.07     .03       0
  5010.5     .12       0  5258.3     .05       0
Bank Sta=4995.07,5010.5
XS Rating Curve= 0 ,0
Exp/Cntr=0.3,0.1

Type RM Length L Ch R = 1 ,2500    ,661,661,661
BEGIN DESCRIPTION:
CRYSTAL CREEK TRIBUTARY NO 5 5.0
END DESCRIPTION:
XS GIS Cut Line= 3
      3856676.64     10125382.76      3856065.78      10125059.1
      3855281.92     10125051.65
#Sta/Elev= 30
  4308.7  222.07    4450  218.49  4477.6  216.67    4494  218.02  4510.3  218.03
  4598.3  213.99  4664.1  212.94    4829   206.5  4988.6  204.85 4990.42 203.943
  4994.3  201.66  4997.8  201.66  5007.9  203.97  5047.9  205.59  5097.9  209.18
  5127.9  207.26  5137.9  208.74  5157.9  208.09  5177.9  211.76  5387.9  218.81
    5408  223.01    5458  223.23    5478  220.97    5488   220.8    5558   222.1
    5588  220.05    5608   220.7    5628  219.79    5718  222.36  5783.9  223.08
#Mann= 5 ,-1 , 0
  4308.7     .05       0  4664.1      .1       0    4829     .05       0
  4988.6     .03       0  5007.9     .05       0
Bank Sta=4990.42,5007.9
XS Rating Curve= 0 ,0
Exp/Cntr=0.3,0.1

Type RM Length L Ch R = 1 ,1839    ,51,51,51
BEGIN DESCRIPTION:
CRYSTAL CREEK TRIBUTARY NO 5 4.0
END DESCRIPTION:
XS GIS Cut Line= 3
      3856910.53     10124947.14      3856428.93      10124686.5
      3855818.44      10124566.4
#Sta/Elev= 30
  4452.4  216.29  4466.8  215.45  4479.8  212.28    4496  214.29  4501.6  212.39
    4534   213.1  4539.7  211.37  4555.9   213.1  4561.6  211.52  4577.8  212.25
  4583.5  211.04  4703.3  210.06  4785.2  207.59  4796.6  204.79  4812.7  207.11
  4834.6  207.14  4850.8   205.4  4856.5   206.9  4976.3  202.86  5041.9  202.96
  5048.7  201.77 5053.96 203.014  5072.4   202.7  5123.4  206.46  5204.6  206.38
  5312.5  211.23    5369  211.99  5388.4   213.9  5531.1  217.22  5622.2   217.6
#Mann= 3 , 0 , 0
  4452.4     .05       0  5041.9     .03       0 5053.96     .05       0
Bank Sta=5041.9,5053.96
XS Rating Curve= 0 ,0
Exp/Cntr=0.3,0.1

Type RM Length L Ch R = 1 ,1788    ,788,788,788
BEGIN DESCRIPTION:
CRYSTAL CREEK TRIBUTARY NO 5 3.0
END DESCRIPTION:
XS GIS Cut Line= 3
      3857007.64     10124808.21      3856422.31     10124641.51
      3855824.71     10124509.99
#Sta/Elev= 30
  4391.4  214.24  4436.8   212.1  4536.7  211.35  4689.4  207.47  4734.3  205.31
  4786.3  205.15  4801.3  204.42  4817.5     202  4835.2  201.14  4859.1  201.84
  4879.9  199.87  4913.3  201.94  5022.6  201.25  5043.8  197.58  5047.3  197.58
 5053.68 201.222  5055.8   202.3  5071.5  205.44  5076.6  203.38  5096.7  205.54
  5137.7  206.68  5158.2  208.59  5178.6  207.77  5434.6  215.03  5485.6  214.97
  5490.8  215.99  5539.6  217.44  5583.4  217.29  5588.5  218.61  5611.9  217.81
#Mann= 3 ,-1 , 0
  4391.4     .05       0  5022.6     .07       0  5055.8     .05       0
Bank Sta=5022.6,5053.68
XS Rating Curve= 0 ,0
Exp/Cntr=0.3,0.1

Type RM Length L Ch R = 1 ,1000    ,727,727,727
BEGIN DESCRIPTION:
Mapping XS cb3f8720
END DESCRIPTION:
XS GIS Cut Line= 3
      3857136.63     10124621.05      3856805.98     10124359.31
      3856453.24      10124111.3
#Sta/Elev= 30
  4578.3  213.64  4591.1  213.91  4613.6  211.94  4627.8  212.21  4684.1  210.62
  4748.2  207.63  4855.6  205.46  4961.3  202.35  4983.8  200.49  4987.6 198.934
  4990.2  197.87  4993.9   194.4  5004.7  195.35  5010.8  197.47  5019.5  196.86
  5025.6  198.97  5055.3  199.99  5078.7  201.88  5154.9  204.61  5168.9  206.45
  5183.3  206.25    5192  206.91  5198.2  204.82  5205.5  207.77  5242.2  207.14
  5284.4  210.13  5291.1  209.56  5320.1  210.52  5334.9  211.75  5431.2  215.17
#Mann= 5 ,-1 , 0
  4578.3     .05       0  4987.6     .07       0  5025.6     .05       0
  5078.7     .12       0  5154.9     .05       0
Bank Sta=4987.6,5025.6
XS Rating Curve= 0 ,0
Exp/Cntr=0.3,0.1

Type RM Length L Ch R = 1 ,273     ,0,0,0
BEGIN DESCRIPTION:
CRYSTAL CREEK TRIBUTARY NO 5 2.0
END DESCRIPTION:
XS GIS Cut Line= 4
      3857235.39     10124496.32      3857211.09     10124081.38
      3857124.55     10123981.12      3856514.46     10123977.21
#Sta/Elev= 30
  4451.9  209.69  4467.2  209.34  4498.8  210.12  4527.3   208.3  4557.3  208.75
  4637.5  207.02  4664.4  207.67  4840.1  206.21  4955.3  199.88  4969.5  198.08
 4974.39 196.072  4976.1  195.37  4981.8  195.06    4982  194.56  4996.7  196.08
  5026.7  195.33  5066.7  197.49  5086.7  195.26  5106.7  197.61  5146.7  198.63
  5176.7  200.42  5246.7  201.55  5266.7  202.68  5326.7  204.11  5396.7   207.2
  5416.7  207.21  5476.7  209.43  5486.7   210.3  5586.7  214.15  5610.1  214.38
#Mann= 3 , 0 , 0
  4451.9     .05       0 4974.39     .03       0  4996.7     .05       0
Bank Sta=4974.39,4996.7
XS Rating Curve= 0 ,0
Exp/Cntr=0.3,0.1