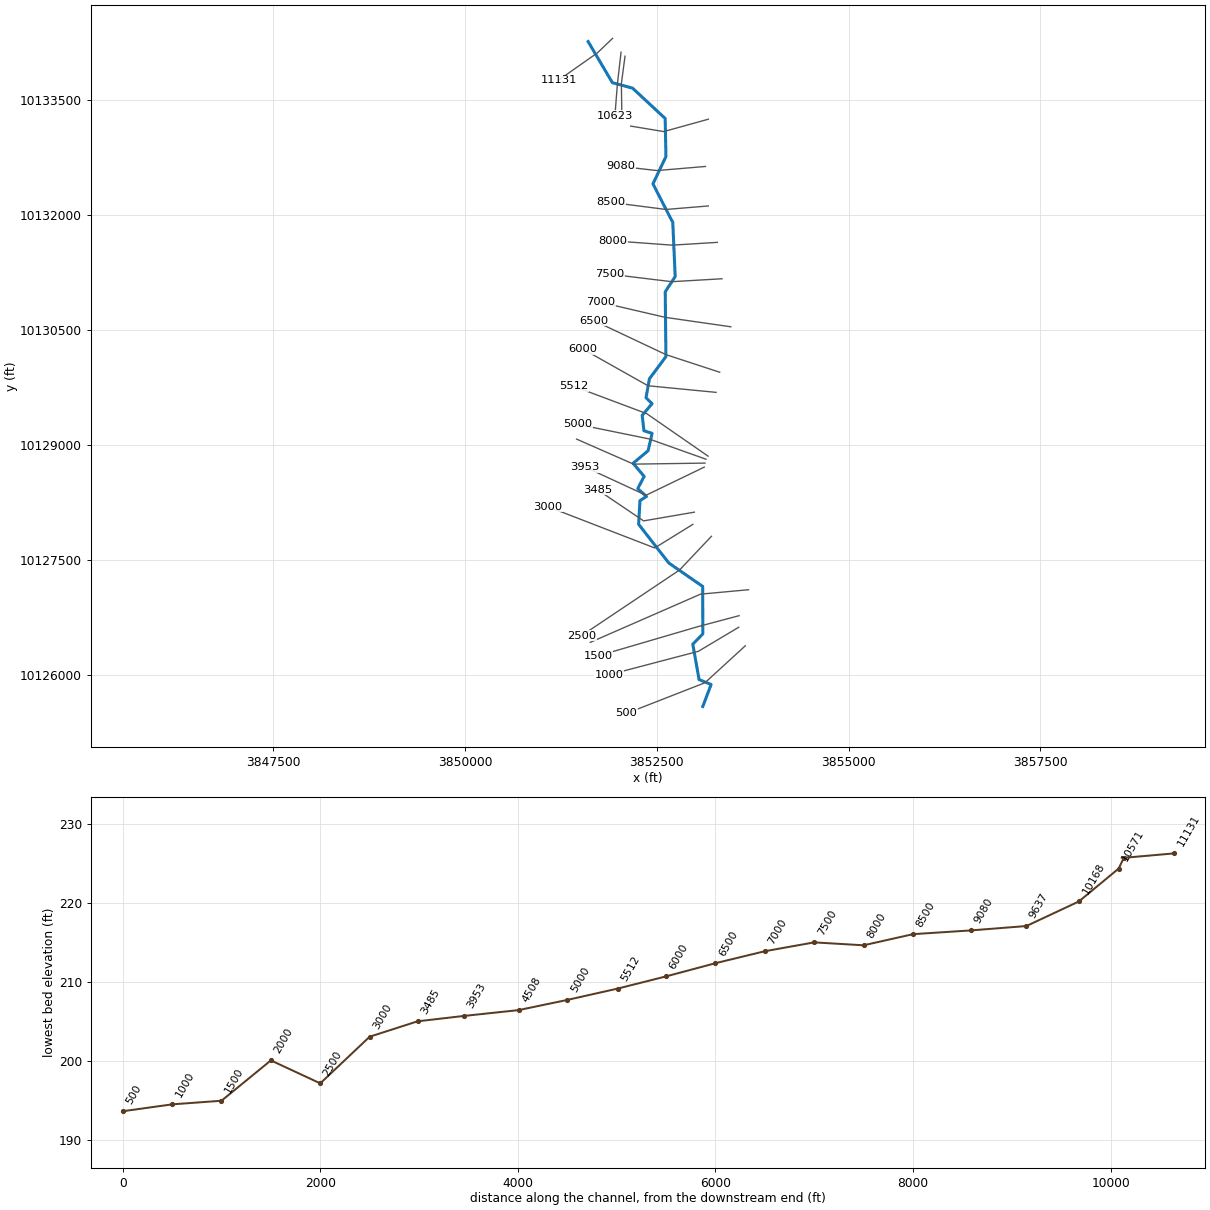
--- CRYSTAL CREEK TRIBUTARY NO 6.prj (project) ---

Proj Title=CRYSTAL CREEK TRIBUTARY NO 6 Base Level Engineering
Current Plan=p01
Default Exp/Contr=0.3,0.1
English Units
Geom File=g01
Flow File=f01
Plan File=p01
Y Axis Title=Elevation
X Axis Title(PF)=Main Channel Distance
X Axis Title(XS)=Station
BEGIN DESCRIPTION:
CRYSTAL CREEK TRIBUTARY NO 6
END DESCRIPTION:
DSS Export Rating Curves= 0
DSS Export Rating Curve Sorted= 0
DSS Export Volume Flow Curves= 0
DXF OffsetX= 0
DXF OffsetY= 0
DXF ScaleX= 1
DXF ScaleY= 10

--- CRYSTAL CREEK TRIBUTARY NO 6.p01 (plan) ---

Plan Title=Multiple Run
Short Identifier=Multiple
Geom File=g01
Flow File=f01
Subcritical Flow
K Sum by GR= 0
Std Step Tol= 0.01
Critical Tol= 0.01
Num of Std Step Trials= 20
Max Error Tol= 0.3
Flow Tol Ratio= 0.001
Split Flow NTrial= 30
Split Flow Tol= 0.02
Split Flow Ratio= 0.02
Log Output Level= 0
Friction Slope Method= 1
Unsteady Friction Slope Method= 2
Unsteady Bridges Friction Slope Method= 1
Parabolic Critical Depth
Global Vel Dist=  1 , 1 , 1
Global Log Level= 0
CheckData=True
Encroach Param= -1, 0, 0, 0
BEGIN DESCRIPTION:
Multiple Run
END DESCRIPTION:

--- CRYSTAL CREEK TRIBUTARY NO 6.f01 (steady flow) ---

Flow Title=Multiple
Program Version=4.10
Number of Profiles= 7
Profile Names=10-year,25-year,50-year,1pct_min,100-year,1pct_plu,500-year
River Rch & RM=CRYSTAL CREEK TR,Reach-1         ,11131
     551     733     981     432    1304    3938    2379
River Rch & RM=CRYSTAL CREEK TR,Reach-1         ,9637
    1166    1610    2203     990    2989    9027    5688
River Rch & RM=CRYSTAL CREEK TR,Reach-1         ,3000
    4081    5857    8226    3774   11396   34415   22625
River Rch & RM=CRYSTAL CREEK TR,Reach-1         ,2500
    4081    5857    8226    3774   11396   34415   22625
River Rch & RM=CRYSTAL CREEK TR,Reach-1         ,2000
    4081    5857    8226    3774   11396   34415   22625
River Rch & RM=CRYSTAL CREEK TR,Reach-1         ,1500
    4081    5857    8226    3774   11396   34415   22625
River Rch & RM=CRYSTAL CREEK TR,Reach-1         ,1000
    4081    5857    8226    3774   11396   34415   22625
River Rch & RM=CRYSTAL CREEK TR,Reach-1         ,500
    4081    5857    8226    3774   11396   34415   22625
Boundary for River Rch & Prof#=CRYSTAL CREEK TR,Reach-1         , 1
Up Type= 0
Dn Type= 3
Dn Slope=0.005
Boundary for River Rch & Prof#=CRYSTAL CREEK TR,Reach-1         , 2
Up Type= 0
Dn Type= 3
Dn Slope=0.005
Boundary for River Rch & Prof#=CRYSTAL CREEK TR,Reach-1         , 3
Up Type= 0
Dn Type= 3
Dn Slope=0.005
Boundary for River Rch & Prof#=CRYSTAL CREEK TR,Reach-1         , 4
Up Type= 0
Dn Type= 3
Dn Slope=0.005
Boundary for River Rch & Prof#=CRYSTAL CREEK TR,Reach-1         , 5
Up Type= 0
Dn Type= 3
Dn Slope=0.005
Boundary for River Rch & Prof#=CRYSTAL CREEK TR,Reach-1         , 6
Up Type= 0
Dn Type= 3
Dn Slope=0.005
Boundary for River Rch & Prof#=CRYSTAL CREEK TR,Reach-1         , 7
Up Type= 0
Dn Type= 3
Dn Slope=0.005
DSS Import GetInterval= 0
DSS Import GetPeak= 0
DSS Import FillOption= 0

--- CRYSTAL CREEK TRIBUTARY NO 6.g01 (geometry) ---

Geom Title=Existing Conditions
Program Version=4.10

River Reach=CRYSTAL CREEK TR,Reach-1
Reach XY= 30
      3851603.11     10134264.11      3851919.23     10133727.88
      3852182.66     10133656.46      3852607.66     10133260.78
      3852617.74     10132763.04      3852448.23     10132407.01
      3852707.01     10131903.46      3852738.25     10131197.13
      3852608.54     10130998.81      3852617.38      10130152.1
      3852402.19     10129863.91      3852358.01     10129615.88
       3852436.7     10129539.39      3852308.12     10129385.85
      3852330.85     10129185.85       3852437.4     10129151.24
      3852384.94     10128924.45      3852189.51     10128761.01
      3852333.42     10128590.08      3852249.51     10128430.15
      3852364.17     10128327.94      3852279.06     10128273.58
      3852261.55     10127964.64      3852654.99      10127459.4
      3853097.15     10127153.55      3853098.26     10126533.62
      3852967.75      10126400.2      3853049.92     10125937.63
      3853206.81     10125874.38      3853098.24     10125586.86

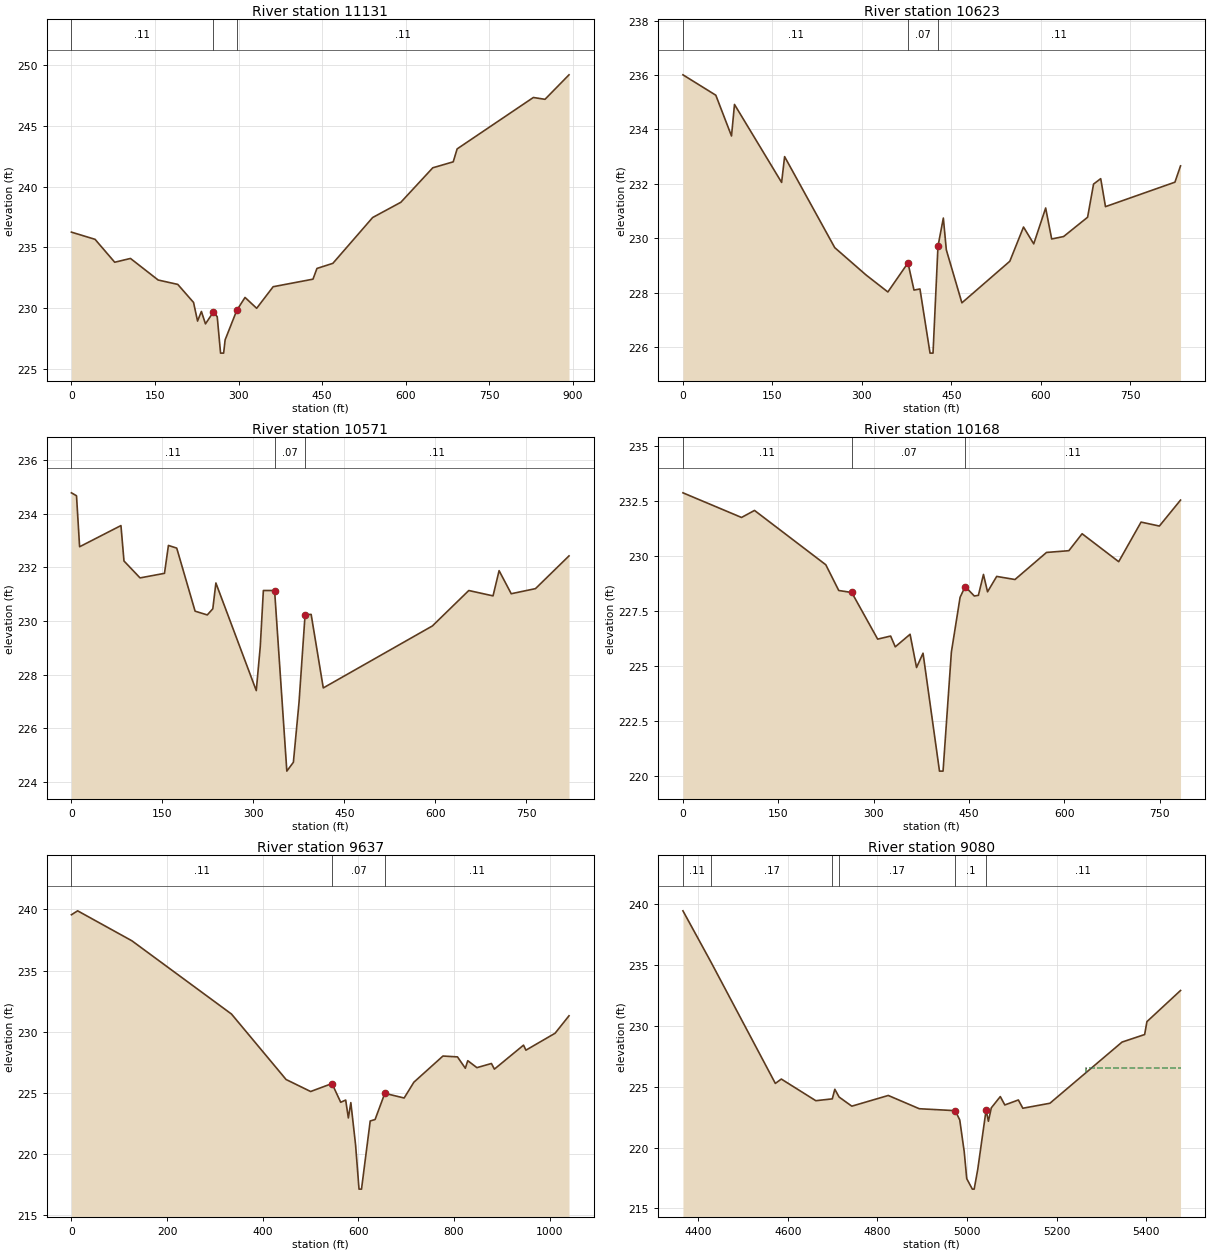
Type RM Length L Ch R = 1 ,11131   ,507,507,507
XS GIS Cut Line= 3
      3851922.34     10134306.53      3851724.88     10134117.76
      3851217.85     10133761.07
#Sta/Elev= 30
       0  236.26    42.4  235.67    77.7  233.79     106   234.1   155.7  232.33
   190.9  231.97   219.2  230.49   226.4  228.96   233.3  229.75   240.6  228.73
   254.7   229.7   261.7  229.32   267.7  226.33   273.2  226.33   275.9  227.42
   296.8  229.84   311.6   230.9   332.5  230.01   362.1  231.78   433.6   232.4
   440.7  233.28   469.3   233.7   540.7  237.46   591.3  238.71   648.6  241.54
   685.3  242.03   692.3  243.09   829.1  247.31     850  247.16   893.1  249.17
#Mann= 3 , 0 , 0
       0     .11       0   254.7     .07       0   296.8     .11       0
Bank Sta=254.7,296.8
XS Rating Curve= 0 ,0
Exp/Cntr=0.3,0.1

Type RM Length L Ch R = 1 ,10623   ,52,52,52
XS GIS Cut Line= 3
      3852032.27      10134125.8      3851984.76     10133712.59
      3851952.17      10133295.4
#Sta/Elev= 30
       0  236.01    55.1  235.26    81.4  233.76    86.4  234.92   165.4  232.05
   170.4     233   254.5  229.65   306.7  228.65   343.5  228.02   377.2  229.09
   387.3  228.09   397.3  228.13   414.2  225.77   419.2  225.77   427.5   229.7
   436.5  230.74   441.5  229.57   467.6  227.62   547.9  229.15   570.9  230.41
     588  229.79     608  231.11   618.1  229.97   638.1  230.06   678.3  230.77
   688.3  231.99   700.3  232.19   708.3  231.16   824.7  232.06   834.1  232.66
#Mann= 3 , 0 , 0
       0     .11       0   377.2     .07       0   427.5     .11       0
Bank Sta=377.2,427.5
XS Rating Curve= 0 ,0
Exp/Cntr=0.3,0.1

Type RM Length L Ch R = 1 ,10571   ,403,403,403
XS GIS Cut Line= 3
      3852084.11     10134073.27      3852036.44     10133714.56
       3852043.4     10133255.39
#Sta/Elev= 30
       0  234.78     8.4  234.67    13.5  232.77    81.7  233.56    86.7  232.24
   113.2  231.61   153.5  231.78     160  232.82   173.7  232.72     204  230.37
   224.1  230.23   233.2  230.46   238.3  231.42   304.9  227.41   311.5  229.06
   316.6  231.14   335.1  231.14   355.3  224.41   366.1  224.74   375.4  226.97
   385.4  230.24   395.4  230.25   415.4  227.51   595.4  229.82   655.4  231.14
   695.4  230.94   705.4  231.88   725.4  231.02   765.4  231.21   820.7  232.43
#Mann= 3 , 0 , 0
       0     .11       0   335.1     .07       0   385.4     .11       0
Bank Sta=335.1,385.4
XS Rating Curve= 0 ,0
Exp/Cntr=0.3,0.1

Type RM Length L Ch R = 1 ,10168   ,531,531,531
#Sta/Elev= 30
       0  232.89    92.2  231.77   112.6  232.09   224.8  229.62   245.2  228.45
   265.6  228.36   306.4  226.24   326.8  226.38   334.1  225.89   357.4  226.46
   367.6  224.95   377.8   225.6   403.7  220.24   409.3  220.24   422.4  225.65
   436.1  228.14   444.1  228.63   458.5   228.2   464.9  228.23   472.9  229.18
   479.3  228.39   493.7  229.09   522.5  228.95   572.1  230.18   607.3  230.26
   628.1  231.03   685.7  229.76   720.9  231.56   749.7  231.38     783  232.56
#Mann= 3 , 0 , 0
       0     .11       0   265.6     .07       0   444.1     .11       0
Bank Sta=265.6,444.1
XS Rating Curve= 0 ,0
Exp/Cntr=0.3,0.1

Type RM Length L Ch R = 1 ,9637    ,557,557,557
XS GIS Cut Line= 3
      3853170.42     10133251.08       3852588.9     10133089.69
      3852157.82     10133161.51
#Sta/Elev= 30
       0  239.56      13  239.88   126.5  237.43   334.8  231.44   448.9  226.09
   500.2  225.11   544.9  225.76   563.1  224.23   573.5  224.41   579.1  222.95
   584.3   224.2   594.2  220.75   601.4  217.13   606.6  217.13   624.8   222.7
     635  222.82   655.3  224.96   695.8  224.58   716.1  225.87   776.9  228.01
   807.3  227.94   823.7  227.01   828.8  227.63   847.9  227.06   878.3   227.4
   884.5  226.94   945.4   228.9   950.4  228.49  1011.3  229.87  1040.5   231.3
#Mann= 3 , 0 , 0
       0     .11       0   544.9     .07       0   655.3     .11       0
Bank Sta=544.9,655.3
XS Rating Curve= 0 ,0
Exp/Cntr=0.3,0.1

Type RM Length L Ch R = 1 ,9080    ,591,591,591
BEGIN DESCRIPTION:
CRYSTAL CREEK TRIBUTARY NO 6 18.0
END DESCRIPTION:
XS GIS Cut Line= 3
      3853133.33      10132634.5       3852501.7     10132580.88
      3852028.23      10132634.5
#Sta/Elev= 30
  4366.1  239.46  4428.9  235.23  4572.3  225.27  4585.6  225.63  4662.6  223.85
  4699.4     224    4705  224.79  4714.6  224.15  4742.9   223.4  4824.3  224.28
  4893.5  223.19  4973.8  223.03  4983.8  222.27  4993.8  219.65  4999.4  217.44
  5011.9  216.58    5016  216.58    5024  218.21  5042.6  223.09  5047.7  222.16
  5054.2  223.26  5074.3  224.19  5084.4   223.5  5114.6  223.91  5124.6  223.23
    5185  223.64    5346  228.67  5396.4  229.29  5401.5  230.35  5476.5  232.91
#Mann= 6 ,-1 , 0
  4366.1     .11       0  4428.9     .17       0  4699.4     .12       0
  4714.6     .17       0  4973.8      .1       0  5042.6     .11       0
#XS Ineff= 2 , 0
       0  4585.6  225.63  5265.5       0   226.5
Permanent Ineff=
       F       F
Bank Sta=4973.8,5042.6
XS Rating Curve= 0 ,0
Exp/Cntr=0.3,0.1

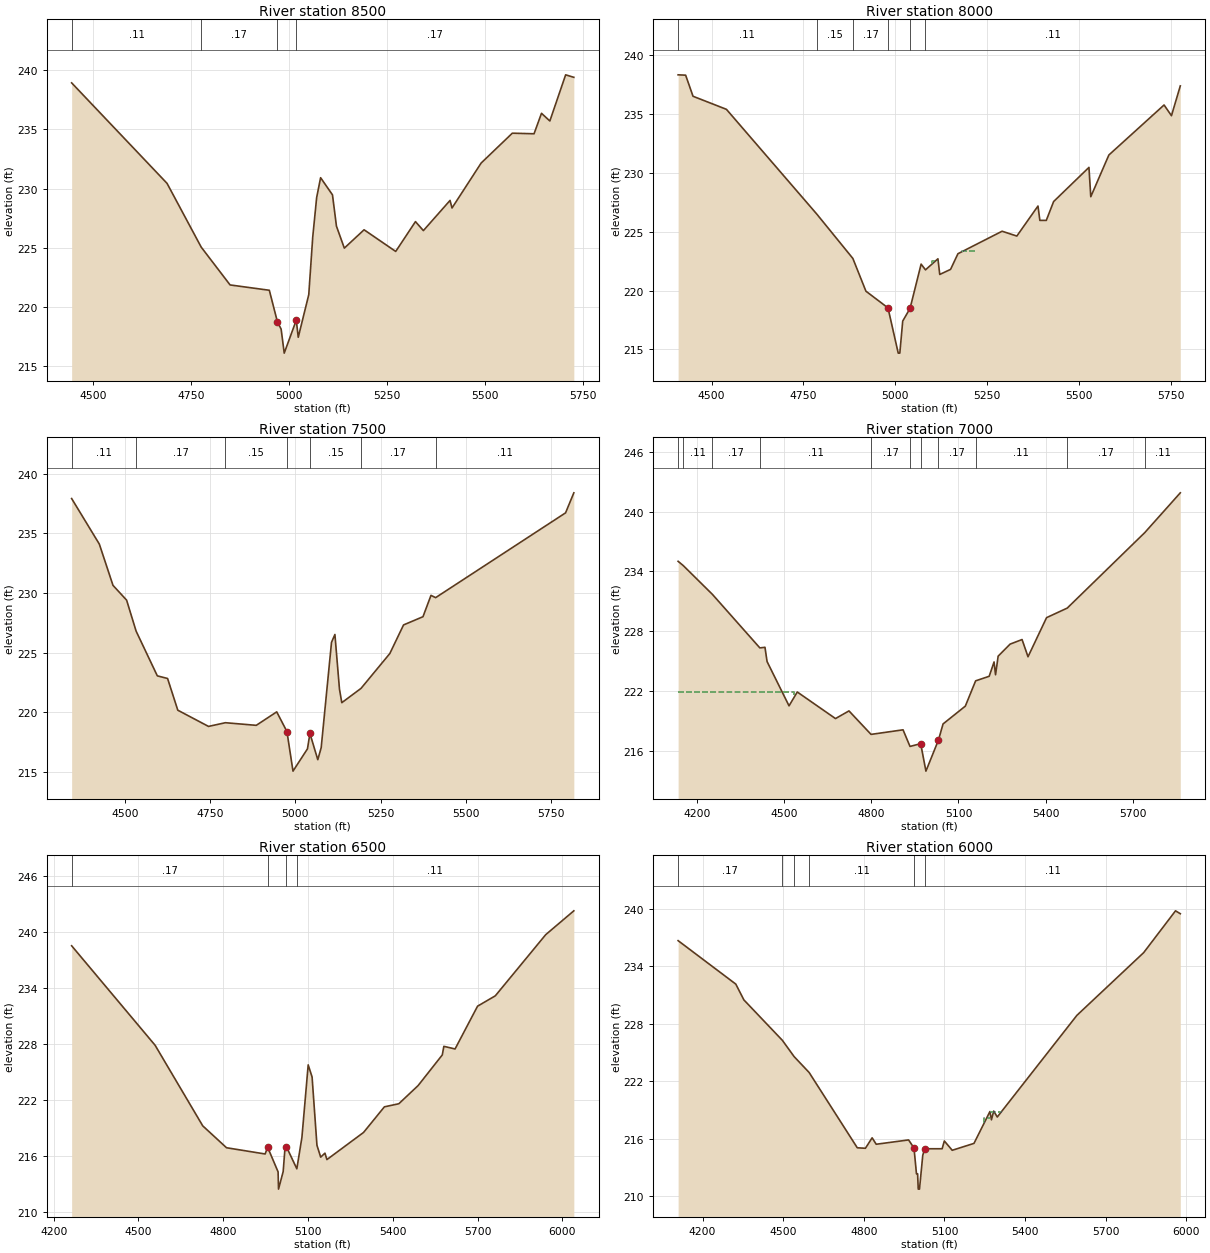
Type RM Length L Ch R = 1 ,8500    ,500,500,500
BEGIN DESCRIPTION:
CRYSTAL CREEK TRIBUTARY NO 6 17.0
END DESCRIPTION:
XS GIS Cut Line= 3
      3853170.42     10132118.99      3852617.71     10132073.27
      3851897.17     10132166.12
#Sta/Elev= 30
  4445.4  238.93  4688.8  230.44    4776  225.05  4849.6  221.86  4949.7  221.41
  4970.4  218.73  4979.8  218.13  4987.7   216.1  5018.4  218.88  5023.5  217.44
  5050.3  221.04  5060.4   225.9  5070.4  229.24  5080.5  230.92  5110.8  229.47
  5120.9  226.83    5141  224.97  5191.4  226.52  5272.1  224.69  5322.5  227.21
  5342.7  226.45  5410.7     229  5415.7  228.36  5490.1  232.16  5569.6  234.68
    5625  234.63    5644  236.36  5665.3  235.71  5705.6  239.61  5726.5   239.4
#Mann= 4 ,-1 , 0
  4445.4     .11       0    4776     .17       0  4970.4      .1       0
  5018.4     .17       0
#XS Ineff= 2 , 0
       0                  5080.5       0  230.92
Permanent Ineff=
       F       F
Bank Sta=4970.4,5018.4
XS Rating Curve= 0 ,0
Exp/Cntr=0.3,0.1

Type RM Length L Ch R = 1 ,8000    ,500,500,500
BEGIN DESCRIPTION:
CRYSTAL CREEK TRIBUTARY NO 6 16.0
END DESCRIPTION:
XS GIS Cut Line= 3
      3853288.33     10131643.92      3852698.25     10131607.54
      3851923.82     10131664.13
#Sta/Elev= 30
  4408.8  238.32  4429.3  238.29  4449.4   236.5  4540.4  235.39  4786.1  226.51
  4884.7  222.73  4920.3  219.95  4980.4  218.53  5008.3  214.69  5012.6  214.69
  5020.5  217.41  5040.5  218.49  5070.6  222.25  5082.5  221.76  5116.4   222.7
  5121.4  221.37  5150.8   221.8  5170.9  223.13  5291.2  225.04  5331.3  224.63
  5388.9  227.18    5394  225.96  5411.5  225.96  5431.5  227.56  5527.7  230.46
  5532.7  227.97  5581.9  231.51  5732.3  235.76  5752.4  234.85  5776.5  237.38
#Mann= 6 ,-1 , 0
  4408.8     .11       0  4786.1     .15       0  4884.7     .17       0
  4980.4     .07       0  5040.5     .17       0  5082.5     .11       0
#XS Ineff= 3 ,-1
  5100.7  5116.4  222.48  5116.4  5180.9   222.7  5180.9    5221  223.32
Permanent Ineff=
       F       F       F
Bank Sta=4980.4,5040.5
XS Rating Curve= 0 ,0
Exp/Cntr=0.3,0.1

Type RM Length L Ch R = 1 ,7500    ,500,500,500
BEGIN DESCRIPTION:
CRYSTAL CREEK TRIBUTARY NO 6 15.0
END DESCRIPTION:
XS GIS Cut Line= 3
      3853349.03     10131168.85      3852693.14     10131130.66
      3851881.41     10131229.32
#Sta/Elev= 30
    4343  237.92  4424.3   234.1  4464.4  230.64  4504.4   229.4  4532.3   226.8
  4594.6  223.05  4624.7  222.83  4654.7  220.17  4744.9  218.81  4794.5  219.12
  4885.1   218.9  4945.2  220.03  4975.2  218.38    4993  215.06  5035.5  216.93
  5042.7  218.22  5065.8  216.02  5075.8  217.03  5106.1  225.86  5116.1  226.52
  5129.5  221.93  5136.3   220.8  5192.8     222  5277.3  224.92  5317.6  227.32
  5374.7  228.01  5398.2   229.8  5411.9  229.61  5793.4  236.72  5817.7   238.4
#Mann= 7 ,-1 , 0
    4343     .11       0  4532.3     .17       0  4794.5     .15       0
  4975.2     .07       0  5042.7     .15       0  5192.8     .17       0
  5411.9     .11       0
#XS Ineff= 2 , 0
       0                  5116.1       0  226.52
Permanent Ineff=
       F       F
Bank Sta=4975.2,5042.7
XS Rating Curve= 0 ,0
Exp/Cntr=0.3,0.1

Type RM Length L Ch R = 1 ,7000    ,500,500,500
BEGIN DESCRIPTION:
CRYSTAL CREEK TRIBUTARY NO 6 14.0
END DESCRIPTION:
XS GIS Cut Line= 3
       3853463.5     10130542.16      3852608.12     10130665.35
      3851767.82     10130861.08
#Sta/Elev= 30
  4135.8  235.02  4153.5  234.59  4253.7   231.7  4416.9  226.32  4434.5  226.38
  4441.7  224.95  4517.2   220.5  4545.6  221.89    4677  219.22  4723.4  219.99
  4799.3  217.63  4909.3  218.09  4933.3  216.42    4970   216.7    4988  213.94
  5031.1  217.06  5046.9  218.68  5123.5  220.47  5158.9  223.01  5205.6  223.47
  5222.3  224.91  5227.4  223.62  5236.4  225.49  5277.5   226.7  5318.6  227.16
  5339.1  225.43  5402.9  229.36    5474  230.32  5740.5   237.9  5862.8   241.9
#Mann= 11 ,-1 , 0
  4135.8     .17       0  4153.5     .11       0  4253.7     .17       0
  4416.9     .11       0  4799.3     .17       0  4933.3     .11       0
    4970     .07       0  5031.1     .17       0  5158.9     .11       0
    5474     .17       0  5740.5     .11       0
#XS Ineff= 2 , 0
       0  4535.5  221.92               0
Permanent Ineff=
       F       F
Bank Sta=4970,5031.1
XS Rating Curve= 0 ,0
Exp/Cntr=0.3,0.1

Type RM Length L Ch R = 1 ,6500    ,500,500,500
BEGIN DESCRIPTION:
CRYSTAL CREEK TRIBUTARY NO 6 13.0
END DESCRIPTION:
XS GIS Cut Line= 3
      3853318.68     10129949.16      3852618.76      10130178.4
      3851677.82     10130623.02
#Sta/Elev= 30
  4263.5  238.53    4559  227.85  4727.4  219.21  4811.6  216.86  4948.3  216.19
    4957  216.92  4994.1  214.27  4995.6  212.42  5012.1  214.31  5017.8  216.55
  5023.3  216.99  5060.4   214.6  5078.4  217.97  5100.6  225.75  5114.4  224.45
  5131.6  217.13  5144.8  215.85  5159.9  216.28  5166.9  215.59  5296.5   218.5
  5370.3  221.25  5421.3  221.58  5489.6  223.53  5575.2  226.82  5580.7  227.74
  5620.4  227.46    5700  232.05  5762.8  233.16  5941.1  239.72  6040.7  242.28
#Mann= 4 ,-1 , 0
  4263.5     .17       0    4957     .07       0  5023.3     .17       0
  5060.4     .11       0
#XS Ineff= 2 , 0
       0                  5100.6       0  225.75
Permanent Ineff=
       F       F
Bank Sta=4957,5023.3
XS Rating Curve= 0 ,0
Exp/Cntr=0.3,0.1

Type RM Length L Ch R = 1 ,6000    ,488,488,488
BEGIN DESCRIPTION:
CRYSTAL CREEK TRIBUTARY NO 6 12.0
END DESCRIPTION:
XS GIS Cut Line= 3
      3853271.47     10129686.36      3852384.53     10129772.43
      3851532.97     10130252.37
#Sta/Elev= 30
  4108.9  236.66  4323.5  232.13  4353.7  230.48    4497  226.26  4540.5  224.57
  4596.5  222.91  4775.6  215.06  4805.8  215.01  4830.8   216.1    4846  215.43
  4966.5  215.88  4986.6  215.04  4995.8  212.35    5000  212.35  5002.4  210.75
    5007  210.75  5019.2  214.27  5026.3  214.96  5091.3  214.96  5099.5  215.77
  5128.9   214.8  5209.8  215.52  5269.1  218.84  5274.8  217.98  5283.2  218.89
  5296.5  218.27  5592.7  228.87  5841.2  235.41  5959.7  239.77  5977.5  239.47
#Mann= 6 ,-1 , 0
  4108.9     .17       0    4497     .11       0  4540.5     .17       0
  4596.5     .11       0  4986.6     .07       0  5026.3     .11       0
#XS Ineff= 2 ,-1
  5247.4  5269.1  218.16  5269.1  5312.4  218.84
Permanent Ineff=
       F       F
Bank Sta=4986.6,5026.3
XS Rating Curve= 0 ,0
Exp/Cntr=0.3,0.1

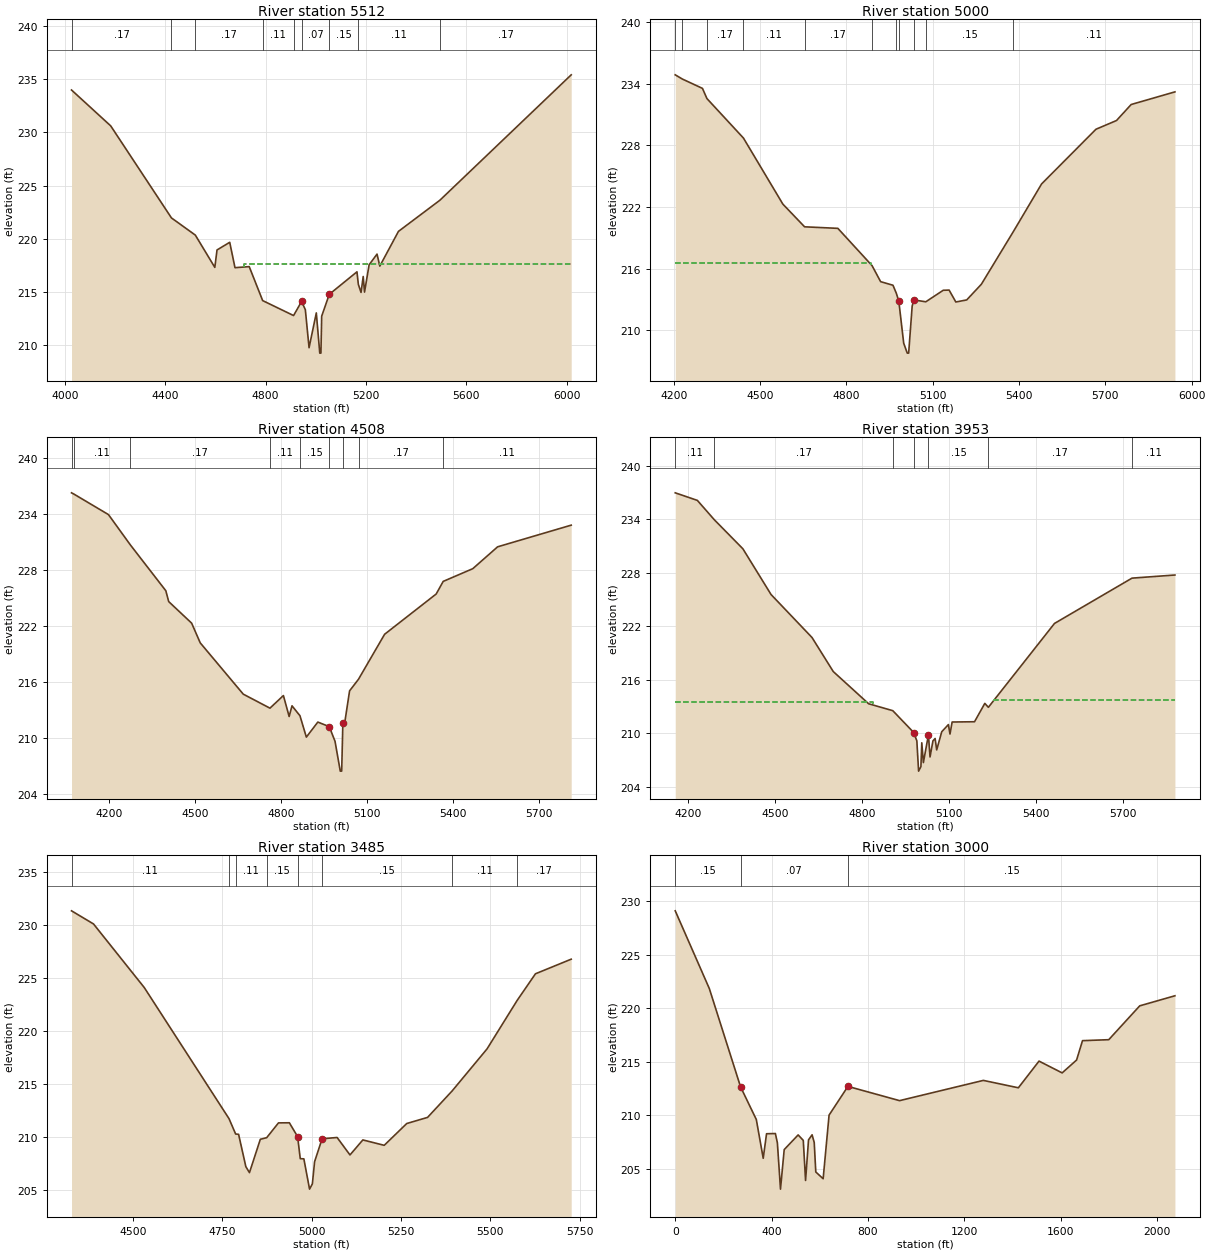
Type RM Length L Ch R = 1 ,5512    ,512,512,512
BEGIN DESCRIPTION:
CRYSTAL CREEK TRIBUTARY NO 6 11.0
END DESCRIPTION:
XS GIS Cut Line= 3
      3853167.01     10128854.16      3852366.65     10129408.52
      3851413.74     10129766.43
#Sta/Elev= 30
  4026.4     234  4182.6  230.62  4424.6  221.95  4519.8  220.33  4597.5  217.29
  4606.3  218.93  4656.9  219.65  4677.9  217.26  4734.6  217.36  4788.2  214.16
  4911.4  212.75  4943.4  214.08  4958.3   213.3  4973.1  209.72    5002     213
  5015.8  209.21  5020.4  209.21  5023.4  212.69  5053.7  214.75    5164  216.87
  5169.5  215.69  5180.3  214.93  5188.9  216.43  5194.2  214.96  5212.4  217.53
    5244  218.54  5255.1  217.41  5329.4  220.68  5494.3  223.61  6017.9  235.43
#Mann= 9 ,-1 , 0
  4026.4     .17       0  4424.6     .11       0  4519.8     .17       0
  4788.2     .11       0  4911.4     .15       0  4943.4     .07       0
  5053.7     .15       0  5169.5     .11       0  5494.3     .17       0
#XS Ineff= 3 ,-1
  4713.7  4656.9  217.61  4656.9  4540.7  219.65    5244  5287.1  218.54
Permanent Ineff=
       F       F       F
Bank Sta=4943.4,5053.7
XS Rating Curve= 0 ,0
Exp/Cntr=0.3,0.1

Type RM Length L Ch R = 1 ,5000    ,492,492,492
BEGIN DESCRIPTION:
CRYSTAL CREEK TRIBUTARY NO 6 10.0
END DESCRIPTION:
XS GIS Cut Line= 3
      3853140.13     10128813.69      3852391.86     10129080.43
      3851468.93     10129268.55
#Sta/Elev= 30
  4205.6  234.87  4230.3  234.46  4300.2  233.55  4315.7  232.56  4442.7  228.71
  4579.6  222.28  4655.1  220.07  4770.7  219.92  4889.5  216.29  4919.3  214.73
  4962.2  214.38  4973.7  213.61  4982.4  212.84  4999.5  208.73  5011.9  207.77
  5016.7  207.77  5028.9  212.35  5034.7  212.95  5076.3  212.77  5136.8  213.89
  5157.2  213.91  5180.6  212.75  5218.4  212.95  5269.4  214.48  5380.8  219.62
  5478.7  224.25  5667.5  229.57  5738.9  230.42  5789.9  231.98  5941.9  233.21
#Mann= 11 ,-1 , 0
  4205.6     .17       0  4230.3     .11       0  4315.7     .17       0
  4442.7     .11       0  4655.1     .17       0  4889.5     .11       0
  4973.7     .17       0  4982.4     .07       0  5034.7     .17       0
  5076.3     .15       0  5380.8     .11       0
#XS Ineff= 2 , 0
       0  4887.5  216.54               0
Permanent Ineff=
       F       F
Bank Sta=4982.4,5034.7
XS Rating Curve= 0 ,0
Exp/Cntr=0.3,0.1

Type RM Length L Ch R = 1 ,4508    ,555,555,555
BEGIN DESCRIPTION:
CRYSTAL CREEK TRIBUTARY NO 6 9.0
END DESCRIPTION:
XS GIS Cut Line= 3
      3853126.59     10128763.16      3852195.19     10128749.72
      3851452.98     10129076.11
#Sta/Elev= 30
  4068.5  236.27    4076  236.15  4197.3  233.94  4273.3  230.71  4397.3  225.79
  4407.3  224.63  4487.3  222.32  4517.3  220.21  4667.3  214.72  4760.4  213.22
  4807.3  214.57  4827.3  212.33  4837.3  213.47    4865  212.41  4887.3  210.12
  4927.3  211.73  4967.3  211.24  4987.3  209.67  5005.6  206.48  5010.5  206.48
  5014.6  211.63  5020.1  211.46    5038  215.07  5069.2  216.32  5160.2  221.13
    5340  225.44  5364.5  226.79  5467.6  228.15  5554.2  230.49  5810.8  232.81
#Mann= 9 ,-1 , 0
  4068.5     .17       0    4076     .11       0  4273.3     .17       0
  4760.4     .11       0    4865     .15       0  4967.3     .07       0
  5014.6     .15       0  5069.2     .17       0  5364.5     .11       0
Bank Sta=4967.3,5014.6
XS Rating Curve= 0 ,0
Exp/Cntr=0.3,0.1

Type RM Length L Ch R = 1 ,3953    ,468,468,468
BEGIN DESCRIPTION:
CRYSTAL CREEK TRIBUTARY NO 6 8.0
END DESCRIPTION:
XS GIS Cut Line= 3
      3853117.82     10128711.06      3852358.14     10128343.55
      3851561.07     10128712.68
#Sta/Elev= 30
  4156.1  236.96  4232.4  236.11  4290.5  233.95  4389.3  230.68  4486.4  225.55
  4627.5  220.73  4700.8  216.91  4822.6   213.3    4906  212.52  4978.1  210.07
  4988.9  209.13  4994.9  205.74  5002.9  206.24  5005.9  208.92  5011.4   206.7
  5028.8  209.81  5034.3  207.33  5044.4  209.14  5051.8   209.4  5057.3  208.12
  5074.7  210.16  5097.6  210.96  5103.1   209.9  5110.5  211.25  5187.7  211.28
  5223.2  213.34  5235.4   212.9  5463.4  222.31  5730.5  227.39  5878.4  227.74
#Mann= 7 ,-1 , 0
  4156.1     .11       0  4290.5     .17       0    4906     .15       0
  4978.1     .07       0  5028.8     .15       0  5235.4     .17       0
  5730.5     .11       0
#XS Ineff= 2 , 0
       0  4836.4  213.55  5253.8       0  213.72
Permanent Ineff=
       F       F
Bank Sta=4978.1,5028.8
XS Rating Curve= 0 ,0
Exp/Cntr=0.3,0.1

Type RM Length L Ch R = 1 ,3485    ,485,485,485
BEGIN DESCRIPTION:
CRYSTAL CREEK TRIBUTARY NO 6 7.0
END DESCRIPTION:
XS GIS Cut Line= 3
      3852988.44     10128122.99      3852326.77     10128009.07
      3851725.01     10128416.11
#Sta/Elev= 30
  4328.6  231.36  4390.1  230.12  4532.1  224.11  4769.2  211.72  4787.7  210.27
    4796  210.24  4816.3  207.18  4826.4  206.62  4856.8  209.77  4874.5  209.92
  4907.6  211.32    4938  211.33  4961.1  210.02  4968.5  207.94  4978.6  207.92
  4994.5  205.06  5002.4  205.56  5008.6  207.65  5029.6  209.82  5071.6  209.94
  5107.6  208.29  5143.6  209.71  5203.4   209.2  5266.4  211.26  5324.7  211.84
  5393.4  214.34    5491  218.31  5575.6  222.91  5626.5  225.41  5726.5  226.79
#Mann= 8 ,-1 , 0
  4328.6     .11       0  4769.2     .17       0  4787.7     .11       0
  4874.5     .15       0  4961.1     .07       0  5029.6     .15       0
  5393.4     .11       0  5575.6     .17       0
Bank Sta=4961.1,5029.6
XS Rating Curve= 0 ,0
Exp/Cntr=0.3,0.1

Type RM Length L Ch R = 1 ,3000    ,500,500,500
XS GIS Cut Line= 3
      3852968.47     10127963.56      3852471.23     10127655.88
      3851080.45      10128193.6
#Sta/Elev= 30
       0  229.09   141.6  221.83   271.2  212.66   336.6  209.61   365.3  205.99
   379.1  208.28   415.8   208.3   424.1  207.43     437  203.11   452.4   206.8
   510.3  208.17   531.6  207.66   541.1  203.92   553.4  207.71   568.2  208.18
     577  207.47   583.6  204.71   614.1  204.08   638.7  210.02     717   212.7
   931.4  211.37  1279.2  213.26  1424.6  212.57  1510.4  215.06  1606.4  213.96
  1666.3  215.16  1690.9  216.97  1799.9  217.06  1928.5  220.22  2074.6  221.16
#Mann= 3 , 0 , 0
       0     .15       0   271.2     .07       0     717     .15       0
Bank Sta=271.2,717
XS Rating Curve= 0 ,0
Exp/Cntr=0.3,0.1

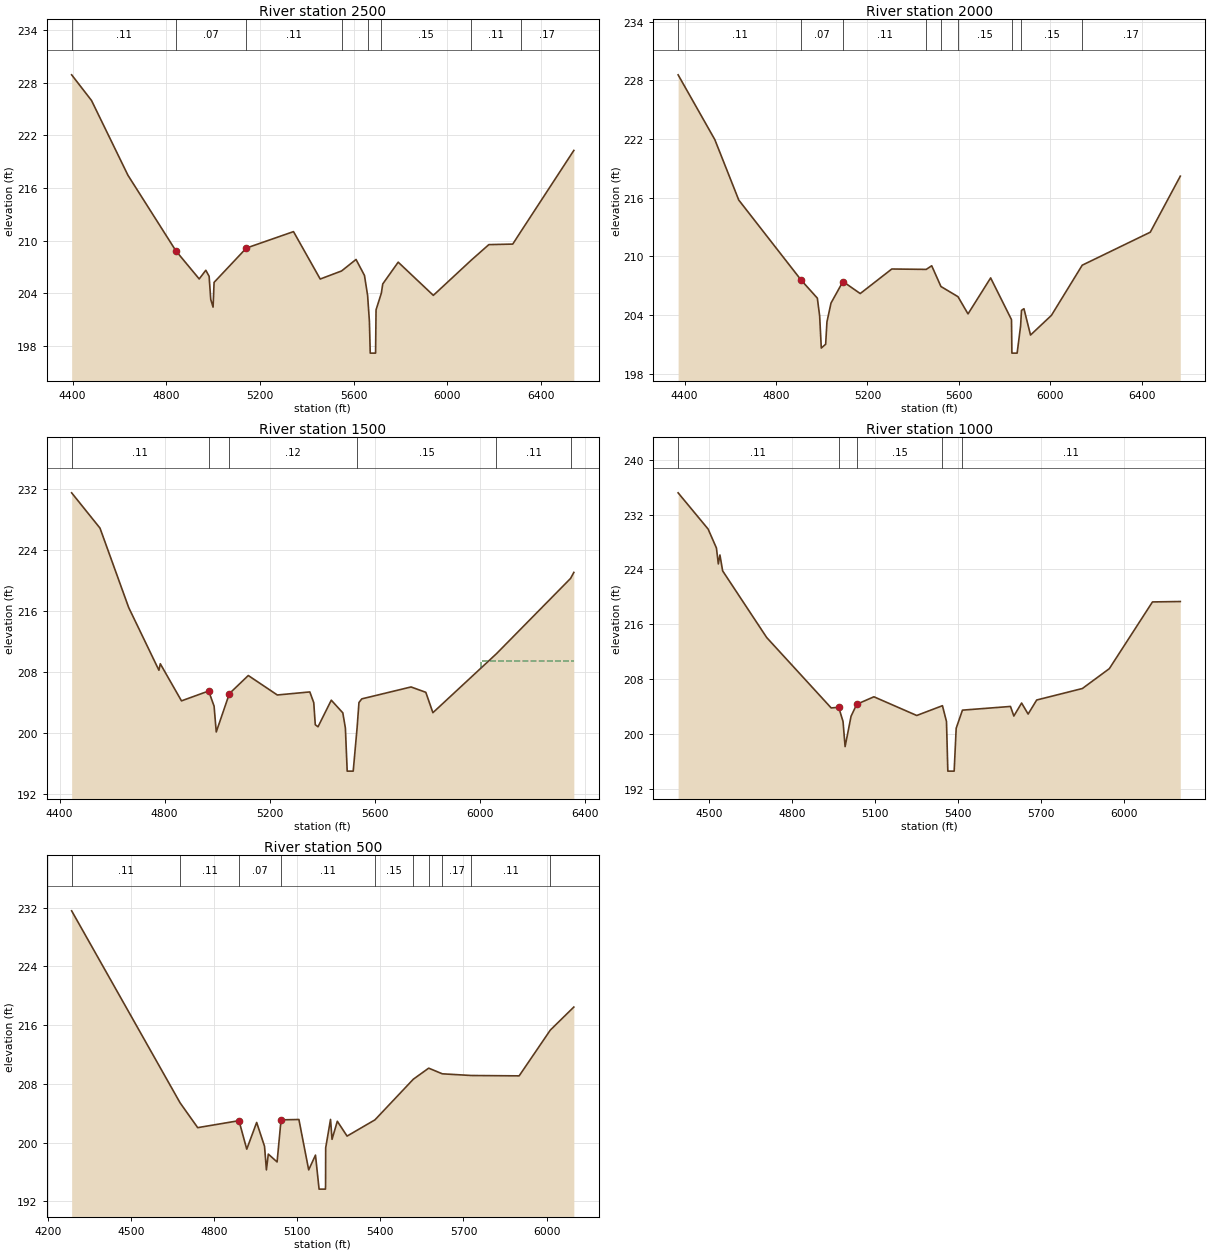
Type RM Length L Ch R = 1 ,2500    ,500,500,500
BEGIN DESCRIPTION:
CRYSTAL CREEK TRIBUTARY NO 6 5.0
END DESCRIPTION:
XS GIS Cut Line= 3
      3853210.84     10127807.95      3852796.05     10127368.76
       3851516.1     10126510.79
#Sta/Elev= 30
  4395.9   228.9  4480.7  225.98  4636.4  217.46  4841.5  208.84  4940.7  205.65
    4969  206.64  4983.1  205.95    4990  203.32    5000  202.44  5004.3  205.26
  5142.3  209.17  5343.5  211.04  5457.6  205.64  5548.9  206.56  5610.6  207.87
  5646.6  206.05    5660  203.78  5667.7  200.83  5671.3   197.2  5694.1   197.2
  5696.1  202.13  5718.7  204.03  5724.7  205.08  5790.7  207.56  5940.8  203.78
  6102.8  207.79  6177.9  209.56    6280  209.62  6314.2  211.03  6540.9  220.29
#Mann= 8 ,-1 , 0
  4395.9     .11       0  4841.5     .07       0  5142.3     .11       0
  5548.9     .15       0    5660     .12       0  5718.7     .15       0
  6102.8     .11       0  6314.2     .17       0
Bank Sta=4841.5,5142.3
XS Rating Curve= 0 ,0
Exp/Cntr=0.3,0.1

Type RM Length L Ch R = 1 ,2000    ,500,500,500
BEGIN DESCRIPTION:
CRYSTAL CREEK TRIBUTARY NO 6 4.0
END DESCRIPTION:
XS GIS Cut Line= 3
       3853694.6     10127110.73      3853068.57     10127052.86
      3851631.13     10126423.95
#Sta/Elev= 30
  4371.3  228.56  4532.1  221.93  4636.7  215.76  4910.3  207.56  4980.6  205.73
  4990.7  203.91  4997.9  200.63    5017  201.02  5022.6   203.3  5040.4  205.23
  5092.7  207.43  5168.3   206.2  5306.4  208.71  5457.1  208.67  5481.1  209.04
  5521.5  206.92  5596.1  205.88    5640  204.12    5739   207.8  5830.3  203.53
    5832  200.11  5854.9  200.11 5870.09202.8884    5874  204.48  5884.8  204.65
  5913.6  201.96    6005  203.97  6139.8   209.1  6437.5  212.47    6569   218.2
#Mann= 9 ,-1 , 0
  4371.3     .11       0  4910.3     .07       0  5092.7     .11       0
  5457.1     .15       0  5521.5     .11       0  5596.1     .15       0
    5832     .12       0 5870.09     .15       0  6139.8     .17       0
Bank Sta=4910.3,5092.7
XS Rating Curve= 0 ,0
Exp/Cntr=0.3,0.1

Type RM Length L Ch R = 1 ,1500    ,500,500,500
BEGIN DESCRIPTION:
CRYSTAL CREEK TRIBUTARY NO 6 3.0
END DESCRIPTION:
XS GIS Cut Line= 3
      3853572.19     10126772.18      3853036.96     10126629.59
      3851732.69     10126247.08
#Sta/Elev= 30
  4446.1  231.44  4554.1  226.82  4663.4  216.42  4778.6  208.21  4783.8  209.06
  4864.5   204.2    4968  205.49  4988.7  203.51    4997  200.13    5047  205.15
    5119  207.52  5229.6  204.97  5353.4  205.37  5368.4  203.97  5374.2  201.07
  5384.7  200.81  5435.2  204.29  5479.1  202.63  5488.9  200.64  5495.8     195
  5518.7     195 5533.49200.6574  5540.6  203.98  5551.4  204.46    5739  206.02
  5795.3  205.32  5822.3  202.65  6064.3  210.37  6346.7  220.23  6359.2  221.02
#Mann= 6 ,-1 , 0
  4446.1     .11       0    4968     .07       0    5047     .12       0
 5533.49     .15       0  6064.3     .11       0  6346.7     .17       0
#XS Ineff= 2 , 0
       0  4783.8  209.06  6006.1       0  209.38
Permanent Ineff=
       F       F
Bank Sta=4968,5047
XS Rating Curve= 0 ,0
Exp/Cntr=0.3,0.1

Type RM Length L Ch R = 1 ,1000    ,500,500,500
BEGIN DESCRIPTION:
CRYSTAL CREEK TRIBUTARY NO 6 2.0
END DESCRIPTION:
XS GIS Cut Line= 3
      3853567.02     10126621.16      3853040.62     10126307.06
      3851874.95     10126000.52
#Sta/Elev= 30
    4387   235.2  4495.6  229.91  4525.8  227.13  4532.6  224.81  4538.4  226.12
  4548.2   223.8  4707.7  214.06  4941.3  203.77  4968.5  203.87  4984.1  201.79
  4991.6  198.12  5013.2  202.56  5033.9  204.31  5095.9   205.4    5251  202.67
  5344.1   204.1  5358.7  201.78  5363.6  194.54  5386.5  194.54  5393.8   200.8
  5416.5  203.45  5590.4  203.99  5602.6  202.59  5630.7  204.49  5654.3  202.88
  5685.3  204.93  5850.7  206.61  5948.3  209.51  6104.5  219.26  6205.3  219.32
#Mann= 5 ,-1 , 0
    4387     .11       0  4968.5     .07       0  5033.9     .15       0
  5344.1     .12       0  5416.5     .11       0
Bank Sta=4968.5,5033.9
XS Rating Curve= 0 ,0
Exp/Cntr=0.3,0.1

Type RM Length L Ch R = 1 ,500     ,0,0,0
BEGIN DESCRIPTION:
CRYSTAL CREEK TRIBUTARY NO 6 1.0
END DESCRIPTION:
XS GIS Cut Line= 3
      3853652.73       10126379.      3853126.93     10125896.85
      3852104.09     10125497.04
#Sta/Elev= 30
  4286.6  231.56  4677.8  205.42  4741.3  202.04  4890.2  202.99  4918.3  199.11
    4954  202.75  4982.4   199.5  4989.2  196.29    4996  198.44  5027.7  197.37
    5042   203.1  5106.4  203.15  5141.7  196.29  5166.2   198.3  5179.2  193.67
  5202.1  193.67  5202.6  194.17    5203  199.29  5220.5  203.16  5225.9  200.45
    5245  202.91  5280.2  200.89  5380.7   203.1  5519.3  208.64  5574.6  210.14
  5623.7  209.37  5728.1  209.14  5900.9  209.09  6013.5  215.33  6098.2  218.46
#Mann= 10 ,-1 , 0
  4286.6     .11       0  4677.8     .11       0  4890.2     .07       0
    5042     .11       0  5380.7     .15       0  5519.3     .17       0
  5574.6     .11       0  5623.7     .17       0  5728.1     .11       0
  6013.5     .17       0
Bank Sta=4890.2,5042
XS Rating Curve= 0 ,0
Exp/Cntr=0.3,0.1

Chan Stop Cuts=-1
Use User Specified Reach Order=0
Composite Channel Slope=5

--- CRYSTAL CREEK TRIBUTARY NO 6.g10 (geometry) ---

Geom Title=Existing Conditions
Program Version=4.10

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
River Reach=CRYSTAL CREEK TR,Reach-1

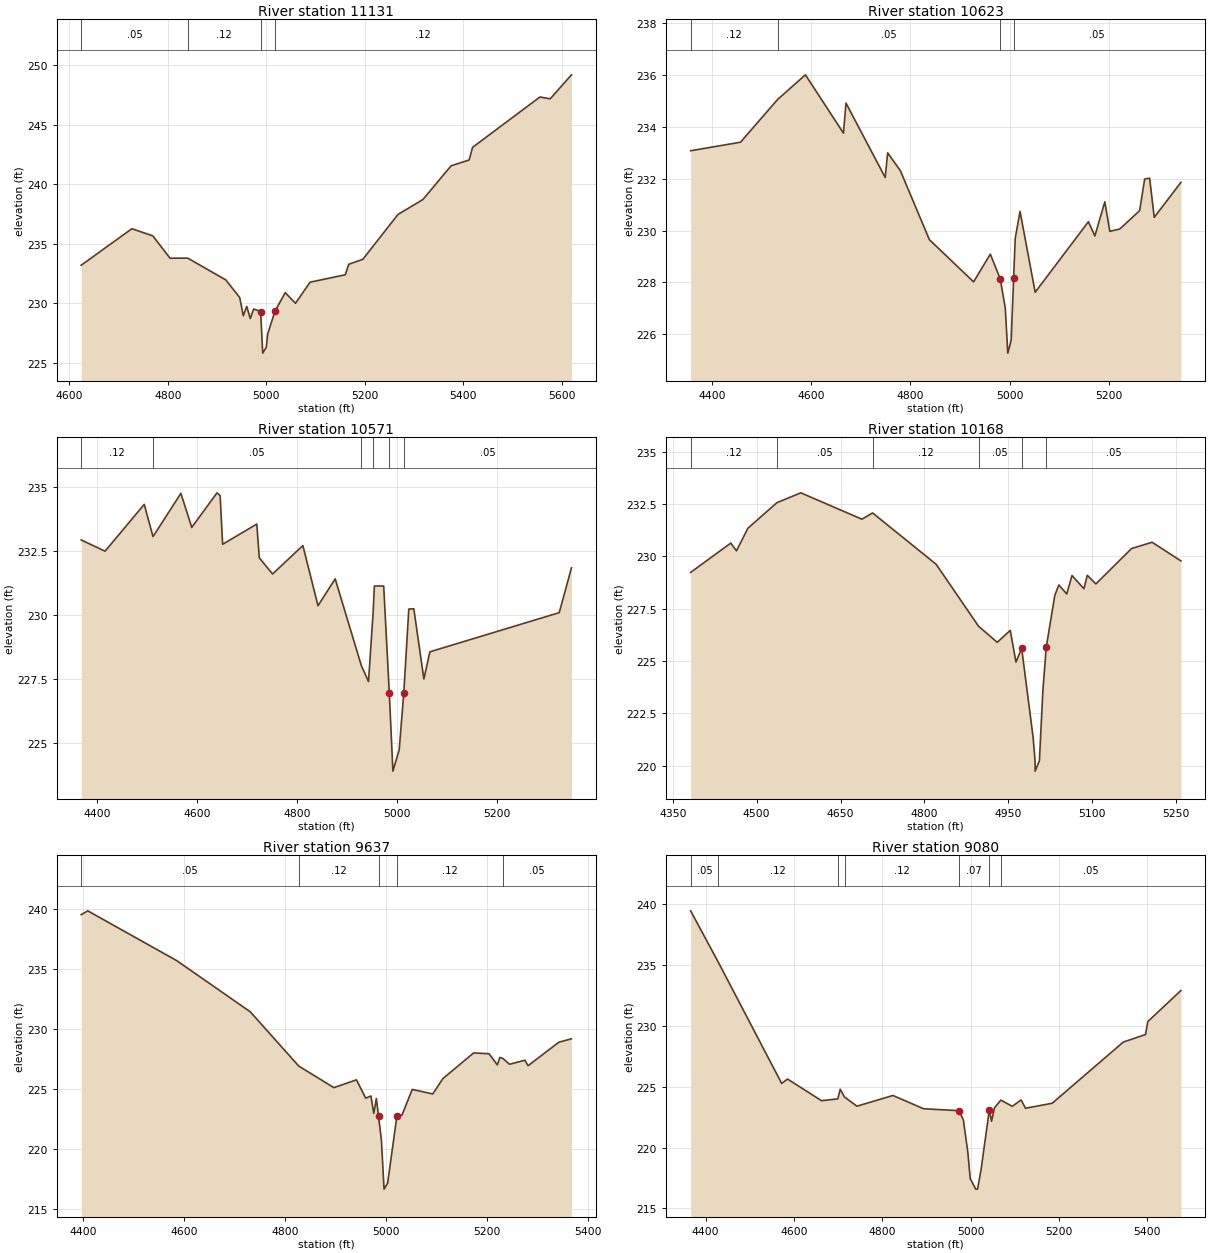
Type RM Length L Ch R = 1 ,11131   ,508,508,508
BEGIN DESCRIPTION:
CRYSTAL CREEK TRIBUTARY NO 6 22.0
END DESCRIPTION:
XS GIS Cut Line= 3
      3851996.74     10134377.65      3851724.88     10134117.76
      3851217.87     10133761.08
#Sta/Elev= 30
  4623.9   233.2  4726.8  236.26  4769.3  235.67  4804.5  233.79  4840.3   233.8
  4917.7  231.97    4946  230.49  4953.2  228.96  4960.2  229.75  4967.4  228.73
  4974.3  229.53  4988.5  229.32  4992.7  225.83    5000  226.33  5002.7  227.42
  5017.5  229.34  5038.4   230.9  5059.3  230.01  5088.9  231.78  5160.4   232.4
  5167.5  233.28  5196.1   233.7  5267.5  237.46  5318.1  238.71  5375.4  241.54
  5412.1  242.03  5419.1  243.09  5555.9  247.31  5576.8  247.16  5619.9  249.17
#Mann= 4 ,-1 , 0
  4623.9     .05       0  4840.3     .12       0  4988.5     .07       0
  5017.5     .12       0
Bank Sta=4988.5,5017.5
XS Rating Curve= 0 ,0
Exp/Cntr=0.3,0.1

Type RM Length L Ch R = 1 ,10623   ,52,52,52
BEGIN DESCRIPTION:
CRYSTAL CREEK TRIBUTARY NO 6 21.0
END DESCRIPTION:
XS GIS Cut Line= 3
      3852058.15     10134350.88      3851984.76     10133712.59
      3851959.19     10133368.24
#Sta/Elev= 30
  4357.5  233.08    4458  233.41  4532.8  235.06  4588.8  236.01  4665.4  233.76
  4670.5  234.92  4749.5  232.05  4754.5     233  4780.1  232.31  4838.5  229.65
  4927.6  228.02  4961.3  229.09  4981.4  228.13  4991.5     227  4996.5  225.27
  5003.3  225.77 5008.32 228.176  5011.5   229.7  5021.2  230.74  5051.7  227.62
  5158.9  230.34    5172  229.79    5192  231.11  5202.1  229.97  5222.1  230.06
  5262.2  230.77  5272.3  231.99  5282.3  232.02  5291.6  230.51  5345.3  231.86
#Mann= 4 ,-1 , 0
  4357.5     .12       0  4532.8     .05       0  4981.4     .07       0
 5008.32     .05       0
Bank Sta=4981.4,5008.32
XS Rating Curve= 0 ,0
Exp/Cntr=0.3,0.1

Type RM Length L Ch R = 1 ,10571   ,403,403,403
BEGIN DESCRIPTION:
Mapping XS afedea0c
END DESCRIPTION:
XS GIS Cut Line= 3
      3852119.57     10134340.06      3852036.44     10133714.56
      3852016.48     10133366.74
#Sta/Elev= 30
    4369  232.94  4416.7   232.5    4495  234.33  4512.5  233.07  4568.2  234.76
  4589.9  233.43  4640.4  234.78  4646.6  234.67  4651.6  232.77  4719.8  233.56
  4724.9  232.24  4751.3  231.61  4811.9  232.72  4842.1  230.37  4876.4  231.42
  4928.7  228.03    4943  227.41  4952.3  230.14  4954.7  231.14  4973.3  231.14
 4984.52 226.968  4991.7  223.91  5004.3  224.74  5013.5  226.97  5023.5  230.24
  5033.5  230.25  5053.6  227.51  5065.6  228.57    5324   230.1  5348.4  231.85
#Mann= 6 ,-1 , 0
    4369     .12       0  4512.5     .05       0  4928.7     .12       0
  4952.3     .05       0 4984.52     .07       0  5013.5     .05       0
Bank Sta=4984.52,5013.5
XS Rating Curve= 0 ,0
Exp/Cntr=0.3,0.1

Type RM Length L Ch R = 1 ,10168   ,531,531,531
BEGIN DESCRIPTION:
CRYSTAL CREEK TRIBUTARY NO 6 20.0
END DESCRIPTION:
XS GIS Cut Line= 3
      3852471.22     10134091.42       3852349.5     10133485.42
      3852213.99     10133265.29
#Sta/Elev= 30
  4381.9  229.23  4453.7  230.63  4463.9  230.26  4484.3  231.34  4536.2  232.56
  4578.9  233.03  4688.2  231.77  4707.2  232.07  4820.8  229.62  4896.7  226.66
  4930.1  225.89  4953.4  226.46  4963.6  224.95  4973.8   225.6  4994.2  221.37
  4997.7  220.24  4997.9  219.74  5005.5  220.24  5011.8  223.62  5017.7  225.65
  5033.1  228.14  5040.3  228.63  5054.4   228.2  5063.8  229.08  5085.2  228.45
  5091.1  229.09  5106.5  228.68  5170.3  230.37    5207  230.67  5258.5  229.78
#Mann= 6 ,-1 , 0
  4381.9     .12       0  4536.2     .05       0  4707.2     .12       0
  4896.7     .05       0  4973.8     .07       0  5017.7     .05       0
Bank Sta=4973.8,5017.7
XS Rating Curve= 0 ,0
Exp/Cntr=0.3,0.1

Type RM Length L Ch R = 1 ,9637    ,557,557,557
BEGIN DESCRIPTION:
CRYSTAL CREEK TRIBUTARY NO 6 19.0
END DESCRIPTION:
XS GIS Cut Line= 3
      3853170.42     10133251.08       3852588.9     10133089.69
      3852226.99     10133150.01
#Sta/Elev= 30
  4396.5  239.56  4409.5  239.88    4586  235.71  4731.3  231.44  4827.2  226.91
  4896.7  225.11  4941.4  225.76  4959.6  224.23    4970  224.41  4975.6  222.95
  4980.8   224.2 4985.02 222.729  4990.7  220.75    4996  216.63  5003.1  217.13
  5021.3   222.7  5031.5  222.82  5051.8  224.96  5092.3  224.58  5112.6  225.87
  5173.4  228.01  5203.8  227.94  5220.2  227.01  5225.2  227.63    5231  227.55
  5244.4  227.06  5274.8   227.4    5281  226.94  5341.8   228.9  5366.9  229.19
#Mann= 5 ,-1 , 0
  4396.5     .05       0  4827.2     .12       0 4985.02     .07       0
  5021.3     .12       0    5231     .05       0
Bank Sta=4985.02,5021.3
XS Rating Curve= 0 ,0
Exp/Cntr=0.3,0.1

Type RM Length L Ch R = 1 ,9080    ,580,580,580
BEGIN DESCRIPTION:
CRYSTAL CREEK TRIBUTARY NO 6 18.0
END DESCRIPTION:
XS GIS Cut Line= 3
      3853133.33      10132634.5       3852501.7     10132580.88
      3852028.23      10132634.5
#Sta/Elev= 30
  4366.1  239.46  4428.9  235.23  4572.3  225.27  4585.6  225.63  4662.6  223.85
  4699.4     224    4705  224.79  4714.6  224.15  4742.9   223.4  4824.3  224.28
  4893.5  223.19  4973.8  223.03  4983.8  222.27  4993.8  219.65  4999.4  217.44
  5011.9  216.58    5016  216.58    5024  218.21  5042.6  223.09  5047.7  222.16
  5054.2  223.26  5068.7   223.9  5094.5  223.39  5114.6  223.91  5124.6  223.23
    5185  223.64    5346  228.67  5396.4  229.29  5401.5  230.35  5476.5  232.91
#Mann= 7 ,-1 , 0
  4366.1     .05       0  4428.9     .12       0  4699.4     .05       0
  4714.6     .12       0  4973.8     .07       0  5042.6     .12       0
  5068.7     .05       0
Bank Sta=4973.8,5042.6
XS Rating Curve= 0 ,0
Exp/Cntr=0.3,0.1