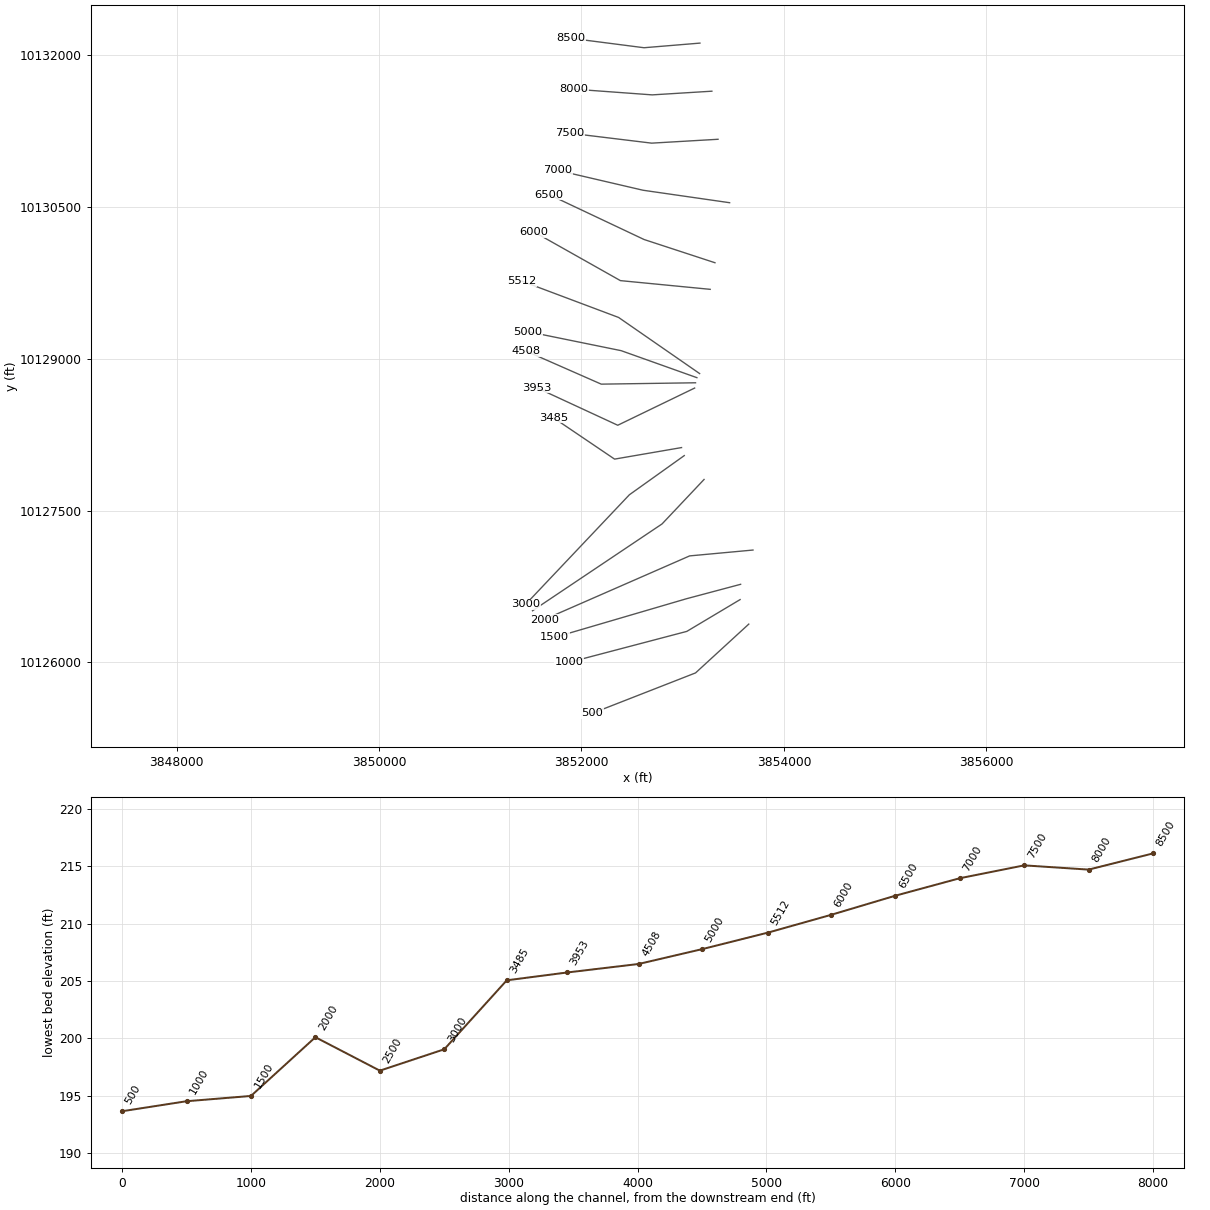
HEC-RAS study CRYSTAL CREEK TRIBUTARY NO 6.prj: CRYSTAL CREEK TRIBUTARY NO 6 Base Level Engineering

--- CRYSTAL CREEK TRIBUTARY NO 6.g10 (geometry) --- (continued)

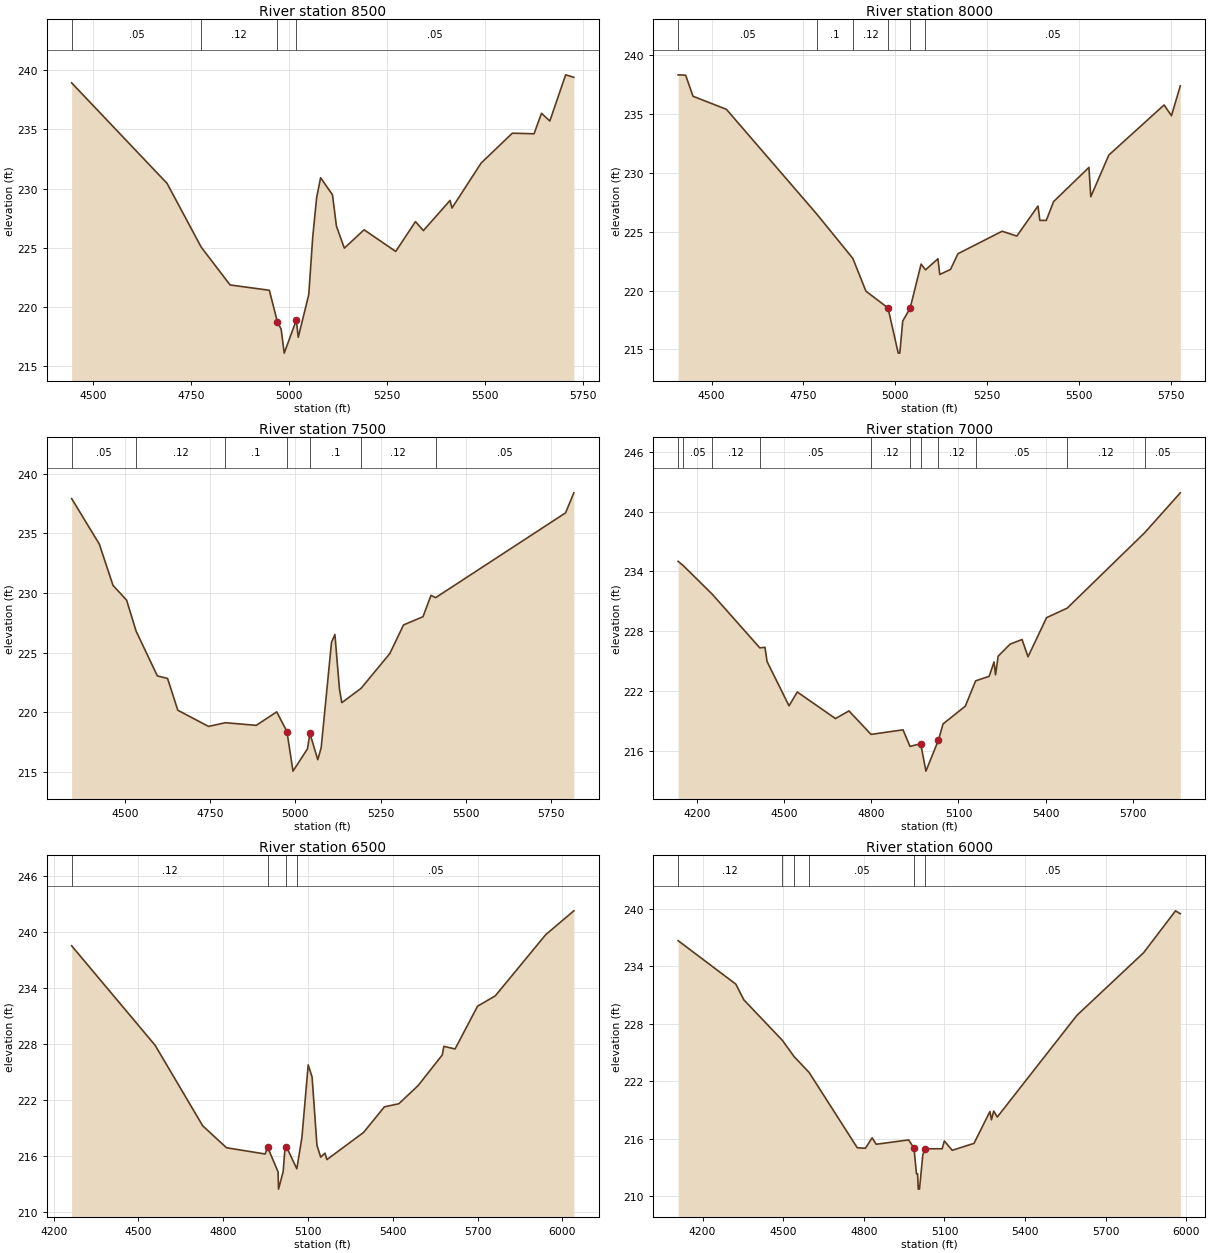
Type RM Length L Ch R = 1 ,8500    ,500,500,500
BEGIN DESCRIPTION:
CRYSTAL CREEK TRIBUTARY NO 6 17.0
END DESCRIPTION:
XS GIS Cut Line= 3
      3853170.42     10132118.99      3852617.71     10132073.27
      3851897.17     10132166.12
#Sta/Elev= 30
  4445.4  238.93  4688.8  230.44    4776  225.05  4849.6  221.86  4949.7  221.41
  4970.4  218.73  4979.8  218.13  4987.7   216.1  5018.4  218.88  5023.5  217.44
  5050.3  221.04  5060.4   225.9  5070.4  229.24  5080.5  230.92  5110.8  229.47
  5120.9  226.83    5141  224.97  5191.4  226.52  5272.1  224.69  5322.5  227.21
  5342.7  226.45  5410.7     229  5415.7  228.36  5490.1  232.16  5569.6  234.68
    5625  234.63    5644  236.36  5665.3  235.71  5705.6  239.61  5726.5   239.4
#Mann= 4 ,-1 , 0
  4445.4     .05       0    4776     .12       0  4970.4     .07       0
  5018.4     .05       0
Bank Sta=4970.4,5018.4
XS Rating Curve= 0 ,0
Exp/Cntr=0.3,0.1

Type RM Length L Ch R = 1 ,8000    ,500,500,500
BEGIN DESCRIPTION:
CRYSTAL CREEK TRIBUTARY NO 6 16.0
END DESCRIPTION:
XS GIS Cut Line= 3
      3853288.33     10131643.92      3852698.25     10131607.54
      3851923.82     10131664.13
#Sta/Elev= 30
  4408.8  238.32  4429.3  238.29  4449.4   236.5  4540.4  235.39  4786.1  226.51
  4884.7  222.73  4920.3  219.95  4980.4  218.53  5008.3  214.69  5012.6  214.69
  5020.5  217.41  5040.5  218.49  5070.6  222.25  5082.5  221.76  5116.4   222.7
  5121.4  221.37  5150.8   221.8  5170.9  223.13  5291.2  225.04  5331.3  224.63
  5388.9  227.18    5394  225.96  5411.5  225.96  5431.5  227.56  5527.7  230.46
  5532.7  227.97  5581.9  231.51  5732.3  235.76  5752.4  234.85  5776.5  237.38
#Mann= 6 ,-1 , 0
  4408.8     .05       0  4786.1      .1       0  4884.7     .12       0
  4980.4     .07       0  5040.5     .12       0  5082.5     .05       0
Bank Sta=4980.4,5040.5
XS Rating Curve= 0 ,0
Exp/Cntr=0.3,0.1

Type RM Length L Ch R = 1 ,7500    ,500,500,500
BEGIN DESCRIPTION:
CRYSTAL CREEK TRIBUTARY NO 6 15.0
END DESCRIPTION:
XS GIS Cut Line= 3
      3853349.03     10131168.85      3852693.14     10131130.66
      3851881.41     10131229.32
#Sta/Elev= 30
    4343  237.92  4424.3   234.1  4464.4  230.64  4504.4   229.4  4532.3   226.8
  4594.6  223.05  4624.7  222.83  4654.7  220.17  4744.9  218.81  4794.5  219.12
  4885.1   218.9  4945.2  220.03  4975.2  218.38    4993  215.06  5035.5  216.93
  5042.7  218.22  5065.8  216.02  5075.8  217.03  5106.1  225.86  5116.1  226.52
  5129.5  221.93  5136.3   220.8  5192.8     222  5277.3  224.92  5317.6  227.32
  5374.7  228.01  5398.2   229.8  5411.9  229.61  5793.4  236.72  5817.7   238.4
#Mann= 7 ,-1 , 0
    4343     .05       0  4532.3     .12       0  4794.5      .1       0
  4975.2     .03       0  5042.7      .1       0  5192.8     .12       0
  5411.9     .05       0
Bank Sta=4975.2,5042.7
XS Rating Curve= 0 ,0
Exp/Cntr=0.3,0.1

Type RM Length L Ch R = 1 ,7000    ,500,500,500
BEGIN DESCRIPTION:
CRYSTAL CREEK TRIBUTARY NO 6 14.0
END DESCRIPTION:
XS GIS Cut Line= 3
       3853463.5     10130542.16      3852608.12     10130665.35
      3851767.82     10130861.08
#Sta/Elev= 30
  4135.8  235.02  4153.5  234.59  4253.7   231.7  4416.9  226.32  4434.5  226.38
  4441.7  224.95  4517.2   220.5  4545.6  221.89    4677  219.22  4723.4  219.99
  4799.3  217.63  4909.3  218.09  4933.3  216.42    4970   216.7    4988  213.94
  5031.1  217.06  5046.9  218.68  5123.5  220.47  5158.9  223.01  5205.6  223.47
  5222.3  224.91  5227.4  223.62  5236.4  225.49  5277.5   226.7  5318.6  227.16
  5339.1  225.43  5402.9  229.36    5474  230.32  5740.5   237.9  5862.8   241.9
#Mann= 11 ,-1 , 0
  4135.8     .12       0  4153.5     .05       0  4253.7     .12       0
  4416.9     .05       0  4799.3     .12       0  4933.3     .05       0
    4970     .07       0  5031.1     .12       0  5158.9     .05       0
    5474     .12       0  5740.5     .05       0
Bank Sta=4970,5031.1
XS Rating Curve= 0 ,0
Exp/Cntr=0.3,0.1

Type RM Length L Ch R = 1 ,6500    ,500,500,500
BEGIN DESCRIPTION:
CRYSTAL CREEK TRIBUTARY NO 6 13.0
END DESCRIPTION:
XS GIS Cut Line= 3
      3853318.68     10129949.16      3852618.76      10130178.4
      3851677.82     10130623.02
#Sta/Elev= 30
  4263.5  238.53    4559  227.85  4727.4  219.21  4811.6  216.86  4948.3  216.19
    4957  216.92  4994.1  214.27  4995.6  212.42  5012.1  214.31  5017.8  216.55
  5023.3  216.99  5060.4   214.6  5078.4  217.97  5100.6  225.75  5114.4  224.45
  5131.6  217.13  5144.8  215.85  5159.9  216.28  5166.9  215.59  5296.5   218.5
  5370.3  221.25  5421.3  221.58  5489.6  223.53  5575.2  226.82  5580.7  227.74
  5620.4  227.46    5700  232.05  5762.8  233.16  5941.1  239.72  6040.7  242.28
#Mann= 4 ,-1 , 0
  4263.5     .12       0    4957     .07       0  5023.3     .12       0
  5060.4     .05       0
Bank Sta=4957,5023.3
XS Rating Curve= 0 ,0
Exp/Cntr=0.3,0.1

Type RM Length L Ch R = 1 ,6000    ,488,488,488
BEGIN DESCRIPTION:
CRYSTAL CREEK TRIBUTARY NO 6 12.0
END DESCRIPTION:
XS GIS Cut Line= 3
      3853271.47     10129686.36      3852384.53     10129772.43
      3851532.97     10130252.37
#Sta/Elev= 30
  4108.9  236.66  4323.5  232.13  4353.7  230.48    4497  226.26  4540.5  224.57
  4596.5  222.91  4775.6  215.06  4805.8  215.01  4830.8   216.1    4846  215.43
  4966.5  215.88  4986.6  215.04  4995.8  212.35    5000  212.35  5002.4  210.75
    5007  210.75  5019.2  214.27  5026.3  214.96  5091.3  214.96  5099.5  215.77
  5128.9   214.8  5209.8  215.52  5269.1  218.84  5274.8  217.98  5283.2  218.89
  5296.5  218.27  5592.7  228.87  5841.2  235.41  5959.7  239.77  5977.5  239.47
#Mann= 6 ,-1 , 0
  4108.9     .12       0    4497     .05       0  4540.5     .12       0
  4596.5     .05       0  4986.6     .07       0  5026.3     .05       0
Bank Sta=4986.6,5026.3
XS Rating Curve= 0 ,0
Exp/Cntr=0.3,0.1

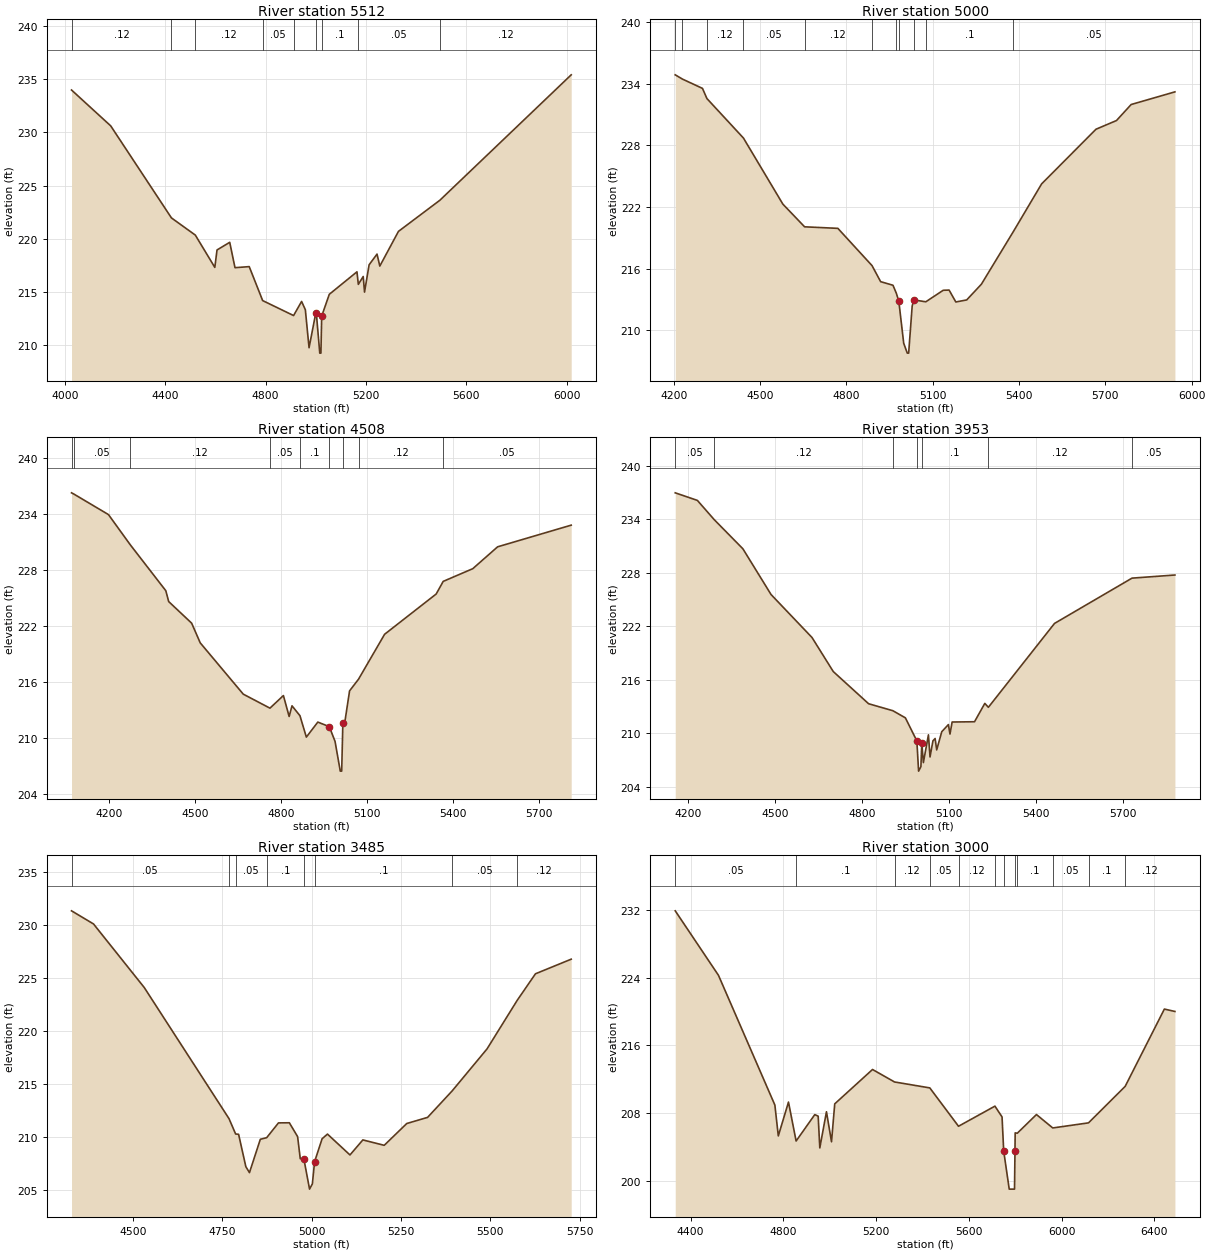
Type RM Length L Ch R = 1 ,5512    ,512,512,512
BEGIN DESCRIPTION:
CRYSTAL CREEK TRIBUTARY NO 6 11.0
END DESCRIPTION:
XS GIS Cut Line= 3
      3853167.01     10128854.16      3852366.65     10129408.52
      3851413.74     10129766.43
#Sta/Elev= 30
  4026.4     234  4182.6  230.62  4424.6  221.95  4519.8  220.33  4597.5  217.29
  4606.3  218.93  4656.9  219.65  4677.9  217.26  4734.6  217.36  4788.2  214.16
  4911.4  212.75  4943.4  214.08  4958.3   213.3  4973.1  209.72    5000     213
    5002     213  5015.8  209.21  5020.4  209.21  5023.4  212.69  5053.7  214.75
    5164  216.87  5169.5  215.69  5188.9  216.43  5194.2  214.96  5212.4  217.53
    5244  218.54  5255.1  217.41  5329.4  220.68  5494.3  223.61  6017.9  235.43
#Mann= 9 ,-1 , 0
  4026.4     .12       0  4424.6     .05       0  4519.8     .12       0
  4788.2     .05       0  4911.4      .1       0    5000     .07       0
  5023.4      .1       0  5169.5     .05       0  5494.3     .12       0
Bank Sta=5002,5023.4
XS Rating Curve= 0 ,0
Exp/Cntr=0.3,0.1

Type RM Length L Ch R = 1 ,5000    ,492,492,492
BEGIN DESCRIPTION:
CRYSTAL CREEK TRIBUTARY NO 6 10.0
END DESCRIPTION:
XS GIS Cut Line= 3
      3853140.13     10128813.69      3852391.86     10129080.43
      3851468.93     10129268.55
#Sta/Elev= 30
  4205.6  234.87  4230.3  234.46  4300.2  233.55  4315.7  232.56  4442.7  228.71
  4579.6  222.28  4655.1  220.07  4770.7  219.92  4889.5  216.29  4919.3  214.73
  4962.2  214.38  4973.7  213.61  4982.4  212.84  4999.5  208.73  5011.9  207.77
  5016.7  207.77  5028.9  212.35  5034.7  212.95  5076.3  212.77  5136.8  213.89
  5157.2  213.91  5180.6  212.75  5218.4  212.95  5269.4  214.48  5380.8  219.62
  5478.7  224.25  5667.5  229.57  5738.9  230.42  5789.9  231.98  5941.9  233.21
#Mann= 11 ,-1 , 0
  4205.6     .12       0  4230.3     .05       0  4315.7     .12       0
  4442.7     .05       0  4655.1     .12       0  4889.5     .05       0
  4973.7     .12       0  4982.4     .07       0  5034.7     .12       0
  5076.3      .1       0  5380.8     .05       0
Bank Sta=4982.4,5034.7
XS Rating Curve= 0 ,0
Exp/Cntr=0.3,0.1

Type RM Length L Ch R = 1 ,4508    ,555,555,555
BEGIN DESCRIPTION:
CRYSTAL CREEK TRIBUTARY NO 6 9.0
END DESCRIPTION:
XS GIS Cut Line= 3
      3853126.59     10128763.16      3852195.19     10128749.72
      3851452.98     10129076.11
#Sta/Elev= 30
  4068.5  236.27    4076  236.15  4197.3  233.94  4273.3  230.71  4397.3  225.79
  4407.3  224.63  4487.3  222.32  4517.3  220.21  4667.3  214.72  4760.4  213.22
  4807.3  214.57  4827.3  212.33  4837.3  213.47    4865  212.41  4887.3  210.12
  4927.3  211.73  4967.3  211.24  4987.3  209.67  5005.6  206.48  5010.5  206.48
  5014.6  211.63  5020.1  211.46    5038  215.07  5069.2  216.32  5160.2  221.13
    5340  225.44  5364.5  226.79  5467.6  228.15  5554.2  230.49  5810.8  232.81
#Mann= 9 ,-1 , 0
  4068.5     .12       0    4076     .05       0  4273.3     .12       0
  4760.4     .05       0    4865      .1       0  4967.3     .07       0
  5014.6      .1       0  5069.2     .12       0  5364.5     .05       0
Bank Sta=4967.3,5014.6
XS Rating Curve= 0 ,0
Exp/Cntr=0.3,0.1

Type RM Length L Ch R = 1 ,3953    ,468,468,468
BEGIN DESCRIPTION:
CRYSTAL CREEK TRIBUTARY NO 6 8.0
END DESCRIPTION:
XS GIS Cut Line= 3
      3853117.82     10128711.06      3852358.14     10128343.55
      3851561.07     10128712.68
#Sta/Elev= 30
  4156.1  236.96  4232.4  236.11  4290.5  233.95  4389.3  230.68  4486.4  225.55
  4627.5  220.73  4700.8  216.91  4822.6   213.3    4906  212.52  4949.3  211.72
  4988.9  209.13  4994.9  205.74  5002.9  206.24  5005.9  208.92  5011.4   206.7
  5028.8  209.81  5034.3  207.33  5044.4  209.14  5051.8   209.4  5057.3  208.12
  5074.7  210.16  5097.6  210.96  5103.1   209.9  5110.5  211.25  5187.7  211.28
  5223.2  213.34  5235.4   212.9  5463.4  222.31  5730.5  227.39  5878.4  227.74
#Mann= 7 ,-1 , 0
  4156.1     .05       0  4290.5     .12       0    4906      .1       0
  4988.9     .07       0  5005.9      .1       0  5235.4     .12       0
  5730.5     .05       0
Bank Sta=4988.9,5005.9
XS Rating Curve= 0 ,0
Exp/Cntr=0.3,0.1

Type RM Length L Ch R = 1 ,3485    ,485,485,485
BEGIN DESCRIPTION:
CRYSTAL CREEK TRIBUTARY NO 6 7.0
END DESCRIPTION:
XS GIS Cut Line= 3
      3852988.44     10128122.99      3852326.77     10128009.07
      3851725.01     10128416.11
#Sta/Elev= 30
  4328.6  231.36  4390.1  230.12  4532.1  224.11  4769.2  211.72  4787.7  210.27
    4796  210.24  4816.3  207.18  4826.4  206.62  4856.8  209.77  4874.5  209.92
  4907.6  211.32    4938  211.33  4961.1  210.02  4968.5  207.94  4978.6  207.92
  4994.5  205.06  5002.4  205.56  5008.6  207.65  5029.6  209.82  5044.6  210.26
  5107.6  208.29  5143.6  209.71  5203.4   209.2  5266.4  211.26  5324.7  211.84
  5393.4  214.34    5491  218.31  5575.6  222.91  5626.5  225.41  5726.5  226.79
#Mann= 8 ,-1 , 0
  4328.6     .05       0  4769.2     .12       0  4787.7     .05       0
  4874.5      .1       0  4978.6     .07       0  5008.6      .1       0
  5393.4     .05       0  5575.6     .12       0
Bank Sta=4978.6,5008.6
XS Rating Curve= 0 ,0
Exp/Cntr=0.3,0.1

Type RM Length L Ch R = 1 ,3000    ,500,500,500
BEGIN DESCRIPTION:
CRYSTAL CREEK TRIBUTARY NO 6 6.0
END DESCRIPTION:
XS GIS Cut Line= 3
      3853015.43     10128043.81      3852473.09     10127656.74
      3851449.29     10126575.42
#Sta/Elev= 30
  4333.7  231.86  4520.2  224.26  4763.5  208.97  4778.3  205.33  4822.2  209.32
  4855.1  204.73  4935.6  207.84  4950.3  207.66  4957.3  203.92    4986  208.18
  5007.8  204.64  5021.7  209.11  5184.7  213.16  5279.6  211.69  5431.8  210.99
  5555.6  206.47  5712.7  208.84  5743.4  207.57  5750.6  203.53  5774.4  199.06
  5797.2  199.06 5799.22 203.612    5800  205.69  5809.2  205.65  5891.8  207.85
  5962.1  206.27  6116.4  206.87  6274.5  211.17  6443.6  220.28  6489.1     220
#Mann= 12 ,-1 , 0
  4333.7     .05       0  4855.1      .1       0  5279.6     .12       0
  5431.8     .05       0  5555.6     .12       0  5712.7     .05       0
  5750.6     .07       0    5800     .05       0  5809.2      .1       0
  5962.1     .05       0  6116.4      .1       0  6274.5     .12       0
Bank Sta=5750.6,5799.22
XS Rating Curve= 0 ,0
Exp/Cntr=0.3,0.1

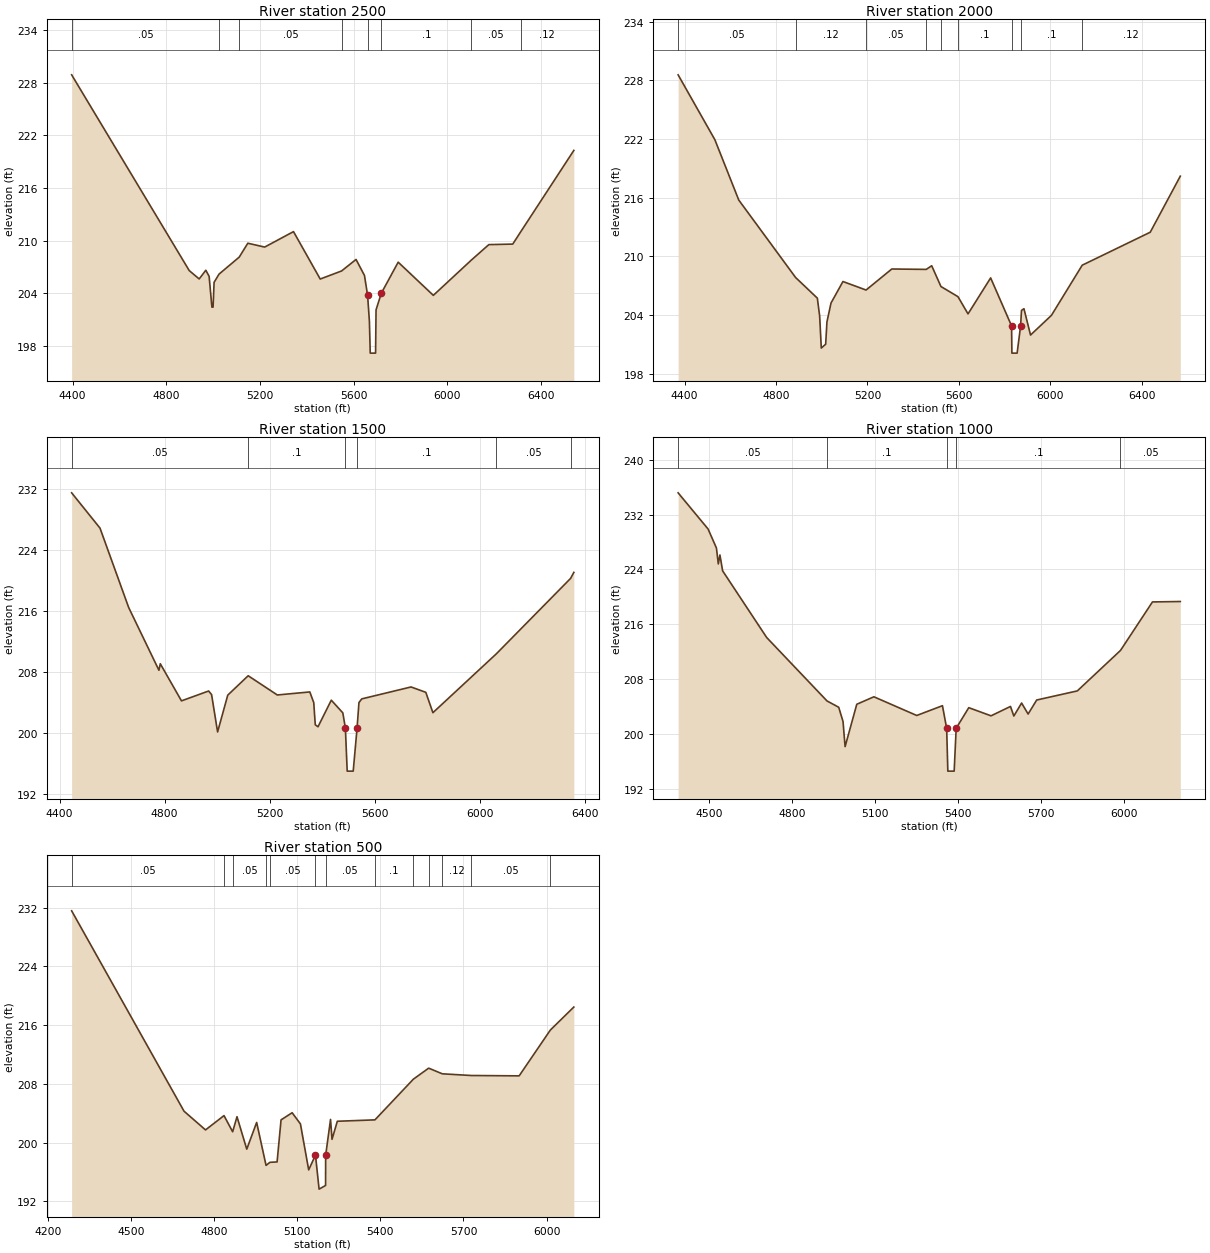
Type RM Length L Ch R = 1 ,2500    ,500,500,500
BEGIN DESCRIPTION:
CRYSTAL CREEK TRIBUTARY NO 6 5.0
END DESCRIPTION:
XS GIS Cut Line= 3
      3853210.84     10127807.95      3852796.05     10127368.76
       3851516.1     10126510.79
#Sta/Elev= 30
  4395.9   228.9  4898.2   206.6  4940.7  205.65    4969  206.64  4983.1  205.95
    4995  202.44    5000  202.44  5004.3  205.26  5025.5   206.2  5111.8  208.14
  5148.4  209.72  5220.4  209.28  5343.5  211.04  5457.6  205.64  5548.9  206.56
  5610.6  207.87  5646.6  206.05    5660  203.78  5667.7  200.83  5671.3   197.2
  5694.1   197.2  5696.1  202.13  5718.7  204.03  5790.7  207.56  5940.8  203.78
  6102.8  207.79  6177.9  209.56    6280  209.62  6314.2  211.03  6540.9  220.29
#Mann= 8 ,-1 , 0
  4395.9     .05       0  5025.5      .1       0  5111.8     .05       0
  5548.9      .1       0    5660     .07       0  5718.7      .1       0
  6102.8     .05       0  6314.2     .12       0
Bank Sta=5660,5718.7
XS Rating Curve= 0 ,0
Exp/Cntr=0.3,0.1

Type RM Length L Ch R = 1 ,2000    ,500,500,500
BEGIN DESCRIPTION:
CRYSTAL CREEK TRIBUTARY NO 6 4.0
END DESCRIPTION:
XS GIS Cut Line= 3
       3853694.6     10127110.73      3853068.57     10127052.86
      3851631.13     10126423.95
#Sta/Elev= 30
  4371.3  228.56  4532.1  221.93  4636.7  215.76  4885.5  207.84  4980.6  205.73
  4990.7  203.91  4997.9  200.63    5017  201.02  5022.6   203.3  5040.4  205.23
  5092.7  207.43  5193.8  206.56  5306.4  208.71  5457.1  208.67  5481.1  209.04
  5521.5  206.92  5596.1  205.88    5640  204.12    5739   207.8 5830.56 202.897
    5832  200.11  5854.9  200.11 5870.09 202.888    5874  204.48  5884.8  204.65
  5913.6  201.96    6005  203.97  6139.8   209.1  6437.5  212.47    6569   218.2
#Mann= 9 ,-1 , 0
  4371.3     .05       0  4885.5     .12       0  5193.8     .05       0
  5457.1      .1       0  5521.5     .05       0  5596.1      .1       0
    5832     .07       0 5870.09      .1       0  6139.8     .12       0
Bank Sta=5830.56,5870.09
XS Rating Curve= 0 ,0
Exp/Cntr=0.3,0.1

Type RM Length L Ch R = 1 ,1500    ,500,500,500
BEGIN DESCRIPTION:
CRYSTAL CREEK TRIBUTARY NO 6 3.0
END DESCRIPTION:
XS GIS Cut Line= 3
      3853572.19     10126772.18      3853036.96     10126629.59
      3851732.69     10126247.08
#Sta/Elev= 30
  4446.1  231.44  4554.1  226.82  4663.4  216.42  4778.6  208.21  4783.8  209.06
  4864.5   204.2    4968  205.49  4979.2  205.02  5002.1  200.13  5040.8  204.95
  5118.6  207.49  5229.6  204.97  5353.4  205.37  5368.4  203.97  5374.2  201.07
  5384.7  200.81  5435.2  204.29  5479.1  202.63  5488.9  200.64  5495.8     195
  5518.7     195 5533.49 200.657  5540.6  203.98  5551.4  204.46    5739  206.02
  5795.3  205.32  5822.3  202.65  6064.3  210.37  6346.7  220.23  6359.2  221.02
#Mann= 6 ,-1 , 0
  4446.1     .05       0  5118.6      .1       0  5488.9     .07       0
 5533.49      .1       0  6064.3     .05       0  6346.7     .12       0
Bank Sta=5488.9,5533.49
XS Rating Curve= 0 ,0
Exp/Cntr=0.3,0.1

Type RM Length L Ch R = 1 ,1000    ,500,500,500
BEGIN DESCRIPTION:
CRYSTAL CREEK TRIBUTARY NO 6 2.0
END DESCRIPTION:
XS GIS Cut Line= 3
      3853567.02     10126621.16      3853040.62     10126307.06
      3851874.95     10126000.52
#Sta/Elev= 30
    4387   235.2  4495.6  229.91  4525.8  227.13  4532.6  224.81  4538.4  226.12
  4548.2   223.8  4707.7  214.06  4926.2  204.79  4968.5  203.87  4984.1  201.79
  4991.6  198.12  5033.9  204.31  5095.9   205.4    5251  202.67  5344.1   204.1
 5359.35 200.784  5363.6  194.54  5386.5  194.54  5393.8   200.8  5439.4  203.81
    5520  202.62  5590.4  203.99  5602.6  202.59  5630.7  204.49  5654.3  202.88
  5685.3  204.93  5832.4  206.26  5988.7  212.17  6104.5  219.26  6205.3  219.32
#Mann= 5 ,-1 , 0
    4387     .05       0  4926.2      .1       0 5359.35     .07       0
  5393.8      .1       0  5988.7     .05       0
Bank Sta=5359.35,5393.8
XS Rating Curve= 0 ,0
Exp/Cntr=0.3,0.1

Type RM Length L Ch R = 1 ,500     ,0,0,0
BEGIN DESCRIPTION:
CRYSTAL CREEK TRIBUTARY NO 6 1.0
END DESCRIPTION:
XS GIS Cut Line= 3
      3853652.73       10126379.      3853126.93     10125896.85
      3852104.09     10125497.04
#Sta/Elev= 30
  4286.6  231.56    4692  204.28  4769.6  201.73  4836.2  203.68  4867.4  201.48
  4883.1  203.53  4918.3  199.11    4954  202.75  4987.9   196.9  5001.9  197.32
  5027.7  197.37    5042   203.1    5082  204.07  5111.9  202.55  5141.7  196.29
  5166.2   198.3  5179.2  193.67  5202.6  194.17 5202.92 198.265  5220.5  203.16
  5225.9  200.45    5245  202.91  5380.7   203.1  5519.3  208.64  5574.6  210.14
  5623.7  209.37  5728.1  209.14  5900.9  209.09  6013.5  215.33  6098.2  218.46
#Mann= 13 ,-1 , 0
  4286.6     .05       0  4836.2      .1       0  4867.4     .05       0
  4987.9      .1       0  5001.9     .05       0  5166.2     .07       0
  5202.6     .05       0  5380.7      .1       0  5519.3     .12       0
  5574.6     .05       0  5623.7     .12       0  5728.1     .05       0
  6013.5     .12       0
Bank Sta=5166.2,5202.92
XS Rating Curve= 0 ,0
Exp/Cntr=0.3,0.1