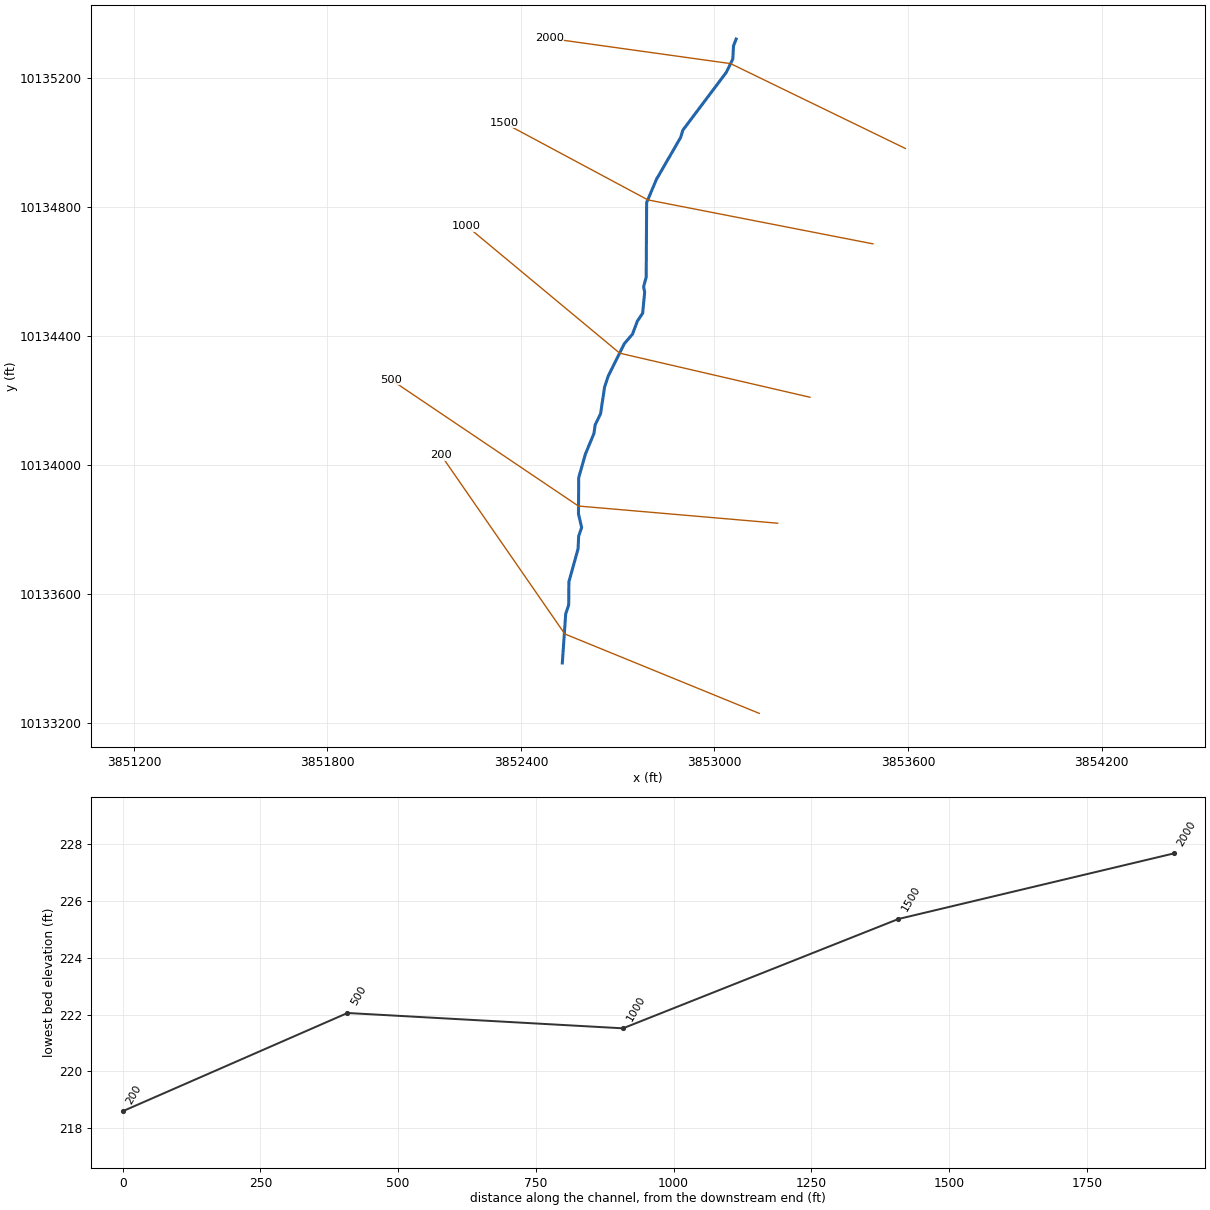
--- CRYSTAL CREEK TRIBUTARY NO 6_2.prj (project) ---

Proj Title=CRYSTAL CREEK TRIBUTARY NO 6_2 Base Level Engineering
Current Plan=p01
Default Exp/Contr=0.3,0.1
English Units
Geom File=g01
Flow File=f01
Plan File=p01
Y Axis Title=Elevation
X Axis Title(PF)=Main Channel Distance
X Axis Title(XS)=Station
BEGIN DESCRIPTION:
CRYSTAL CREEK TRIBUTARY NO 6_2
END DESCRIPTION:
DSS Export Rating Curves= 0
DSS Export Rating Curve Sorted= 0
DSS Export Volume Flow Curves= 0
DXF OffsetX= 0
DXF OffsetY= 0
DXF ScaleX= 1
DXF ScaleY= 10

--- CRYSTAL CREEK TRIBUTARY NO 6_2.p01 (plan) ---

Plan Title=Multiple Run
Short Identifier=Multiple
Geom File=g01
Flow File=f01
Subcritical Flow
K Sum by GR= 0
Std Step Tol= 0.01
Critical Tol= 0.01
Num of Std Step Trials= 20
Max Error Tol= 0.3
Flow Tol Ratio= 0.001
Split Flow NTrial= 30
Split Flow Tol= 0.02
Split Flow Ratio= 0.02
Log Output Level= 0
Friction Slope Method= 1
Unsteady Friction Slope Method= 2
Unsteady Bridges Friction Slope Method= 1
Parabolic Critical Depth
Global Vel Dist=  1 , 1 , 1
Global Log Level= 0
CheckData=True
Encroach Param= -1, 0, 0, 0
BEGIN DESCRIPTION:
Multiple Run
END DESCRIPTION:

--- CRYSTAL CREEK TRIBUTARY NO 6_2.f01 (steady flow) ---

Flow Title=Multiple
Program Version=4.10
Number of Profiles= 7
Profile Names=10-year,25-year,50-year,1pct_min,100-year,1pct_plu,500-year
River Rch & RM=CRYSTAL CREEK TR,Reach-1         ,2000
     435     567     745     323     976    2947    1725
Boundary for River Rch & Prof#=CRYSTAL CREEK TR,Reach-1         , 1
Up Type= 0
Dn Type= 3
Dn Slope=0.009
Boundary for River Rch & Prof#=CRYSTAL CREEK TR,Reach-1         , 2
Up Type= 0
Dn Type= 3
Dn Slope=0.009
Boundary for River Rch & Prof#=CRYSTAL CREEK TR,Reach-1         , 3
Up Type= 0
Dn Type= 3
Dn Slope=0.009
Boundary for River Rch & Prof#=CRYSTAL CREEK TR,Reach-1         , 4
Up Type= 0
Dn Type= 3
Dn Slope=0.009
Boundary for River Rch & Prof#=CRYSTAL CREEK TR,Reach-1         , 5
Up Type= 0
Dn Type= 3
Dn Slope=0.009
Boundary for River Rch & Prof#=CRYSTAL CREEK TR,Reach-1         , 6
Up Type= 0
Dn Type= 3
Dn Slope=0.009
Boundary for River Rch & Prof#=CRYSTAL CREEK TR,Reach-1         , 7
Up Type= 0
Dn Type= 3
Dn Slope=0.009
DSS Import GetInterval= 0
DSS Import GetPeak= 0
DSS Import FillOption= 0

--- CRYSTAL CREEK TRIBUTARY NO 6_2.g01 (geometry) ---

Geom Title=Existing Conditions
Program Version=4.10

River Reach=CRYSTAL CREEK TR,Reach-1
Reach XY= 30
      3853067.13      10135321.2      3853058.88     10135299.84
      3853056.81     10135259.33      3853036.39     10135217.68
       3852901.6     10135038.33      3852895.22     10135016.26
      3852820.32     10134886.88      3852789.65     10134814.37
      3852788.28     10134583.24      3852780.25     10134553.53
      3852783.52     10134536.35      3852777.26      10134471.1
      3852760.91     10134446.69      3852745.59     10134406.11
      3852720.49     10134376.84      3852670.32     10134276.01
      3852659.32     10134242.53      3852646.74     10134159.39
      3852630.07     10134125.17      3852626.36     10134098.57
      3852600.05     10134035.18      3852579.06     10133961.63
      3852578.32     10133849.36      3852588.13     10133806.95
      3852578.89     10133779.72      3852577.14      10133741.2
      3852548.65     10133638.77      3852548.02     10133567.15
       3852538.7     10133538.87      3852528.24     10133386.86

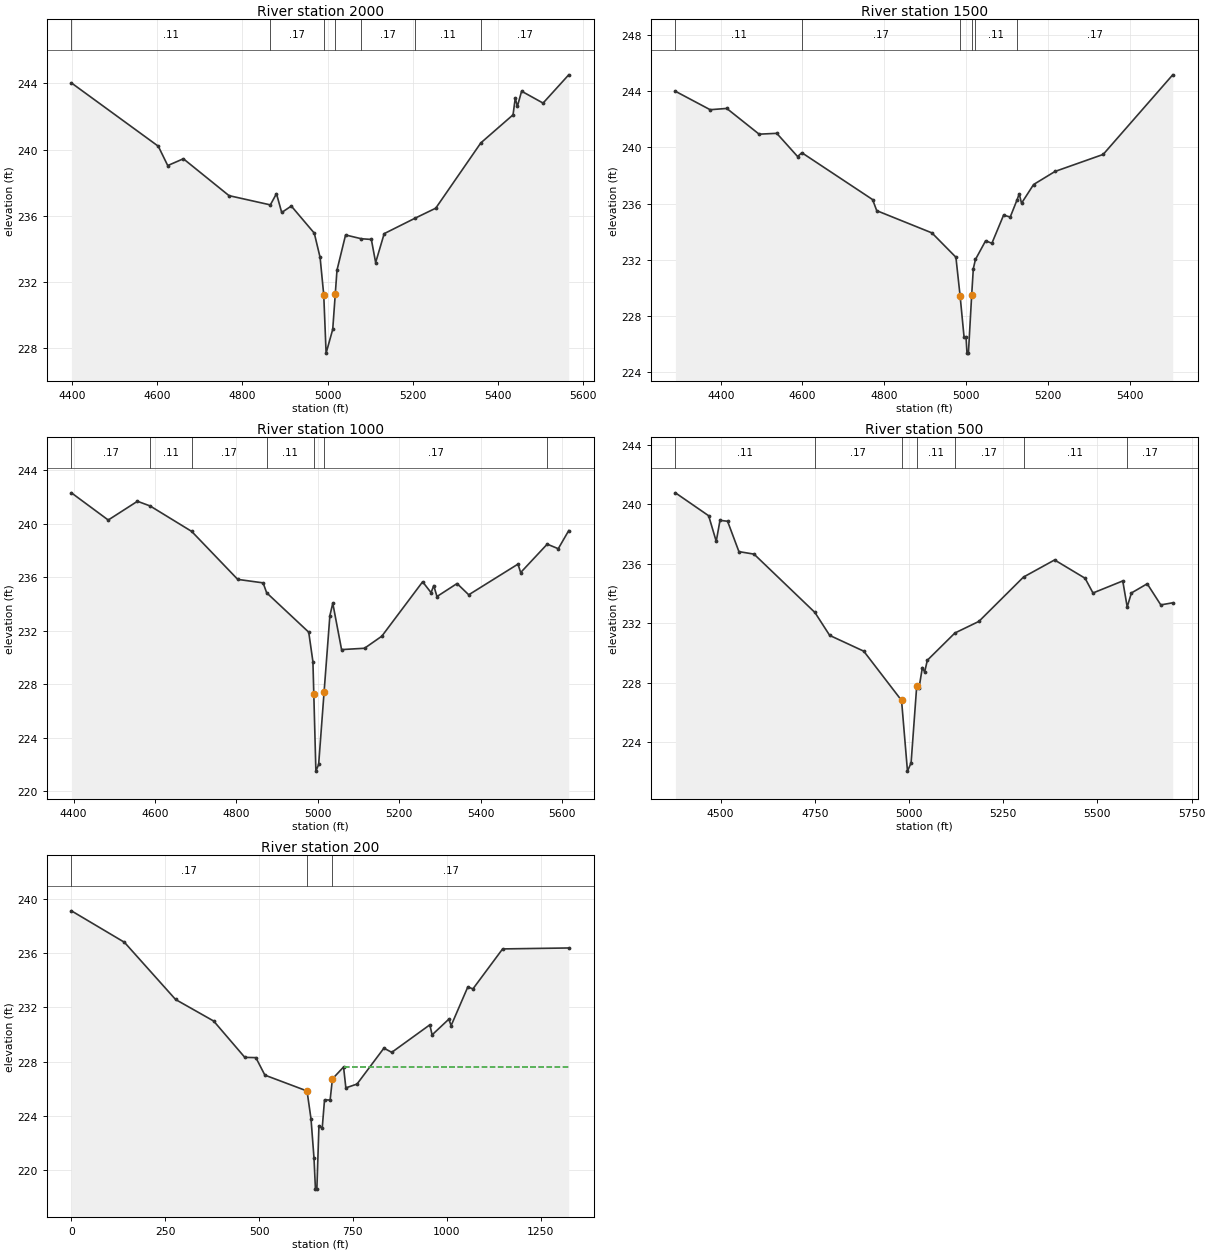
Type RM Length L Ch R = 1 ,2000    ,500,500,500
BEGIN DESCRIPTION:
CRYSTAL CREEK TRIBUTARY NO 6_2 4.0
END DESCRIPTION:
XS GIS Cut Line= 3
      3853591.65     10134982.02      3853049.82     10135245.06
      3852488.16     10135323.42
#Sta/Elev= 30
  4397.7  244.03    4602   240.2  4624.2  239.03    4661  239.44  4768.3  237.21
  4865.5  236.65  4879.9  237.33  4892.2  236.19  4914.8  236.58  4968.8  234.94
  4982.5  233.47  4991.1  231.19  4996.6  227.68  5012.2  229.12  5018.1231.2322
  5022.2   232.7  5042.4  234.83  5079.7   234.6    5103  234.56  5113.1  233.16
  5133.2  234.91  5205.4  235.84  5254.4  236.45  5360.4   240.4  5436.2   242.1
  5441.4  243.11  5446.4  242.61  5456.3  243.53  5506.8  242.81  5567.1  244.52
#Mann= 7 ,-1 , 0
  4397.7     .11       0  4865.5     .17       0  4991.1     .09       0
  5018.1     .11       0  5079.7     .17       0  5205.4     .11       0
  5360.4     .17       0
Bank Sta=4991.1,5018.1
XS Rating Curve= 0 ,0
Exp/Cntr=0.3,0.1

Type RM Length L Ch R = 1 ,1500    ,500,500,500
BEGIN DESCRIPTION:
CRYSTAL CREEK TRIBUTARY NO 6_2 3.0
END DESCRIPTION:
XS GIS Cut Line= 3
      3853491.13      10134686.3      3852793.52     10134822.58
      3852347.92     10135061.27
#Sta/Elev= 30
  4289.2  243.99  4374.1  242.68  4414.8  242.77  4493.9  240.94  4537.1     241
    4588  239.35  4598.5  239.62  4771.4  236.29  4781.6   235.5  4916.5  233.92
  4975.2  232.19  4985.4  229.46  4995.2   226.5    5000   226.5  5002.3  225.37
  5005.8  225.37 5013.85229.5335  5017.8  231.38    5023  232.03  5047.9  233.36
  5063.2  233.18  5091.8  235.18  5108.1  235.05  5124.8  236.27    5130   236.7
  5135.7  236.03  5165.2  237.36  5217.7  238.29  5335.4   239.5  5505.5  245.16
#Mann= 6 ,-1 , 0
  4289.2     .11       0  4598.5     .17       0  4985.4     .09       0
 5013.85     .17       0    5023     .11       0  5124.8     .17       0
Bank Sta=4985.4,5013.85
XS Rating Curve= 0 ,0
Exp/Cntr=0.3,0.1

Type RM Length L Ch R = 1 ,1000    ,500,500,500
BEGIN DESCRIPTION:
CRYSTAL CREEK TRIBUTARY NO 6_2 2.0
END DESCRIPTION:
XS GIS Cut Line= 3
      3853296.01     10134210.75      3852706.22     10134347.34
      3852231.95     10134741.53
#Sta/Elev= 30
  4394.6  242.29  4485.1  240.26  4556.9  241.66    4588  241.31  4690.2  239.41
  4803.3  235.83  4865.7  235.57  4874.4  234.83  4977.8  231.89  4988.1  229.69
 4990.23227.3134  4995.4  221.52  5002.2  222.02  5015.5  227.41  5029.8  233.13
  5036.9  234.05  5058.5  230.59  5114.9  230.69  5157.4  231.59  5257.7  235.65
  5278.5  234.84    5285  235.37  5292.9  234.55  5342.3  235.52    5371  234.68
    5492  236.97  5498.6  236.34  5563.9  238.46    5591  238.12  5616.7  239.47
#Mann= 7 ,-1 , 0
  4394.6     .17       0    4588     .11       0  4690.2     .17       0
  4874.4     .11       0 4990.23     .09       0  5015.5     .17       0
  5563.9     .11       0
#XS Ineff= 2 , 0
                          5036.9          234.05
Permanent Ineff=
       F       F
Bank Sta=4990.23,5015.5
XS Rating Curve= 0 ,0
Exp/Cntr=0.3,0.1

Type RM Length L Ch R = 1 ,500     ,408,408,408
BEGIN DESCRIPTION:
CRYSTAL CREEK TRIBUTARY NO 6_2 1.0
END DESCRIPTION:
XS GIS Cut Line= 3
      3853195.76     10133820.22      3852578.16     10133873.51
      3851997.88     10134264.66
#Sta/Elev= 30
  4380.1  240.76  4468.3  239.22  4488.4   237.5  4498.4  238.91  4518.5  238.85
  4548.6  236.81  4588.8  236.64  4750.3  232.72  4789.5  231.18  4879.9  230.12
  4980.2  226.81  4995.9  222.06  5005.5  222.61  5020.5   227.8  5026.5  227.64
  5035.4  229.02  5041.5  228.72  5048.6  229.51  5121.7  231.34  5185.4  232.12
  5303.8   235.1  5386.3  236.25  5467.2  235.02  5488.2  234.03  5567.2  234.84
    5579  233.09  5590.1  234.03  5632.1  234.65  5668.1  233.23  5699.8  233.37
#Mann= 7 ,-1 , 0
  4380.1     .11       0  4750.3     .17       0  4980.2     .09       0
  5020.5     .11       0  5121.7     .17       0  5303.8     .11       0
    5579     .17       0
Bank Sta=4980.2,5020.5
XS Rating Curve= 0 ,0
Exp/Cntr=0.3,0.1

Type RM Length L Ch R = 1 ,200     ,0,0,0
XS GIS Cut Line= 3
      3853138.76     10133230.72      3852535.96     10133476.89
      3852152.65     10134031.07
#Sta/Elev= 30
       0  239.13   141.2  236.81   277.5  232.59     379     231   461.9  228.32
   491.4   228.3   515.4  227.01   627.7  225.84   638.3  223.78   646.3  220.87
   650.1   218.6   653.9   218.6   659.4  223.26   668.2  223.12   674.3  225.19
   689.2  225.17   695.3  226.73     725  227.61   731.1  226.07   760.8  226.35
   832.5     229   853.4  228.69   954.8  230.72   960.9  229.98  1005.5  231.14
  1011.5  230.66  1056.1  233.52  1069.6  233.37  1148.7  236.32  1324.8  236.39
#Mann= 3 , 0 , 0
       0     .17       0   627.7     .09       0   695.3     .17       0
#XS Ineff= 2 , 0
                          725.04          227.62
Permanent Ineff=
       F       F
Bank Sta=627.7,695.3
XS Rating Curve= 0 ,0
Exp/Cntr=0.3,0.1

Chan Stop Cuts=-1
Use User Specified Reach Order=0
Composite Channel Slope=5

--- CRYSTAL CREEK TRIBUTARY NO 6_2.g10 (geometry) ---

Geom Title=Existing Conditions
Program Version=4.10

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
River Reach=CRYSTAL CREEK TR,Reach-1

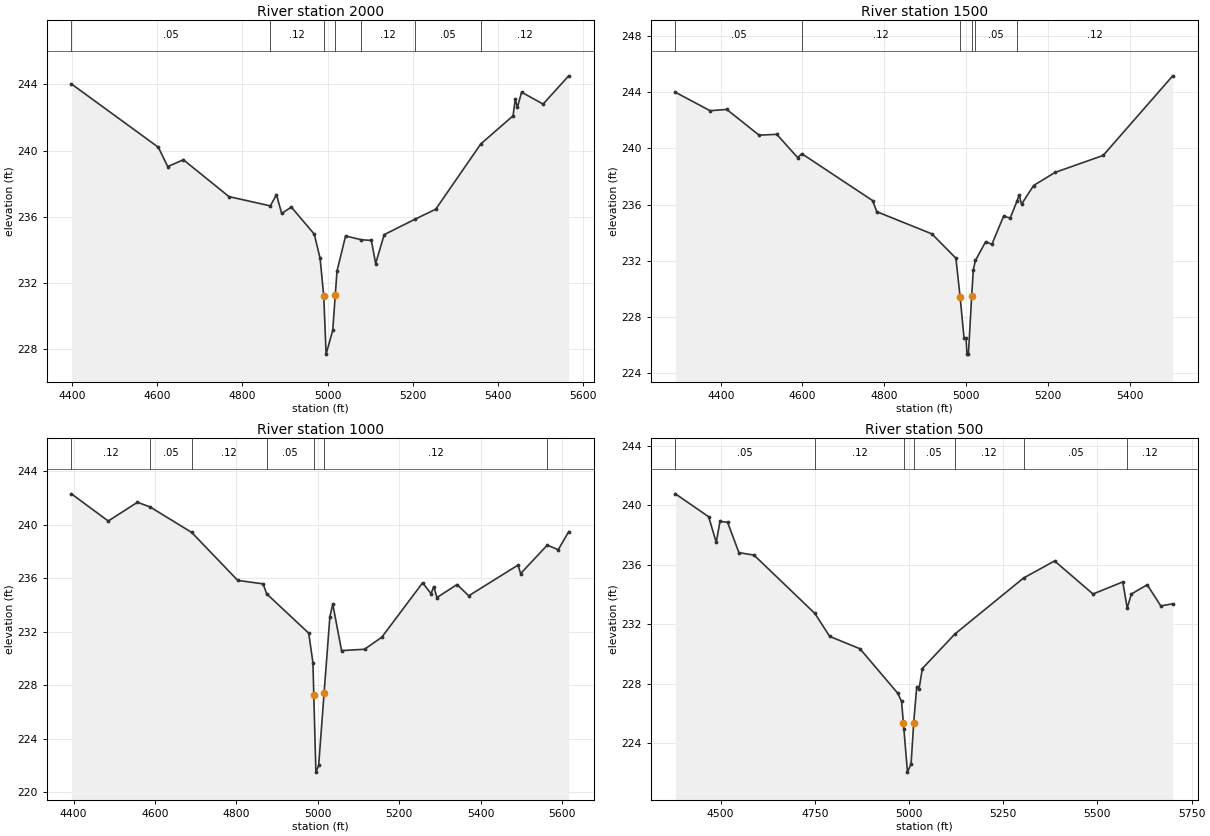
Type RM Length L Ch R = 1 ,2000    ,500,500,500
BEGIN DESCRIPTION:
CRYSTAL CREEK TRIBUTARY NO 6_2 4.0
END DESCRIPTION:
XS GIS Cut Line= 3
      3853591.65     10134982.02      3853049.82     10135245.06
      3852488.16     10135323.42
#Sta/Elev= 30
  4397.7  244.03    4602   240.2  4624.2  239.03    4661  239.44  4768.3  237.21
  4865.5  236.65  4879.9  237.33  4892.2  236.19  4914.8  236.58  4968.8  234.94
  4982.5  233.47  4991.1  231.19  4996.6  227.68  5012.2  229.12  5018.1 231.232
  5022.2   232.7  5042.4  234.83  5079.7   234.6    5103  234.56  5113.1  233.16
  5133.2  234.91  5205.4  235.84  5254.4  236.45  5360.4   240.4  5436.2   242.1
  5441.4  243.11  5446.4  242.61  5456.3  243.53  5506.8  242.81  5567.1  244.52
#Mann= 7 ,-1 , 0
  4397.7     .05       0  4865.5     .12       0  4991.1     .07       0
  5018.1     .05       0  5079.7     .12       0  5205.4     .05       0
  5360.4     .12       0
Bank Sta=4991.1,5018.1
XS Rating Curve= 0 ,0
Exp/Cntr=0.3,0.1

Type RM Length L Ch R = 1 ,1500    ,500,500,500
BEGIN DESCRIPTION:
CRYSTAL CREEK TRIBUTARY NO 6_2 3.0
END DESCRIPTION:
XS GIS Cut Line= 3
      3853491.13      10134686.3      3852793.52     10134822.58
      3852347.92     10135061.27
#Sta/Elev= 30
  4289.2  243.99  4374.1  242.68  4414.8  242.77  4493.9  240.94  4537.1     241
    4588  239.35  4598.5  239.62  4771.4  236.29  4781.6   235.5  4916.5  233.92
  4975.2  232.19  4985.4  229.46  4995.2   226.5    5000   226.5  5002.3  225.37
  5005.8  225.37 5013.85 229.534  5017.8  231.38    5023  232.03  5047.9  233.36
  5063.2  233.18  5091.8  235.18  5108.1  235.05  5124.8  236.27    5130   236.7
  5135.7  236.03  5165.2  237.36  5217.7  238.29  5335.4   239.5  5505.5  245.16
#Mann= 6 ,-1 , 0
  4289.2     .05       0  4598.5     .12       0  4985.4     .07       0
 5013.85     .12       0    5023     .05       0  5124.8     .12       0
Bank Sta=4985.4,5013.85
XS Rating Curve= 0 ,0
Exp/Cntr=0.3,0.1

Type RM Length L Ch R = 1 ,1000    ,500,500,500
BEGIN DESCRIPTION:
CRYSTAL CREEK TRIBUTARY NO 6_2 2.0
END DESCRIPTION:
XS GIS Cut Line= 3
      3853296.01     10134210.75      3852706.22     10134347.34
      3852231.95     10134741.53
#Sta/Elev= 30
  4394.6  242.29  4485.1  240.26  4556.9  241.66    4588  241.31  4690.2  239.41
  4803.3  235.83  4865.7  235.57  4874.4  234.83  4977.8  231.89  4988.1  229.69
 4990.23 227.313  4995.4  221.52  5002.2  222.02  5015.5  227.41  5029.8  233.13
  5036.9  234.05  5058.5  230.59  5114.9  230.69  5157.4  231.59  5257.7  235.65
  5278.5  234.84    5285  235.37  5292.9  234.55  5342.3  235.52    5371  234.68
    5492  236.97  5498.6  236.34  5563.9  238.46    5591  238.12  5616.7  239.47
#Mann= 7 ,-1 , 0
  4394.6     .12       0    4588     .05       0  4690.2     .12       0
  4874.4     .05       0 4990.23     .07       0  5015.5     .12       0
  5563.9     .05       0
Bank Sta=4990.23,5015.5
XS Rating Curve= 0 ,0
Exp/Cntr=0.3,0.1

Type RM Length L Ch R = 1 ,500     ,0,0,0
BEGIN DESCRIPTION:
CRYSTAL CREEK TRIBUTARY NO 6_2 1.0
END DESCRIPTION:
XS GIS Cut Line= 3
      3853195.76     10133820.22      3852578.16     10133873.51
      3851997.88     10134264.66
#Sta/Elev= 30
  4380.1  240.76  4468.3  239.22  4488.4   237.5  4498.4  238.91  4518.5  238.85
  4548.6  236.81  4588.8  236.64  4750.3  232.72  4789.5  231.18  4869.8  230.35
  4970.2  227.36  4980.2  226.81 4985.03 225.369  4986.3  224.99  4995.9  222.06
  5005.5  222.61  5012.4  225.39  5020.5   227.8  5026.5  227.64  5035.4  229.02
  5121.7  231.34  5303.8   235.1  5386.3  236.25  5488.2  234.03  5567.2  234.84
    5579  233.09  5590.1  234.03  5632.1  234.65  5668.1  233.23  5699.8  233.37
#Mann= 7 ,-1 , 0
  4380.1     .05       0  4750.3     .12       0  4986.3     .07       0
  5012.4     .05       0  5121.7     .12       0  5303.8     .05       0
    5579     .12       0
Bank Sta=4985.03,5012.4
XS Rating Curve= 0 ,0
Exp/Cntr=0.3,0.1