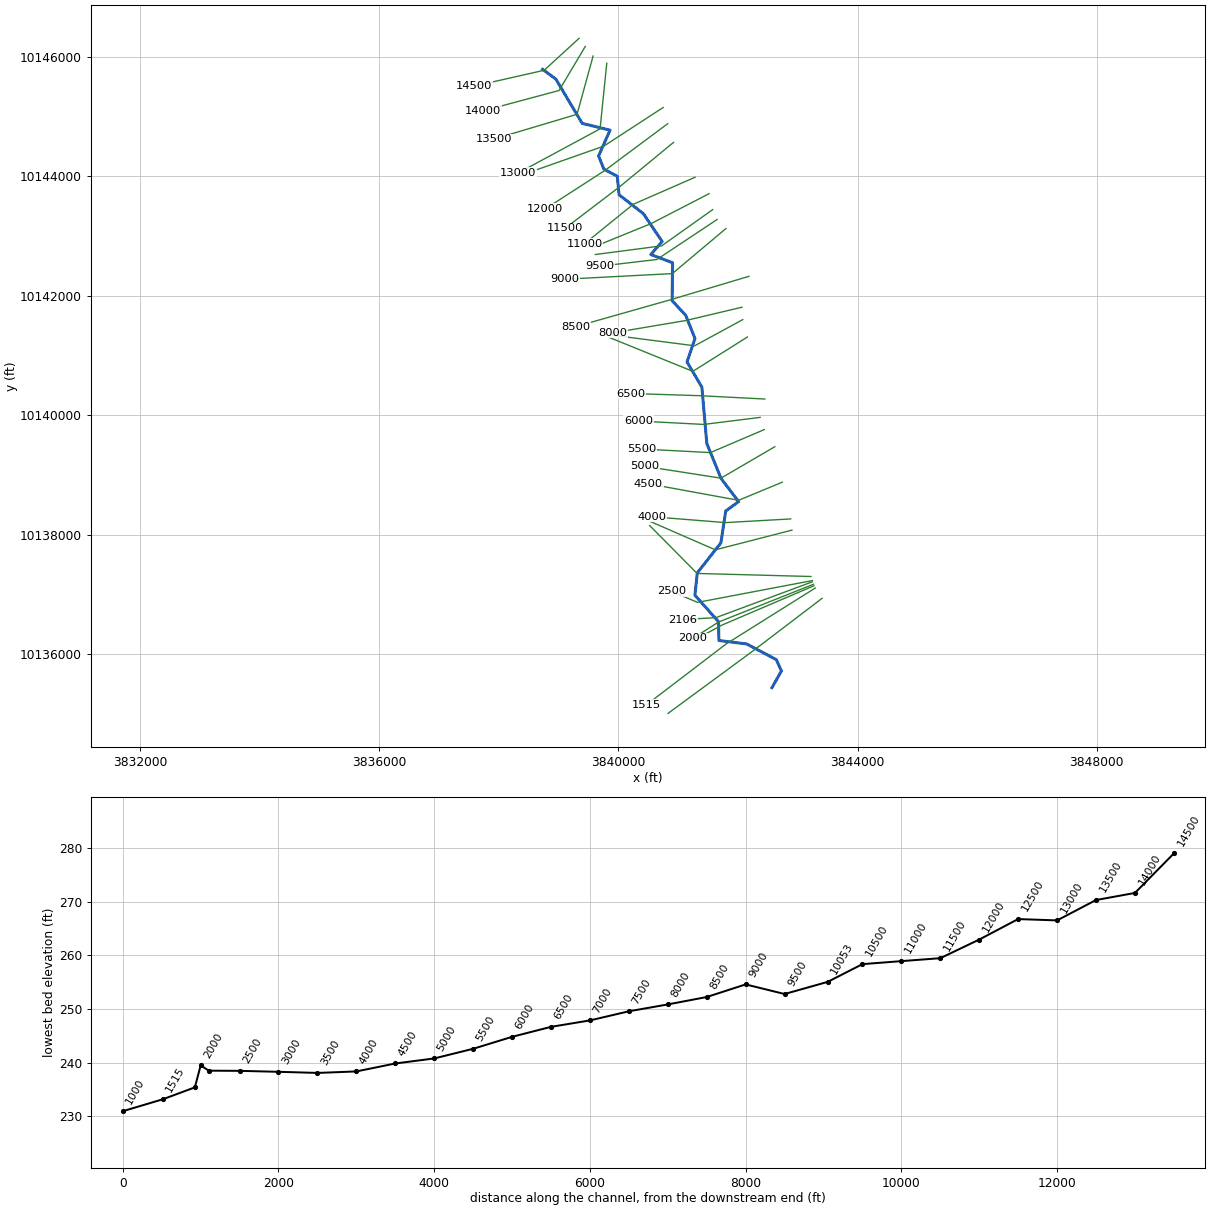
--- CRYSTAL CREEK TRIBUTARY NO 7.prj (project) ---

Proj Title=CRYSTAL CREEK TRIBUTARY NO 7 Base Level Engineering
Current Plan=p01
Default Exp/Contr=0.3,0.1
English Units
Geom File=g01
Flow File=f01
Plan File=p01
Y Axis Title=Elevation
X Axis Title(PF)=Main Channel Distance
X Axis Title(XS)=Station
BEGIN DESCRIPTION:
CRYSTAL CREEK TRIBUTARY NO 7
END DESCRIPTION:
DSS Export Rating Curves= 0
DSS Export Rating Curve Sorted= 0
DSS Export Volume Flow Curves= 0
DXF OffsetX= 0
DXF OffsetY= 0
DXF ScaleX= 1
DXF ScaleY= 10

--- CRYSTAL CREEK TRIBUTARY NO 7.p01 (plan) ---

Plan Title=Multiple Run
Short Identifier=Multiple
Geom File=g01
Flow File=f01
Subcritical Flow
K Sum by GR= 0
Std Step Tol= 0.01
Critical Tol= 0.01
Num of Std Step Trials= 20
Max Error Tol= 0.3
Flow Tol Ratio= 0.001
Split Flow NTrial= 30
Split Flow Tol= 0.02
Split Flow Ratio= 0.02
Log Output Level= 0
Friction Slope Method= 1
Unsteady Friction Slope Method= 2
Unsteady Bridges Friction Slope Method= 1
Parabolic Critical Depth
Global Vel Dist=  1 , 1 , 1
Global Log Level= 0
CheckData=True
Encroach Param= -1, 0, 0, 0
BEGIN DESCRIPTION:
Multiple Run
END DESCRIPTION:

--- CRYSTAL CREEK TRIBUTARY NO 7.f01 (steady flow) ---

Flow Title=Multiple
Program Version=4.10
Number of Profiles= 7
Profile Names=10-year,25-year,50-year,1pct_min,100-year,1pct_plu,500-year
River Rch & RM=CRYSTAL CREEK TR,Reach-1         ,14500
     731     989    1337     594    1795    5421    3340
River Rch & RM=CRYSTAL CREEK TR,Reach-1         ,8000
     907    1234    1673     744    2248    6789    4199
River Rch & RM=CRYSTAL CREEK TR,Reach-1         ,1515
    2903    4154    5825    2670    8064   24353   15996
River Rch & RM=CRYSTAL CREEK TR,Reach-1         ,1000
    2903    4154    5825    2670    8064   24353   15996
River Rch & RM=CRYSTAL CREEK TR,Reach-1         ,500
    2903    4154    5825    2670    8064   24353   15996
Boundary for River Rch & Prof#=CRYSTAL CREEK TR,Reach-1         , 1
Up Type= 0
Dn Type= 3
Dn Slope=0.005
Boundary for River Rch & Prof#=CRYSTAL CREEK TR,Reach-1         , 2
Up Type= 0
Dn Type= 3
Dn Slope=0.005
Boundary for River Rch & Prof#=CRYSTAL CREEK TR,Reach-1         , 3
Up Type= 0
Dn Type= 3
Dn Slope=0.005
Boundary for River Rch & Prof#=CRYSTAL CREEK TR,Reach-1         , 4
Up Type= 0
Dn Type= 3
Dn Slope=0.005
Boundary for River Rch & Prof#=CRYSTAL CREEK TR,Reach-1         , 5
Up Type= 0
Dn Type= 3
Dn Slope=0.005
Boundary for River Rch & Prof#=CRYSTAL CREEK TR,Reach-1         , 6
Up Type= 0
Dn Type= 3
Dn Slope=0.005
Boundary for River Rch & Prof#=CRYSTAL CREEK TR,Reach-1         , 7
Up Type= 0
Dn Type= 3
Dn Slope=0.005
DSS Import GetInterval= 0
DSS Import GetPeak= 0
DSS Import FillOption= 0

--- CRYSTAL CREEK TRIBUTARY NO 7.g01 (geometry) ---

Geom Title=Existing Conditions
Program Version=4.10

River Reach=CRYSTAL CREEK TR,Reach-1
Reach XY= 30
      3838733.24     10145791.86      3838954.27     10145629.52
      3839395.48     10144887.97      3839861.14     10144774.07
      3839669.89     10144343.65      3839757.76     10144122.09
      3839981.73     10144003.51      3840012.51     10143692.81
      3840418.19     10143377.18      3840732.82     10142910.86
      3840542.93     10142692.96      3840906.87      10142555.3
      3840899.56     10141919.31      3841125.14     10141678.47
      3841281.58     10141286.62      3841148.61     10140894.94
      3841397.16     10140473.42       3841479.7     10139529.37
      3841718.77     10138943.23       3842011.9     10138557.97
      3841795.82     10138400.52      3841715.46      10137867.6
       3841320.5     10137365.47      3841280.43      10136991.5
      3841675.39     10136547.61      3841682.01     10136233.39
       3842145.7     10136175.39      3842641.77     10135912.94
      3842727.71     10135724.01      3842568.49     10135443.19

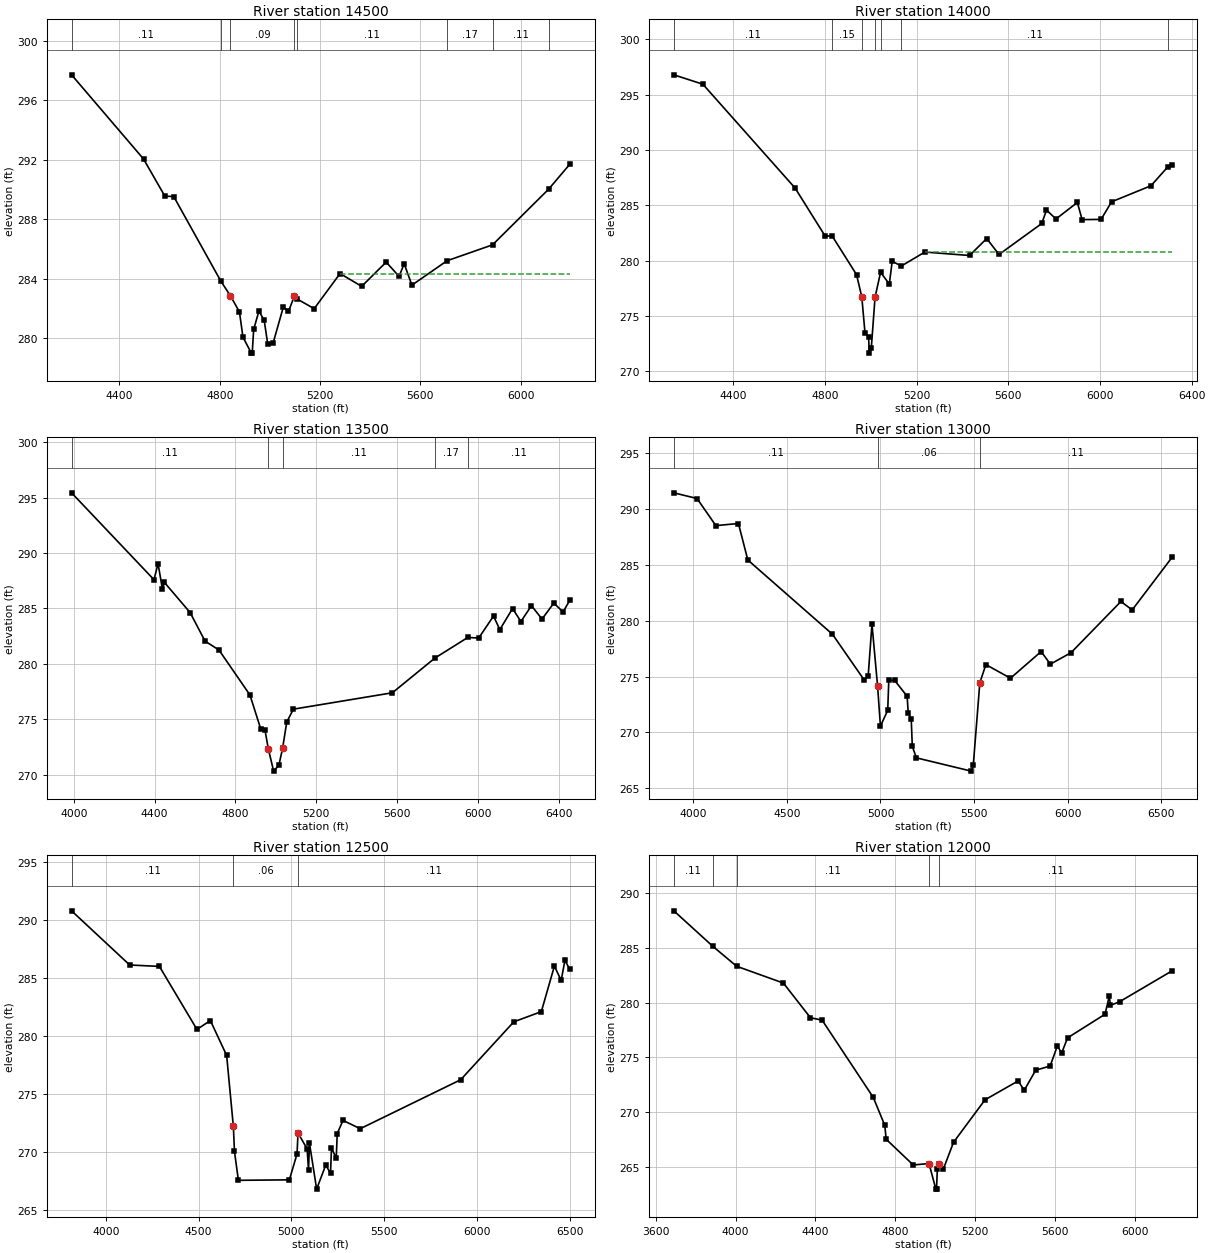
Type RM Length L Ch R = 1 ,14500   ,500,500,500
BEGIN DESCRIPTION:
CRYSTAL CREEK TRIBUTARY NO 7 29.0
END DESCRIPTION:
XS GIS Cut Line= 3
      3839343.31     10146311.05      3838760.08     10145776.86
      3837593.64     10145512.59
#Sta/Elev= 30
  4209.1  297.72  4496.1  292.06  4581.2  289.56  4616.4  289.54    4804  283.86
  4842.7  282.86  4878.5  281.78  4892.6  280.08    4926  279.01  4929.5  279.01
  4935.2   280.6  4956.2  281.84  4977.1  281.22  4991.3  279.63  5012.5  279.67
  5053.7  282.12  5074.1  281.81  5096.9  282.82  5107.3  282.66  5176.6     282
  5279.7  284.36  5365.9   283.5  5463.7  285.13    5515  284.17  5535.5  285.02
  5566.2  283.58  5706.4  285.22  5887.8  286.29  6111.4  290.03    6196  291.71
#Mann= 8 ,-1 , 0
  4209.1     .11       0    4804     .17       0  4842.7     .09       0
  5096.9     .15       0  5107.3     .11       0  5706.4     .17       0
  5887.8     .11       0  6111.4     .17       0
#XS Ineff= 2 , 0
                         5279.66          284.36
Permanent Ineff=
       F       F
Bank Sta=4842.7,5096.9
XS Rating Curve= 0 ,0
Exp/Cntr=0.3,0.1

Type RM Length L Ch R = 1 ,14000   ,500,500,500
BEGIN DESCRIPTION:
CRYSTAL CREEK TRIBUTARY NO 7 28.0
END DESCRIPTION:
XS GIS Cut Line= 3
      3839447.21     10146175.72      3839008.63     10145437.93
      3837738.85     10145097.58
#Sta/Elev= 30
  4141.7  296.78  4268.4  295.93  4670.6  286.55  4800.2  282.26  4833.5  282.18
  4938.5  278.73  4961.4  276.72  4975.5  273.44  4991.1   273.1  4994.1  271.64
    5003  272.14 5019.29276.7036  5043.4  278.94  5081.4  277.88    5094  279.93
  5133.9  279.51  5236.3  280.77  5431.3  280.46  5506.1  281.99  5559.9  280.55
  5746.2  283.35  5766.9  284.56  5808.3  283.76  5901.5  285.25  5922.2   283.7
    6005  283.72  6050.8  285.31  6222.5  286.76  6294.9  288.44  6314.6  288.59
#Mann= 7 ,-1 , 0
  4141.7     .11       0  4833.5     .15       0  4961.4     .09       0
 5019.29     .15       0  5043.4     .17       0  5133.9     .11       0
  6294.9     .17       0
#XS Ineff= 2 , 0
                         5236.27          280.77
Permanent Ineff=
       F       F
Bank Sta=4961.4,5019.29
XS Rating Curve= 0 ,0
Exp/Cntr=0.3,0.1

Type RM Length L Ch R = 1 ,13500   ,500,500,500
BEGIN DESCRIPTION:
CRYSTAL CREEK TRIBUTARY NO 7 27.0
END DESCRIPTION:
XS GIS Cut Line= 3
      3839577.41     10146014.26       3839309.7     10145039.76
      3837915.99     10144623.64
#Sta/Elev= 30
  3989.4  295.43  4397.2  287.59  4417.3  289.05  4438.6  286.76    4449  287.34
  4575.7  284.63  4649.8  282.05  4718.6  281.25  4871.9  277.19    4926  274.08
    4946  274.06 4962.61272.3396    4989  270.32  5015.2  270.86  5033.2  272.37
  5054.1  274.75  5086.7  275.91  5576.6  277.39    5787  280.52  5949.7  282.38
  6003.8  282.33  6076.9  284.31  6108.2  283.09  6171.2  284.99  6212.5  283.82
  6264.7  285.25  6316.9  284.04  6375.2  285.48  6421.3  284.68  6454.5  285.75
#Mann= 5 ,-1 , 0
  3989.4     .11       0 4962.61     .06       0  5033.2     .11       0
    5787     .17       0  5949.7     .11       0
Bank Sta=4962.61,5033.2
XS Rating Curve= 0 ,0
Exp/Cntr=0.3,0.1

Type RM Length L Ch R = 1 ,13000   ,500,500,500
BEGIN DESCRIPTION:
CRYSTAL CREEK TRIBUTARY NO 7 26.0
END DESCRIPTION:
XS GIS Cut Line= 3
      3839806.58     10145894.46      3839694.51     10144795.96
      3838322.67     10144056.17
#Sta/Elev= 30
  3895.8  291.47  4019.8  290.96  4120.3  288.53    4241  288.72  4291.2  285.45
  4743.6  278.79  4913.6  274.68  4934.5  275.07  4954.7   279.7  4984.8  274.13
  4999.9  270.55  5038.9  271.97  5044.6  274.67  5075.7  274.66  5142.7  273.23
  5148.4  271.76  5164.6  271.17  5170.3  268.73  5192.2  267.71  5485.6  266.52
  5496.1  267.05  5531.2  274.45  5563.6  276.07    5695  274.85  5858.8  277.24
  5908.2  276.11  6018.7  277.14  6285.3  281.73  6345.3  280.97  6558.6  285.69
#Mann= 3 , 0 , 0
  3895.8     .11       0  4984.8     .06       0  5531.2     .11       0
Bank Sta=4984.8,5531.2
XS Rating Curve= 0 ,0
Exp/Cntr=0.3,0.1

Type RM Length L Ch R = 1 ,12500   ,500,500,500
BEGIN DESCRIPTION:
CRYSTAL CREEK TRIBUTARY NO 7 25.0
END DESCRIPTION:
XS GIS Cut Line= 3
      3840749.91     10145153.89      3839757.93     10144507.49
      3838343.06     10144009.06
#Sta/Elev= 30
    3816  290.76  4129.1  286.09  4289.1  285.97  4491.3  280.54  4563.7   281.3
  4651.3   278.3  4687.5  272.18  4693.5  270.02  4714.6  267.53  4989.2  267.57
  5030.5   269.8  5035.8  271.61  5084.9  270.24  5092.4  268.42  5097.7  270.72
  5136.2  266.77  5185.2  268.85  5210.9  268.13  5216.2  270.31  5241.8  269.44
  5247.1  271.56  5278.1  272.69  5371.2  271.98  5912.2   276.2  6198.2  281.19
  6346.6  282.07  6417.1     286  6453.4  284.76  6473.8   286.5  6500.1  285.71
#Mann= 3 , 0 , 0
    3816     .11       0  4687.5     .06       0  5035.8     .11       0
Bank Sta=4687.5,5035.8
XS Rating Curve= 0 ,0
Exp/Cntr=0.3,0.1

Type RM Length L Ch R = 1 ,12000   ,500,500,500
BEGIN DESCRIPTION:
CRYSTAL CREEK TRIBUTARY NO 7 24.0
END DESCRIPTION:
XS GIS Cut Line= 3
      3840825.71     10144882.34      3839775.26     10144099.95
      3838777.97     10143455.48
#Sta/Elev= 30
  3690.2  288.41  3885.2  285.17  4004.8  283.34  4239.4   281.8  4374.9  278.63
  4433.4  278.41  4689.8  271.34  4747.4  268.79  4754.5  267.51    4890  265.16
  4969.3  265.29  5003.3  262.95  5006.8  262.95    5011  264.83  5020.2  265.25
  5041.3   264.8  5092.2  267.24  5249.8  271.12    5416  272.85  5446.4  271.99
  5503.8  273.83  5576.3  274.21  5612.6  276.06  5633.7  275.39  5663.7  276.79
  5851.4  278.95  5872.6   280.6  5878.5  279.76    5924  280.09  6187.4  282.92
#Mann= 5 ,-1 , 0
  3690.2     .11       0  3885.2     .17       0  4004.8     .11       0
  4969.3     .06       0  5020.2     .11       0
Bank Sta=4969.3,5020.2
XS Rating Curve= 0 ,0
Exp/Cntr=0.3,0.1

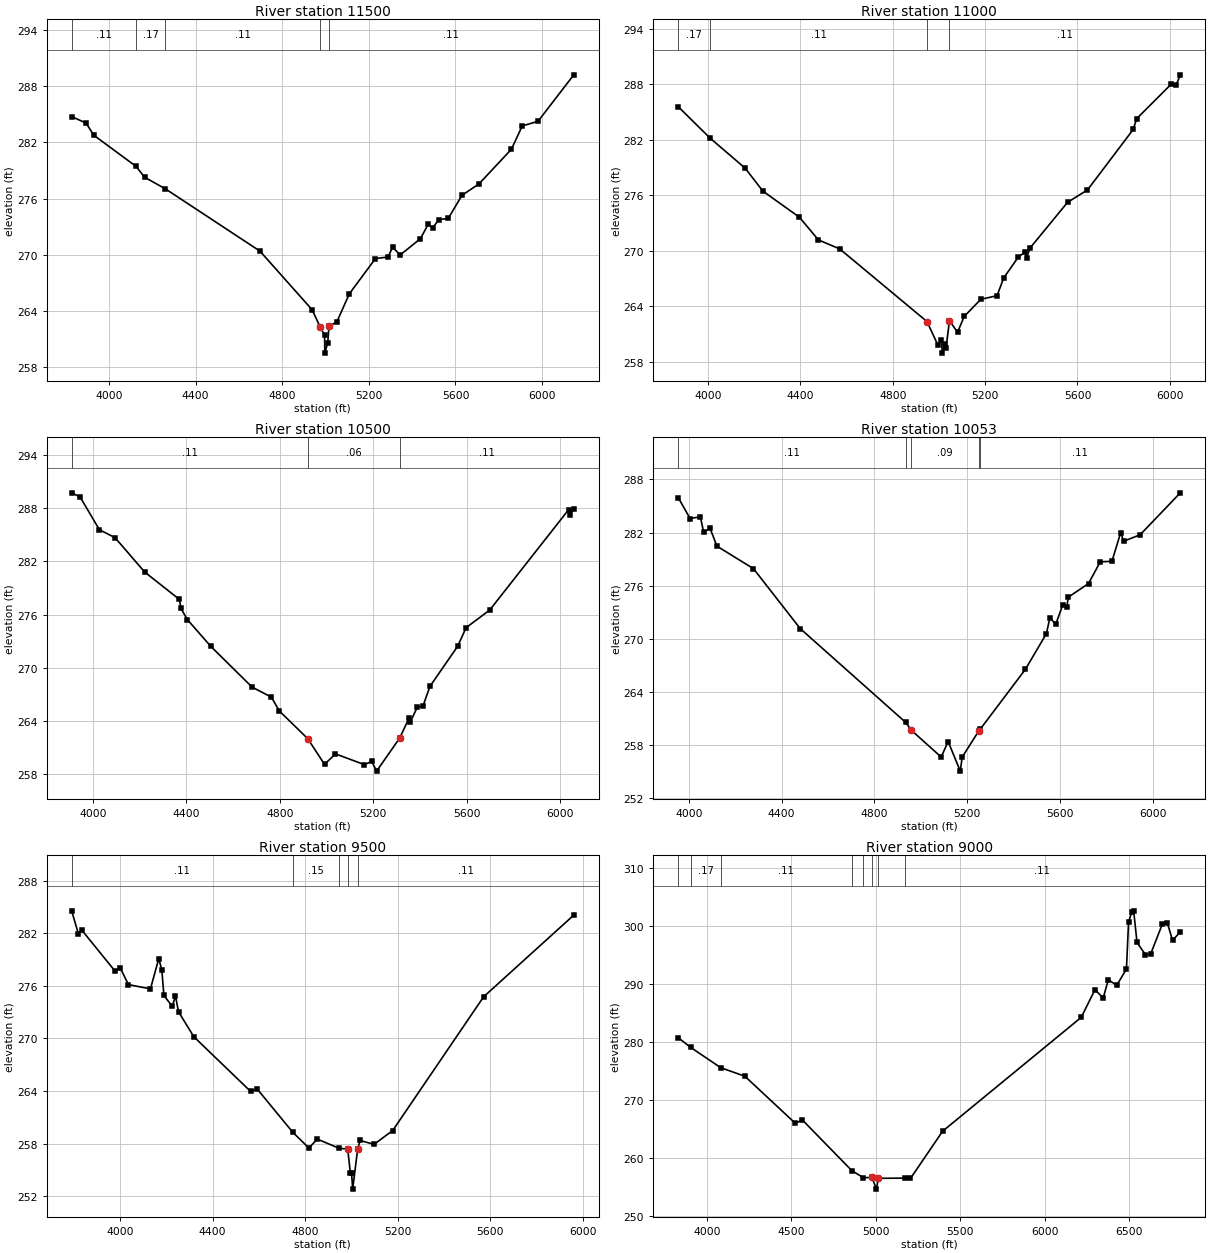
Type RM Length L Ch R = 1 ,11500   ,500,500,500
BEGIN DESCRIPTION:
CRYSTAL CREEK TRIBUTARY NO 7 23.0
END DESCRIPTION:
XS GIS Cut Line= 3
      3840922.87     10144569.79      3840018.45     10143824.24
      3839106.91     10143129.36
#Sta/Elev= 30
  3827.9  284.76  3894.7  284.06  3929.8  282.77  4125.1  279.44  4164.4  278.28
  4261.1  277.03  4697.3  270.38  4938.3  264.11  4974.9  262.29  4995.7   261.4
  4996.8  259.48  5010.3   260.6 5015.96 262.371  5051.9   262.8    5110  265.82
  5230.6  269.59  5288.8  269.75  5309.6   270.8    5345  269.97  5438.5  271.72
  5473.8  273.24  5494.6  272.87  5523.7  273.75  5566.6  273.87  5629.8  276.34
  5708.7  277.57  5858.4  281.27  5908.3  283.76    5981  284.25  6146.2  289.22
#Mann= 5 ,-1 , 0
  3827.9     .11       0  4125.1     .17       0  4261.1     .11       0
  4974.9     .07       0 5015.96     .11       0
Bank Sta=4974.9,5015.96
XS Rating Curve= 0 ,0
Exp/Cntr=0.3,0.1

Type RM Length L Ch R = 1 ,11000   ,500,500,500
BEGIN DESCRIPTION:
CRYSTAL CREEK TRIBUTARY NO 7 22.0
END DESCRIPTION:
XS GIS Cut Line= 3
      3841283.99     10143986.47      3840249.61     10143533.78
       3839437.2     10142875.71
#Sta/Elev= 30
  3870.9  285.59  4009.8  282.17  4161.4  278.92  4237.8  276.45  4395.9  273.63
    4478  271.18  4570.5   270.2  4948.6  262.34  4995.4  259.81  5010.5  260.38
  5015.2  258.93  5024.9  259.93  5031.3  259.53  5045.7  262.43  5080.9  261.19
  5109.6   262.9  5181.5  264.75  5251.9  265.14  5280.6  267.06  5344.6  269.34
  5373.3  269.85  5379.8  269.22  5394.2  270.28  5557.2  275.24  5643.5  276.58
  5841.8  283.13  5856.2  284.28  6006.1  288.02  6027.2   287.9  6045.5  289.03
#Mann= 4 ,-1 , 0
  3870.9     .17       0  4009.8     .11       0  4948.6     .06       0
  5045.7     .11       0
Bank Sta=4948.6,5045.7
XS Rating Curve= 0 ,0
Exp/Cntr=0.3,0.1

Type RM Length L Ch R = 1 ,10500   ,447,447,447
BEGIN DESCRIPTION:
CRYSTAL CREEK TRIBUTARY NO 7 21.0
END DESCRIPTION:
XS GIS Cut Line= 3
      3841517.83     10143711.06      3840548.47     10143210.86
      3839567.84     10142811.07
#Sta/Elev= 30
  3909.2   289.7  3945.2  289.24  4028.2  285.54  4094.7  284.66    4222  280.78
  4370.5   277.7  4377.1  276.68  4404.9  275.42  4504.4  272.43  4681.7  267.83
  4764.4   266.7  4798.1  265.15  4919.8  262.03  4991.9  259.13  5038.8  260.31
  5162.7   259.1  5193.9  259.46  5214.9  258.37  5313.8   262.1  5354.3  264.37
  5359.7  263.93  5389.4  265.59  5413.2  265.69  5443.4  267.92  5562.2  272.44
  5597.7  274.51  5699.3  276.51  6037.4  287.82  6044.3  287.26    6059  287.91
#Mann= 3 , 0 , 0
  3909.2     .11       0  4919.8     .06       0  5313.8     .11       0
Bank Sta=4919.8,5313.8
XS Rating Curve= 0 ,0
Exp/Cntr=0.3,0.1

Type RM Length L Ch R = 1 ,10053   ,553,553,553
BEGIN DESCRIPTION:
CRYSTAL CREEK TRIBUTARY NO 7 20.0
END DESCRIPTION:
XS GIS Cut Line= 3
      3841577.43     10143443.96      3840725.07     10142838.18
      3839615.62     10142693.08
#Sta/Elev= 30
  3954.3  285.95  4005.7  283.58    4050  283.77  4064.2  282.03  4091.8  282.47
  4121.3  280.46  4278.8  277.92  4480.5  271.15  4935.1  260.56  4959.8  259.67
    5088  256.65  5118.2   258.4  5170.3  255.06  5178.7  256.65    5251  259.63
  5256.3  259.79    5451  266.55  5541.8  270.59  5556.5  272.37  5582.1  271.65
  5612.4  273.85  5630.3  273.61  5635.4  274.69  5723.3  276.24  5773.8  278.69
  5824.2  278.75    5862     282  5874.6  281.01  5945.9  281.75  6118.9  286.48
#Mann= 5 ,-1 , 0
  3954.3     .11       0  4935.1     .15       0  4959.8     .09       0
    5251     .15       0  5256.3     .11       0
Bank Sta=4959.8,5251
XS Rating Curve= 0 ,0
Exp/Cntr=0.3,0.1

Type RM Length L Ch R = 1 ,9500    ,500,500,500
BEGIN DESCRIPTION:
CRYSTAL CREEK TRIBUTARY NO 7 19.0
END DESCRIPTION:
XS GIS Cut Line= 3
      3841651.24     10143279.04      3840644.55      10142609.7
      3839691.08     10142497.96
#Sta/Elev= 30
  3791.1  284.56  3819.9  281.97  3834.9  282.36  3979.2  277.66  4000.2  278.09
  4036.3  276.14  4131.4  275.65  4167.4   279.1  4180.6  277.82  4189.6   274.9
  4225.7  273.66  4239.5  274.85  4252.7  273.04  4318.9  270.19  4563.7  263.96
  4592.4  264.23  4746.2  259.29  4815.9  257.49  4851.9  258.51  4947.5  257.45
  4983.3  257.39    4995  254.67    5000  254.67    5005   252.8 5026.44257.3616
    5037  258.35  5097.4  257.91  5177.9  259.49  5570.6  274.75    5960  284.07
#Mann= 5 ,-1 , 0
  3791.1     .11       0  4746.2     .15       0  4947.5     .11       0
  4983.3     .09       0 5026.44     .11       0
Bank Sta=4983.3,5026.44
XS Rating Curve= 0 ,0
Exp/Cntr=0.3,0.1

Type RM Length L Ch R = 1 ,9000    ,500,500,500
BEGIN DESCRIPTION:
CRYSTAL CREEK TRIBUTARY NO 7 18.0
END DESCRIPTION:
XS GIS Cut Line= 3
      3841798.79     10143127.12      3840902.86     10142373.42
       3839101.8     10142279.59
#Sta/Elev= 30
  3829.2   280.7  3903.2  279.02  4081.3  275.52  4224.1  274.05    4523  265.94
  4564.8  266.51  4857.8  257.78  4926.8  256.55  4977.1  256.61  5003.3  254.59
    5015  256.45  5169.8  256.49  5205.3  256.43  5395.5  264.57  6216.7   284.2
  6298.1  288.97  6346.8  287.53  6376.9  290.67  6426.9  289.73  6484.4  292.51
    6497  300.65  6517.1  302.42  6527.1  302.56  6547.1  297.11  6597.2  294.98
  6627.2  295.07  6697.3  300.29  6727.3  300.43  6757.4  297.47  6803.5  298.93
#Mann= 8 ,-1 , 0
  3829.2     .11       0  3903.2     .17       0  4081.3     .11       0
  4857.8     .17       0  4926.8     .15       0  4977.1     .09       0
    5015     .15       0  5169.8     .11       0
Bank Sta=4977.1,5015
XS Rating Curve= 0 ,0
Exp/Cntr=0.3,0.1

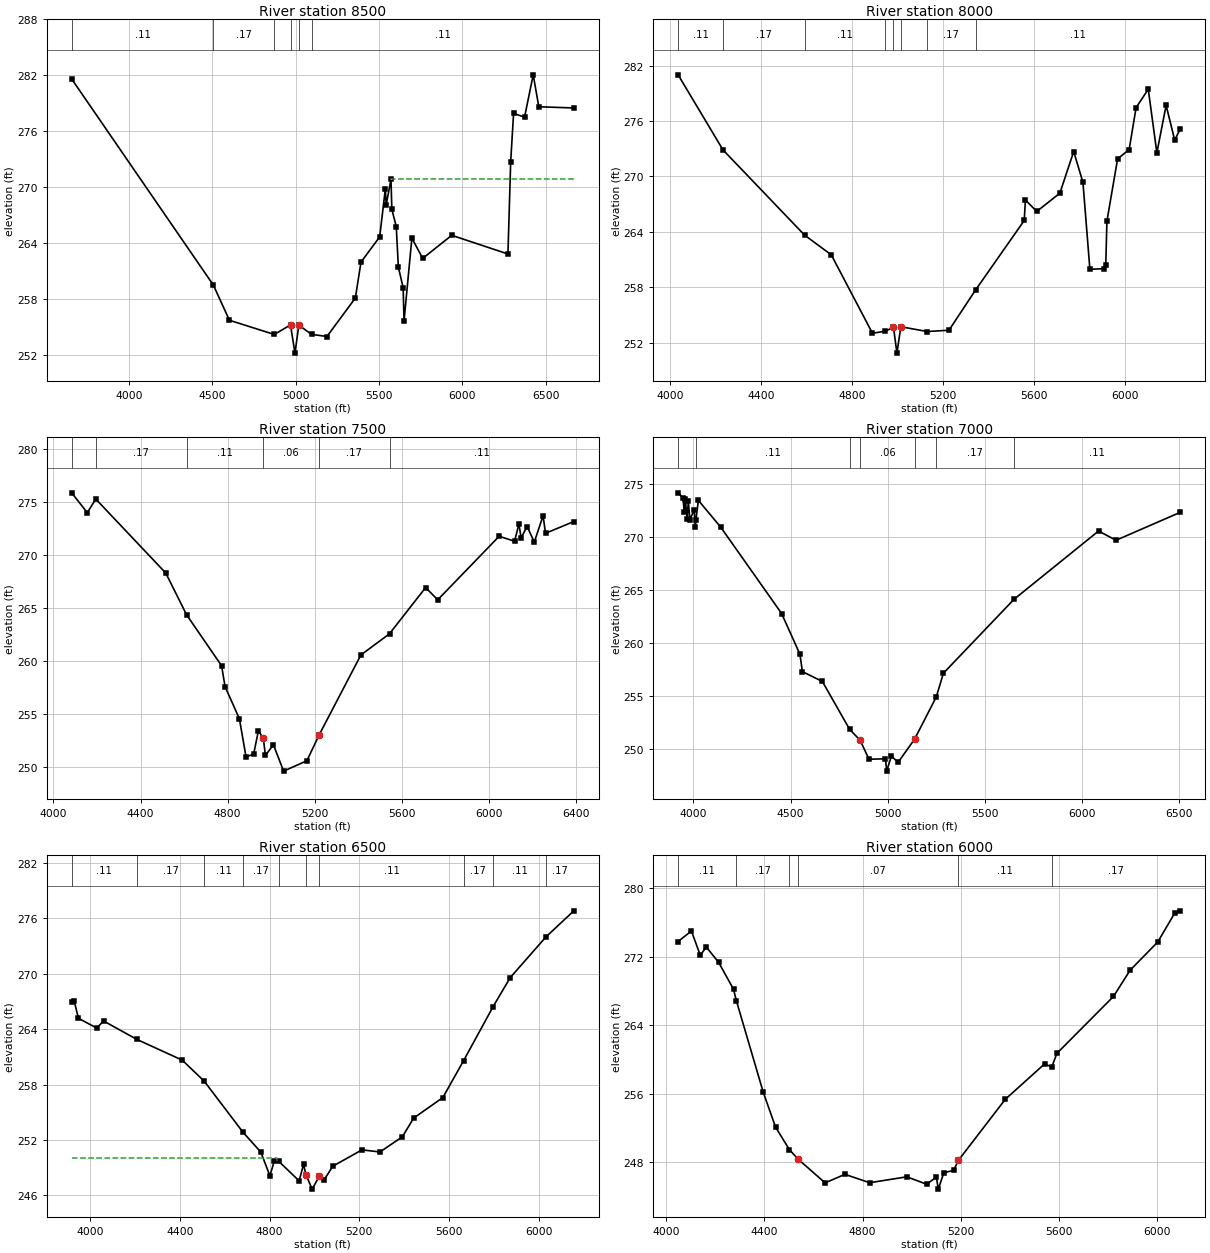
Type RM Length L Ch R = 1 ,8500    ,500,500,500
BEGIN DESCRIPTION:
CRYSTAL CREEK TRIBUTARY NO 7 17.0
END DESCRIPTION:
XS GIS Cut Line= 3
      3842185.06      10142328.5      3840898.02     10141943.45
      3839293.55     10141487.87
#Sta/Elev= 30
  3656.6  281.61  4506.6  259.52  4602.7  255.76  4871.7  254.24  4968.9  255.26
  4995.7  252.24 5018.84255.2398  5094.9  254.25  5187.3  254.02  5357.7  258.14
  5391.6  261.99  5503.7  264.69  5537.6  269.82  5542.7  268.13  5571.4  270.86
  5576.6  267.64  5603.1   265.8  5615.7  261.44  5644.4  259.25  5649.6  255.66
  5696.7  264.56  5761.7  262.39  5935.8  264.86  6272.7  262.86  6289.2  272.75
  6306.6  277.91  6372.4  277.52  6424.3  282.05  6457.8  278.63  6667.9   278.5
#Mann= 6 ,-1 , 0
  3656.6     .11       0  4506.6     .17       0  4871.7     .15       0
  4968.9     .06       0 5018.84     .15       0  5094.9     .11       0
#XS Ineff= 2 , 0
                         5571.16          270.87
Permanent Ineff=
       F       F
Bank Sta=4968.9,5018.84
XS Rating Curve= 0 ,0
Exp/Cntr=0.3,0.1

Type RM Length L Ch R = 1 ,8000    ,500,500,500
BEGIN DESCRIPTION:
CRYSTAL CREEK TRIBUTARY NO 7 16.0
END DESCRIPTION:
XS GIS Cut Line= 3
       3842067.9     10141811.08      3841130.03     10141588.57
      3839906.39     10141382.31
#Sta/Elev= 30
  4036.1  281.01    4233  272.88  4591.1  263.65  4708.5  261.51  4889.2  253.02
    4944  253.22  4981.7  253.65  4996.8  250.86 5013.86  253.72  5129.2   253.2
  5225.3  253.34  5342.3  257.71  5555.7  265.23  5560.8  267.45  5610.7  266.21
  5712.1  268.19  5772.9   272.7  5813.5  269.35  5843.9  259.94  5904.8  260.01
  5913.6  260.37  5918.7  265.16  5965.6  271.91  6016.3  272.91  6046.7  277.45
  6100.2  279.45    6138  272.56  6178.6  277.71  6216.2  273.94  6240.9  275.15
#Mann= 8 ,-1 , 0
  4036.1     .11       0    4233     .17       0  4591.1     .11       0
    4944     .15       0  4981.7     .06       0 5013.86     .15       0
  5129.2     .17       0  5342.3     .11       0
Bank Sta=4981.7,5013.86
XS Rating Curve= 0 ,0
Exp/Cntr=0.3,0.1

Type RM Length L Ch R = 1 ,7500    ,500,500,500
BEGIN DESCRIPTION:
CRYSTAL CREEK TRIBUTARY NO 7 15.0
END DESCRIPTION:
XS GIS Cut Line= 3
      3842080.89     10141603.67      3841276.21     10141165.17
      3839897.77     10141343.25
#Sta/Elev= 30
  4083.6  275.85  4155.4  273.98  4194.5  275.26  4515.8  268.28  4611.4  264.34
  4772.1  259.53  4788.3  257.54  4853.8  254.54  4884.3  250.94  4919.3  251.17
  4941.2  253.39    4964  252.68  4973.4  251.06  5010.2  252.07    5057  249.58
  5163.9  250.56  5220.2     253  5411.8  260.54  5543.5  262.55  5709.3  266.91
  5764.7  265.75    6047  271.75  6117.6  271.28  6137.7  272.91  6147.8   271.6
  6175.4  272.67  6208.3   271.2  6248.7  273.69  6259.8  272.03  6389.9  273.14
#Mann= 6 ,-1 , 0
  4083.6     .11       0  4194.5     .17       0  4611.4     .11       0
    4964     .06       0  5220.2     .17       0  5543.5     .11       0
Bank Sta=4964,5220.2
XS Rating Curve= 0 ,0
Exp/Cntr=0.3,0.1

Type RM Length L Ch R = 1 ,7000    ,500,500,500
BEGIN DESCRIPTION:
CRYSTAL CREEK TRIBUTARY NO 7 14.0
END DESCRIPTION:
XS GIS Cut Line= 3
        3842159.     10141312.86      3841246.11     10140737.63
      3839851.38     10141303.62
#Sta/Elev= 30
    3921  274.17    3946  273.69  3952.2   272.4  3958.1  273.56  3967.5  271.66
  3973.4  273.39  3981.5  271.65    4004  272.55  4009.9  270.92  4012.5  271.58
  4025.2  273.46  4140.5  270.92  4453.6  262.77  4547.8  258.92  4560.6  257.28
  4663.2  256.35  4803.5  251.83  4857.4   250.8  4903.3     249  4988.1  249.05
  4994.2  247.88  5018.4   249.3  5053.3  248.71  5138.4  250.92  5249.2  254.88
  5286.2  257.13  5649.4  264.11  6084.5  270.56  6174.5  269.69  6505.2  272.33
#Mann= 7 ,-1 , 0
    3921     .17       0  4012.5     .11       0  4803.5     .15       0
  4857.4     .06       0  5138.4     .11       0  5249.2     .17       0
  5649.4     .11       0
Bank Sta=4857.4,5138.4
XS Rating Curve= 0 ,0
Exp/Cntr=0.3,0.1

Type RM Length L Ch R = 1 ,6500    ,500,500,500
BEGIN DESCRIPTION:
CRYSTAL CREEK TRIBUTARY NO 7 13.0
END DESCRIPTION:
XS GIS Cut Line= 3
      3842449.75     10140274.33       3841369.6     10140330.36
      3840214.57     10140366.69
#Sta/Elev= 30
  3918.4  266.94  3930.3  266.99  3948.6  265.17  4030.5  264.11  4060.5  264.88
  4209.2  262.88    4411  260.64  4509.1  258.36    4681  252.86  4761.4  250.68
  4801.5  248.12  4821.5  249.74  4840.1  249.71  4931.7  247.58  4951.7  249.37
  4961.7  248.26  4989.8  246.68  5021.8  248.08  5041.8  247.63  5081.8  249.16
  5211.9  250.93  5291.9   250.7  5391.9  252.35    5442  254.37    5572  256.59
  5664.4  260.58  5796.1  266.44  5872.2  269.57  6031.5  273.98  6155.6   276.8
#Mann= 10 ,-1 , 0
  3918.4     .11       0  4209.2     .17       0  4509.1     .11       0
    4681     .17       0  4840.1     .15       0  4961.7     .06       0
  5021.8     .11       0  5664.4     .17       0  5796.1     .11       0
  6031.5     .17       0
#XS Ineff= 2 , 0
         4831.59  250.03
Permanent Ineff=
       F       F
Bank Sta=4961.7,5021.8
XS Rating Curve= 0 ,0
Exp/Cntr=0.3,0.1

Type RM Length L Ch R = 1 ,6000    ,500,500,500
BEGIN DESCRIPTION:
CRYSTAL CREEK TRIBUTARY NO 7 12.0
END DESCRIPTION:
XS GIS Cut Line= 3
      3842371.66     10139967.38      3841428.09     10139849.48
      3840336.09     10139906.62
#Sta/Elev= 30
  4049.1  273.79  4103.3  275.02  4139.4  272.17  4163.8  273.15  4214.2  271.34
  4274.6  268.21  4286.1  266.88  4395.6  256.16    4446  252.06  4502.5  249.43
  4536.7  248.35  4647.5  245.55  4728.1  246.55  4828.9  245.57  4980.1  246.26
  5060.3   245.4  5100.4  246.21  5108.4  244.82  5130.8  246.74  5170.5  247.01
  5190.5   248.2  5380.8  255.32    5541  259.47  5570.3   259.1    5591   260.7
  5821.4  267.36  5889.1  270.43  6001.6  273.73  6071.7  277.16  6093.5  277.38
#Mann= 6 ,-1 , 0
  4049.1     .11       0  4286.1     .17       0  4502.5     .11       0
  4536.7     .07       0  5190.5     .11       0  5570.3     .17       0
Bank Sta=4536.7,5190.5
XS Rating Curve= 0 ,0
Exp/Cntr=0.3,0.1

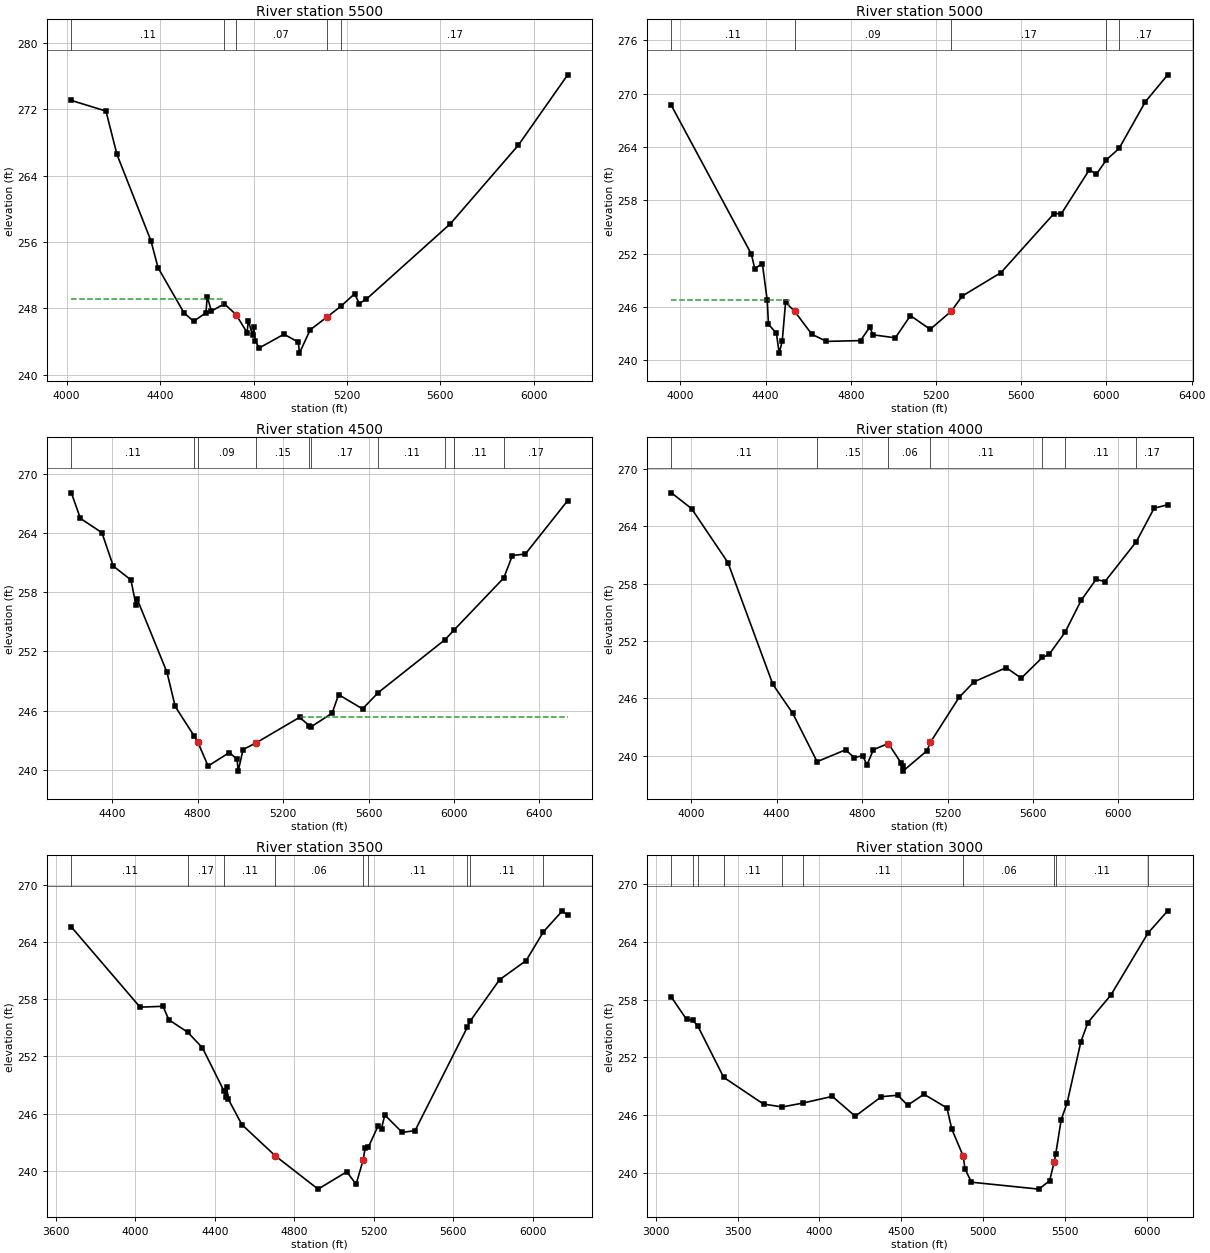
Type RM Length L Ch R = 1 ,5500    ,500,500,500
BEGIN DESCRIPTION:
CRYSTAL CREEK TRIBUTARY NO 7 11.0
END DESCRIPTION:
XS GIS Cut Line= 3
      3842441.16      10139763.4      3841540.27     10139377.91
      3840396.84     10139437.87
#Sta/Elev= 30
  4020.1  273.07  4168.2  271.79  4215.4  266.55  4360.9  256.14  4391.3  252.89
  4502.3  247.45  4543.7  246.43  4596.3  247.46  4601.8  249.38  4619.9  247.67
  4675.2  248.53  4725.2  247.24  4772.3  245.06  4777.8  246.52  4795.9  244.74
  4801.4  245.74  4806.8  244.05  4824.9  243.22  4930.2  244.87  4991.8  243.92
  4996.6  242.59  5042.5   245.4  5112.6   246.9  5176.5   248.3  5232.7  249.75
  5252.8  248.57  5282.8  249.09  5643.3  258.21  5933.7  267.67    6145  276.16
#Mann= 5 ,-1 , 0
  4020.1     .11       0  4675.2     .15       0  4725.2     .07       0
  5112.6     .11       0  5176.5     .17       0
#XS Ineff= 2 , 0
         4665.49  249.08
Permanent Ineff=
       F       F
Bank Sta=4725.2,5112.6
XS Rating Curve= 0 ,0
Exp/Cntr=0.3,0.1

Type RM Length L Ch R = 1 ,5000    ,500,500,500
BEGIN DESCRIPTION:
CRYSTAL CREEK TRIBUTARY NO 7 10.0
END DESCRIPTION:
XS GIS Cut Line= 3
      3842616.47     10139476.06      3841716.77     10138950.02
      3840444.57     10139147.94
#Sta/Elev= 30
  3957.8  268.66  4333.4  251.93  4349.1   250.3  4384.8  250.87  4407.8  246.72
  4413.6  244.04  4450.8  243.02  4463.9  240.79  4478.1  242.12  4493.8  246.51
  4536.8  245.48  4616.9  242.92  4685.5  242.11  4845.8   242.2  4888.8  243.71
  4904.5  242.85    5009  242.51  5079.9  245.01  5172.7  243.47  5272.2  245.52
  5322.8  247.21  5504.9  249.85  5753.9   256.5  5788.3  256.48  5919.9  261.43
  5952.7  260.92  6000.1  262.55  6059.4  263.83    6183  269.09  6287.5  272.11
#Mann= 5 ,-1 , 0
  3957.8     .11       0  4536.8     .09       0  5272.2     .17       0
  6000.1     .11       0  6059.4     .17       0
#XS Ineff= 2 , 0
         4509.66  246.76
Permanent Ineff=
       F       F
Bank Sta=4536.8,5272.2
XS Rating Curve= 0 ,0
Exp/Cntr=0.3,0.1

Type RM Length L Ch R = 1 ,4500    ,500,500,500
BEGIN DESCRIPTION:
CRYSTAL CREEK TRIBUTARY NO 7 9.0
END DESCRIPTION:
XS GIS Cut Line= 3
      3842741.44      10138882.3      3842010.18     10138579.43
      3840502.96     10138856.08
#Sta/Elev= 30
  4208.5  268.11  4250.6  265.52  4351.6  264.06  4404.8  260.67  4487.3  259.27
  4511.1  256.72  4516.6  257.32  4656.2  249.89  4694.6  246.42  4784.9  243.37
    4801  242.77  4848.8  240.37  4948.4  241.74  4984.5  241.05  4989.6  239.85
  5012.5  242.04  5073.5  242.72  5276.9  245.31  5323.4  244.46  5330.3  244.34
  5429.5  245.74  5459.9  247.62  5571.7  246.17  5645.6  247.83  5958.7  253.21
    6000  254.17  6233.3  259.47  6273.3  261.74  6334.3   261.9  6532.4  267.32
#Mann= 10 ,-1 , 0
  4208.5     .11       0  4784.9     .15       0    4801     .09       0
  5073.5     .15       0  5323.4     .11       0  5330.3     .17       0
  5645.6     .11       0  5958.7     .17       0    6000     .11       0
  6233.3     .17       0
#XS Ineff= 2 , 0
                         5276.87          245.31
Permanent Ineff=
       F       F
Bank Sta=4801,5073.5
XS Rating Curve= 0 ,0
Exp/Cntr=0.3,0.1

Type RM Length L Ch R = 1 ,4000    ,500,500,500
BEGIN DESCRIPTION:
CRYSTAL CREEK TRIBUTARY NO 7 8.0
END DESCRIPTION:
XS GIS Cut Line= 3
      3842882.11     10138267.73      3841791.22     10138206.52
       3840564.4     10138304.19
#Sta/Elev= 30
  3907.4   267.5  4001.8  265.85  4172.1   260.2  4382.4  247.45    4475  244.44
  4589.6  239.36  4722.9   240.6    4763  239.79  4803.1  239.98  4823.1  239.02
  4853.1  240.62  4923.2  241.26  4983.3   239.2    4991  238.87  4991.3  238.37
  5103.7   240.5  5119.5  241.37  5254.2  246.09  5324.4  247.72  5474.9   249.2
  5545.1   248.1  5644.1  250.27  5675.5  250.58  5750.6  252.92    5826  256.26
  5896.2  258.46  5936.3  258.19    6084  262.39  6167.1  265.89  6230.7  266.25
#Mann= 7 ,-1 , 0
  3907.4     .11       0  4589.6     .15       0  4923.2     .06       0
  5119.5     .11       0  5644.1     .17       0  5750.6     .11       0
    6084     .17       0
Bank Sta=4923.2,5119.5
XS Rating Curve= 0 ,0
Exp/Cntr=0.3,0.1

Type RM Length L Ch R = 1 ,3500    ,500,500,500
BEGIN DESCRIPTION:
CRYSTAL CREEK TRIBUTARY NO 7 7.0
END DESCRIPTION:
XS GIS Cut Line= 3
      3842902.98     10138080.24      3841621.79     10137750.67
      3840543.55     10138220.86
#Sta/Elev= 30
  3677.1  265.58  4023.1  257.17  4138.6  257.26  4167.7  255.85  4263.6  254.53
  4337.1  252.91  4446.3  248.35  4454.1  247.71  4459.2  248.84  4467.1  247.54
  4535.5  244.86  4704.6  241.57  4919.4  238.09  5063.9  239.91  5110.8   238.6
  5146.1  241.12    5157  242.44  5173.1  242.51  5222.5  244.76  5238.8  244.44
  5255.2  245.87  5343.3  244.03  5407.9  244.23  5671.1  255.07  5684.1  255.67
  5833.4  260.05    5967  262.05  6054.5  265.08  6149.8  267.27  6176.3  266.79
#Mann= 9 ,-1 , 0
  3677.1     .11       0  4263.6     .17       0  4446.3     .11       0
  4704.6     .06       0  5146.1     .15       0  5173.1     .11       0
  5671.1     .17       0  5684.1     .11       0  6054.5     .17       0
Bank Sta=4704.6,5146.1
XS Rating Curve= 0 ,0
Exp/Cntr=0.3,0.1

Type RM Length L Ch R = 1 ,3000    ,500,500,500
BEGIN DESCRIPTION:
CRYSTAL CREEK TRIBUTARY NO 7 6.0
END DESCRIPTION:
XS GIS Cut Line= 3
      3843220.62     10137304.19      3841317.01     10137355.49
       3840523.9     10138157.17
#Sta/Elev= 30
  3095.7  258.26  3188.5  255.94    3226  255.86  3256.3  255.28  3415.2  249.92
  3658.7  247.14  3773.1  246.84  3899.8  247.25  4078.8  247.94  4218.9  245.88
  4378.9  247.91    4479  248.06    4539  247.02    4639  248.16  4779.1  246.74
  4809.1  244.52  4879.1  241.71  4889.1  240.41  4929.1  239.02  5340.6   238.3
  5406.4  239.17  5434.7  241.16  5444.2     242  5477.1  245.52  5512.5  247.22
  5597.4  253.62  5639.8  255.61  5781.2  258.49  6007.1  264.91  6127.7  267.23
#Mann= 10 ,-1 , 0
  3095.7     .17       0    3226     .11       0  3256.3     .17       0
  3415.2     .11       0  3773.1     .17       0  3899.8     .11       0
  4879.1     .06       0  5434.7     .15       0  5444.2     .11       0
  6007.1     .17       0
Bank Sta=4879.1,5434.7
XS Rating Curve= 0 ,0
Exp/Cntr=0.3,0.1

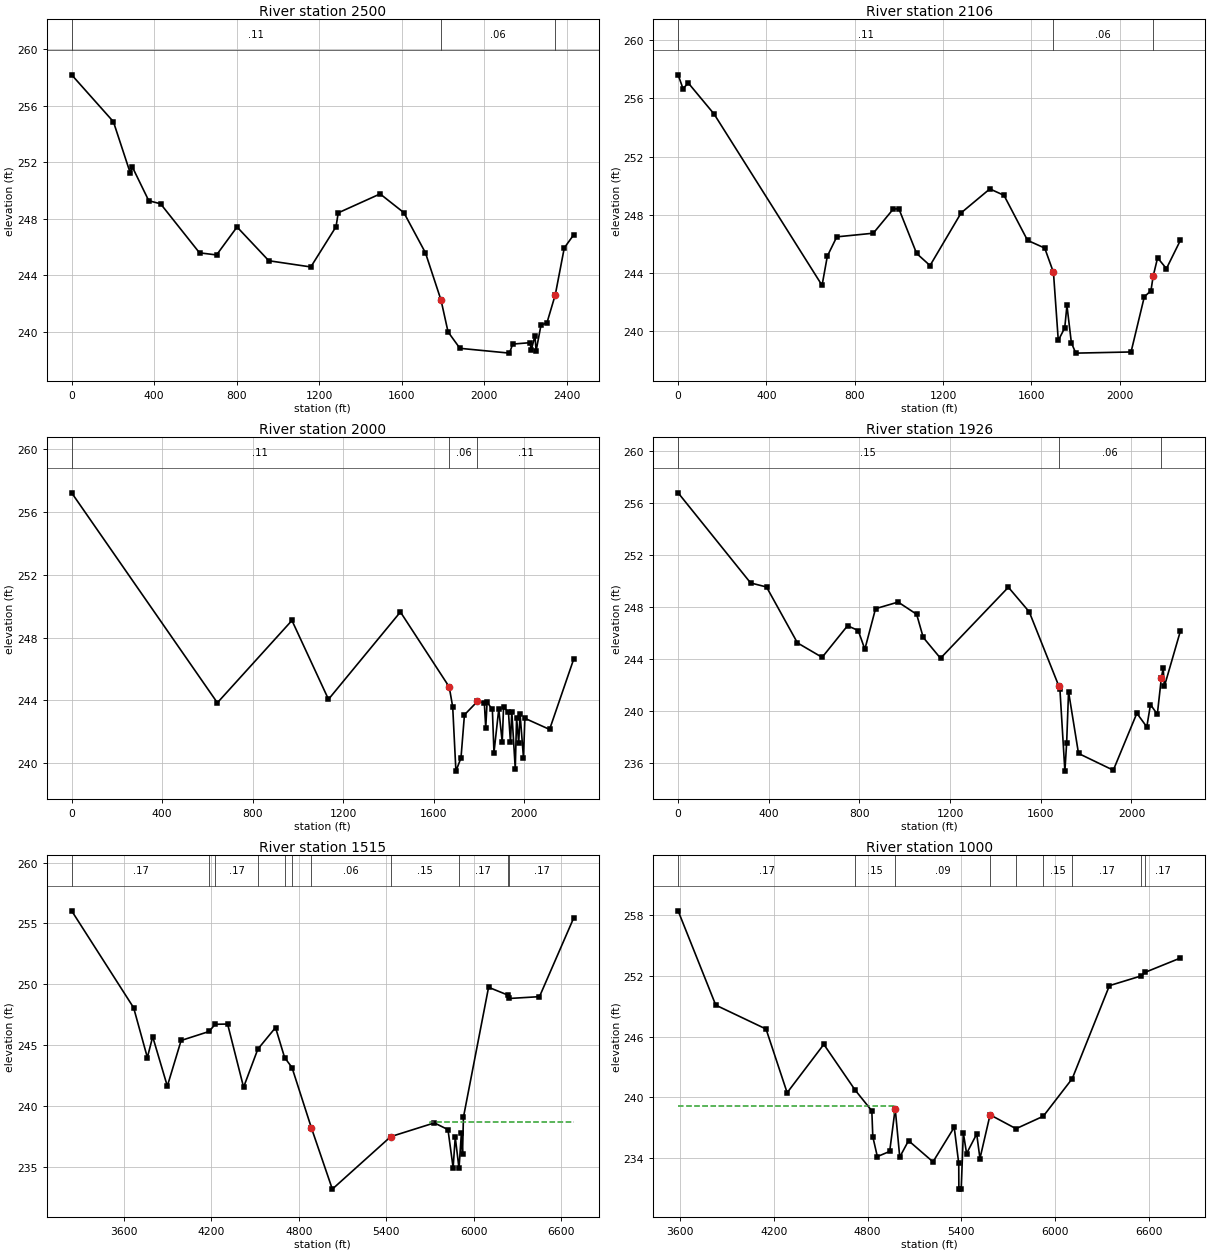
Type RM Length L Ch R = 1 ,2500    ,394,394,394
XS GIS Cut Line= 3
      3843246.69     10137236.48      3841324.42     10136871.06
      3840885.26     10137058.03
#Sta/Elev= 30
       0  258.18   202.4  254.86   283.8  251.24     294  251.66   373.7  249.27
     431  249.05   619.7  245.58   702.3  245.43   801.6  247.41   955.6  245.02
  1159.2  244.58  1281.4  247.43    1292  248.41  1495.1  249.75  1610.4  248.42
  1714.8  245.58  1790.3  242.23  1824.4  239.98  1881.9  238.82    2122  238.48
  2137.7  239.12    2222  239.22  2227.4  238.68  2245.6  239.72  2251.1  238.64
  2274.7  240.46  2303.8  240.63  2344.2  242.62  2387.7  245.93    2434  246.87
#Mann= 3 , 0 , 0
       0     .11       0  1790.3     .06       0  2344.2     .15       0
Bank Sta=1790.3,2344.2
XS Rating Curve= 0 ,0
Exp/Cntr=0.3,0.1

Type RM Length L Ch R = 1 ,2106    ,106,106,106
XS GIS Cut Line= 3
      3843241.54     10137214.36       3841631.3      10136615.4
      3841075.04     10136584.65
#Sta/Elev= 30
       0  257.61    21.9  256.67    46.6  257.04   162.9  254.92   652.1  243.16
   676.1  245.17   718.8  246.49   884.2  246.74   975.3  248.41  1000.3  248.41
  1080.6  245.35  1141.3  244.52  1282.4  248.14  1412.3  249.78  1476.3  249.34
    1583  246.25  1660.9  245.72  1700.4  244.05  1722.3  239.38  1751.5  240.24
  1761.5  241.78  1781.6  239.22  1801.6  238.51    2052  238.59  2112.1  242.38
  2142.1  242.79  2152.1  243.79  2172.2  245.05  2212.2  244.31  2275.1  246.24
#Mann= 3 , 0 , 0
       0     .11       0  1700.4     .06       0  2152.1     .11       0
Bank Sta=1700.4,2152.1
XS Rating Curve= 0 ,0
Exp/Cntr=0.3,0.1

Type RM Length L Ch R = 1 ,2000    ,74,74,74
XS GIS Cut Line= 3
      3843262.31     10137173.98      3841677.29     10136542.49
      3841243.61     10136267.79
#Sta/Elev= 30
       0  257.23     644  243.84   973.6  249.09  1135.1  244.06    1453  249.63
  1668.7  244.85  1684.1  243.58  1698.3  239.48  1720.7  240.32    1736  243.07
  1793.6  243.93  1823.9  243.84  1830.1  242.24    1836  243.87  1859.4  243.42
  1866.5  240.66  1887.7  243.44  1902.9  241.34  1908.9  243.54  1930.4  243.26
  1939.4  241.32  1945.3  243.27  1960.6  239.62  1966.5  242.89  1975.8  241.26
  1981.8  243.14    1997  240.31  2002.9  242.85  2112.3  242.14  2219.5  246.65
#Mann= 3 , 0 , 0
       0     .11       0  1668.7     .06       0  1793.6     .11       0
Bank Sta=1668.7,1793.6
XS Rating Curve= 0 ,0
Exp/Cntr=0.3,0.1

Type RM Length L Ch R = 1 ,1926    ,412,412,412
XS GIS Cut Line= 4
      3843271.92     10137149.25      3841739.81     10136493.87
      3841347.58     10136283.41      3841246.64       10136259.
#Sta/Elev= 30
       0   256.8   319.8  249.87     390  249.56   526.5  245.26   635.3  244.15
   747.5  246.58   794.6  246.21   823.7  244.77   870.9  247.89   970.6   248.4
  1052.3  247.46  1081.3  245.68  1157.5  244.08  1456.9  249.54  1548.9  247.65
  1678.6  241.98  1684.3   241.7  1706.2   235.4    1714  237.57  1722.4  241.51
  1766.3  236.76  1919.8  235.47  2023.7  239.85  2067.6   238.8  2083.8  240.52
    2114  239.77  2131.8  242.56  2139.9  243.33    2145  241.91  2215.4  246.15
#Mann= 3 , 0 , 0
       0     .15       0  1678.6     .06       0  2131.8     .15       0
Bank Sta=1678.6,2131.8
XS Rating Curve= 0 ,0
Exp/Cntr=0.3,0.1

Type RM Length L Ch R = 1 ,1515    ,515,515,515
BEGIN DESCRIPTION:
CRYSTAL CREEK TRIBUTARY NO 7 3.0
END DESCRIPTION:
XS GIS Cut Line= 3
      3843293.58     10137111.49      3841805.36     10136177.38
      3840465.47     10135153.17
#Sta/Elev= 30
  3242.9  256.04  3667.9  248.08  3762.1  243.99  3798.6   245.7    3899  241.64
  3993.5  245.39  4185.6  246.13  4226.9  246.72  4312.3  246.74  4421.9  241.55
  4519.6  244.68    4641  246.45  4703.1  243.99  4753.8  243.17  4887.2   238.2
  5030.4  233.18  5430.7  237.49  5729.9  238.62  5823.4  238.07  5858.7  234.94
  5873.3  237.45  5899.1  234.88  5915.7  237.83  5923.1  236.05  5929.4  239.08
  6101.8  249.76  6231.9  249.13  6243.9  248.84  6450.9  248.99  6686.5  255.48
#Mann= 11 ,-1 , 0
  3242.9     .17       0  4185.6     .11       0  4226.9     .17       0
  4519.6     .11       0  4703.1     .17       0  4753.8     .15       0
  4887.2     .06       0  5430.7     .15       0  5899.1     .17       0
  6231.9     .11       0  6243.9     .17       0
#XS Ineff= 2 , 0
                         5701.72          238.71
Permanent Ineff=
       F       F
Bank Sta=4887.2,5430.7
XS Rating Curve= 0 ,0
Exp/Cntr=0.3,0.1

Type RM Length L Ch R = 1 ,1000    ,500,500,500
BEGIN DESCRIPTION:
CRYSTAL CREEK TRIBUTARY NO 7 2.0
END DESCRIPTION:
XS GIS Cut Line= 3
      3843408.13     10136939.59      3842283.26     10136082.31
      3840831.42     10135013.55
#Sta/Elev= 30
  3585.7   258.4  3826.8   249.1    4149  246.74  4284.1  240.46  4519.1  245.23
  4719.7  240.72  4826.7  238.67  4832.9  236.12    4862  234.16    4941  234.67
  4976.3  238.89  5005.5  234.11  5061.9  235.73  5218.5  233.64  5354.4  237.05
  5383.5  233.48  5384.1  230.95  5399.2  230.95  5412.8   236.5  5433.7  234.46
  5498.5  236.39  5519.3  233.97  5584.1  238.28  5750.4  236.91    5925  238.14
  6110.6  241.85  6348.6  251.02  6552.3  251.98  6578.2  252.34  6802.8  253.74
#Mann= 9 ,-1 , 0
  3585.7     .17       0  4719.7     .15       0  4976.3     .09       0
  5584.1     .15       0  5750.4     .17       0    5925     .15       0
  6110.6     .17       0  6552.3     .11       0  6578.2     .17       0
#XS Ineff= 2 , 0
         4969.14  239.12 5584.11          238.26
Permanent Ineff=
       F       F
Bank Sta=4976.3,5584.1
XS Rating Curve= 0 ,0
Exp/Cntr=0.3,0.1