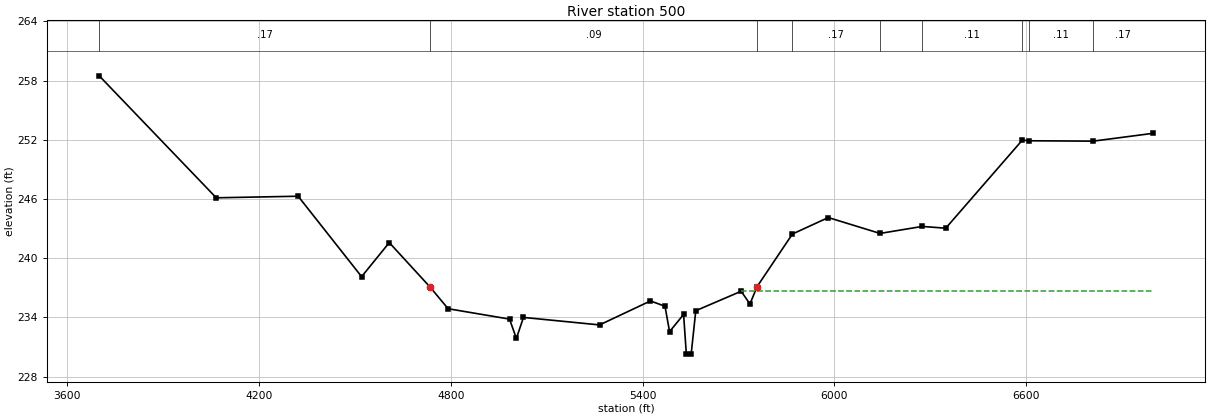
HEC-RAS study CRYSTAL CREEK TRIBUTARY NO 7.prj: CRYSTAL CREEK TRIBUTARY NO 7 Base Level Engineering

--- CRYSTAL CREEK TRIBUTARY NO 7.g01 (geometry) --- (continued)

Type RM Length L Ch R = 1 ,500     ,0,0,0
BEGIN DESCRIPTION:
CRYSTAL CREEK TRIBUTARY NO 7 1.0
END DESCRIPTION:
XS GIS Cut Line= 3
       3843491.5     10136871.92      3842681.88     10135854.43
      3840923.77     10134908.35
#Sta/Elev= 30
  3699.7  258.48    4066  246.12  4322.2  246.28  4520.8  238.13  4607.4  241.58
  4735.5  237.06  4791.5  234.88  4983.7  233.83  5005.1  231.87  5027.3     234
  5265.5  233.24  5424.7  235.67  5470.2  235.13  5484.5  232.56  5528.4   234.3
    5537  230.28  5552.1  230.28  5566.5  234.68  5708.5  236.65  5736.1  235.36
    5758   237.1  5868.9  242.45  5981.2  244.12  6143.1  242.51  6275.3  243.22
  6348.7  243.04  6588.5  251.97  6608.3   251.9  6809.8  251.86  6996.5  252.65
#Mann= 9 ,-1 , 0
  3699.7     .17       0  4735.5     .09       0    5758     .15       0
  5868.9     .17       0  6143.1     .15       0  6275.3     .11       0
  6588.5     .17       0  6608.3     .11       0  6809.8     .17       0
#XS Ineff= 2 , 0
                         5708.46          236.65
Permanent Ineff=
       F       F
Bank Sta=4735.5,5758
XS Rating Curve= 0 ,0
Exp/Cntr=0.3,0.1

Chan Stop Cuts=-1
Use User Specified Reach Order=0
Composite Channel Slope=5

--- CRYSTAL CREEK TRIBUTARY NO 7.g10 (geometry) ---

Geom Title=Existing Conditions
Program Version=4.10

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
River Reach=CRYSTAL CREEK TR,Reach-1

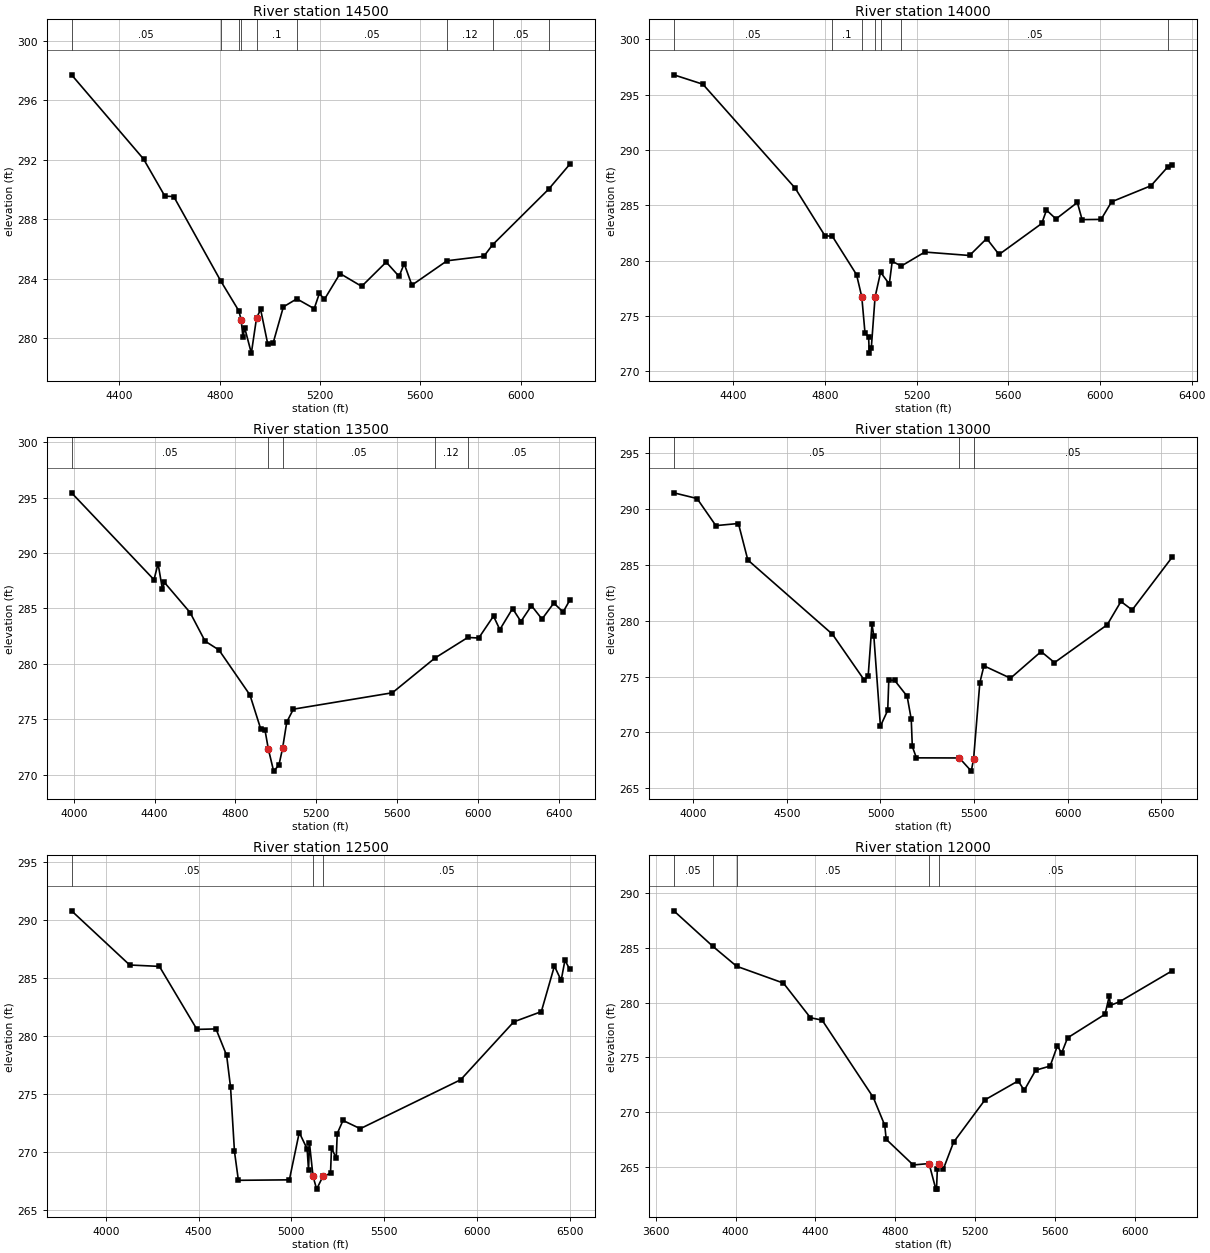
Type RM Length L Ch R = 1 ,14500   ,500,500,500
BEGIN DESCRIPTION:
CRYSTAL CREEK TRIBUTARY NO 7 29.0
END DESCRIPTION:
XS GIS Cut Line= 3
      3839343.31     10146311.05      3838760.08     10145776.86
      3837593.64     10145512.59
#Sta/Elev= 30
  4209.1  297.72  4496.1  292.06  4581.2  289.56  4616.4  289.54    4804  283.86
  4876.1  281.85  4885.2  281.25  4892.6  280.08  4899.4  280.71    4926  279.01
 4946.61 281.363  4962.9  281.95  4991.3  279.63  5012.5  279.67  5053.7  282.12
  5107.3  282.66  5176.6     282  5197.1  283.02  5217.6  282.63  5279.7  284.36
  5365.9   283.5  5463.7  285.13    5515  284.17  5535.5  285.02  5566.2  283.58
  5706.4  285.22  5853.3  285.52  5887.8  286.29  6111.4  290.03    6196  291.71
#Mann= 9 ,-1 , 0
  4209.1     .05       0    4804     .12       0  4876.1      .1       0
  4885.2     .07       0 4946.61      .1       0  5107.3     .05       0
  5706.4     .12       0  5887.8     .05       0  6111.4     .12       0
Bank Sta=4885.2,4946.61
XS Rating Curve= 0 ,0
Exp/Cntr=0.3,0.1

Type RM Length L Ch R = 1 ,14000   ,500,500,500
BEGIN DESCRIPTION:
CRYSTAL CREEK TRIBUTARY NO 7 28.0
END DESCRIPTION:
XS GIS Cut Line= 3
      3839447.21     10146175.72      3839008.63     10145437.93
      3837738.85     10145097.58
#Sta/Elev= 30
  4141.7  296.78  4268.4  295.93  4670.6  286.55  4800.2  282.26  4833.5  282.18
  4938.5  278.73  4961.4  276.72  4975.5  273.44  4991.1   273.1  4994.1  271.64
    5003  272.14 5019.29 276.704  5043.4  278.94  5081.4  277.88    5094  279.93
  5133.9  279.51  5236.3  280.77  5431.3  280.46  5506.1  281.99  5559.9  280.55
  5746.2  283.35  5766.9  284.56  5808.3  283.76  5901.5  285.25  5922.2   283.7
    6005  283.72  6050.8  285.31  6222.5  286.76  6294.9  288.44  6314.6  288.59
#Mann= 7 ,-1 , 0
  4141.7     .05       0  4833.5      .1       0  4961.4     .07       0
 5019.29      .1       0  5043.4     .12       0  5133.9     .05       0
  6294.9     .12       0
Bank Sta=4961.4,5019.29
XS Rating Curve= 0 ,0
Exp/Cntr=0.3,0.1

Type RM Length L Ch R = 1 ,13500   ,500,500,500
BEGIN DESCRIPTION:
CRYSTAL CREEK TRIBUTARY NO 7 27.0
END DESCRIPTION:
XS GIS Cut Line= 3
      3839577.41     10146014.26       3839309.7     10145039.76
      3837915.99     10144623.64
#Sta/Elev= 30
  3989.4  295.43  4397.2  287.59  4417.3  289.05  4438.6  286.76    4449  287.34
  4575.7  284.63  4649.8  282.05  4718.6  281.25  4871.9  277.19    4926  274.08
    4946  274.06 4962.61  272.34    4989  270.32  5015.2  270.86  5033.2  272.37
  5054.1  274.75  5086.7  275.91  5576.6  277.39    5787  280.52  5949.7  282.38
  6003.8  282.33  6076.9  284.31  6108.2  283.09  6171.2  284.99  6212.5  283.82
  6264.7  285.25  6316.9  284.04  6375.2  285.48  6421.3  284.68  6454.5  285.75
#Mann= 5 ,-1 , 0
  3989.4     .05       0 4962.61     .03       0  5033.2     .05       0
    5787     .12       0  5949.7     .05       0
Bank Sta=4962.61,5033.2
XS Rating Curve= 0 ,0
Exp/Cntr=0.3,0.1

Type RM Length L Ch R = 1 ,13000   ,500,500,500
BEGIN DESCRIPTION:
CRYSTAL CREEK TRIBUTARY NO 7 26.0
END DESCRIPTION:
XS GIS Cut Line= 3
      3839806.58     10145894.46      3839694.51     10144795.96
      3838322.67     10144056.17
#Sta/Elev= 30
  3895.8  291.47  4019.8  290.96  4120.3  288.53    4241  288.72  4291.2  285.45
  4743.6  278.79  4913.6  274.68  4934.5  275.07  4954.7   279.7  4964.7  278.63
  4999.9  270.55  5038.9  271.97  5044.6  274.67  5075.7  274.66  5142.7  273.23
  5164.6  271.17  5170.3  268.73  5192.2  267.71  5421.7   267.7  5485.6  266.52
 5497.99  267.64  5531.2  274.45  5553.1  275.96    5695  274.85  5858.8  277.24
  5930.1  276.25  6211.9  279.64  6285.3  281.73  6345.3  280.97  6558.6  285.69
#Mann= 3 , 0 , 0
  3895.8     .05       0  5421.7     .03       0 5497.99     .05       0
Bank Sta=5421.7,5497.99
XS Rating Curve= 0 ,0
Exp/Cntr=0.3,0.1

Type RM Length L Ch R = 1 ,12500   ,500,500,500
BEGIN DESCRIPTION:
CRYSTAL CREEK TRIBUTARY NO 7 25.0
END DESCRIPTION:
XS GIS Cut Line= 3
      3840749.91     10145153.89      3839757.93     10144507.49
      3838343.06     10144009.06
#Sta/Elev= 30
    3816  290.76  4129.1  286.09  4289.1  285.97  4491.3  280.54    4594  280.58
  4651.3   278.3  4672.4  275.56  4693.5  270.02  4714.6  267.53  4989.2  267.57
  5042.5  271.65  5084.9  270.24  5092.4  268.42  5097.7  270.72  5116.7  267.87
  5136.2  266.77  5169.7  267.86  5210.9  268.13  5216.2  270.31  5241.8  269.44
  5247.1  271.56  5278.1  272.69  5371.2  271.98  5912.2   276.2  6198.2  281.19
  6346.6  282.07  6417.1     286  6453.4  284.76  6473.8   286.5  6500.1  285.71
#Mann= 3 , 0 , 0
    3816     .05       0  5116.7     .03       0  5169.7     .05       0
Bank Sta=5116.7,5169.7
XS Rating Curve= 0 ,0
Exp/Cntr=0.3,0.1

Type RM Length L Ch R = 1 ,12000   ,500,500,500
BEGIN DESCRIPTION:
CRYSTAL CREEK TRIBUTARY NO 7 24.0
END DESCRIPTION:
XS GIS Cut Line= 3
      3840825.71     10144882.34      3839775.26     10144099.95
      3838777.97     10143455.48
#Sta/Elev= 30
  3690.2  288.41  3885.2  285.17  4004.8  283.34  4239.4   281.8  4374.9  278.63
  4433.4  278.41  4689.8  271.34  4747.4  268.79  4754.5  267.51    4890  265.16
  4969.3  265.29  5003.3  262.95  5006.8  262.95    5011  264.83  5020.2  265.25
  5041.3   264.8  5092.2  267.24  5249.8  271.12    5416  272.85  5446.4  271.99
  5503.8  273.83  5576.3  274.21  5612.6  276.06  5633.7  275.39  5663.7  276.79
  5851.4  278.95  5872.6   280.6  5878.5  279.76    5924  280.09  6187.4  282.92
#Mann= 5 ,-1 , 0
  3690.2     .05       0  3885.2     .12       0  4004.8     .05       0
  4969.3     .03       0  5020.2     .05       0
Bank Sta=4969.3,5020.2
XS Rating Curve= 0 ,0
Exp/Cntr=0.3,0.1

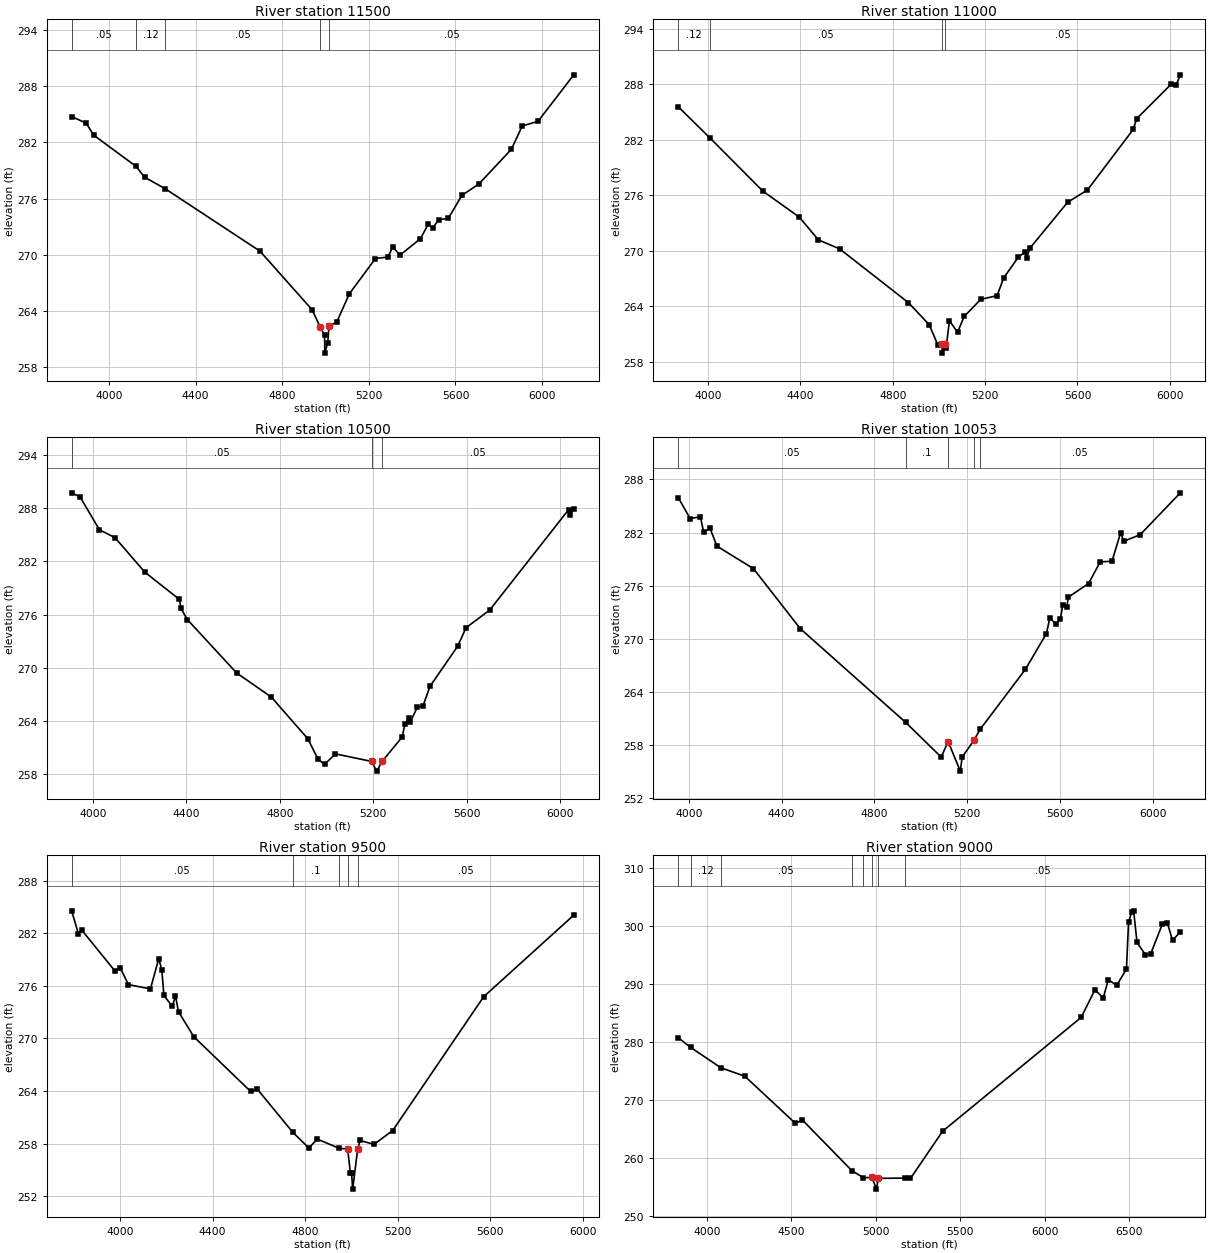
Type RM Length L Ch R = 1 ,11500   ,500,500,500
BEGIN DESCRIPTION:
CRYSTAL CREEK TRIBUTARY NO 7 23.0
END DESCRIPTION:
XS GIS Cut Line= 3
      3840922.87     10144569.79      3840018.45     10143824.24
      3839106.91     10143129.36
#Sta/Elev= 30
  3827.9  284.76  3894.7  284.06  3929.8  282.77  4125.1  279.44  4164.4  278.28
  4261.1  277.03  4697.3  270.38  4938.3  264.11  4974.9  262.29  4995.7   261.4
  4996.8  259.48  5010.3   260.6 5015.96 262.371  5051.9   262.8    5110  265.82
  5230.6  269.59  5288.8  269.75  5309.6   270.8    5345  269.97  5438.5  271.72
  5473.8  273.24  5494.6  272.87  5523.7  273.75  5566.6  273.87  5629.8  276.34
  5708.7  277.57  5858.4  281.27  5908.3  283.76    5981  284.25  6146.2  289.22
#Mann= 5 ,-1 , 0
  3827.9     .05       0  4125.1     .12       0  4261.1     .05       0
  4974.9     .05       0 5015.96     .05       0
Bank Sta=4974.9,5015.96
XS Rating Curve= 0 ,0
Exp/Cntr=0.3,0.1

Type RM Length L Ch R = 1 ,11000   ,500,500,500
BEGIN DESCRIPTION:
CRYSTAL CREEK TRIBUTARY NO 7 22.0
END DESCRIPTION:
XS GIS Cut Line= 3
      3841283.99     10143986.47      3840249.61     10143533.78
       3839437.2     10142875.71
#Sta/Elev= 30
  3870.9  285.59  4009.8  282.17  4237.8  276.45  4395.9  273.63    4478  271.18
  4570.5   270.2  4867.5   264.4  4958.3     262  4995.4  259.81 5012.69 259.907
  5015.2  258.93  5024.9  259.93  5031.3  259.53  5045.7  262.43  5080.9  261.19
  5109.6   262.9  5181.5  264.75  5251.9  265.14  5280.6  267.06  5344.6  269.34
  5373.3  269.85  5379.8  269.22  5394.2  270.28  5557.2  275.24  5643.5  276.58
  5841.8  283.13  5856.2  284.28  6006.1  288.02  6027.2   287.9  6045.5  289.03
#Mann= 4 ,-1 , 0
  3870.9     .12       0  4009.8     .05       0 5012.69     .03       0
  5024.9     .05       0
Bank Sta=5012.69,5024.9
XS Rating Curve= 0 ,0
Exp/Cntr=0.3,0.1

Type RM Length L Ch R = 1 ,10500   ,447,447,447
BEGIN DESCRIPTION:
CRYSTAL CREEK TRIBUTARY NO 7 21.0
END DESCRIPTION:
XS GIS Cut Line= 3
      3841517.83     10143711.06      3840548.47     10143210.86
      3839567.84     10142811.07
#Sta/Elev= 30
  3909.2   289.7  3945.2  289.24  4028.2  285.54  4094.7  284.66    4222  280.78
  4370.5   277.7  4377.1  276.68  4404.9  275.42  4615.2  269.43  4764.4   266.7
  4919.8  262.03  4964.1  259.72  4991.9  259.13  5038.8  260.31  5193.9  259.46
  5214.9  258.37 5239.86 259.507  5324.6  262.22  5335.7  263.65  5354.3  264.37
  5359.7  263.93  5389.4  265.59  5413.2  265.69  5443.4  267.92  5562.2  272.44
  5597.7  274.51  5699.3  276.51  6037.4  287.82  6044.3  287.26    6059  287.91
#Mann= 3 , 0 , 0
  3909.2     .05       0  5193.9     .03       0 5239.86     .05       0
Bank Sta=5193.9,5239.86
XS Rating Curve= 0 ,0
Exp/Cntr=0.3,0.1

Type RM Length L Ch R = 1 ,10053   ,553,553,553
BEGIN DESCRIPTION:
CRYSTAL CREEK TRIBUTARY NO 7 20.0
END DESCRIPTION:
XS GIS Cut Line= 3
      3841577.43     10143443.96      3840725.07     10142838.18
      3839615.62     10142693.08
#Sta/Elev= 30
  3954.3  285.95  4005.7  283.58    4050  283.77  4064.2  282.03  4091.8  282.47
  4121.3  280.46  4278.8  277.92  4480.5  271.15  4935.1  260.56    5088  256.65
  5118.2   258.4  5170.3  255.06  5178.7  256.65  5229.2  258.54  5256.3  259.79
    5451  266.55  5541.8  270.59  5556.5  272.37  5582.1  271.65  5602.3  272.28
  5612.4  273.85  5630.3  273.61  5635.4  274.69  5723.3  276.24  5773.8  278.69
  5824.2  278.75    5862     282  5874.6  281.01  5945.9  281.75  6118.9  286.48
#Mann= 5 ,-1 , 0
  3954.3     .05       0  4935.1      .1       0  5118.2     .07       0
  5229.2      .1       0  5256.3     .05       0
Bank Sta=5118.2,5229.2
XS Rating Curve= 0 ,0
Exp/Cntr=0.3,0.1

Type RM Length L Ch R = 1 ,9500    ,500,500,500
BEGIN DESCRIPTION:
CRYSTAL CREEK TRIBUTARY NO 7 19.0
END DESCRIPTION:
XS GIS Cut Line= 3
      3841651.24     10143279.04      3840644.55      10142609.7
      3839691.08     10142497.96
#Sta/Elev= 30
  3791.1  284.56  3819.9  281.97  3834.9  282.36  3979.2  277.66  4000.2  278.09
  4036.3  276.14  4131.4  275.65  4167.4   279.1  4180.6  277.82  4189.6   274.9
  4225.7  273.66  4239.5  274.85  4252.7  273.04  4318.9  270.19  4563.7  263.96
  4592.4  264.23  4746.2  259.29  4815.9  257.49  4851.9  258.51  4947.5  257.45
  4983.3  257.39    4995  254.67    5000  254.67    5005   252.8 5026.44 257.362
    5037  258.35  5097.4  257.91  5177.9  259.49  5570.6  274.75    5960  284.07
#Mann= 5 ,-1 , 0
  3791.1     .05       0  4746.2      .1       0  4947.5     .05       0
  4983.3     .07       0 5026.44     .05       0
Bank Sta=4983.3,5026.44
XS Rating Curve= 0 ,0
Exp/Cntr=0.3,0.1

Type RM Length L Ch R = 1 ,9000    ,500,500,500
BEGIN DESCRIPTION:
CRYSTAL CREEK TRIBUTARY NO 7 18.0
END DESCRIPTION:
XS GIS Cut Line= 3
      3841798.79     10143127.12      3840902.86     10142373.42
       3839101.8     10142279.59
#Sta/Elev= 30
  3829.2   280.7  3903.2  279.02  4081.3  275.52  4224.1  274.05    4523  265.94
  4564.8  266.51  4857.8  257.78  4926.8  256.55  4977.1  256.61  5003.3  254.59
    5015  256.45  5169.8  256.49  5205.3  256.43  5395.5  264.57  6216.7   284.2
  6298.1  288.97  6346.8  287.53  6376.9  290.67  6426.9  289.73  6484.4  292.51
    6497  300.65  6517.1  302.42  6527.1  302.56  6547.1  297.11  6597.2  294.98
  6627.2  295.07  6697.3  300.29  6727.3  300.43  6757.4  297.47  6803.5  298.93
#Mann= 8 ,-1 , 0
  3829.2     .05       0  3903.2     .12       0  4081.3     .05       0
  4857.8     .12       0  4926.8      .1       0  4977.1     .07       0
    5015      .1       0  5169.8     .05       0
Bank Sta=4977.1,5015
XS Rating Curve= 0 ,0
Exp/Cntr=0.3,0.1

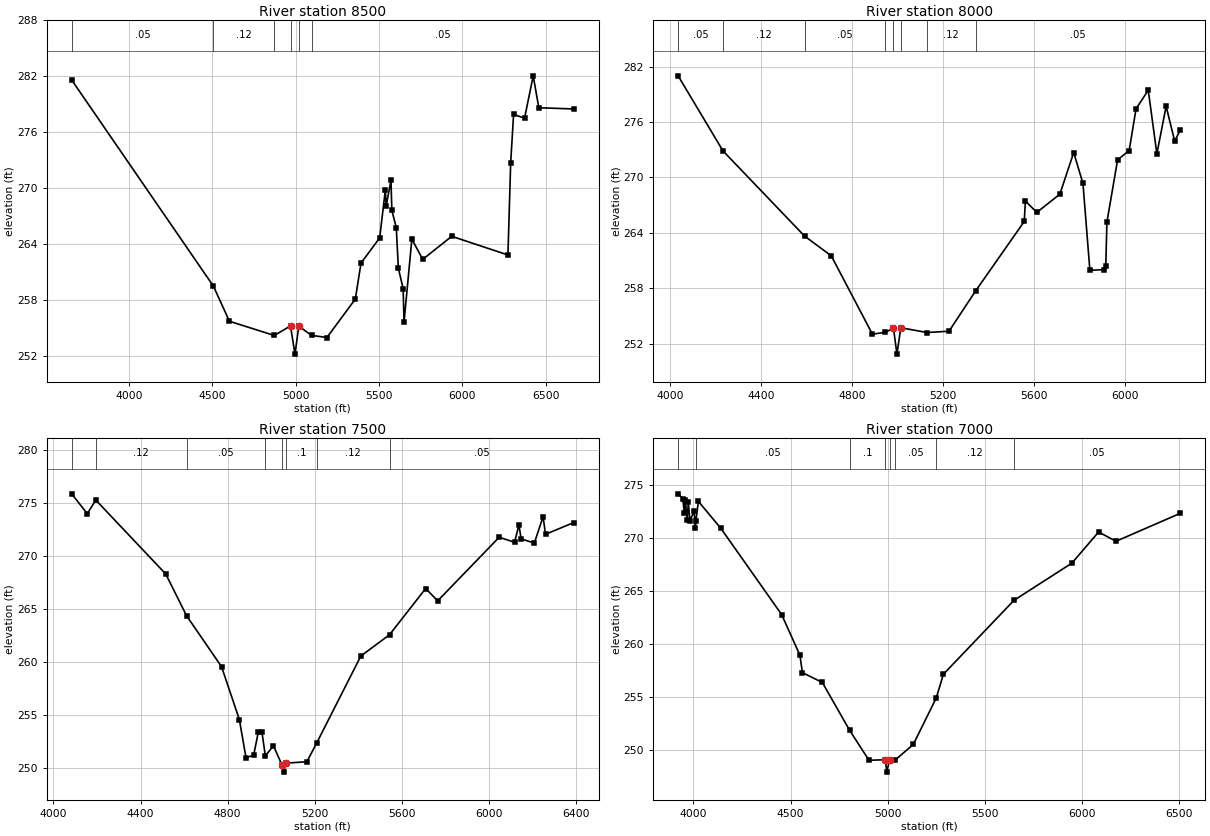
Type RM Length L Ch R = 1 ,8500    ,500,500,500
BEGIN DESCRIPTION:
CRYSTAL CREEK TRIBUTARY NO 7 17.0
END DESCRIPTION:
XS GIS Cut Line= 3
      3842185.06      10142328.5      3840898.02     10141943.45
      3839293.55     10141487.87
#Sta/Elev= 30
  3656.6  281.61  4506.6  259.52  4602.7  255.76  4871.7  254.24  4968.9  255.26
  4995.7  252.24 5018.84  255.24  5094.9  254.25  5187.3  254.02  5357.7  258.14
  5391.6  261.99  5503.7  264.69  5537.6  269.82  5542.7  268.13  5571.4  270.86
  5576.6  267.64  5603.1   265.8  5615.7  261.44  5644.4  259.25  5649.6  255.66
  5696.7  264.56  5761.7  262.39  5935.8  264.86  6272.7  262.86  6289.2  272.75
  6306.6  277.91  6372.4  277.52  6424.3  282.05  6457.8  278.63  6667.9   278.5
#Mann= 6 ,-1 , 0
  3656.6     .05       0  4506.6     .12       0  4871.7      .1       0
  4968.9     .03       0 5018.84      .1       0  5094.9     .05       0
Bank Sta=4968.9,5018.84
XS Rating Curve= 0 ,0
Exp/Cntr=0.3,0.1

Type RM Length L Ch R = 1 ,8000    ,500,500,500
BEGIN DESCRIPTION:
CRYSTAL CREEK TRIBUTARY NO 7 16.0
END DESCRIPTION:
XS GIS Cut Line= 3
       3842067.9     10141811.08      3841130.03     10141588.57
      3839906.39     10141382.31
#Sta/Elev= 30
  4036.1  281.01    4233  272.88  4591.1  263.65  4708.5  261.51  4889.2  253.02
    4944  253.22  4981.7  253.65  4996.8  250.86 5013.86  253.72  5129.2   253.2
  5225.3  253.34  5342.3  257.71  5555.7  265.23  5560.8  267.45  5610.7  266.21
  5712.1  268.19  5772.9   272.7  5813.5  269.35  5843.9  259.94  5904.8  260.01
  5913.6  260.37  5918.7  265.16  5965.6  271.91  6016.3  272.91  6046.7  277.45
  6100.2  279.45    6138  272.56  6178.6  277.71  6216.2  273.94  6240.9  275.15
#Mann= 8 ,-1 , 0
  4036.1     .05       0    4233     .12       0  4591.1     .05       0
    4944      .1       0  4981.7     .03       0 5013.86      .1       0
  5129.2     .12       0  5342.3     .05       0
Bank Sta=4981.7,5013.86
XS Rating Curve= 0 ,0
Exp/Cntr=0.3,0.1

Type RM Length L Ch R = 1 ,7500    ,500,500,500
BEGIN DESCRIPTION:
CRYSTAL CREEK TRIBUTARY NO 7 15.0
END DESCRIPTION:
XS GIS Cut Line= 3
      3842080.89     10141603.67      3841276.21     10141165.17
      3839897.77     10141343.25
#Sta/Elev= 30
  4083.6  275.85  4155.4  273.98  4194.5  275.26  4515.8  268.28  4611.4  264.34
  4772.1  259.53  4853.8  254.54  4884.3  250.94  4919.3  251.17  4941.2  253.39
  4957.3  253.39  4973.1  251.11  5010.2  252.07  5048.8  250.29    5057  249.58
  5068.9  250.43  5163.9  250.56  5208.4  252.31  5411.8  260.54  5543.5  262.55
  5709.3  266.91  5764.7  265.75    6047  271.75  6117.6  271.28  6137.7  272.91
  6147.8   271.6  6208.3   271.2  6248.7  273.69  6259.8  272.03  6389.9  273.14
#Mann= 8 ,-1 , 0
  4083.6     .05       0  4194.5     .12       0  4611.4     .05       0
  4973.1      .1       0  5048.8     .03       0  5068.9      .1       0
  5208.4     .12       0  5543.5     .05       0
Bank Sta=5048.8,5068.9
XS Rating Curve= 0 ,0
Exp/Cntr=0.3,0.1

Type RM Length L Ch R = 1 ,7000    ,500,500,500
BEGIN DESCRIPTION:
CRYSTAL CREEK TRIBUTARY NO 7 14.0
END DESCRIPTION:
XS GIS Cut Line= 3
        3842159.     10141312.86      3841246.11     10140737.63
      3839851.38     10141303.62
#Sta/Elev= 30
    3921  274.17    3946  273.69  3952.2   272.4  3958.1  273.56  3967.5  271.66
  3973.4  273.39  3981.5  271.65    4004  272.55  4009.9  270.92  4012.5  271.58
  4025.2  273.46  4140.5  270.92  4453.6  262.77  4547.8  258.92  4560.6  257.28
  4663.2  256.35  4803.5  251.83  4903.3     249  4988.1  249.05  4994.2  247.88
  5008.9     249    5037  249.01  5130.9  250.49  5249.2  254.88  5286.2  257.13
  5649.4  264.11  5947.8  267.63  6084.5  270.56  6174.5  269.69  6505.2  272.33
#Mann= 8 ,-1 , 0
    3921     .12       0  4012.5     .05       0  4803.5      .1       0
  4988.1     .03       0  5008.9      .1       0    5037     .05       0
  5249.2     .12       0  5649.4     .05       0
Bank Sta=4988.1,5008.9
XS Rating Curve= 0 ,0
Exp/Cntr=0.3,0.1