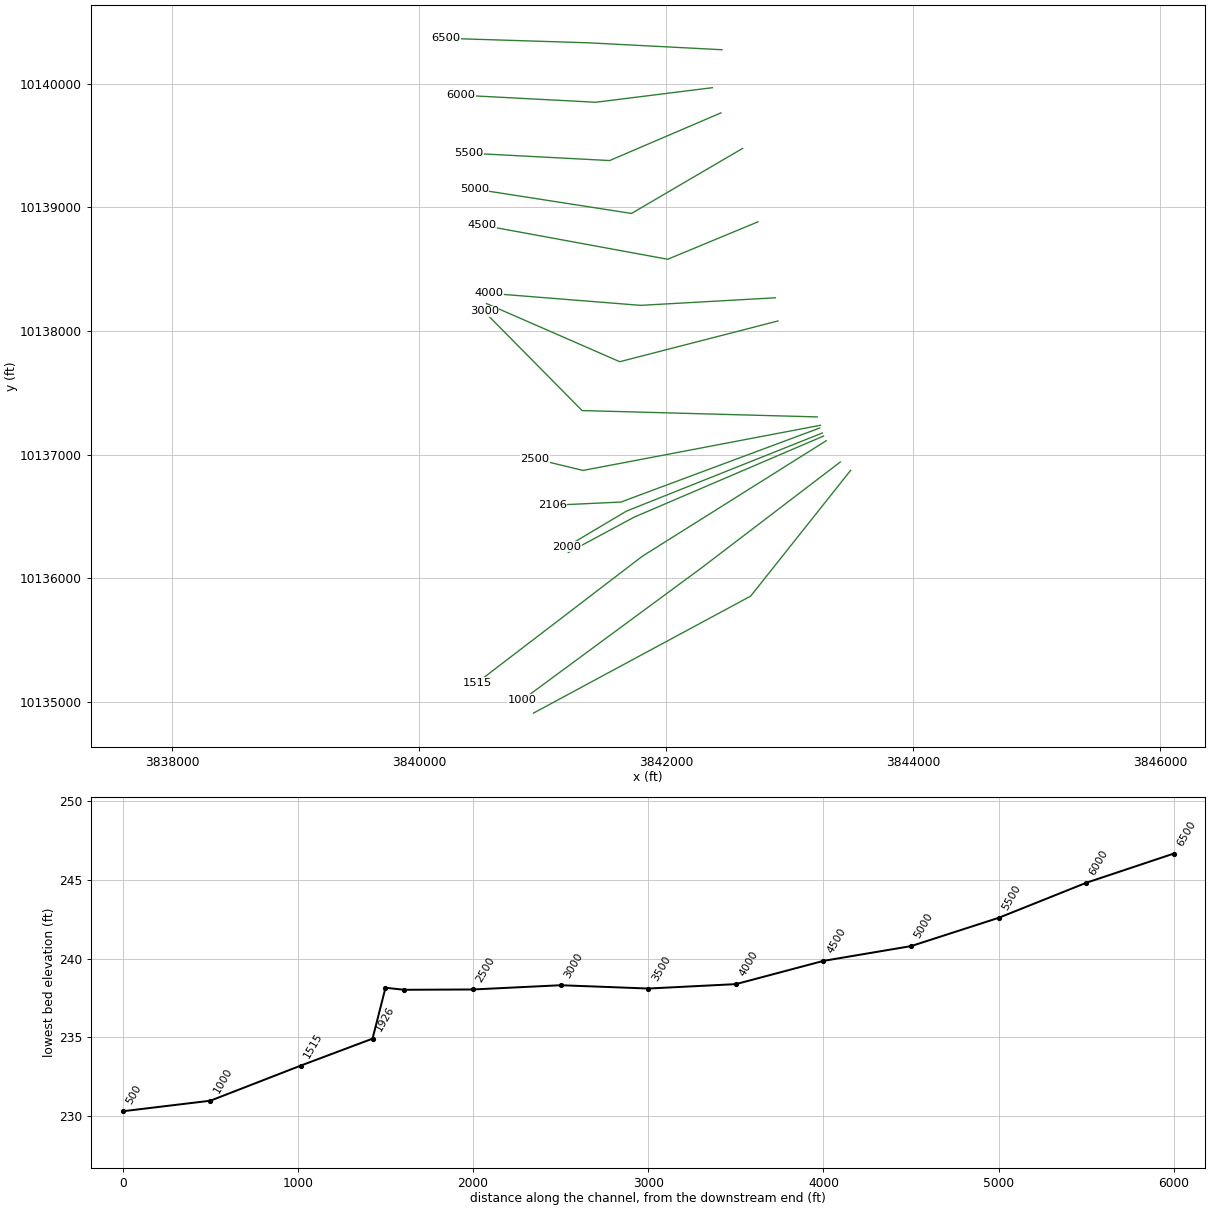
HEC-RAS study CRYSTAL CREEK TRIBUTARY NO 7.prj: CRYSTAL CREEK TRIBUTARY NO 7 Base Level Engineering

--- CRYSTAL CREEK TRIBUTARY NO 7.g10 (geometry) --- (continued)

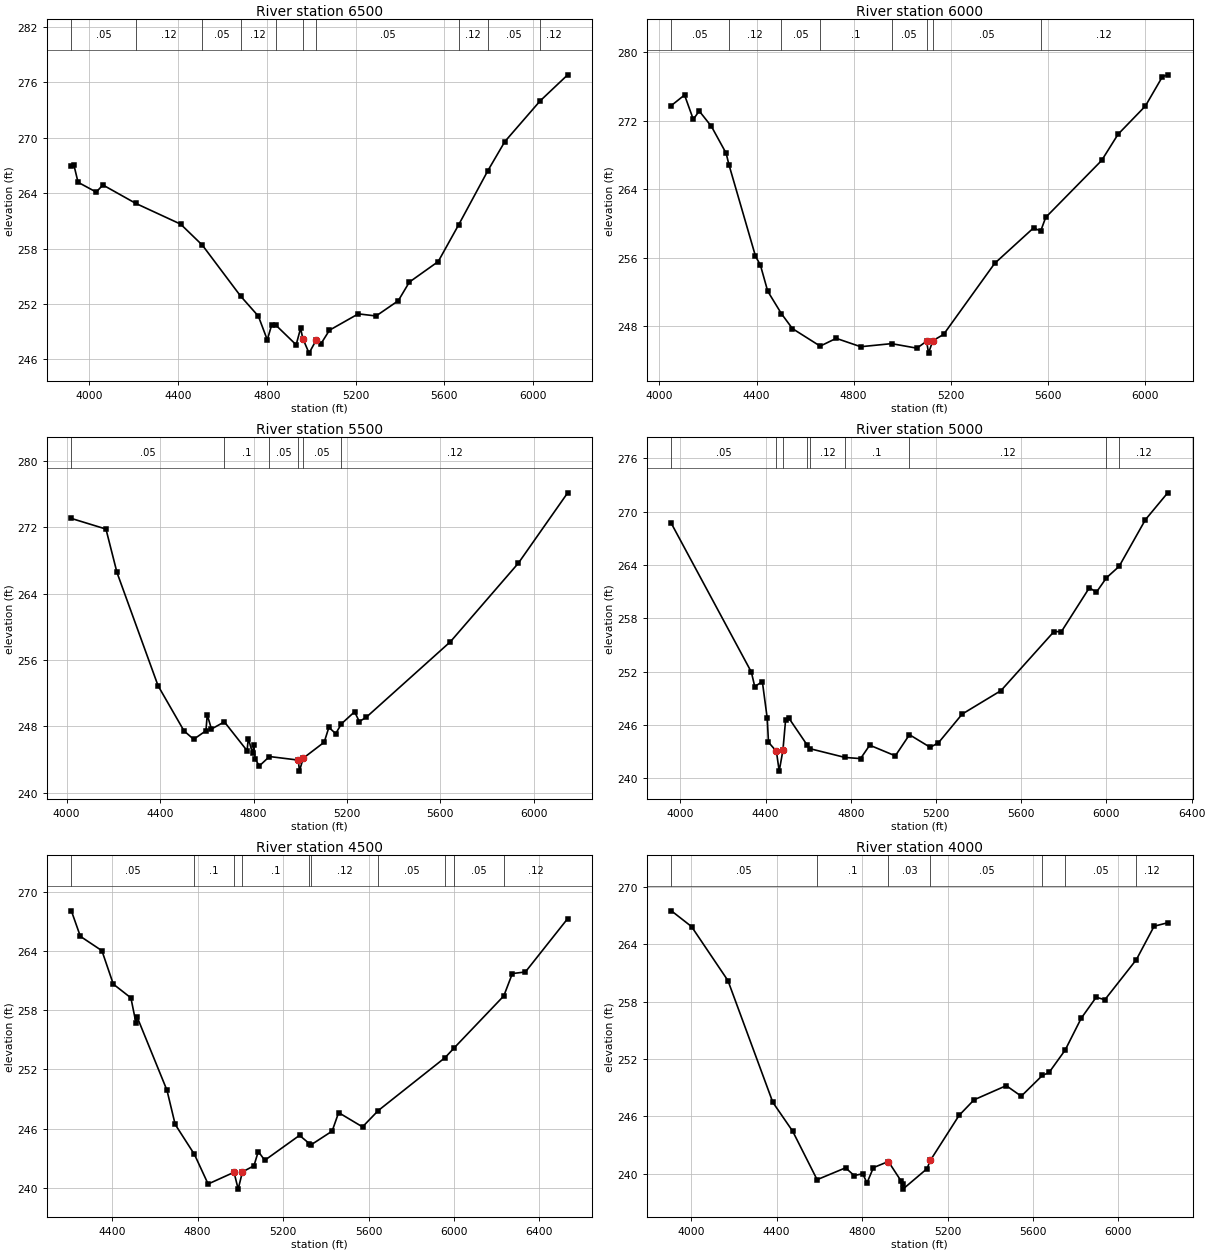
Type RM Length L Ch R = 1 ,6500    ,500,500,500
BEGIN DESCRIPTION:
CRYSTAL CREEK TRIBUTARY NO 7 13.0
END DESCRIPTION:
XS GIS Cut Line= 3
      3842449.75     10140274.33       3841369.6     10140330.36
      3840214.57     10140366.69
#Sta/Elev= 30
  3918.4  266.94  3930.3  266.99  3948.6  265.17  4030.5  264.11  4060.5  264.88
  4209.2  262.88    4411  260.64  4509.1  258.36    4681  252.86  4761.4  250.68
  4801.5  248.12  4821.5  249.74  4840.1  249.71  4931.7  247.58  4951.7  249.37
  4961.7  248.26  4989.8  246.68  5021.8  248.08  5041.8  247.63  5081.8  249.16
  5211.9  250.93  5291.9   250.7  5391.9  252.35    5442  254.37    5572  256.59
  5664.4  260.58  5796.1  266.44  5872.2  269.57  6031.5  273.98  6155.6   276.8
#Mann= 10 ,-1 , 0
  3918.4     .05       0  4209.2     .12       0  4509.1     .05       0
    4681     .12       0  4840.1      .1       0  4961.7     .03       0
  5021.8     .05       0  5664.4     .12       0  5796.1     .05       0
  6031.5     .12       0
Bank Sta=4961.7,5021.8
XS Rating Curve= 0 ,0
Exp/Cntr=0.3,0.1

Type RM Length L Ch R = 1 ,6000    ,500,500,500
BEGIN DESCRIPTION:
CRYSTAL CREEK TRIBUTARY NO 7 12.0
END DESCRIPTION:
XS GIS Cut Line= 3
      3842371.66     10139967.38      3841428.09     10139849.48
      3840336.09     10139906.62
#Sta/Elev= 30
  4049.1  273.79  4103.3  275.02  4139.4  272.17  4163.8  273.15  4214.2  271.34
  4274.6  268.21  4286.1  266.88  4395.6  256.16  4415.7  255.13    4446  252.06
  4502.5  249.43  4547.7  247.69    4662  245.64  4728.1  246.55  4828.9  245.57
    4956  245.93  5060.3   245.4  5100.4  246.21  5108.4  244.82  5125.8  246.27
  5170.5  247.01  5380.8  255.32    5541  259.47  5570.3   259.1    5591   260.7
  5821.4  267.36  5889.1  270.43  6001.6  273.73  6071.7  277.16  6093.5  277.38
#Mann= 8 ,-1 , 0
  4049.1     .05       0  4286.1     .12       0  4502.5     .05       0
    4662      .1       0    4956     .05       0  5100.4     .05       0
  5125.8     .05       0  5570.3     .12       0
Bank Sta=5100.4,5125.8
XS Rating Curve= 0 ,0
Exp/Cntr=0.3,0.1

Type RM Length L Ch R = 1 ,5500    ,500,500,500
BEGIN DESCRIPTION:
CRYSTAL CREEK TRIBUTARY NO 7 11.0
END DESCRIPTION:
XS GIS Cut Line= 3
      3842441.16      10139763.4      3841540.27     10139377.91
      3840396.84     10139437.87
#Sta/Elev= 30
  4020.1  273.07  4168.2  271.79  4215.4  266.55  4391.3  252.89  4502.3  247.45
  4543.7  246.43  4596.3  247.46  4601.8  249.38  4619.9  247.67  4675.2  248.53
  4772.3  245.06  4777.8  246.52  4795.9  244.74  4801.4  245.74  4806.8  244.05
  4824.9  243.22  4868.3  244.35  4991.8  243.92  4996.6  242.59  5012.4  244.14
  5102.6  246.08  5122.6  247.87  5151.8  247.11  5176.5   248.3  5232.7  249.75
  5252.8  248.57  5282.8  249.09  5643.3  258.21  5933.7  267.67    6145  276.16
#Mann= 6 ,-1 , 0
  4020.1     .05       0  4675.2      .1       0  4868.3     .05       0
  4991.8     .05       0  5012.4     .05       0  5176.5     .12       0
Bank Sta=4991.8,5012.4
XS Rating Curve= 0 ,0
Exp/Cntr=0.3,0.1

Type RM Length L Ch R = 1 ,5000    ,500,500,500
BEGIN DESCRIPTION:
CRYSTAL CREEK TRIBUTARY NO 7 10.0
END DESCRIPTION:
XS GIS Cut Line= 3
      3842616.47     10139476.06      3841716.77     10138950.02
      3840444.57     10139147.94
#Sta/Elev= 30
  3957.8  268.66  4333.4  251.93  4349.1   250.3  4384.8  250.87  4407.8  246.72
  4413.6  244.04  4450.8  243.02  4463.9  240.79 4481.32 243.115  4493.8  246.51
  4509.5  246.75  4594.2  243.76  4607.6  243.32  4772.9  242.33  4845.8   242.2
  4888.8  243.71    5009  242.51  5075.4  244.89  5172.7  243.47  5211.4  243.98
  5322.8  247.21  5504.9  249.85  5753.9   256.5  5788.3  256.48  5919.9  261.43
  5952.7  260.92  6000.1  262.55  6059.4  263.83    6183  269.09  6287.5  272.11
#Mann= 9 ,-1 , 0
  3957.8     .05       0  4450.8     .07       0 4481.32     .05       0
  4594.2      .1       0  4607.6     .12       0  4772.9      .1       0
  5075.4     .12       0  6000.1     .05       0  6059.4     .12       0
Bank Sta=4450.8,4481.32
XS Rating Curve= 0 ,0
Exp/Cntr=0.3,0.1

Type RM Length L Ch R = 1 ,4500    ,500,500,500
BEGIN DESCRIPTION:
CRYSTAL CREEK TRIBUTARY NO 7 9.0
END DESCRIPTION:
XS GIS Cut Line= 3
      3842741.44      10138882.3      3842010.18     10138579.43
      3840502.96     10138856.08
#Sta/Elev= 30
  4208.5  268.11  4250.6  265.52  4351.6  264.06  4404.8  260.67  4487.3  259.27
  4511.1  256.72  4516.6  257.32  4656.2  249.89  4694.6  246.42  4784.9  243.37
  4848.8  240.37  4970.1  241.56  4989.6  239.85 5009.46 241.598  5063.4  242.22
  5083.7  243.67  5114.2  242.78  5276.9  245.31  5323.4  244.46  5330.3  244.34
  5429.5  245.74  5459.9  247.62  5571.7  246.17  5645.6  247.83  5958.7  253.21
    6000  254.17  6233.3  259.47  6273.3  261.74  6334.3   261.9  6532.4  267.32
#Mann= 10 ,-1 , 0
  4208.5     .05       0  4784.9      .1       0  4970.1     .07       0
 5009.46      .1       0  5323.4     .05       0  5330.3     .12       0
  5645.6     .05       0  5958.7     .12       0    6000     .05       0
  6233.3     .12       0
Bank Sta=4970.1,5009.46
XS Rating Curve= 0 ,0
Exp/Cntr=0.3,0.1

Type RM Length L Ch R = 1 ,4000    ,500,500,500
BEGIN DESCRIPTION:
CRYSTAL CREEK TRIBUTARY NO 7 8.0
END DESCRIPTION:
XS GIS Cut Line= 3
      3842882.11     10138267.73      3841791.22     10138206.52
       3840564.4     10138304.19
#Sta/Elev= 30
  3907.4   267.5  4001.8  265.85  4172.1   260.2  4382.4  247.45    4475  244.44
  4589.6  239.36  4722.9   240.6    4763  239.79  4803.1  239.98  4823.1  239.02
  4853.1  240.62  4923.2  241.26  4983.3   239.2    4991  238.87  4991.3  238.37
  5103.7   240.5  5119.5  241.37  5254.2  246.09  5324.4  247.72  5474.9   249.2
  5545.1   248.1  5644.1  250.27  5675.5  250.58  5750.6  252.92    5826  256.26
  5896.2  258.46  5936.3  258.19    6084  262.39  6167.1  265.89  6230.7  266.25
#Mann= 7 ,-1 , 0
  3907.4     .05       0  4589.6      .1       0  4923.2     .03       0
  5119.5     .05       0  5644.1     .12       0  5750.6     .05       0
    6084     .12       0
Bank Sta=4923.2,5119.5
XS Rating Curve= 0 ,0
Exp/Cntr=0.3,0.1

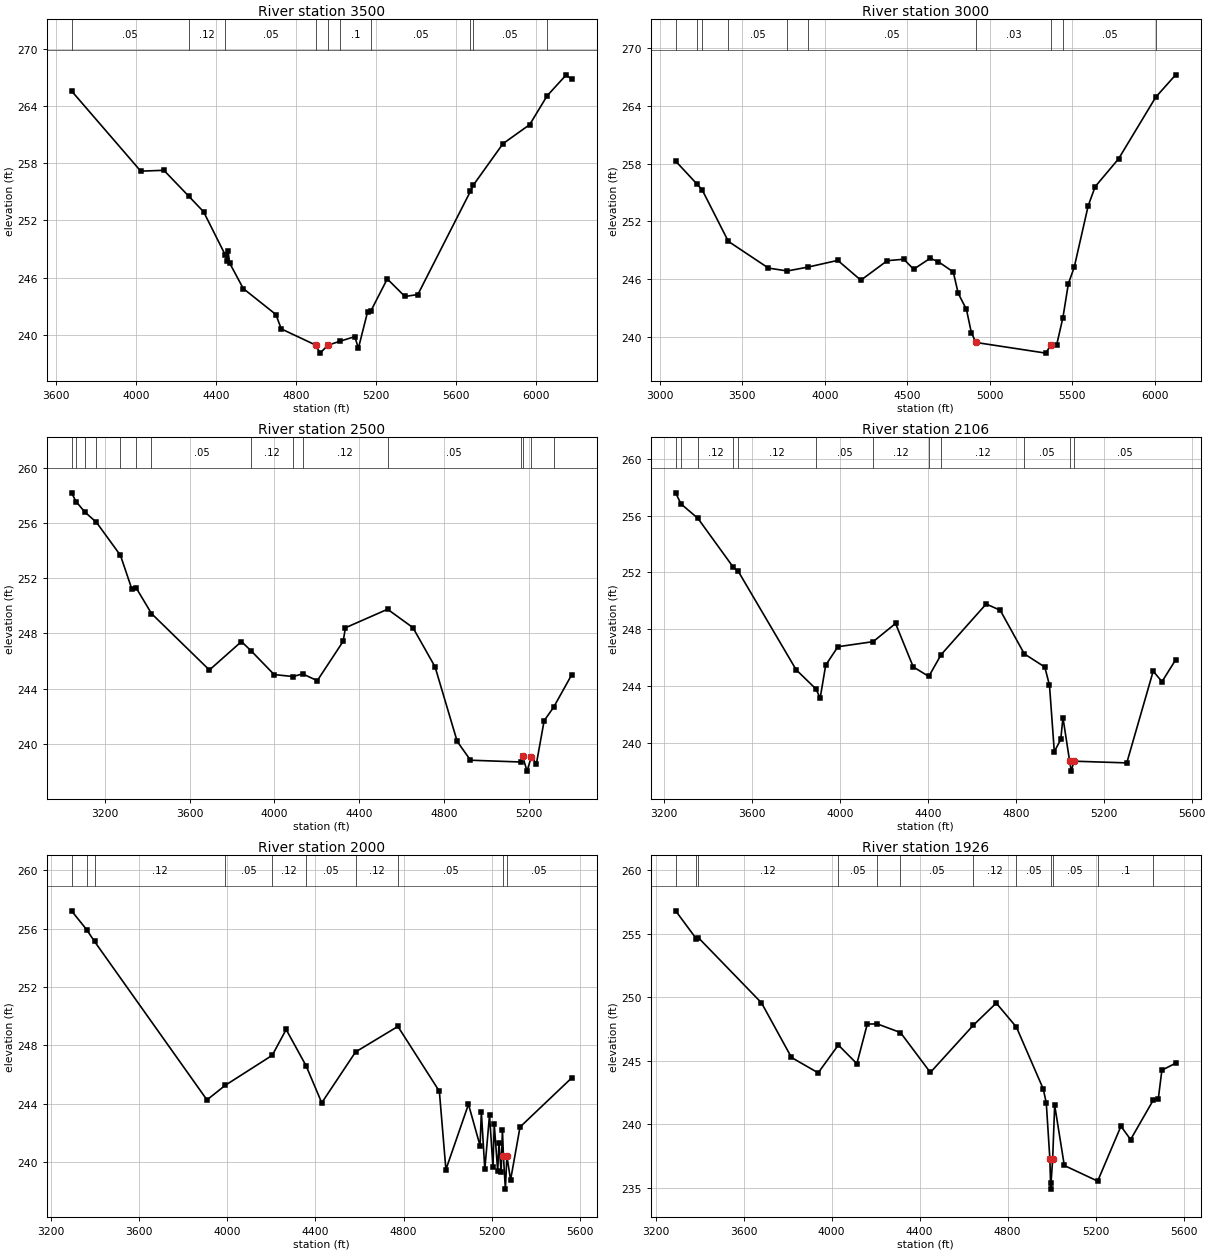
Type RM Length L Ch R = 1 ,3500    ,500,500,500
BEGIN DESCRIPTION:
CRYSTAL CREEK TRIBUTARY NO 7 7.0
END DESCRIPTION:
XS GIS Cut Line= 3
      3842902.98     10138080.24      3841621.79     10137750.67
      3840543.55     10138220.86
#Sta/Elev= 30
  3677.1  265.58  4023.1  257.17  4138.6  257.26  4263.6  254.53  4337.1  252.91
  4446.3  248.35  4454.1  247.71  4459.2  248.84  4467.1  247.54  4535.5  244.86
  4698.4  242.14  4725.3  240.63  4896.8  238.94  4919.4  238.09 4958.74 238.926
    5021  239.35  5092.8  239.82  5110.8   238.6    5157  242.44  5173.1  242.51
  5255.2  245.87  5343.3  244.03  5407.9  244.23  5671.1  255.07  5684.1  255.67
  5833.4  260.05    5967  262.05  6054.5  265.08  6149.8  267.27  6176.3  266.79
#Mann= 10 ,-1 , 0
  3677.1     .05       0  4263.6     .12       0  4446.3     .05       0
  4896.8     .03       0 4958.74     .05       0    5021      .1       0
  5173.1     .05       0  5671.1     .12       0  5684.1     .05       0
  6054.5     .12       0
Bank Sta=4896.8,4958.74
XS Rating Curve= 0 ,0
Exp/Cntr=0.3,0.1

Type RM Length L Ch R = 1 ,3000    ,500,500,500
BEGIN DESCRIPTION:
CRYSTAL CREEK TRIBUTARY NO 7 6.0
END DESCRIPTION:
XS GIS Cut Line= 3
      3843220.62     10137304.19      3841317.01     10137355.49
       3840523.9     10138157.17
#Sta/Elev= 30
  3095.7  258.26    3226  255.86  3256.3  255.28  3415.2  249.92  3658.7  247.14
  3773.1  246.84  3899.8  247.25  4078.8  247.94  4218.9  245.88  4378.9  247.91
    4479  248.06    4539  247.02    4639  248.16    4689   247.8  4779.1  246.74
  4809.1  244.52  4859.1  242.84  4889.1  240.41 4916.83 239.408  5340.6   238.3
  5371.1  239.17  5406.4  239.17  5444.2     242  5477.1  245.52  5512.5  247.22
  5597.4  253.62  5639.8  255.61  5781.2  258.49  6007.1  264.91  6127.7  267.23
#Mann= 10 ,-1 , 0
  3095.7     .12       0    3226     .05       0  3256.3     .12       0
  3415.2     .05       0  3773.1     .12       0  3899.8     .05       0
 4916.83     .03       0  5371.1      .1       0  5444.2     .05       0
  6007.1     .12       0
Bank Sta=4916.83,5371.1
XS Rating Curve= 0 ,0
Exp/Cntr=0.3,0.1

Type RM Length L Ch R = 1 ,2500    ,394,394,394
BEGIN DESCRIPTION:
CRYSTAL CREEK TRIBUTARY NO 7 5.0
END DESCRIPTION:
XS GIS Cut Line= 3
      3843246.69     10137236.48      3841324.42     10136871.06
      3840933.61     10136965.66
#Sta/Elev= 30
  3043.3  258.18  3064.6  257.55  3104.6  256.81    3161  256.04  3274.1  253.65
  3327.1  251.24  3349.3  251.27  3420.4  249.44  3693.6  245.35  3844.9  247.41
  3891.7  246.72    3999  245.02  4087.7  244.88  4133.6  245.07  4202.5  244.58
  4324.7  247.43  4335.3  248.41  4534.2  249.75  4653.7  248.42  4758.1  245.58
  4862.6  240.18  4925.3  238.82  5163.1  238.69  5171.4  239.09  5192.1  238.03
  5212.5  239.08    5236  238.55  5272.7  241.68  5317.2  242.65  5402.1  244.99
#Mann= 15 ,-1 , 0
  3043.3     .05       0  3064.6     .12       0  3104.6     .05       0
    3161     .12       0  3274.1     .05       0  3349.3     .12       0
  3420.4     .05       0  3891.7     .12       0  4087.7     .05       0
  4133.6     .12       0  4534.2     .05       0  5163.1      .1       0
  5171.4     .03       0  5212.5      .1       0  5317.2     .05       0
Bank Sta=5171.4,5212.5
XS Rating Curve= 0 ,0
Exp/Cntr=0.3,0.1

Type RM Length L Ch R = 1 ,2106    ,106,106,106
BEGIN DESCRIPTION:
Mapping XS e20e06b7
END DESCRIPTION:
XS GIS Cut Line= 3
      3843241.57     10137214.37       3841631.3      10136615.4
      3841075.77     10136589.36
#Sta/Elev= 30
  3253.1  257.61  3277.5  256.83  3354.5  255.81  3515.8  252.36  3538.4  252.07
  3801.2  245.15  3890.3  243.81  3910.6  243.17  3935.6  245.47    3991  246.77
  4151.7  247.13  4253.4  248.41  4333.8  245.35  4404.5  244.68  4460.9  246.22
  4665.4  249.78  4729.4  249.34  4838.9  246.27  4932.2  245.34  4953.5  244.05
  4975.4  239.38  5004.6  240.24  5014.7  241.78  5044.7  238.75  5052.5  238.01
  5064.7  238.71    5305  238.59  5425.1  245.05  5465.1  244.31  5527.3  245.85
#Mann= 12 ,-1 , 0
  3253.1     .12       0  3277.5     .05       0  3354.5     .12       0
  3515.8     .05       0  3538.4     .12       0  3890.3     .05       0
  4151.7     .12       0  4404.5     .05       0  4460.9     .12       0
  4838.9     .05       0  5044.7     .03       0  5064.7     .05       0
Bank Sta=5044.7,5064.7
XS Rating Curve= 0 ,0
Exp/Cntr=0.3,0.1

Type RM Length L Ch R = 1 ,2000    ,74,74,74
BEGIN DESCRIPTION:
CRYSTAL CREEK TRIBUTARY NO 7 4.0
END DESCRIPTION:
XS GIS Cut Line= 3
      3843262.33     10137173.99      3841677.29     10136542.49
      3841193.68      10136255.6
#Sta/Elev= 30
  3293.8  257.23  3362.2  255.94    3398  255.13  3908.2  244.26  3991.1  245.26
  4204.4  247.32  4267.4  249.09  4357.9   246.6  4428.9  244.06  4582.4  247.55
  4774.3   249.3  4962.5  244.85  4992.2  239.48  5094.6  243.96  5147.2  241.11
    5153  243.42  5168.7   239.5  5190.1  243.23  5205.7  239.65  5211.5  242.58
  5227.1  239.39  5232.9  241.32  5242.7   239.3  5248.6  242.23 5253.13 240.411
    5262  238.14 5268.93 240.411  5285.6  238.77  5328.5   242.4  5562.3  245.76
#Mann= 10 ,-1 , 0
  3293.8     .12       0  3362.2     .05       0    3398     .12       0
  3991.1     .05       0  4204.4     .12       0  4357.9     .05       0
  4582.4     .12       0  4774.3     .05       0 5253.13     .07       0
 5268.93     .05       0
Bank Sta=5253.13,5268.93
XS Rating Curve= 0 ,0
Exp/Cntr=0.3,0.1

Type RM Length L Ch R = 1 ,1926    ,411,411,411
BEGIN DESCRIPTION:
Mapping XS a5ecf2e1
END DESCRIPTION:
XS GIS Cut Line= 3
      3843271.96     10137149.27      3841739.81     10136493.87
      3841205.95     10136207.41
#Sta/Elev= 30
  3291.1   256.8  3384.3  254.62  3394.2  254.69  3681.2  249.56  3817.6  245.26
  3938.8  244.05  4030.5  246.24  4114.8  244.77    4162  247.89  4207.7   247.9
  4312.9  247.22  4448.7  244.08  4643.5  247.79  4748.1  249.54  4839.7  247.65
  4961.5  242.79  4975.4   241.7  4991.7  237.29  4994.8   235.4  4995.2   234.9
 5004.45 237.263  5013.6  241.51  5057.4  236.76    5209  235.53  5314.8  239.85
  5358.7   238.8  5461.5   241.9  5484.6  242.02  5500.8  244.26  5563.4  244.81
#Mann= 12 ,-1 , 0
  3291.1     .12       0  3384.3     .05       0  3394.2     .12       0
  4030.5     .05       0  4207.7     .12       0  4312.9     .05       0
  4643.5     .12       0  4839.7     .05       0  4994.8     .07       0
 5004.45     .05       0    5209      .1       0  5461.5     .05       0
Bank Sta=4991.7,5004.45
XS Rating Curve= 0 ,0
Exp/Cntr=0.3,0.1

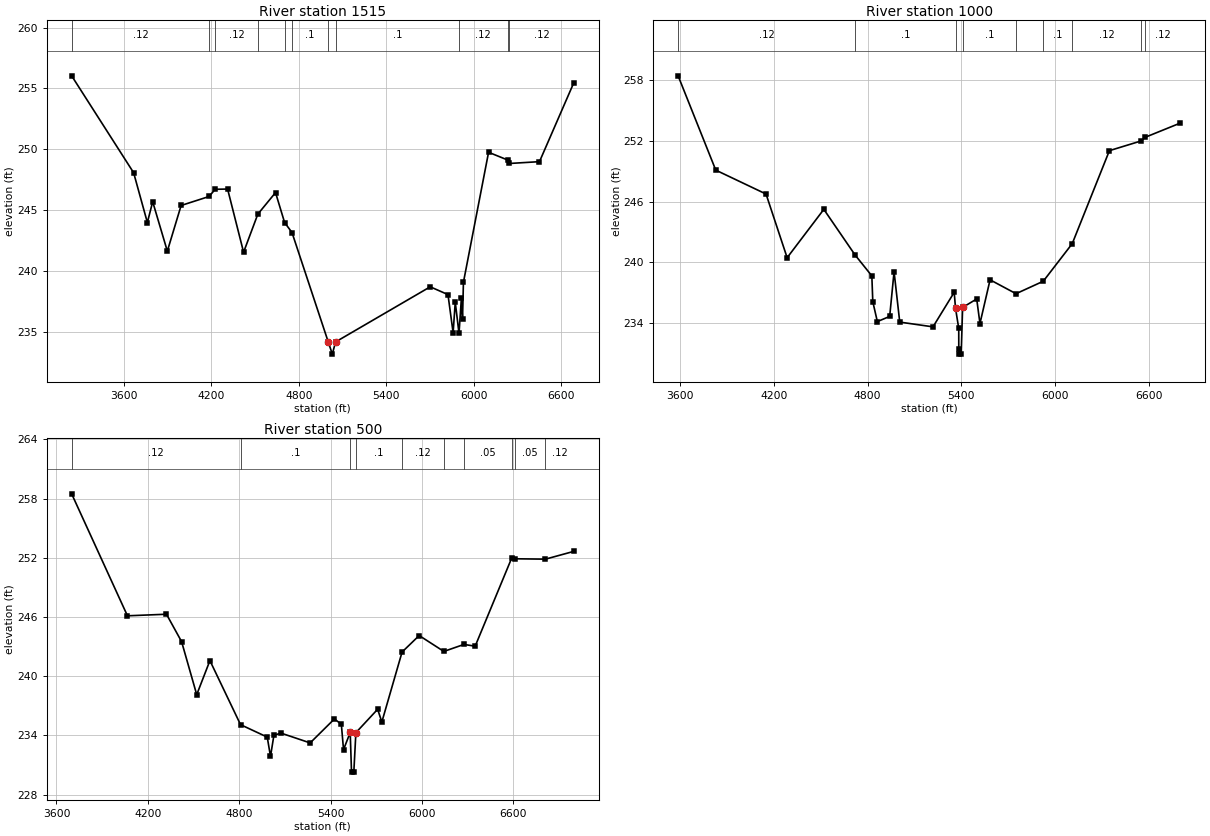
Type RM Length L Ch R = 1 ,1515    ,515,515,515
BEGIN DESCRIPTION:
CRYSTAL CREEK TRIBUTARY NO 7 3.0
END DESCRIPTION:
XS GIS Cut Line= 3
      3843293.58     10137111.49      3841805.36     10136177.38
      3840465.47     10135153.17
#Sta/Elev= 30
  3242.9  256.04  3667.9  248.08  3762.1  243.99  3798.6   245.7    3899  241.64
  3993.5  245.39  4185.6  246.13  4226.9  246.72  4312.3  246.74  4421.9  241.55
  4519.6  244.68    4641  246.45  4703.1  243.99  4753.8  243.17  5002.7  234.17
  5030.4  233.18  5052.5  234.18  5701.7  238.71  5823.4  238.07  5858.7  234.94
  5873.3  237.45  5899.1  234.88  5915.7  237.83  5923.1  236.05  5929.4  239.08
  6101.8  249.76  6231.9  249.13  6243.9  248.84  6450.9  248.99  6686.5  255.48
#Mann= 11 ,-1 , 0
  3242.9     .12       0  4185.6     .05       0  4226.9     .12       0
  4519.6     .05       0  4703.1     .12       0  4753.8      .1       0
  5002.7     .03       0  5052.5      .1       0  5899.1     .12       0
  6231.9     .05       0  6243.9     .12       0
Bank Sta=5002.7,5052.5
XS Rating Curve= 0 ,0
Exp/Cntr=0.3,0.1

Type RM Length L Ch R = 1 ,1000    ,500,500,500
BEGIN DESCRIPTION:
CRYSTAL CREEK TRIBUTARY NO 7 2.0
END DESCRIPTION:
XS GIS Cut Line= 3
      3843408.13     10136939.59      3842283.26     10136082.31
      3840831.42     10135013.55
#Sta/Elev= 30
  3585.7   258.4  3826.8   249.1    4149  246.74  4284.1  240.46  4519.1  245.23
  4719.7  240.72  4826.7  238.67  4832.9  236.12    4862  234.16    4941  234.67
  4969.1  239.08  5005.5  234.11  5218.5  233.64  5354.4  237.05  5362.7  235.48
  5383.5  233.48  5383.6  231.45  5384.1  230.95  5399.2  230.95 5408.22 235.557
  5498.5  236.39  5519.3  233.97  5584.1  238.28  5750.4  236.91    5925  238.14
  6110.6  241.85  6348.6  251.02  6552.3  251.98  6578.2  252.34  6802.8  253.74
#Mann= 9 ,-1 , 0
  3585.7     .12       0  4719.7      .1       0  5362.7     .07       0
 5408.22      .1       0  5750.4     .12       0    5925      .1       0
  6110.6     .12       0  6552.3     .05       0  6578.2     .12       0
Bank Sta=5362.7,5408.22
XS Rating Curve= 0 ,0
Exp/Cntr=0.3,0.1

Type RM Length L Ch R = 1 ,500     ,0,0,0
BEGIN DESCRIPTION:
CRYSTAL CREEK TRIBUTARY NO 7 1.0
END DESCRIPTION:
XS GIS Cut Line= 3
       3843491.5     10136871.92      3842681.88     10135854.43
      3840923.77     10134908.35
#Sta/Elev= 30
  3699.7  258.48    4066  246.12  4322.2  246.28  4421.5   243.5  4520.8  238.13
  4607.4  241.58  4808.4  235.09  4983.7  233.83  5005.1  231.87  5027.3     234
  5072.7  234.24  5265.5  233.24  5424.7  235.67  5470.2  235.13  5484.5  232.56
  5528.4   234.3    5537  230.28  5552.1  230.28  5565.6 234.276  5708.5  236.65
  5736.1  235.36  5868.9  242.45  5981.2  244.12  6143.1  242.51  6275.3  243.22
  6348.7  243.04  6588.5  251.97  6608.3   251.9  6809.8  251.86  6996.5  252.65
#Mann= 10 ,-1 , 0
  3699.7     .12       0  4808.4      .1       0  5528.4     .07       0
  5565.6      .1       0  5868.9     .12       0  6143.1      .1       0
  6275.3     .05       0  6588.5     .12       0  6608.3     .05       0
  6809.8     .12       0
Bank Sta=5528.4,5565.6
XS Rating Curve= 0 ,0
Exp/Cntr=0.3,0.1