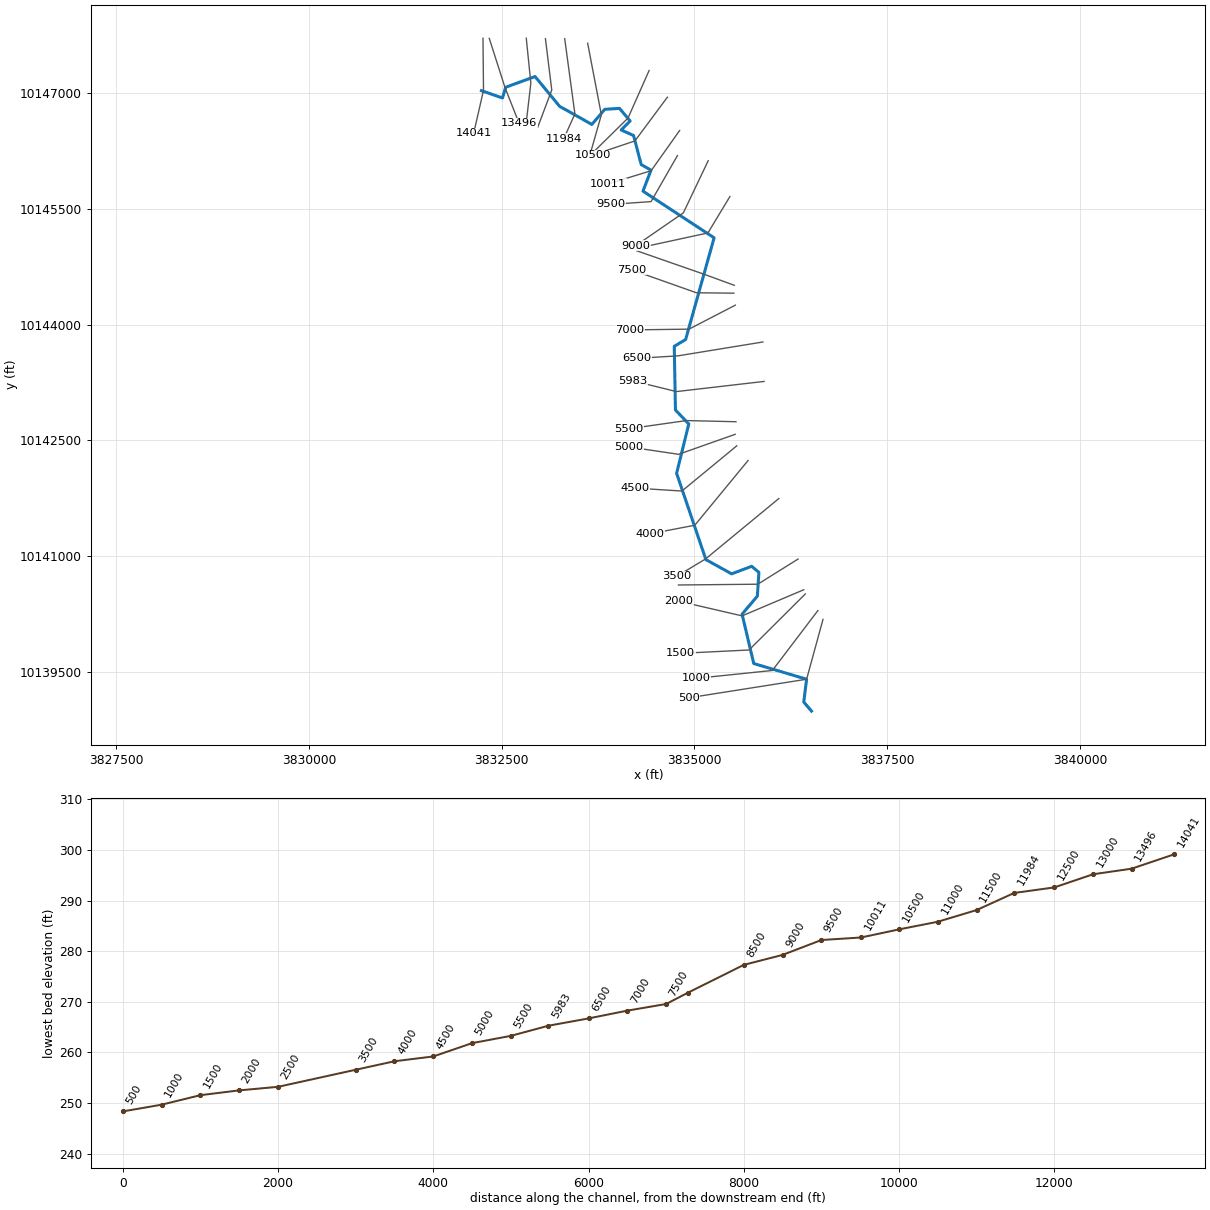
--- CRYSTAL CREEK TRIBUTARY NO 8.prj (project) ---

Proj Title=CRYSTAL CREEK TRIBUTARY NO 8 Base Level Engineering
Current Plan=p01
Default Exp/Contr=0.3,0.1
English Units
Geom File=g01
Flow File=f01
Plan File=p01
Y Axis Title=Elevation
X Axis Title(PF)=Main Channel Distance
X Axis Title(XS)=Station
BEGIN DESCRIPTION:
CRYSTAL CREEK TRIBUTARY NO 8
END DESCRIPTION:
DSS Export Rating Curves= 0
DSS Export Rating Curve Sorted= 0
DSS Export Volume Flow Curves= 0
DXF OffsetX= 0
DXF OffsetY= 0
DXF ScaleX= 1
DXF ScaleY= 10

--- CRYSTAL CREEK TRIBUTARY NO 8.p01 (plan) ---

Plan Title=Multiple Run
Short Identifier=Multiple
Geom File=g01
Flow File=f01
Subcritical Flow
K Sum by GR= 0
Std Step Tol= 0.01
Critical Tol= 0.01
Num of Std Step Trials= 20
Max Error Tol= 0.3
Flow Tol Ratio= 0.001
Split Flow NTrial= 30
Split Flow Tol= 0.02
Split Flow Ratio= 0.02
Log Output Level= 0
Friction Slope Method= 1
Unsteady Friction Slope Method= 2
Unsteady Bridges Friction Slope Method= 1
Parabolic Critical Depth
Global Vel Dist=  1 , 1 , 1
Global Log Level= 0
CheckData=True
Encroach Param= -1, 0, 0, 0
BEGIN DESCRIPTION:
Multiple Run
END DESCRIPTION:

--- CRYSTAL CREEK TRIBUTARY NO 8.f01 (steady flow) ---

Flow Title=Multiple
Program Version=4.10
Number of Profiles= 7
Profile Names=10-year,25-year,50-year,1pct_min,100-year,1pct_plu,500-year
River Rch & RM=CRYSTAL CREEK TR,Reach-1         ,14041
     765    1042    1413     631    1906    5756    3576
River Rch & RM=CRYSTAL CREEK TR,Reach-1         ,11000
    1121    1551    2128     958    2893    8737    5528
Boundary for River Rch & Prof#=CRYSTAL CREEK TR,Reach-1         , 1
Up Type= 0
Dn Type= 3
Dn Slope=0.005
Boundary for River Rch & Prof#=CRYSTAL CREEK TR,Reach-1         , 2
Up Type= 0
Dn Type= 3
Dn Slope=0.005
Boundary for River Rch & Prof#=CRYSTAL CREEK TR,Reach-1         , 3
Up Type= 0
Dn Type= 3
Dn Slope=0.005
Boundary for River Rch & Prof#=CRYSTAL CREEK TR,Reach-1         , 4
Up Type= 0
Dn Type= 3
Dn Slope=0.005
Boundary for River Rch & Prof#=CRYSTAL CREEK TR,Reach-1         , 5
Up Type= 0
Dn Type= 3
Dn Slope=0.005
Boundary for River Rch & Prof#=CRYSTAL CREEK TR,Reach-1         , 6
Up Type= 0
Dn Type= 3
Dn Slope=0.005
Boundary for River Rch & Prof#=CRYSTAL CREEK TR,Reach-1         , 7
Up Type= 0
Dn Type= 3
Dn Slope=0.005
DSS Import GetInterval= 0
DSS Import GetPeak= 0
DSS Import FillOption= 0

--- CRYSTAL CREEK TRIBUTARY NO 8.g01 (geometry) ---

Geom Title=Existing Conditions
Program Version=4.10

River Reach=CRYSTAL CREEK TR,Reach-1
Reach XY= 30
      3832238.24     10147036.86      3832510.83     10146941.62
      3832552.79     10147080.96      3832933.53     10147219.77
      3833251.23     10146833.69      3833669.95      10146598.5
      3833837.38     10146794.43      3834028.24     10146806.86
      3834166.87     10146642.71      3834050.75     10146526.19
      3834210.78     10146454.71      3834310.21     10146077.02
      3834437.22     10146004.58      3834332.77     10145732.93
      3835255.49     10145127.59      3834886.41     10143807.67
      3834738.52     10143719.75      3834754.24     10142893.57
      3834926.89     10142711.89      3834769.15     10142071.16
      3835149.16     10140951.93      3835482.41     10140767.76
      3835742.52     10140865.44      3835836.41     10140786.24
      3835816.28     10140477.67      3835618.19      10140244.7
      3835769.39     10139603.79      3836454.74     10139400.46
      3836418.52     10139104.01      3836518.24     10138986.86

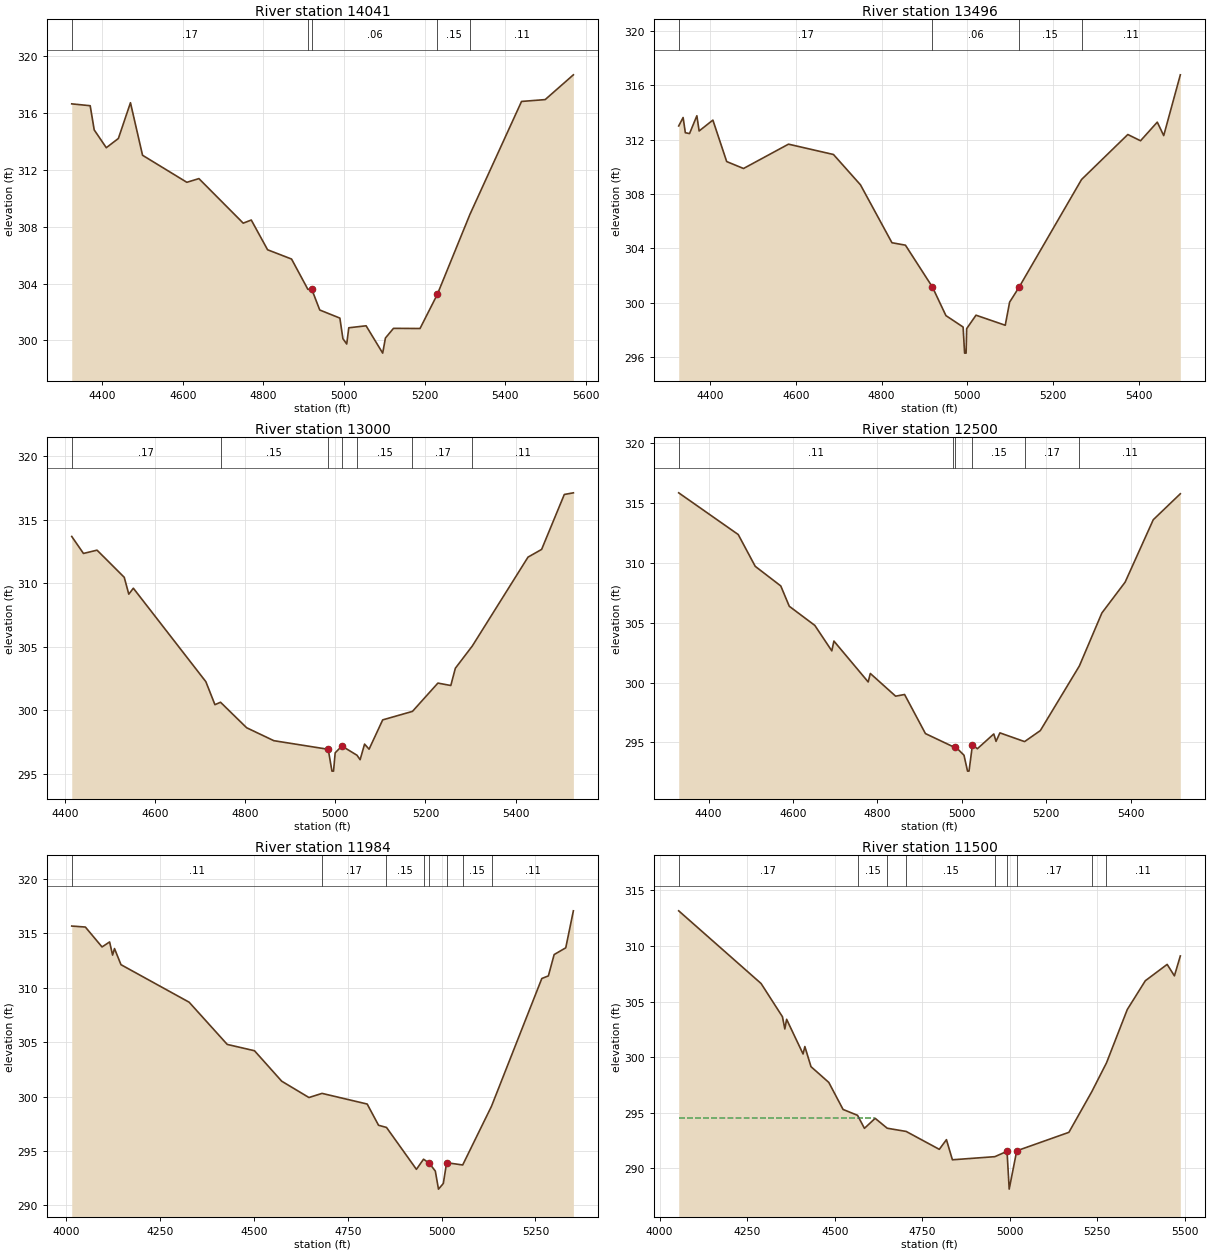
Type RM Length L Ch R = 1 ,14041   ,545,545,545
BEGIN DESCRIPTION:
CRYSTAL CREEK TRIBUTARY NO 8 27.0
END DESCRIPTION:
XS GIS Cut Line= 3
      3832258.11     10147716.83      3832264.76     10147040.76
      3832137.77      10146485.6
#Sta/Elev= 30
  4323.9  316.62  4369.7  316.49  4379.7  314.79  4409.7  313.54  4439.7  314.19
  4469.7   316.7  4499.7  313.01  4609.7  311.11  4639.7  311.37  4749.7  308.24
  4769.7  308.46  4810.2  306.37  4869.7  305.72  4910.3  303.59  4919.7  303.61
  4939.7  302.14  4989.7  301.57  4997.3  300.12  5006.7  299.75  5011.8  300.89
  5054.8  301.03    5096  299.11  5102.8  300.17  5122.8  300.85  5188.7  300.84
  5231.6  303.23  5312.7  308.86  5440.8  316.79  5499.5  316.92  5569.5  318.66
#Mann= 5 ,-1 , 0
  4323.9     .17       0  4910.3     .15       0  4919.7     .06       0
  5231.6     .15       0  5312.7     .11       0
Bank Sta=4919.7,5231.6
XS Rating Curve= 0 ,0
Exp/Cntr=0.3,0.1

Type RM Length L Ch R = 1 ,13496   ,496,496,496
BEGIN DESCRIPTION:
CRYSTAL CREEK TRIBUTARY NO 8 26.0
END DESCRIPTION:
XS GIS Cut Line= 3
      3832339.49     10147715.16      3832544.71     10147073.69
      3832727.52     10146610.99
#Sta/Elev= 30
  4326.5     313  4336.8  313.62    4342   312.5  4351.8  312.44  4368.9  313.75
  4374.2  312.63  4406.3  313.43  4438.5  310.38  4477.8  309.87  4582.8  311.66
  4687.8   310.9  4750.8  308.67  4824.3  304.41  4855.8  304.23  4918.8  301.15
  4950.3  299.05  4990.4  298.21  4993.9  296.29  4997.4  296.29  4998.7  298.09
  5020.5  299.08  5088.8  298.34    5099  300.04  5121.1  301.14  5266.9  309.06
  5374.9  312.37  5404.6  311.91  5443.7  313.28  5458.7  312.29  5497.5  316.76
#Mann= 4 ,-1 , 0
  4326.5     .17       0  4918.8     .06       0  5121.1     .15       0
  5266.9     .11       0
Bank Sta=4918.8,5121.1
XS Rating Curve= 0 ,0
Exp/Cntr=0.3,0.1

Type RM Length L Ch R = 1 ,13000   ,500,500,500
BEGIN DESCRIPTION:
CRYSTAL CREEK TRIBUTARY NO 8 25.0
END DESCRIPTION:
XS GIS Cut Line= 3
      3832819.53      10147716.9      3832878.64      10147135.5
      3832817.86     10146611.11
#Sta/Elev= 30
  4415.6  313.69  4441.6  312.35  4471.7  312.61    4532  310.47  4542.1  309.14
  4552.2  309.61    4713  302.24  4733.1  300.43  4745.5  300.62  4803.4  298.61
  4863.7  297.59  4984.3  296.91  4992.6  295.19  4996.1  295.19  4999.7  296.63
  5014.5  297.17  5048.2  296.44    5055  296.09  5064.9  297.32  5074.9  296.92
  5105.1  299.23  5171.1   299.9  5227.5  302.13  5256.1  301.94  5266.2   303.3
  5303.9  305.06  5427.3  312.06  5457.5  312.67  5507.8     317  5527.9  317.13
#Mann= 7 ,-1 , 0
  4415.6     .17       0  4745.5     .15       0  4984.3     .06       0
  5014.5     .17       0  5048.2     .15       0  5171.1     .17       0
  5303.9     .11       0
Bank Sta=4984.3,5014.5
XS Rating Curve= 0 ,0
Exp/Cntr=0.3,0.1

Type RM Length L Ch R = 1 ,12500   ,516,516,516
BEGIN DESCRIPTION:
CRYSTAL CREEK TRIBUTARY NO 8 24.0
END DESCRIPTION:
XS GIS Cut Line= 3
      3833067.86     10147711.03      3833149.97     10147045.28
      3832967.86      10146561.1
#Sta/Elev= 30
  4329.2  315.87  4470.2  312.38  4510.5  309.72    4571  308.08  4591.1  306.38
  4651.6  304.78  4691.8  302.65  4696.8  303.47    4778  300.05    4783  300.76
    4843  298.86  4864.2     299  4913.6  295.73  4979.3  294.63  4984.1  294.65
  5004.9  293.92  5013.3  292.59  5016.8  292.59 5025.02294.8022  5036.5  294.46
  5075.5   295.7  5080.8  295.08    5090  295.79  5148.4  295.06  5185.7  295.98
  5278.2  301.39  5331.5  305.82  5386.6   308.4  5453.2  313.62  5517.3  315.79
#Mann= 6 ,-1 , 0
  4329.2     .11       0  4979.3     .15       0  4984.1     .06       0
 5025.02     .15       0  5148.4     .17       0  5278.2     .11       0
Bank Sta=4984.1,5025.02
XS Rating Curve= 0 ,0
Exp/Cntr=0.3,0.1

Type RM Length L Ch R = 1 ,11984   ,484,484,484
BEGIN DESCRIPTION:
CRYSTAL CREEK TRIBUTARY NO 8 23.0
END DESCRIPTION:
XS GIS Cut Line= 3
      3833317.86     10147711.04      3833450.09     10146734.65
      3833305.99     10146414.38
#Sta/Elev= 30
  4014.7  315.68    4051  315.59  4095.4  313.76  4115.6  314.22  4123.5  313.01
  4128.6  313.61  4145.9  312.13  4327.5  308.68    4429   304.8  4501.6  304.22
  4574.1  301.42  4646.7  299.92  4681.6   300.3  4801.9  299.32  4832.1  297.37
  4853.3  297.17    4933  293.32    4952  294.25 4967.26293.8817  4983.4  293.16
  4991.8   291.5  5004.7  292.02  5013.5  293.93  5056.3  293.72  5133.1  299.12
  5267.1  310.86  5284.6   311.1    5300  313.06  5330.9  313.68  5351.2  317.08
#Mann= 8 ,-1 , 0
  4014.7     .11       0  4681.6     .17       0  4853.3     .15       0
    4952     .17       0 4967.26     .06       0  5013.5     .17       0
  5056.3     .15       0  5133.1     .11       0
Bank Sta=4967.26,5013.5
XS Rating Curve= 0 ,0
Exp/Cntr=0.3,0.1

Type RM Length L Ch R = 1 ,11500   ,500,500,500
BEGIN DESCRIPTION:
CRYSTAL CREEK TRIBUTARY NO 8 22.0
END DESCRIPTION:
XS GIS Cut Line= 3
      3833615.53     10147652.12      3833793.35     10146723.39
      3833660.15     10146254.86
#Sta/Elev= 30
  4054.4  313.16  4289.7  306.62  4350.7  303.63  4357.5  302.53  4362.6   303.4
  4409.6  300.28  4414.7  300.95  4432.2  299.14  4483.1  297.72  4523.8  295.29
  4565.2  294.76  4584.9  293.59  4615.5  294.49  4649.9   293.6  4704.1  293.31
  4798.7   291.7  4819.1  292.57  4836.1  290.76  4957.2  291.04  4992.2  291.52
  4998.3  288.12 5019.86 291.568  5168.8  293.23  5234.1  296.88  5276.2  299.48
  5335.6  304.28  5387.1  306.87  5449.5  308.34  5470.2  307.31  5487.1   309.1
#Mann= 9 ,-1 , 0
  4054.4     .17       0  4565.2     .15       0  4649.9     .11       0
  4704.1     .15       0  4957.2     .17       0  4992.2     .09       0
 5019.86     .17       0  5234.1     .15       0  5276.2     .11       0
#XS Ineff= 2 , 0
          4615.8  294.52
Permanent Ineff=
       F       F
Bank Sta=4992.2,5019.86
XS Rating Curve= 0 ,0
Exp/Cntr=0.3,0.1

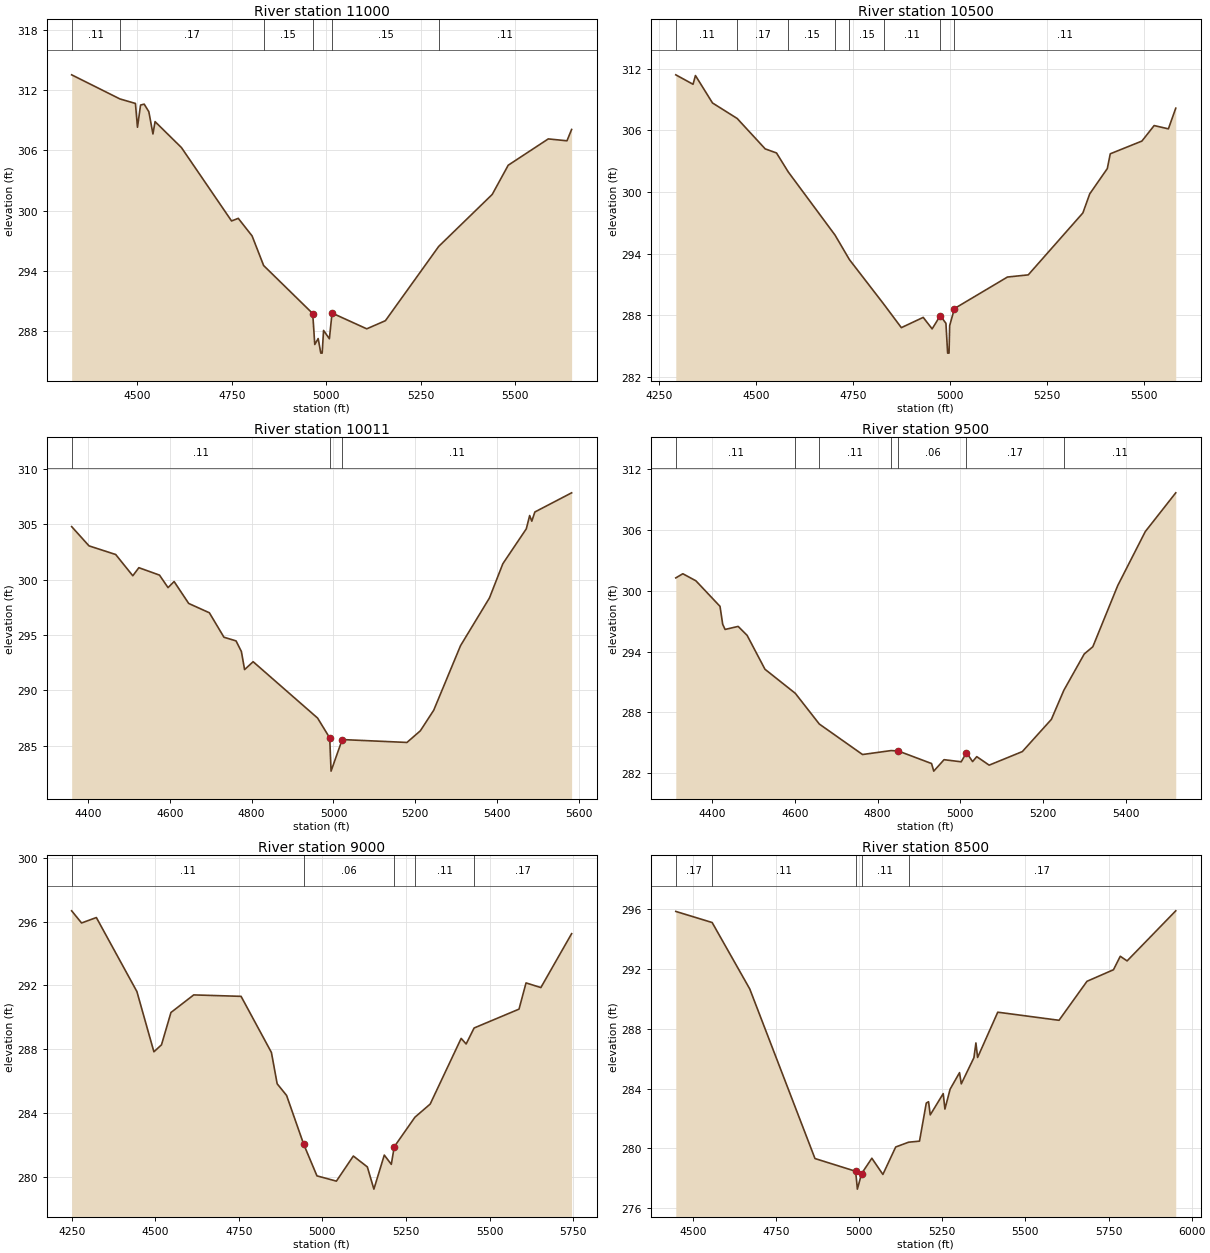
Type RM Length L Ch R = 1 ,11000   ,500,500,500
BEGIN DESCRIPTION:
CRYSTAL CREEK TRIBUTARY NO 8 21.0
END DESCRIPTION:
XS GIS Cut Line= 3
      3834412.41     10147297.93      3834139.18     10146681.57
      3833675.98     10146225.57
#Sta/Elev= 30
  4325.8  313.52  4453.6  311.12  4494.7  310.67  4500.1   308.3  4508.3  310.51
  4517.9   310.6  4530.2  309.85  4541.1  307.63  4546.7  308.86  4616.5  306.28
  4749.3  298.97  4767.1  299.23  4803.7  297.48  4834.3  294.53  4964.3  289.75
  4969.7  286.67  4978.7  287.26  4985.7  285.81  4989.3  285.81    4993  288.07
  5008.4  287.24  5015.5   289.8  5107.4  288.23  5156.8  289.04  5298.1  296.44
  5439.7  301.61  5482.1  304.52  5588.2  307.14  5637.7  306.95    5650  308.08
#Mann= 6 ,-1 , 0
  4325.8     .11       0  4453.6     .17       0  4834.3     .15       0
  4964.3     .09       0  5015.5     .15       0  5298.1     .11       0
Bank Sta=4964.3,5015.5
XS Rating Curve= 0 ,0
Exp/Cntr=0.3,0.1

Type RM Length L Ch R = 1 ,10500   ,489,489,489
BEGIN DESCRIPTION:
CRYSTAL CREEK TRIBUTARY NO 8 20.0
END DESCRIPTION:
XS GIS Cut Line= 3
      3834649.39     10146951.59      3834228.77     10146384.82
      3833678.08       10146199.
#Sta/Elev= 30
  4294.2   311.4  4338.6  310.48  4344.8  311.33  4388.7  308.66  4452.2  307.15
  4524.3  304.19  4553.5  303.79  4583.6  301.95  4704.2  295.79  4741.1  293.41
  4830.2  289.04  4874.8  286.78  4931.1  287.78  4954.1  286.66    4975  287.95
  4989.6   287.2    4994   284.3  4997.6   284.3  4999.2  286.98  5011.5  288.64
    5148  291.71  5201.5  291.92  5342.1  297.95  5359.8  299.81    5405  302.27
  5412.6  303.71  5494.1  304.95  5525.6  306.46  5562.3  306.14  5581.2  308.15
#Mann= 8 ,-1 , 0
  4294.2     .11       0  4452.2     .17       0  4583.6     .15       0
  4704.2     .11       0  4741.1     .15       0  4830.2     .11       0
    4975     .06       0  5011.5     .11       0
Bank Sta=4975,5011.5
XS Rating Curve= 0 ,0
Exp/Cntr=0.3,0.1

Type RM Length L Ch R = 1 ,10011   ,511,511,511
BEGIN DESCRIPTION:
CRYSTAL CREEK TRIBUTARY NO 8 19.0
END DESCRIPTION:
XS GIS Cut Line= 3
      3834808.27     10146519.34      3834438.26     10145997.63
      3833881.99     10145826.84
#Sta/Elev= 30
  4360.4  304.78  4402.8  303.04    4468  302.26  4509.8  300.34  4524.6  301.07
    4575   300.4  4595.9  299.27  4610.7  299.82  4646.4  297.84  4696.8     297
  4732.5  294.79    4762  294.46  4775.1   293.5  4782.9  291.87  4803.8  292.58
  4961.3  287.49  4990.9   285.7  4994.2   282.7  5021.4  285.55  5179.6  285.29
  5212.3  286.34    5245   288.2  5310.5  294.03  5381.2  298.34  5413.9  301.43
  5471.2  304.58  5479.4  305.78  5484.6  305.27  5492.1   306.1  5581.9  307.83
#Mann= 3 , 0 , 0
  4360.4     .11       0  4990.9     .09       0  5021.4     .11       0
Bank Sta=4990.9,5021.4
XS Rating Curve= 0 ,0
Exp/Cntr=0.3,0.1

Type RM Length L Ch R = 1 ,9500    ,500,500,500
BEGIN DESCRIPTION:
CRYSTAL CREEK TRIBUTARY NO 8 18.0
END DESCRIPTION:
XS GIS Cut Line= 3
      3834779.62     10146193.81      3834437.71     10145597.13
      3833917.86     10145561.07
#Sta/Elev= 30
  4312.3  301.28  4329.3  301.69    4361  300.99  4419.2  298.47  4425.7   296.7
  4431.5  296.19  4463.1  296.49  4484.7  295.61  4527.9  292.26  4601.3  289.88
  4659.3  286.85  4763.8  283.84    4833  284.23  4850.1  284.19  4930.7  282.95
    4936   282.2  4960.9  283.33  5002.4  283.12  5015.1  284.03  5029.9  283.14
    5040  283.63    5070  282.79  5150.2  284.13  5220.4  287.31  5250.5  290.18
  5299.9  293.77  5320.6  294.48  5380.8  300.52  5447.4  305.85  5521.1  309.68
#Mann= 7 ,-1 , 0
  4312.3     .11       0  4601.3     .17       0  4659.3     .11       0
    4833     .17       0  4850.1     .06       0  5015.1     .17       0
  5250.5     .11       0
Bank Sta=4850.1,5015.1
XS Rating Curve= 0 ,0
Exp/Cntr=0.3,0.1

Type RM Length L Ch R = 1 ,9000    ,500,500,500
BEGIN DESCRIPTION:
CRYSTAL CREEK TRIBUTARY NO 8 17.0
END DESCRIPTION:
XS GIS Cut Line= 3
      3835178.91     10146127.82      3834856.27     10145450.55
      3834242.12      10145027.6
#Sta/Elev= 30
  4249.8  296.67  4279.4  295.91  4323.7  296.25    4445  291.62  4495.9  287.85
  4518.6  288.29  4546.9  290.31    4615  291.41  4756.7  291.32  4847.5  287.81
  4864.7  285.85  4892.9  285.12    4944  282.07  4983.7  280.09  5041.9  279.76
  5092.6  281.33  5134.5  280.65  5154.1  279.26  5185.2  281.39  5206.2  280.81
    5215  281.91  5276.9  283.76  5322.5  284.58  5415.2  288.69  5430.1  288.34
  5453.9  289.34  5588.3  290.52  5609.3  292.16  5653.7  291.87  5745.7  295.24
#Mann= 5 ,-1 , 0
  4249.8     .11       0    4944     .06       0    5215     .17       0
  5276.9     .11       0  5453.9     .17       0
Bank Sta=4944,5215
XS Rating Curve= 0 ,0
Exp/Cntr=0.3,0.1

Type RM Length L Ch R = 1 ,8500    ,721,721,721
BEGIN DESCRIPTION:
CRYSTAL CREEK TRIBUTARY NO 8 16.0
END DESCRIPTION:
XS GIS Cut Line= 3
      3835460.15     10145662.52      3835175.41     10145190.68
      3834244.83     10144988.91
#Sta/Elev= 30
  4448.9  295.81  4558.2  295.07  4671.3  290.64  4867.4  279.33  4989.7  278.48
  4994.9  277.29  5007.7  278.33  5038.4  279.35  5071.6  278.27  5110.1   280.1
    5149  280.42  5181.7  280.49  5202.1  283.03  5208.9  283.12    5214  282.24
    5253  283.66  5258.1  282.63  5273.8  283.96  5302.1  285.06  5307.3  284.31
  5345.4  286.06  5351.3  287.04  5356.4  286.07    5417  289.09  5601.2  288.55
  5685.3  291.15  5764.9  291.92  5785.4  292.82  5805.9  292.51  5952.2  295.85
#Mann= 5 ,-1 , 0
  4448.9     .17       0  4558.2     .11       0  4989.7     .06       0
  5007.7     .11       0    5149     .17       0
Bank Sta=4989.7,5007.7
XS Rating Curve= 0 ,0
Exp/Cntr=0.3,0.1

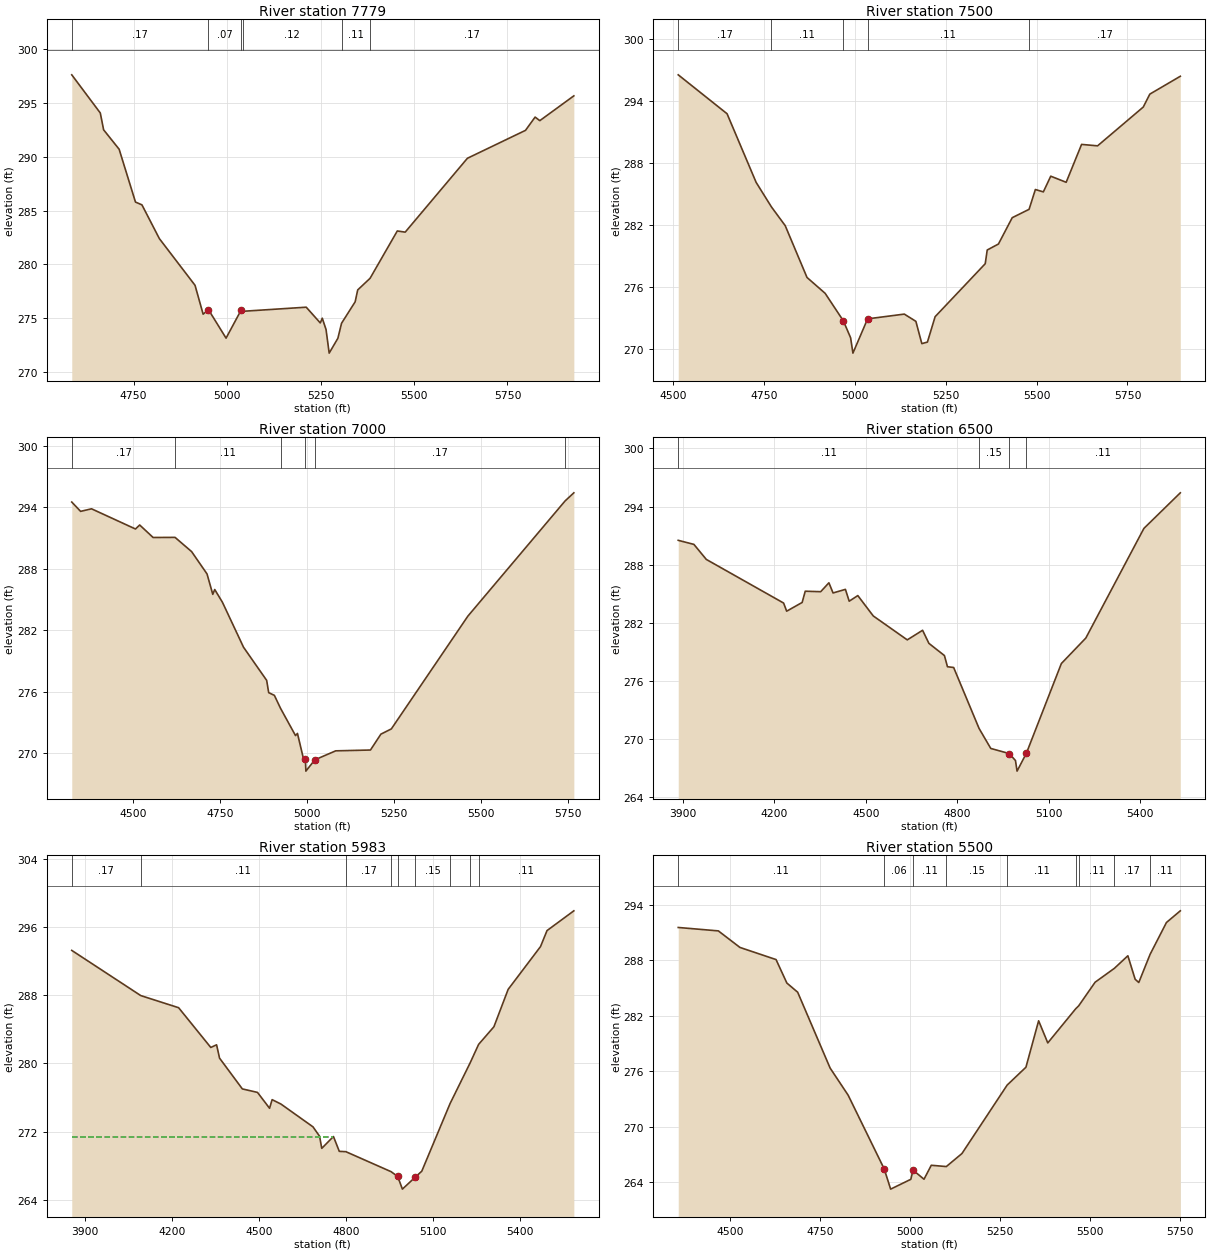
Type RM Length L Ch R = 1 ,7779    ,279,279,279
BEGIN DESCRIPTION:
CRYSTAL CREEK TRIBUTARY NO 8 15.0
END DESCRIPTION:
XS GIS Cut Line= 3
      3835517.86     10144511.07      3835127.76     10144653.83
      3834251.93     10144959.06
#Sta/Elev= 30
  4584.6  297.59  4660.9  294.05  4669.8  292.49  4711.3  290.69    4755  285.79
  4772.3  285.53  4818.9   282.4  4914.3  278.07    4936  275.39  4950.2  275.81
  4997.3  273.17  5037.1  275.74  5042.4  275.66  5211.7  276.04  5249.3  274.58
  5254.6  275.02  5264.7  273.97  5273.1  271.78  5296.4  273.16  5306.2  274.55
  5342.6  276.54  5349.4  277.64  5382.5  278.72  5455.3  283.11  5476.4     283
  5642.8  289.85  5798.2  292.44  5823.9  293.67  5836.5  293.34  5927.5  295.64
#Mann= 6 ,-1 , 0
  4584.6     .17       0  4950.2     .07       0  5037.1     .11       0
  5042.4     .12       0  5306.2     .11       0  5382.5     .17       0
Bank Sta=4950.2,5037.1
XS Rating Curve= 0 ,0
Exp/Cntr=0.3,0.1

Type RM Length L Ch R = 1 ,7500    ,500,500,500
BEGIN DESCRIPTION:
CRYSTAL CREEK TRIBUTARY NO 8 14.0
END DESCRIPTION:
XS GIS Cut Line= 3
      3835512.21     10144409.06      3835025.94      10144414.5
      3834181.77     10144713.34
#Sta/Elev= 30
  4513.7  296.52  4648.1  292.75  4728.1   286.1  4770.3  283.72  4808.1  281.91
  4868.1  276.89  4918.1  275.35  4968.1  272.69  4988.1  271.05  4994.5  269.56
  5034.9  272.88  5135.9  273.34  5167.7  272.64  5184.1  270.48  5199.5  270.63
  5220.7  273.09  5358.6  278.22  5364.1  279.55    5395  280.13  5432.9  282.68
  5479.3  283.49  5496.6  285.41  5518.6  285.18  5538.9   286.7  5581.4  286.11
  5623.8  289.78  5667.8  289.64  5793.6   293.4  5811.6  294.65  5895.5  296.38
#Mann= 5 ,-1 , 0
  4513.7     .17       0  4770.3     .11       0  4968.1     .06       0
  5034.9     .11       0  5479.3     .17       0
Bank Sta=4968.1,5034.9
XS Rating Curve= 0 ,0
Exp/Cntr=0.3,0.1

Type RM Length L Ch R = 1 ,7000    ,500,500,500
BEGIN DESCRIPTION:
CRYSTAL CREEK TRIBUTARY NO 8 13.0
END DESCRIPTION:
XS GIS Cut Line= 3
      3835530.44     10144253.66      3834929.42     10143942.28
      3834163.28     10143932.49
#Sta/Elev= 30
  4323.1  294.52  4348.5  293.61  4379.9  293.86  4506.2  291.89  4518.3  292.28
  4556.9  291.06    4620  291.07  4667.6  289.68  4711.9   287.5  4728.4  285.51
    4734  285.98  4756.1  284.74  4816.9  280.34  4883.3  277.11  4889.1  275.91
  4905.4  275.65  4923.2  274.38  4966.2  271.72  4971.8  271.93  4988.3  269.57
 4994.56269.4023    4996  268.25  5021.6  269.35  5081.6  270.23  5181.6  270.31
  5211.6  271.86  5241.6  272.37  5461.6  283.38  5741.1  294.63  5766.2  295.42
#Mann= 6 ,-1 , 0
  4323.1     .17       0    4620     .11       0  4923.2     .17       0
 4994.56     .06       0  5021.6     .17       0  5741.1     .11       0
Bank Sta=4994.56,5021.6
XS Rating Curve= 0 ,0
Exp/Cntr=0.3,0.1

Type RM Length L Ch R = 1 ,6500    ,517,517,517
BEGIN DESCRIPTION:
CRYSTAL CREEK TRIBUTARY NO 8 12.0
END DESCRIPTION:
XS GIS Cut Line= 3
       3835888.6     10143775.95      3834788.49     10143596.21
       3834258.8     10143563.57
#Sta/Elev= 30
  3885.3  290.52  3936.7   290.1  3977.3  288.55  4230.6  284.05  4240.7  283.21
  4291.4  284.11  4301.5  285.27  4352.2  285.22  4379.1  286.14  4392.7  285.09
  4433.2  285.46  4445.6  284.24  4473.8  284.82  4524.4  282.72  4635.9  280.25
  4686.1  281.24  4706.8  279.89  4757.7  278.63  4767.6  277.48  4787.9   277.4
  4871.1  271.12  4909.5  269.05  4970.3  268.52  4990.5   267.8  4995.7  266.71
 5026.54268.5758  5140.9  277.81  5221.1  280.44  5411.4  291.75  5530.7  295.42
#Mann= 4 ,-1 , 0
  3885.3     .11       0  4871.1     .15       0  4970.3     .06       0
 5026.54     .11       0
Bank Sta=4970.3,5026.54
XS Rating Curve= 0 ,0
Exp/Cntr=0.3,0.1

Type RM Length L Ch R = 1 ,5983    ,483,483,483
BEGIN DESCRIPTION:
CRYSTAL CREEK TRIBUTARY NO 8 11.0
END DESCRIPTION:
XS GIS Cut Line= 3
      3835903.72     10143264.09      3834766.43     10143132.33
      3834198.02     10143272.77
#Sta/Elev= 30
  3855.1  293.26    4093  287.96  4223.4  286.54  4334.2  281.88  4354.2  282.19
  4364.4  280.63    4443  277.02  4495.2  276.61  4536.8  274.75  4545.6  275.76
  4575.8  275.25  4686.5  272.57  4709.2  271.47  4716.7  270.05    4757  271.44
  4777.1   269.7  4799.8  269.66  4955.4  267.32  4978.4  266.76  4994.6  265.27
  5039.7   266.7  5061.4  267.37  5158.9   275.3  5228.2  280.08  5257.3  282.24
  5310.1  284.31  5359.1  288.69  5470.7  293.71    5493  295.58  5585.5   297.9
#Mann= 9 ,-1 , 0
  3855.1     .17       0    4093     .11       0  4799.8     .17       0
  4955.4     .15       0  4978.4     .06       0  5039.7     .15       0
  5158.9     .17       0  5228.2     .15       0  5257.3     .11       0
#XS Ineff= 2 , 0
         4756.94  271.44
Permanent Ineff=
       F       F
Bank Sta=4978.4,5039.7
XS Rating Curve= 0 ,0
Exp/Cntr=0.3,0.1

Type RM Length L Ch R = 1 ,5500    ,500,500,500
BEGIN DESCRIPTION:
CRYSTAL CREEK TRIBUTARY NO 8 10.0
END DESCRIPTION:
XS GIS Cut Line= 3
      3835539.14     10142741.09      3834896.22     10142756.22
      3834153.76     10142650.81
#Sta/Elev= 30
  4356.9  291.56  4468.2  291.19  4528.2   289.4  4628.3  288.09  4658.3  285.55
  4688.3  284.56  4778.3  276.36  4828.3  273.43  4928.3  265.46  4946.2  263.27
  5002.2  264.33  5008.4  265.32  5038.8  264.34    5059  265.85  5100.7  265.71
  5144.1  267.12  5269.5  274.52  5321.6  276.45  5356.8  281.47  5382.2  279.08
  5459.9  282.78  5467.8  283.08  5513.5  285.64  5566.9  287.14  5604.4   288.5
  5624.6  285.96  5634.7  285.61    5666  288.65  5711.5   292.1  5749.9  293.36
#Mann= 9 ,-1 , 0
  4356.9     .11       0  4928.3     .06       0  5008.4     .11       0
  5100.7     .15       0  5269.5     .11       0  5459.9     .17       0
  5467.8     .11       0  5566.9     .17       0    5666     .11       0
Bank Sta=4928.3,5008.4
XS Rating Curve= 0 ,0
Exp/Cntr=0.3,0.1

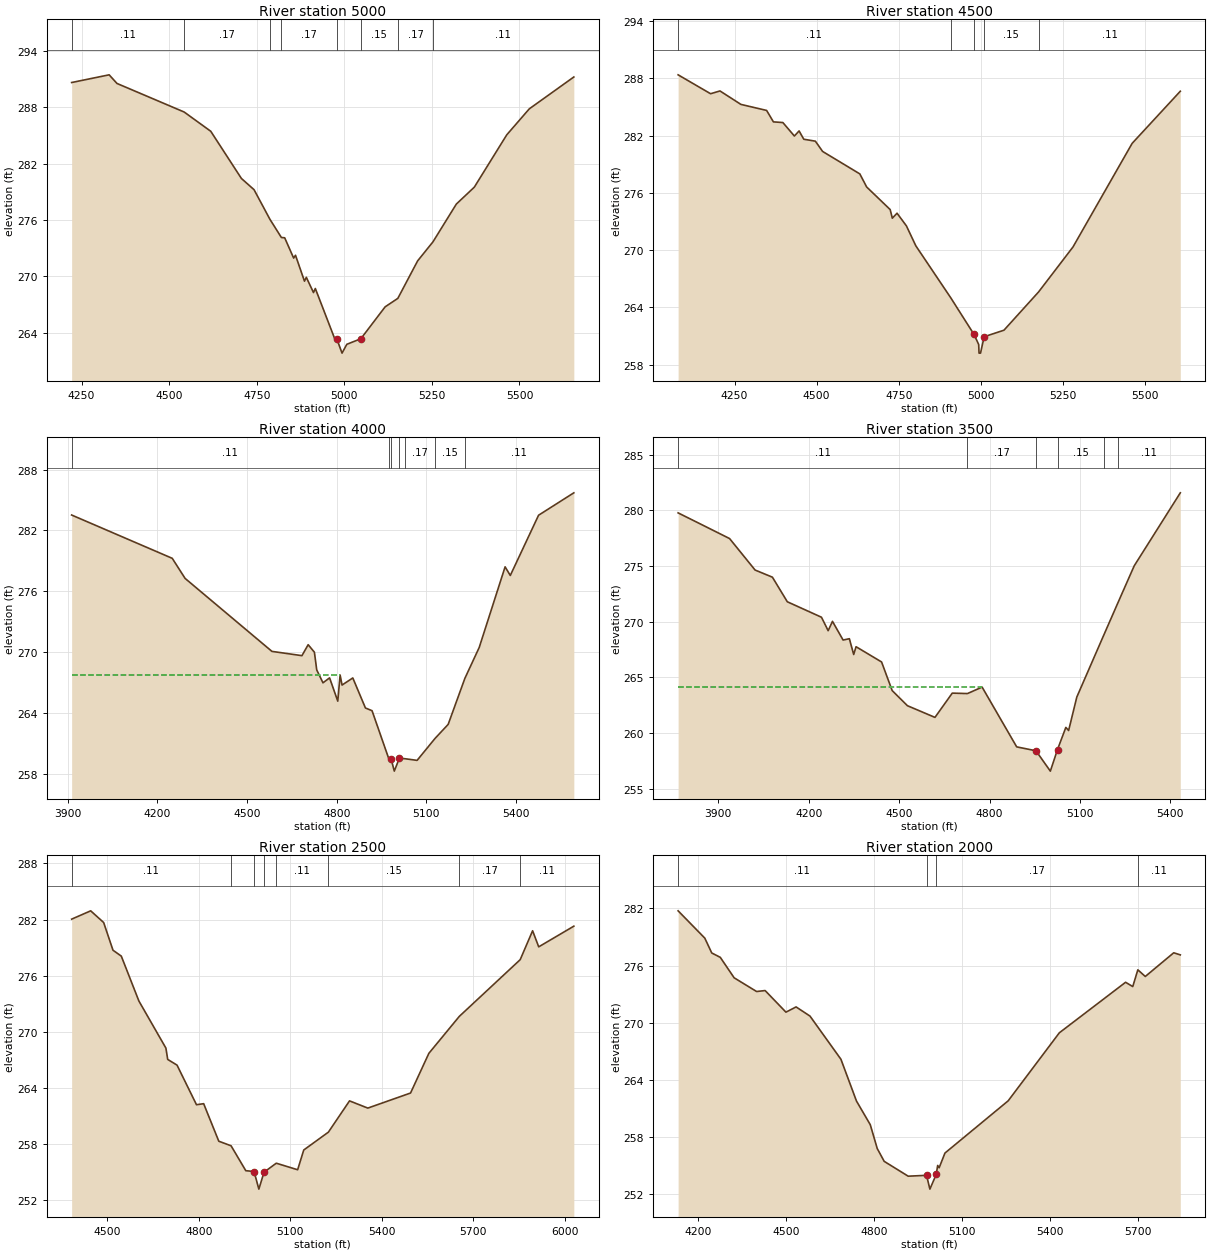
Type RM Length L Ch R = 1 ,5000    ,500,500,500
BEGIN DESCRIPTION:
CRYSTAL CREEK TRIBUTARY NO 8 9.0
END DESCRIPTION:
XS GIS Cut Line= 3
      3835528.72     10142577.89      3834794.93     10142318.46
      3834146.84     10142414.69
#Sta/Elev= 30
  4221.7  290.64  4328.7  291.46  4351.2  290.54  4542.9   287.5  4618.8  285.45
  4706.2  280.43  4742.4  279.23  4787.5  276.09  4820.4  274.14  4829.8  274.11
  4855.4  271.95  4860.7  272.25  4886.3  269.49  4891.6   269.9    4912  268.28
  4917.3  268.71  4973.8  263.25  4979.1   263.3  4993.5  261.83  5007.2  262.77
  5047.2  263.36  5116.6  266.76  5152.8  267.66  5209.3  271.65  5253.1  273.68
  5319.8   277.7  5371.1   279.5  5463.7  285.07  5528.1  287.84  5655.2  291.23
#Mann= 8 ,-1 , 0
  4221.7     .11       0  4542.9     .17       0  4787.5     .11       0
  4820.4     .17       0  4979.1     .06       0  5047.2     .15       0
  5152.8     .17       0  5253.1     .11       0
Bank Sta=4979.1,5047.2
XS Rating Curve= 0 ,0
Exp/Cntr=0.3,0.1

Type RM Length L Ch R = 1 ,4500    ,500,500,500
BEGIN DESCRIPTION:
CRYSTAL CREEK TRIBUTARY NO 8 8.0
END DESCRIPTION:
XS GIS Cut Line= 3
      3835549.58      10142428.6      3834838.16     10141841.97
      3834231.44     10141879.89
#Sta/Elev= 30
  4077.9  288.36  4176.8  286.38  4205.5  286.67  4269.3  285.26  4347.5  284.63
  4368.3  283.43    4397  283.36  4432.1  281.95  4446.5  282.48  4460.8  281.61
    4496  281.41  4518.2  280.33  4631.5  277.98  4652.3  276.61    4724  274.24
  4730.5  273.34  4744.9  273.86  4773.5  272.53  4802.2  270.44  4908.3  265.01
  4979.4  261.16  4993.7   260.1  4994.7   259.2  4999.2   259.2  5010.3  260.92
  5070.6   261.6  5176.1  265.61  5280.9  270.32  5461.2  281.18  5607.9  286.64
#Mann= 5 ,-1 , 0
  4077.9     .11       0  4908.3     .15       0  4979.4     .06       0
  5010.3     .15       0  5176.1     .11       0
Bank Sta=4979.4,5010.3
XS Rating Curve= 0 ,0
Exp/Cntr=0.3,0.1

Type RM Length L Ch R = 1 ,4000    ,500,500,500
BEGIN DESCRIPTION:
CRYSTAL CREEK TRIBUTARY NO 8 7.0
END DESCRIPTION:
XS GIS Cut Line= 3
       3835695.4     10142237.61      3835004.86     10141398.26
      3834421.99      10141286.4
#Sta/Elev= 30
  3913.1  283.51  4249.7  279.24  4292.7  277.26  4583.3  270.06  4683.7  269.64
  4704.5  270.72  4725.4  269.98  4733.2  268.23  4754.1  266.96  4776.2  267.45
  4803.6  265.15  4811.4  267.73  4817.9  266.74  4853.9  267.44  4896.1  264.48
  4918.3  264.21  4974.6  259.45  4982.2  259.45  4992.7  258.25  5009.7259.5288
  5029.4  259.47    5069  259.31  5129.2  261.48    5173  262.86  5228.9   267.4
  5276.9  270.45  5363.5   278.4  5380.9  277.55  5475.5  283.49  5593.5   285.7
#Mann= 7 ,-1 , 0
  3913.1     .11       0  4974.6     .15       0  4982.2     .06       0
  5009.7     .15       0  5029.4     .17       0  5129.2     .15       0
  5228.9     .11       0
#XS Ineff= 2 , 0
         4811.29  267.75
Permanent Ineff=
       F       F
Bank Sta=4982.2,5009.7
XS Rating Curve= 0 ,0
Exp/Cntr=0.3,0.1

Type RM Length L Ch R = 1 ,3500    ,1000,1000,1000
BEGIN DESCRIPTION:
CRYSTAL CREEK TRIBUTARY NO 8 6.0
END DESCRIPTION:
XS GIS Cut Line= 3
      3836094.73     10141744.58      3835143.45     10140959.98
       3834772.4     10140736.99
#Sta/Elev= 30
  3766.9  279.78  3937.6  277.47  4022.3  274.64  4079.7     274  4129.2  271.79
  4242.5   270.4  4264.7  269.19    4279  270.03  4314.2  268.35    4335  268.47
  4349.4  267.05  4357.2  267.75  4441.9  266.38    4477  263.81  4527.6  262.45
    4619   261.4  4676.4  263.58  4726.7  263.54  4775.4  264.12  4890.1  258.75
    4954   258.4  5001.8  256.57  5025.5  258.51  5053.2   260.5  5062.4  260.22
  5089.6  263.23  5178.8  268.78  5226.8  271.75    5280  275.02  5432.9  281.58
#Mann= 6 ,-1 , 0
  3766.9     .11       0  4726.7     .17       0    4954     .06       0
  5025.5     .15       0  5178.8     .17       0  5226.8     .11       0
#XS Ineff= 2 , 0
         4775.67  264.15
Permanent Ineff=
       F       F
Bank Sta=4954,5025.5
XS Rating Curve= 0 ,0
Exp/Cntr=0.3,0.1

Type RM Length L Ch R = 1 ,2500    ,500,500,500
BEGIN DESCRIPTION:
CRYSTAL CREEK TRIBUTARY NO 8 5.0
END DESCRIPTION:
XS GIS Cut Line= 3
       3836344.7     10140959.83        3835822.     10140633.13
      3834792.75     10140623.03
#Sta/Elev= 30
  4383.6  282.05    4446  282.94  4488.5  281.69  4519.1  278.73  4546.3   278.1
    4604   273.3  4692.5  268.27  4698.4  267.06    4729  266.45  4792.7  262.22
  4816.2  262.33  4865.8  258.32  4906.1  257.83  4954.3  255.17  4981.4  255.08
  4997.1   253.2  5014.1  255.01  5054.2  255.97  5124.2  255.27  5144.2  257.38
    5225  259.29  5294.2  262.63  5354.2  261.86  5494.2  263.47  5554.2  267.71
    5654  271.66  5853.5  277.72  5894.2  280.81  5914.2  279.09  6029.3   281.3
#Mann= 8 ,-1 , 0
  4383.6     .11       0  4906.1     .17       0  4981.4     .06       0
  5014.1     .17       0  5054.2     .11       0    5225     .15       0
    5654     .17       0  5853.5     .11       0
Bank Sta=4981.4,5014.1
XS Rating Curve= 0 ,0
Exp/Cntr=0.3,0.1

Type RM Length L Ch R = 1 ,2000    ,500,500,500
BEGIN DESCRIPTION:
CRYSTAL CREEK TRIBUTARY NO 8 4.0
END DESCRIPTION:
XS GIS Cut Line= 3
      3836417.85     10140561.07       3835618.1     10140222.17
      3834796.05     10140412.97
#Sta/Elev= 30
  4131.4  281.75  4222.4  278.88  4246.1  277.32  4275.2  276.86  4322.5  274.71
    4399  273.27  4428.1  273.37  4499.1   271.1  4533.7  271.65    4581  270.69
  4686.6  266.15  4739.6  261.76  4786.7  259.27  4810.4  256.77  4834.1  255.42
    4916  253.86  4978.5  253.95    4990   252.5  5011.7 254.054  5016.5  254.99
  5021.6  254.75  5041.3  256.29  5256.9  261.78  5431.4  268.93  5657.3  274.24
  5681.8  273.79  5699.1  275.55  5724.5  274.85  5821.5  277.34  5843.9  277.12
#Mann= 4 ,-1 , 0
  4131.4     .11       0  4978.5     .06       0  5011.7     .17       0
  5699.1     .11       0
Bank Sta=4978.5,5011.7
XS Rating Curve= 0 ,0
Exp/Cntr=0.3,0.1

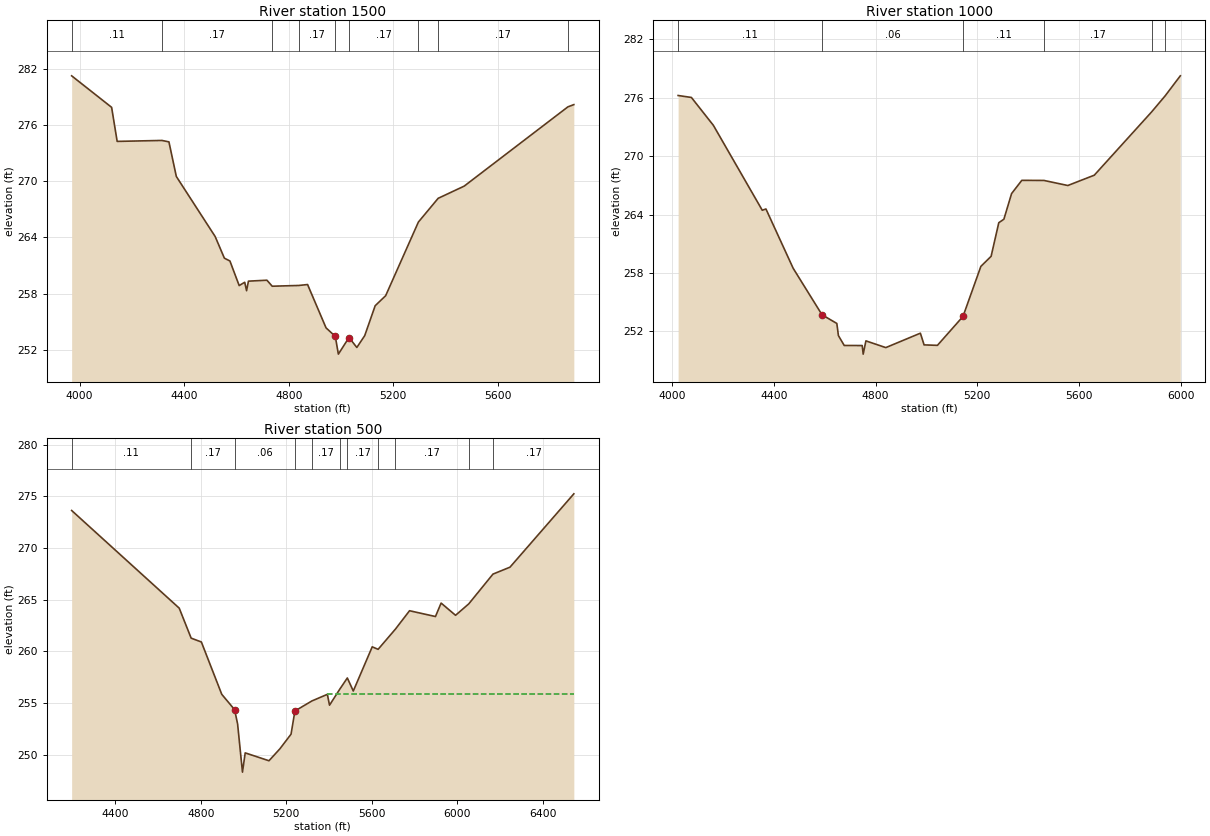
Type RM Length L Ch R = 1 ,1500    ,500,500,500
BEGIN DESCRIPTION:
CRYSTAL CREEK TRIBUTARY NO 8 3.0
END DESCRIPTION:
XS GIS Cut Line= 3
      3836438.43     10140506.69      3835708.22     10139779.57
      3834818.89     10139735.97
#Sta/Elev= 30
  3969.5  281.22  4122.4  277.86  4143.6  274.23  4314.8  274.33  4341.6  274.18
  4369.9  270.49  4518.4  264.09  4553.7  261.78  4574.9  261.48  4610.3  258.86
  4631.5  259.21  4638.6  258.31  4645.7  259.33  4716.4  259.43  4736.7  258.79
  4838.5  258.87  4871.9  258.97  4942.6  254.35    4978  253.44  4989.7  251.55
  5030.4  253.32  5060.4  252.26  5090.5  253.52  5130.5  256.71  5170.6  257.78
  5295.8  265.63  5371.4  268.16  5470.9  269.46  5867.6  277.91  5890.4  278.15
#Mann= 9 ,-1 , 0
  3969.5     .11       0  4314.8     .17       0  4736.7     .11       0
  4838.5     .17       0    4978     .09       0  5030.4     .17       0
  5295.8     .15       0  5371.4     .17       0  5867.6     .15       0
Bank Sta=4978,5030.4
XS Rating Curve= 0 ,0
Exp/Cntr=0.3,0.1

Type RM Length L Ch R = 1 ,1000    ,500,500,500
BEGIN DESCRIPTION:
CRYSTAL CREEK TRIBUTARY NO 8 2.0
END DESCRIPTION:
XS GIS Cut Line= 3
      3836601.63      10140291.4      3836010.94     10139513.94
      3835017.85     10139411.07
#Sta/Elev= 30
  4023.6  276.22  4075.8  276.02  4162.2  273.16  4354.5  264.44    4369  264.57
  4476.1  258.48  4589.5  253.71  4647.7  252.82    4654  251.57  4676.8  250.56
  4747.5  250.55  4751.4  249.67  4762.1  251.03  4840.3  250.34  4976.3  251.82
  4990.8  250.62  5043.3  250.57  5143.9  253.54  5214.2  258.68  5254.4  259.71
  5284.6  263.16  5304.7  263.52  5334.9  266.15  5375.1  267.51  5462.3   267.5
    5556  266.98  5660.2  268.04  5885.4  274.53    5939  276.19  5998.4  278.24
#Mann= 6 ,-1 , 0
  4023.6     .11       0  4589.5     .06       0  5143.9     .11       0
  5462.3     .17       0  5885.4     .11       0    5939     .17       0
Bank Sta=4589.5,5143.9
XS Rating Curve= 0 ,0
Exp/Cntr=0.3,0.1

Type RM Length L Ch R = 1 ,500     ,0,0,0
BEGIN DESCRIPTION:
CRYSTAL CREEK TRIBUTARY NO 8 1.0
END DESCRIPTION:
XS GIS Cut Line= 3
      3836667.61     10140176.83      3836455.03      10139400.2
      3834927.99     10139159.48
#Sta/Elev= 30
  4194.8  273.63  4698.4  264.19  4754.3  261.29  4802.1  260.92  4897.6  255.86
  4957.6  254.38  4971.8  252.99  4994.5  248.34  5007.3   250.2  5118.6  249.44
  5169.2  250.58    5222  252.01  5240.1  254.25  5319.7  255.22    5392  255.86
  5402.1  254.81  5450.2  256.36  5485.5  257.44  5513.4  256.18    5602  260.45
  5629.6  260.21  5710.5  262.16  5776.7  263.94  5898.1  263.38  5924.5  264.68
  5992.1   263.5  6053.8   264.6  6167.2  267.48    6247  268.15  6545.9  275.24
#Mann= 11 ,-1 , 0
  4194.8     .11       0  4754.3     .17       0  4957.6     .06       0
  5240.1     .15       0  5319.7     .17       0  5450.2     .15       0
  5485.5     .17       0  5629.6     .11       0  5710.5     .17       0
  6053.8     .11       0  6167.2     .17       0
#XS Ineff= 2 , 0
                            5392          255.87
Permanent Ineff=
       F       F
Bank Sta=4957.6,5240.1
XS Rating Curve= 0 ,0
Exp/Cntr=0.3,0.1

Chan Stop Cuts=-1
Use User Specified Reach Order=0
Composite Channel Slope=5

--- CRYSTAL CREEK TRIBUTARY NO 8.g10 (geometry) ---

Geom Title=Existing Conditions
Program Version=4.10

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
River Reach=CRYSTAL CREEK TR,Reach-1