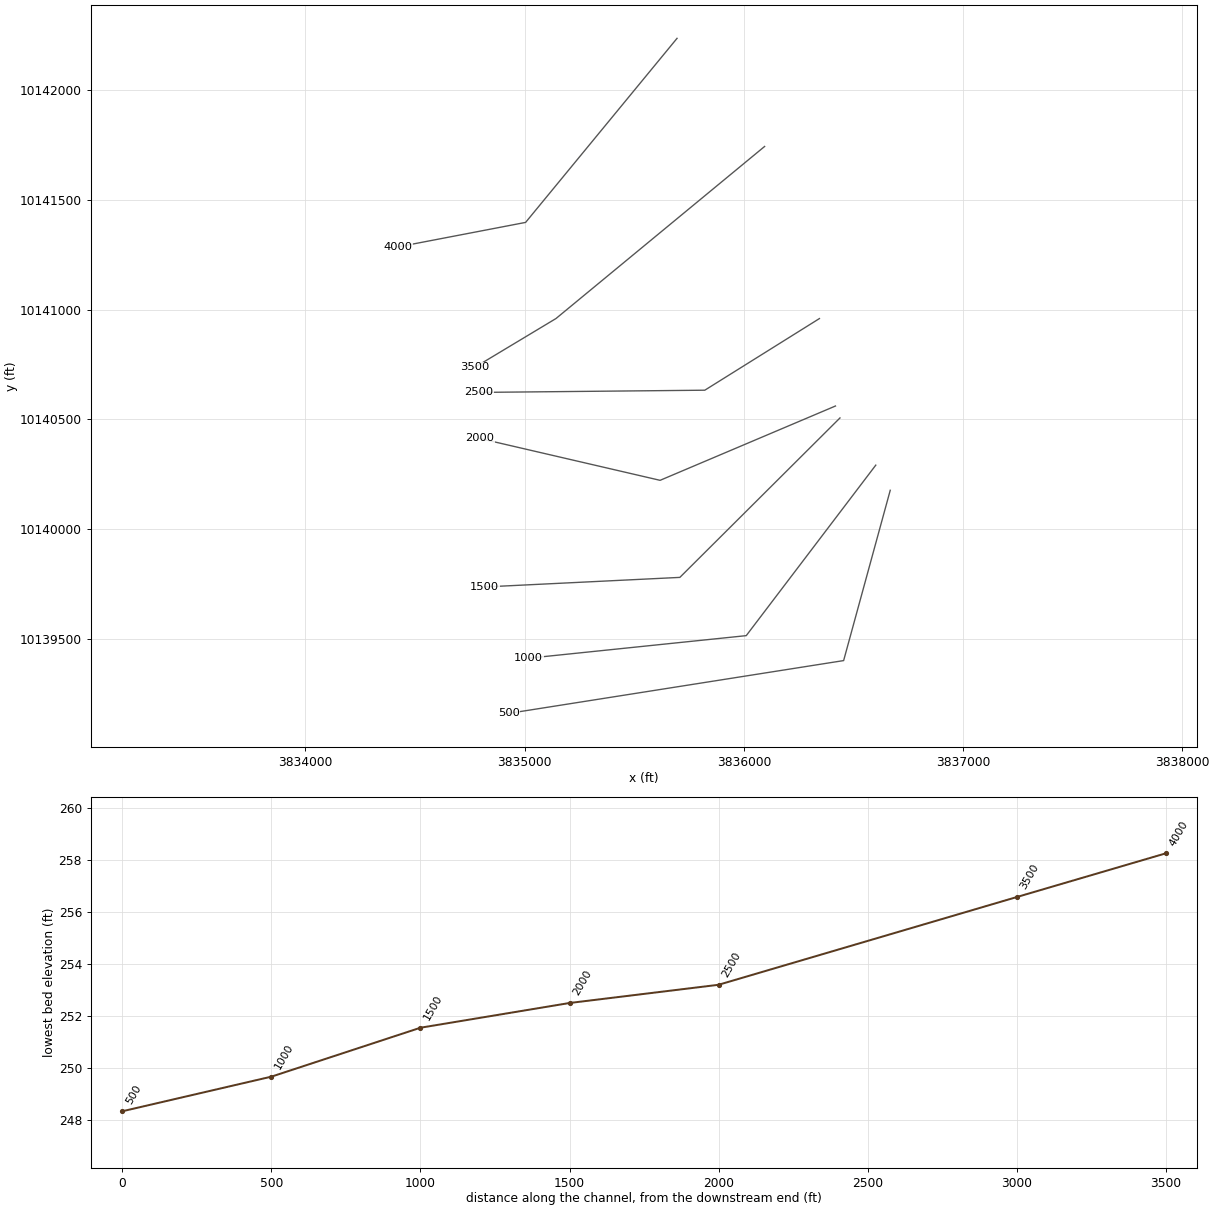
HEC-RAS study CRYSTAL CREEK TRIBUTARY NO 8.prj: CRYSTAL CREEK TRIBUTARY NO 8 Base Level Engineering

--- CRYSTAL CREEK TRIBUTARY NO 8.g10 (geometry) --- (continued)

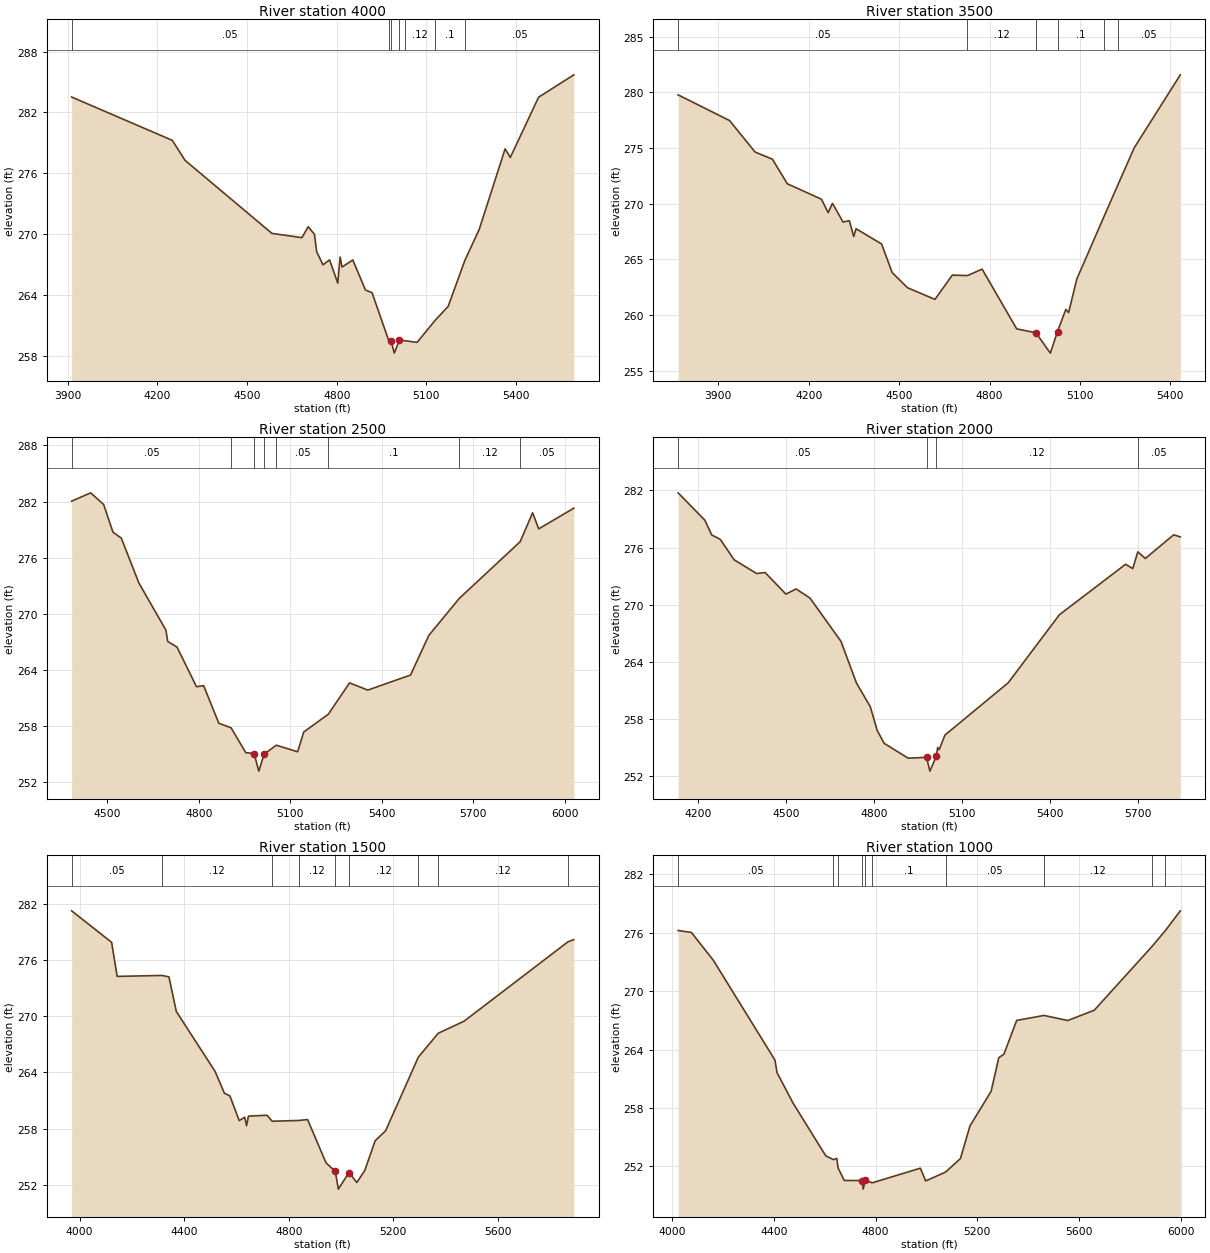
Type RM Length L Ch R = 1 ,4000    ,500,500,500
BEGIN DESCRIPTION:
CRYSTAL CREEK TRIBUTARY NO 8 7.0
END DESCRIPTION:
XS GIS Cut Line= 3
       3835695.4     10142237.61      3835004.86     10141398.26
      3834421.99      10141286.4
#Sta/Elev= 30
  3913.1  283.51  4249.7  279.24  4292.7  277.26  4583.3  270.06  4683.7  269.64
  4704.5  270.72  4725.4  269.98  4733.2  268.23  4754.1  266.96  4776.2  267.45
  4803.6  265.15  4811.4  267.73  4817.9  266.74  4853.9  267.44  4896.1  264.48
  4918.3  264.21  4974.6  259.45  4982.2  259.45  4992.7  258.25  5009.7 259.529
  5029.4  259.47    5069  259.31  5129.2  261.48    5173  262.86  5228.9   267.4
  5276.9  270.45  5363.5   278.4  5380.9  277.55  5475.5  283.49  5593.5   285.7
#Mann= 7 ,-1 , 0
  3913.1     .05       0  4974.6      .1       0  4982.2     .03       0
  5009.7      .1       0  5029.4     .12       0  5129.2      .1       0
  5228.9     .05       0
Bank Sta=4982.2,5009.7
XS Rating Curve= 0 ,0
Exp/Cntr=0.3,0.1

Type RM Length L Ch R = 1 ,3500    ,1000,1000,1000
BEGIN DESCRIPTION:
CRYSTAL CREEK TRIBUTARY NO 8 6.0
END DESCRIPTION:
XS GIS Cut Line= 3
      3836094.73     10141744.58      3835143.45     10140959.98
       3834772.4     10140736.99
#Sta/Elev= 30
  3766.9  279.78  3937.6  277.47  4022.3  274.64  4079.7     274  4129.2  271.79
  4242.5   270.4  4264.7  269.19    4279  270.03  4314.2  268.35    4335  268.47
  4349.4  267.05  4357.2  267.75  4441.9  266.38    4477  263.81  4527.6  262.45
    4619   261.4  4676.4  263.58  4726.7  263.54  4775.4  264.12  4890.1  258.75
    4954   258.4  5001.8  256.57  5025.5  258.51  5053.2   260.5  5062.4  260.22
  5089.6  263.23  5178.8  268.78  5226.8  271.75    5280  275.02  5432.9  281.58
#Mann= 6 ,-1 , 0
  3766.9     .05       0  4726.7     .12       0    4954     .03       0
  5025.5      .1       0  5178.8     .12       0  5226.8     .05       0
Bank Sta=4954,5025.5
XS Rating Curve= 0 ,0
Exp/Cntr=0.3,0.1

Type RM Length L Ch R = 1 ,2500    ,500,500,500
BEGIN DESCRIPTION:
CRYSTAL CREEK TRIBUTARY NO 8 5.0
END DESCRIPTION:
XS GIS Cut Line= 3
       3836344.7     10140959.83        3835822.     10140633.13
      3834792.75     10140623.03
#Sta/Elev= 30
  4383.6  282.05    4446  282.94  4488.5  281.69  4519.1  278.73  4546.3   278.1
    4604   273.3  4692.5  268.27  4698.4  267.06    4729  266.45  4792.7  262.22
  4816.2  262.33  4865.8  258.32  4906.1  257.83  4954.3  255.17  4981.4  255.08
  4997.1   253.2  5014.1  255.01  5054.2  255.97  5124.2  255.27  5144.2  257.38
    5225  259.29  5294.2  262.63  5354.2  261.86  5494.2  263.47  5554.2  267.71
    5654  271.66  5853.5  277.72  5894.2  280.81  5914.2  279.09  6029.3   281.3
#Mann= 8 ,-1 , 0
  4383.6     .05       0  4906.1     .12       0  4981.4     .03       0
  5014.1     .12       0  5054.2     .05       0    5225      .1       0
    5654     .12       0  5853.5     .05       0
Bank Sta=4981.4,5014.1
XS Rating Curve= 0 ,0
Exp/Cntr=0.3,0.1

Type RM Length L Ch R = 1 ,2000    ,500,500,500
BEGIN DESCRIPTION:
CRYSTAL CREEK TRIBUTARY NO 8 4.0
END DESCRIPTION:
XS GIS Cut Line= 3
      3836417.85     10140561.07       3835618.1     10140222.17
      3834796.05     10140412.97
#Sta/Elev= 30
  4131.4  281.75  4222.4  278.88  4246.1  277.32  4275.2  276.86  4322.5  274.71
    4399  273.27  4428.1  273.37  4499.1   271.1  4533.7  271.65    4581  270.69
  4686.6  266.15  4739.6  261.76  4786.7  259.27  4810.4  256.77  4834.1  255.42
    4916  253.86  4978.5  253.95    4990   252.5  5011.7 254.054  5016.5  254.99
  5021.6  254.75  5041.3  256.29  5256.9  261.78  5431.4  268.93  5657.3  274.24
  5681.8  273.79  5699.1  275.55  5724.5  274.85  5821.5  277.34  5843.9  277.12
#Mann= 4 ,-1 , 0
  4131.4     .05       0  4978.5     .03       0  5011.7     .12       0
  5699.1     .05       0
Bank Sta=4978.5,5011.7
XS Rating Curve= 0 ,0
Exp/Cntr=0.3,0.1

Type RM Length L Ch R = 1 ,1500    ,500,500,500
BEGIN DESCRIPTION:
CRYSTAL CREEK TRIBUTARY NO 8 3.0
END DESCRIPTION:
XS GIS Cut Line= 3
      3836438.43     10140506.69      3835708.22     10139779.57
      3834818.89     10139735.97
#Sta/Elev= 30
  3969.5  281.22  4122.4  277.86  4143.6  274.23  4314.8  274.33  4341.6  274.18
  4369.9  270.49  4518.4  264.09  4553.7  261.78  4574.9  261.48  4610.3  258.86
  4631.5  259.21  4638.6  258.31  4645.7  259.33  4716.4  259.43  4736.7  258.79
  4838.5  258.87  4871.9  258.97  4942.6  254.35    4978  253.44  4989.7  251.55
  5030.4  253.32  5060.4  252.26  5090.5  253.52  5130.5  256.71  5170.6  257.78
  5295.8  265.63  5371.4  268.16  5470.9  269.46  5867.6  277.91  5890.4  278.15
#Mann= 9 ,-1 , 0
  3969.5     .05       0  4314.8     .12       0  4736.7     .05       0
  4838.5     .12       0    4978     .07       0  5030.4     .12       0
  5295.8      .1       0  5371.4     .12       0  5867.6      .1       0
Bank Sta=4978,5030.4
XS Rating Curve= 0 ,0
Exp/Cntr=0.3,0.1

Type RM Length L Ch R = 1 ,1000    ,500,500,500
BEGIN DESCRIPTION:
CRYSTAL CREEK TRIBUTARY NO 8 2.0
END DESCRIPTION:
XS GIS Cut Line= 3
      3836601.63      10140291.4      3836010.94     10139513.94
      3835017.85     10139411.07
#Sta/Elev= 30
  4023.6  276.22  4075.8  276.02  4162.2  273.16  4404.4  262.92  4412.7  261.62
  4476.1  258.48  4604.1  253.09  4634.5   252.7  4647.7  252.82  4652.6  251.85
  4676.8  250.56  4747.5  250.55  4751.4  249.67 4759.16 250.562  4787.4  250.32
  4976.3  251.82  4997.1  250.51  5075.4  251.42  5133.8  252.81  5171.2  256.15
  5254.4  259.71  5284.6  263.16  5304.7  263.52    5355  266.99  5462.3   267.5
    5556  266.98  5660.2  268.04  5885.4  274.53    5939  276.19  5998.4  278.24
#Mann= 10 ,-1 , 0
  4023.6     .05       0  4634.5     .12       0  4652.6     .05       0
  4747.5     .03       0 4759.16     .05       0  4787.4      .1       0
  5075.4     .05       0  5462.3     .12       0  5885.4     .05       0
    5939     .12       0
Bank Sta=4747.5,4759.16
XS Rating Curve= 0 ,0
Exp/Cntr=0.3,0.1

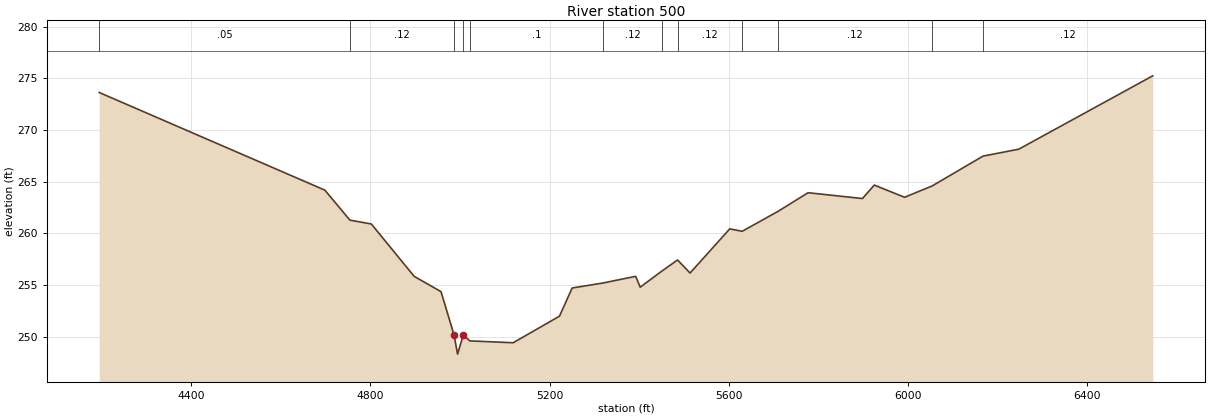
Type RM Length L Ch R = 1 ,500     ,0,0,0
BEGIN DESCRIPTION:
CRYSTAL CREEK TRIBUTARY NO 8 1.0
END DESCRIPTION:
XS GIS Cut Line= 3
      3836667.61     10140176.83      3836455.03      10139400.2
      3834927.99     10139159.48
#Sta/Elev= 30
  4194.8  273.63  4698.4  264.19  4754.3  261.29  4802.1  260.92  4897.6  255.86
  4957.6  254.38 4986.83 250.165  4994.5  248.34  5007.3   250.2  5021.9  249.62
  5118.6  249.44    5222  252.01  5250.2  254.73  5319.7  255.22    5392  255.86
  5402.1  254.81  5450.2  256.36  5485.5  257.44  5513.4  256.18    5602  260.45
  5629.6  260.21  5710.5  262.16  5776.7  263.94  5898.1  263.38  5924.5  264.68
  5992.1   263.5  6053.8   264.6  6167.2  267.48    6247  268.15  6545.9  275.24
#Mann= 12 ,-1 , 0
  4194.8     .05       0  4754.3     .12       0 4986.83     .03       0
  5007.3     .12       0  5021.9      .1       0  5319.7     .12       0
  5450.2      .1       0  5485.5     .12       0  5629.6     .05       0
  5710.5     .12       0  6053.8     .05       0  6167.2     .12       0
Bank Sta=4986.83,5007.3
XS Rating Curve= 0 ,0
Exp/Cntr=0.3,0.1