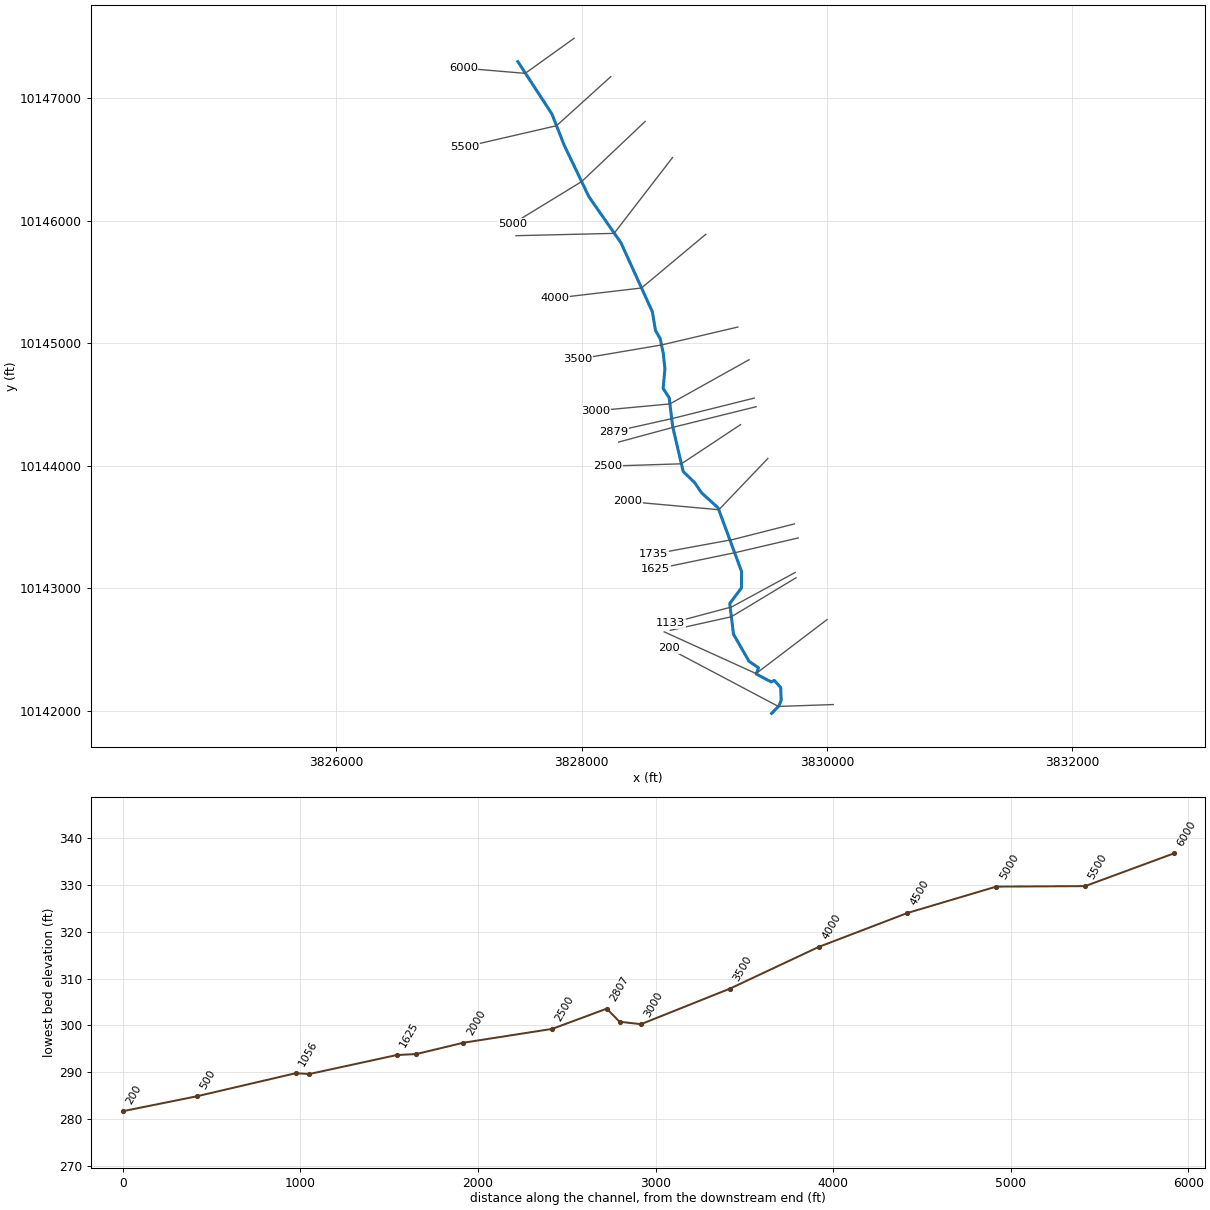
--- CRYSTAL CREEK TRIBUTARY NO 9.prj (project) ---

Proj Title=CRYSTAL CREEK TRIBUTARY NO 9 Base Level Engineering
Current Plan=p01
Default Exp/Contr=0.3,0.1
English Units
Geom File=g01
Flow File=f01
Plan File=p01
Y Axis Title=Elevation
X Axis Title(PF)=Main Channel Distance
X Axis Title(XS)=Station
BEGIN DESCRIPTION:
CRYSTAL CREEK TRIBUTARY NO 9
END DESCRIPTION:
DSS Export Rating Curves= 0
DSS Export Rating Curve Sorted= 0
DSS Export Volume Flow Curves= 0
DXF OffsetX= 0
DXF OffsetY= 0
DXF ScaleX= 1
DXF ScaleY= 10

--- CRYSTAL CREEK TRIBUTARY NO 9.p01 (plan) ---

Plan Title=Multiple Run
Short Identifier=Multiple
Geom File=g01
Flow File=f01
Subcritical Flow
K Sum by GR= 0
Std Step Tol= 0.01
Critical Tol= 0.01
Num of Std Step Trials= 20
Max Error Tol= 0.3
Flow Tol Ratio= 0.001
Split Flow NTrial= 30
Split Flow Tol= 0.02
Split Flow Ratio= 0.02
Log Output Level= 0
Friction Slope Method= 1
Unsteady Friction Slope Method= 2
Unsteady Bridges Friction Slope Method= 1
Parabolic Critical Depth
Global Vel Dist=  1 , 1 , 1
Global Log Level= 0
CheckData=True
Encroach Param= -1, 0, 0, 0
BEGIN DESCRIPTION:
Multiple Run
END DESCRIPTION:

--- CRYSTAL CREEK TRIBUTARY NO 9.f01 (steady flow) ---

Flow Title=Multiple
Program Version=4.10
Number of Profiles= 7
Profile Names=10-year,25-year,50-year,1pct_min,100-year,1pct_plu,500-year
River Rch & RM=CRYSTAL CREEK TR,Reach-1         ,6000
     497     661     884     389    1175    3548    2147
Boundary for River Rch & Prof#=CRYSTAL CREEK TR,Reach-1         , 1
Up Type= 0
Dn Type= 3
Dn Slope=0.008
Boundary for River Rch & Prof#=CRYSTAL CREEK TR,Reach-1         , 2
Up Type= 0
Dn Type= 3
Dn Slope=0.008
Boundary for River Rch & Prof#=CRYSTAL CREEK TR,Reach-1         , 3
Up Type= 0
Dn Type= 3
Dn Slope=0.008
Boundary for River Rch & Prof#=CRYSTAL CREEK TR,Reach-1         , 4
Up Type= 0
Dn Type= 3
Dn Slope=0.008
Boundary for River Rch & Prof#=CRYSTAL CREEK TR,Reach-1         , 5
Up Type= 0
Dn Type= 3
Dn Slope=0.008
Boundary for River Rch & Prof#=CRYSTAL CREEK TR,Reach-1         , 6
Up Type= 0
Dn Type= 3
Dn Slope=0.008
Boundary for River Rch & Prof#=CRYSTAL CREEK TR,Reach-1         , 7
Up Type= 0
Dn Type= 3
Dn Slope=0.008
DSS Import GetInterval= 0
DSS Import GetPeak= 0
DSS Import FillOption= 0

--- CRYSTAL CREEK TRIBUTARY NO 9.g01 (geometry) ---

Geom Title=Existing Conditions
Program Version=4.10

River Reach=CRYSTAL CREEK TR,Reach-1
Reach XY= 30
      3827479.91     10147298.48      3827756.91     10146872.37
      3827857.04     10146618.02      3828058.04     10146197.77
      3828320.42      10145819.9      3828576.23     10145257.12
      3828601.08     10145105.83      3828639.82     10145038.59
      3828665.03     10144918.52      3828678.57     10144790.92
      3828663.99     10144632.07      3828712.94     10144556.55
      3828742.11     10144318.52      3828827.53     10143953.94
       3828921.8     10143862.27      3828977.01      10143780.5
      3829111.38     10143658.11      3829303.57     10143137.27
      3829302.01     10143003.42      3829206.69     10142876.86
      3829237.42     10142626.34      3829363.99      10142405.5
      3829441.59     10142352.38      3829422.84     10142301.86
      3829544.19     10142237.27      3829569.72     10142249.77
      3829622.32     10142191.44      3829625.97     10142087.27
      3829607.74     10142041.44      3829548.24     10141980.53

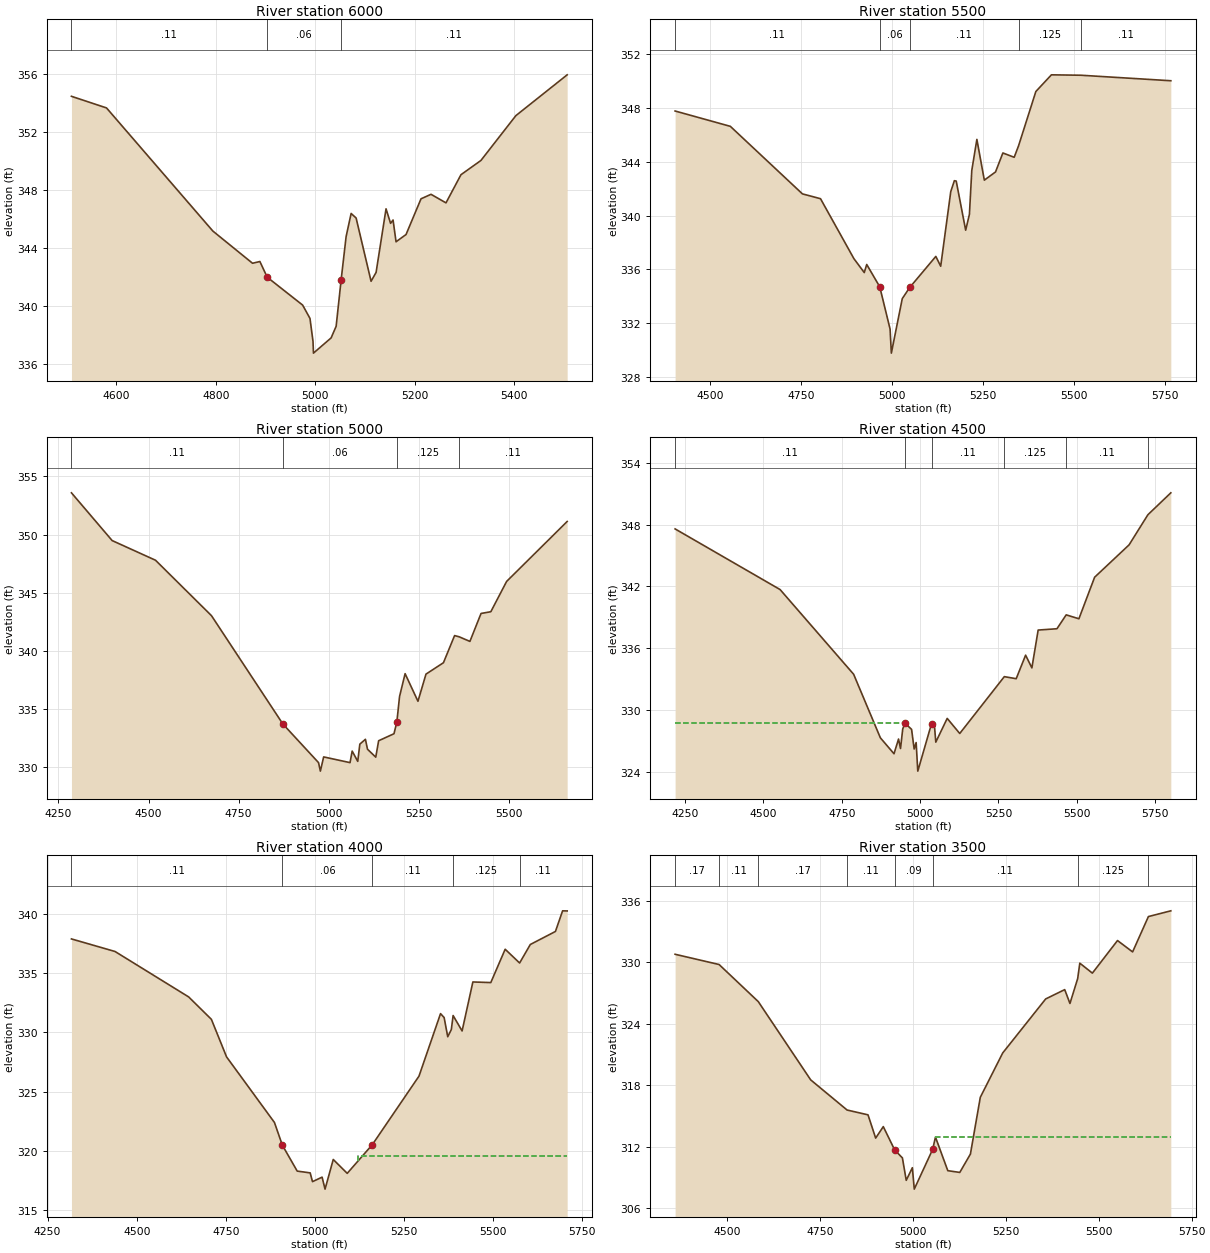
Type RM Length L Ch R = 1 ,6000    ,500,500,500
BEGIN DESCRIPTION:
CRYSTAL CREEK TRIBUTARY NO 9 12.0
END DESCRIPTION:
XS GIS Cut Line= 3
      3827937.91     10147488.75      3827539.38     10147202.98
      3827035.08     10147245.67
#Sta/Elev= 30
  4509.6  354.47  4580.1  353.67  4793.8  345.19  4873.6  342.97  4888.4  343.09
  4903.1  342.01  4974.3  340.09  4989.1  339.17  4995.2  337.58  4996.1  336.78
  5031.6  337.83  5041.7  338.63  5051.7  341.82  5061.7   344.8  5071.8   346.4
  5081.8  346.09  5111.9  341.73    5122  342.34    5142  346.72  5151.1  345.72
  5156.1  345.95  5162.1  344.45  5182.2  344.95  5212.3  347.41  5232.4  347.72
  5262.5  347.13  5292.6  349.07  5332.7  350.05    5403  353.14  5506.1  355.95
#Mann= 3 , 0 , 0
  4509.6     .11       0  4903.1     .06       0  5051.7     .11       0
Bank Sta=4903.1,5051.7
XS Rating Curve= 0 ,0
Exp/Cntr=0.3,0.1

Type RM Length L Ch R = 1 ,5500    ,500,500,500
BEGIN DESCRIPTION:
CRYSTAL CREEK TRIBUTARY NO 9 11.0
END DESCRIPTION:
XS GIS Cut Line= 3
      3828237.37     10147176.24      3827794.99     10146775.65
      3827048.12     10146603.31
#Sta/Elev= 30
  4403.2  347.78  4555.1  346.64  4753.3  341.62  4803.1  341.26    4895   336.8
  4923.4  335.77  4930.2  336.37    4966  334.71  4994.4  331.57  4997.9  329.78
  5027.9  333.83  5048.4  334.66  5120.2  336.97  5133.6  336.24  5161.3  341.79
  5171.2   342.6  5176.3  342.57  5202.3  338.92  5212.6   340.1  5219.1  343.36
  5233.1  345.67  5253.6  342.64  5284.4  343.25  5304.6  344.66  5335.7  344.34
  5347.7  345.19  5395.3  349.23  5438.1  350.47  5518.8  350.44  5766.5  350.03
#Mann= 5 ,-1 , 0
  4403.2     .11       0    4966     .06       0  5048.4     .11       0
  5347.7    .125       0  5518.8     .11       0
Bank Sta=4966,5048.4
XS Rating Curve= 0 ,0
Exp/Cntr=0.3,0.1

Type RM Length L Ch R = 1 ,5000    ,500,500,500
BEGIN DESCRIPTION:
CRYSTAL CREEK TRIBUTARY NO 9 10.0
END DESCRIPTION:
XS GIS Cut Line= 3
      3828517.82     10146811.04      3827999.68     10146319.78
      3827434.38     10145973.95
#Sta/Elev= 30
    4286  353.58    4399  349.48  4519.5  347.79  4674.9  343.03  4873.1  333.73
  4972.2  330.41  4977.3  329.68  4986.4   330.9  5059.7  330.41  5065.6   331.4
  5081.1  330.52  5086.9     332  5102.4  332.41  5108.2  331.56  5131.1  330.88
  5139.1  332.29  5181.7  332.89  5189.7   333.9  5197.2  336.09  5212.6  338.05
  5248.3  335.68  5270.6  338.01  5319.1  338.99    5350  341.32  5362.4  341.22
  5392.6  340.82  5423.5  343.22  5450.7  343.37  5494.5  345.97  5662.7  351.12
#Mann= 4 ,-1 , 0
    4286     .11       0  4873.1     .06       0  5189.7    .125       0
  5362.4     .11       0
Bank Sta=4873.1,5189.7
XS Rating Curve= 0 ,0
Exp/Cntr=0.3,0.1

Type RM Length L Ch R = 1 ,4500    ,500,500,500
BEGIN DESCRIPTION:
CRYSTAL CREEK TRIBUTARY NO 9 9.0
END DESCRIPTION:
XS GIS Cut Line= 3
      3828740.85     10146516.52      3828264.36     10145897.21
      3827464.78     10145878.48
#Sta/Elev= 30
  4218.6   347.6  4553.5   341.7  4788.1  333.46  4873.3  327.28  4916.8  325.73
  4931.3  327.16  4937.6  326.24  4944.7  328.15  4952.1   328.7  4972.9   328.1
  4981.1  326.19  4987.4  326.82  4992.7  324.04  5036.5  328.65  5045.1  328.73
  5050.1  326.86  5086.5  329.17  5126.5   327.7  5268.7  333.23  5306.6  333.03
  5336.6  335.32  5356.6  334.08  5376.6  337.76  5436.6  337.89    5466  339.24
  5506.6  338.86  5556.7   342.9  5666.7  346.05  5726.7  348.98  5799.8  351.11
#Mann= 6 ,-1 , 0
  4218.6     .11       0  4952.1     .06       0  5036.5     .11       0
  5268.7    .125       0    5466     .11       0  5726.7     .17       0
#XS Ineff= 2 , 0
         4951.96  328.71 5036.54          328.65
Permanent Ineff=
       F       F
Bank Sta=4952.1,5036.5
XS Rating Curve= 0 ,0
Exp/Cntr=0.3,0.1

Type RM Length L Ch R = 1 ,4000    ,500,500,500
BEGIN DESCRIPTION:
CRYSTAL CREEK TRIBUTARY NO 9 8.0
END DESCRIPTION:
XS GIS Cut Line= 3
      3829011.64     10145889.74      3828487.68      10145451.6
      3827785.13     10145368.94
#Sta/Elev= 30
    4317  337.87  4439.3  336.81  4645.7  332.98  4709.5  331.09  4752.1  327.92
  4886.4  322.39  4908.5  320.48  4950.2  318.29  4986.6  318.14  4993.1   317.4
    5020  317.78  5028.3  316.77  5051.3  319.27  5090.5   318.1  5160.9  320.52
  5291.8   326.3  5352.2  331.57  5362.3  331.24  5372.4  329.62  5382.5  330.23
  5387.5  331.41  5412.7  330.11  5442.9  334.24  5493.2  334.19  5533.5     337
    5574  335.84    5604   337.4  5674.5   338.5  5694.6  340.24  5707.4  340.23
#Mann= 5 ,-1 , 0
    4317     .11       0  4908.5     .06       0  5160.9     .11       0
  5387.5    .125       0    5574     .11       0
#XS Ineff= 2 , 0
                         5120.69          319.56
Permanent Ineff=
       F       F
Bank Sta=4908.5,5160.9
XS Rating Curve= 0 ,0
Exp/Cntr=0.3,0.1

Type RM Length L Ch R = 1 ,3500    ,500,500,500
BEGIN DESCRIPTION:
CRYSTAL CREEK TRIBUTARY NO 9 7.0
END DESCRIPTION:
XS GIS Cut Line= 3
      3829272.91     10145133.03      3828650.69     10144986.68
      3827966.49     10144870.45
#Sta/Elev= 30
  4360.8  330.77  4479.1  329.77  4584.5  326.15  4725.5  318.51  4823.3  315.57
  4879.6   315.1  4900.2  312.83  4920.7  313.95  4951.5  311.66  4972.1   310.9
  4982.4  308.71  4998.9  309.94    5004  307.85  5053.6  311.74    5061  312.93
  5094.2  309.65  5126.4  309.48    5155  311.27  5181.6  316.81  5241.9  321.14
  5357.4  326.41  5408.6  327.32  5422.7  325.97  5443.5   328.4  5449.2   329.9
    5483  328.93  5550.6  332.11  5591.2     331  5633.7  334.45    5694  335.01
#Mann= 8 ,-1 , 0
  4360.8     .17       0  4479.1     .11       0  4584.5     .17       0
  4823.3     .11       0  4951.5     .09       0  5053.6     .11       0
  5443.5    .125       0  5633.7     .11       0
#XS Ineff= 2 , 0
                         5061.07          312.93
Permanent Ineff=
       F       F
Bank Sta=4951.5,5053.6
XS Rating Curve= 0 ,0
Exp/Cntr=0.3,0.1

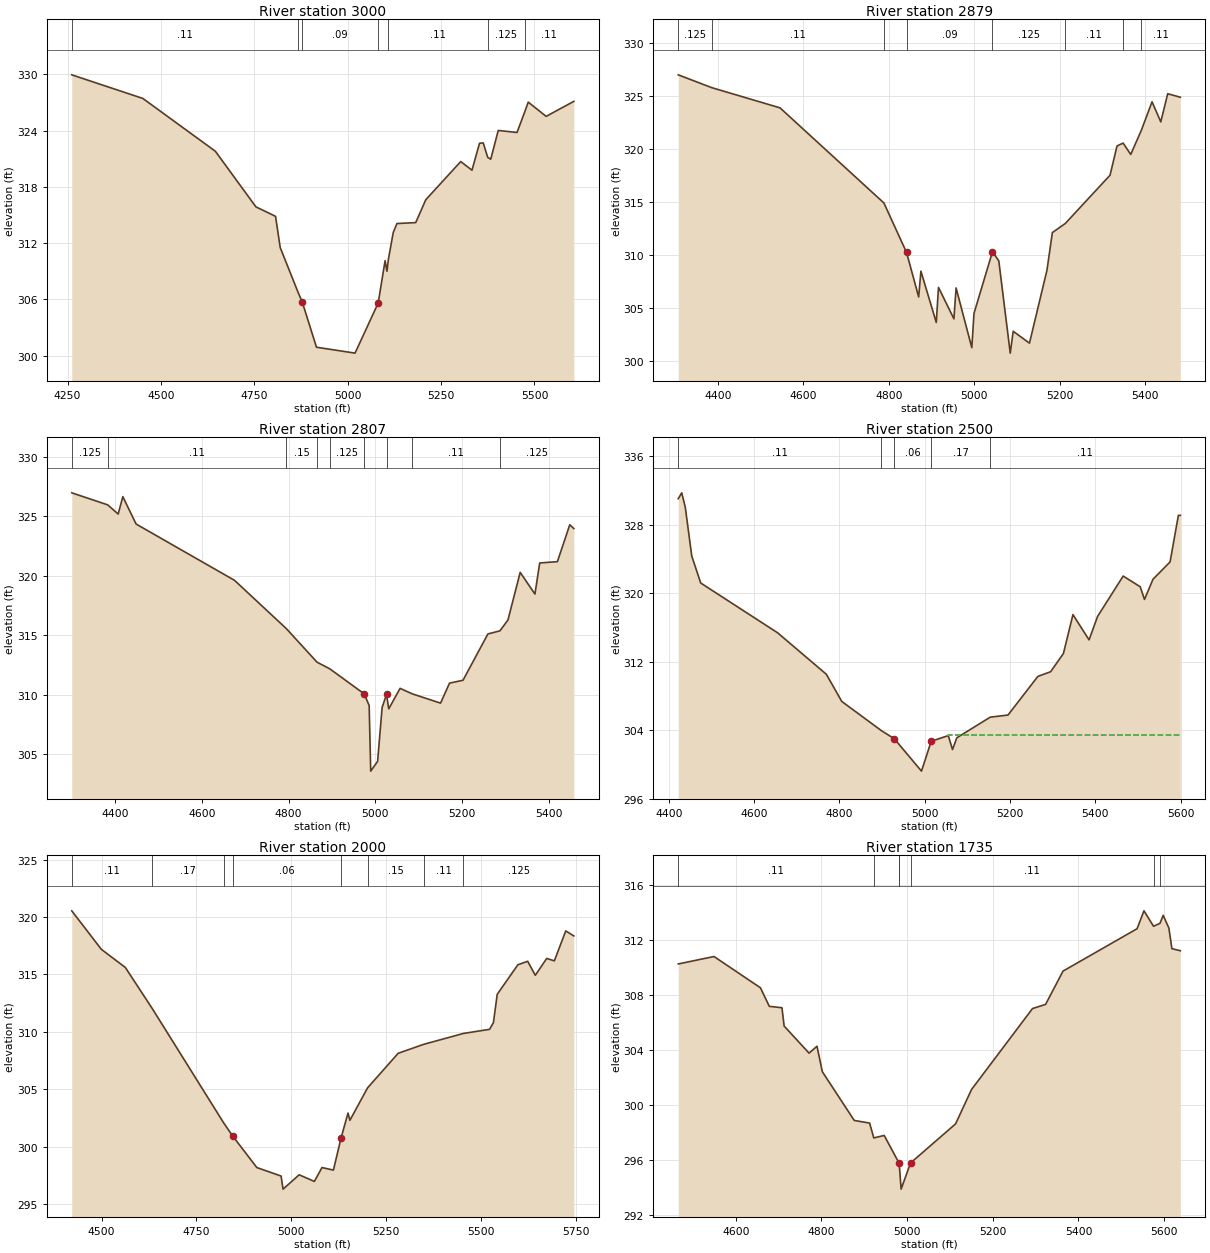
Type RM Length L Ch R = 1 ,3000    ,121,121,121
BEGIN DESCRIPTION:
CRYSTAL CREEK TRIBUTARY NO 9 6.0
END DESCRIPTION:
XS GIS Cut Line= 3
      3829364.09     10144866.11      3828719.18     10144505.67
      3828116.29     10144449.45
#Sta/Elev= 30
  4261.2  329.94  4451.6  327.42  4645.7  321.79  4754.2  315.86  4806.8  314.85
  4819.3  311.52  4866.8  306.78  4878.7  305.66  4916.4  300.89  5019.7  300.26
  5081.7  305.61  5100.1  310.12  5105.1  308.99  5108.8  310.22  5121.9  313.12
  5131.9  314.08  5182.1  314.18  5209.1  316.62  5302.6  320.69  5332.8  319.77
  5352.9  322.64  5362.9  322.68  5374.9  321.14    5383  320.94  5403.1  324.01
  5453.3  323.79  5473.6  325.94  5483.4  327.03  5531.4  325.51  5605.5  327.11
#Mann= 7 ,-1 , 0
  4261.2     .11       0  4866.8    .125       0  4878.7     .09       0
  5081.7     .15       0  5108.8     .11       0  5374.9    .125       0
  5473.6     .11       0
Bank Sta=4878.7,5081.7
XS Rating Curve= 0 ,0
Exp/Cntr=0.3,0.1

Type RM Length L Ch R = 1 ,2879    ,72,72,72
BEGIN DESCRIPTION:
Mapping XS 4734292c
END DESCRIPTION:
XS GIS Cut Line= 3
       3829406.5     10144553.26      3828750.22     10144389.19
      3828263.23     10144279.82
#Sta/Elev= 30
  4306.8  326.99  4385.4  325.78  4545.1  323.88  4788.4  314.92  4841.4  310.26
  4869.8  306.07    4875   308.5    4911  303.67  4916.2  306.97  4952.3  304.01
  4957.4  306.92  4994.2  301.29  4999.3  304.52  5042.6  310.33  5057.4  309.47
  5084.2  300.78  5091.1  302.84  5129.2  301.72  5170.2  308.59  5182.8  312.13
  5213.1  312.99  5317.9  317.54  5334.2  320.29  5348.5  320.56  5366.3  319.49
    5391  321.75  5416.2  324.45  5436.7  322.56  5452.9  325.21  5482.4  324.88
#Mann= 8 ,-1 , 0
  4306.8    .125       0  4385.4     .11       0  4788.4     .15       0
  4841.4     .09       0  5042.6    .125       0  5213.1     .11       0
  5348.5    .125       0    5391     .11       0
Bank Sta=4841.4,5042.6
XS Rating Curve= 0 ,0
Exp/Cntr=0.3,0.1

Type RM Length L Ch R = 1 ,2807    ,307,307,307
BEGIN DESCRIPTION:
Mapping XS b52ab322
END DESCRIPTION:
XS GIS Cut Line= 3
      3829422.12     10144482.95      3828760.63     10144318.88
      3828301.26     10144194.31
#Sta/Elev= 30
  4300.2  326.95    4383  325.94  4407.2  325.17  4417.9  326.63  4448.5  324.33
  4675.5   319.6  4794.8  315.55  4865.6  312.73  4895.5  312.16  4974.3  310.07
  4985.8  309.09  4989.4  303.58  5005.3   304.4  5015.7  308.93  5025.8  310.02
    5031  308.81  5057.1  310.53  5085.1  310.07  5150.4  309.29  5171.1  310.97
  5202.2  311.21  5259.6   315.1  5287.3  315.36  5305.8  316.27    5334  320.27
    5368  318.45    5379  321.06  5419.8  321.17  5448.3  324.27  5457.7  323.95
#Mann= 9 ,-1 , 0
  4300.2    .125       0    4383     .11       0  4794.8     .15       0
  4865.6     .11       0  4895.5    .125       0  4974.3     .09       0
  5025.8    .125       0  5085.1     .11       0  5287.3    .125       0
Bank Sta=4974.3,5025.8
XS Rating Curve= 0 ,0
Exp/Cntr=0.3,0.1

Type RM Length L Ch R = 1 ,2500    ,500,500,500
BEGIN DESCRIPTION:
CRYSTAL CREEK TRIBUTARY NO 9 5.0
END DESCRIPTION:
XS GIS Cut Line= 3
      3829294.69     10144336.62      3828812.91     10144016.93
      3828213.91     10143998.06
#Sta/Elev= 30
  4421.8  331.06    4430  331.75  4438.4  330.05  4453.5  324.37  4474.5  321.22
    4655   315.4  4769.2  310.56  4805.3  307.39  4898.5  303.97  4928.6  303.03
  4992.3  299.25  5015.1  302.74  5055.1   303.4  5065.1  301.77  5075.1  303.14
  5153.5  305.55  5195.2   305.8  5265.2  310.31  5295.2  310.86  5325.2  312.99
  5347.5  317.53  5385.3  314.58  5405.3  317.32  5465.3  322.03  5505.3  320.78
  5515.3   319.3  5535.3  321.66  5575.3  323.68  5594.8  329.12  5599.3  329.12
#Mann= 5 ,-1 , 0
  4421.8     .11       0  4898.5     .17       0  4928.6     .06       0
  5015.1     .17       0  5153.5     .11       0
#XS Ineff= 2 , 0
                         5055.07          303.42
Permanent Ineff=
       F       F
Bank Sta=4928.6,5015.1
XS Rating Curve= 0 ,0
Exp/Cntr=0.3,0.1

Type RM Length L Ch R = 1 ,2000    ,265,265,265
BEGIN DESCRIPTION:
CRYSTAL CREEK TRIBUTARY NO 9 4.0
END DESCRIPTION:
XS GIS Cut Line= 3
      3829517.82     10144061.04      3829118.55     10143642.29
      3828376.68     10143709.43
#Sta/Elev= 30
  4421.4  320.55  4499.2   317.2  4562.7  315.61  4633.6  312.03  4822.1  302.05
  4845.8  300.91  4909.3  298.17  4973.2  297.43  4978.4  296.29  5020.8  297.54
  5060.9  296.96    5081  298.17  5111.1  297.95  5131.2  300.74  5149.6  302.92
  5154.6  302.29  5201.2  305.12  5281.8  308.13  5348.9  308.91  5453.7  309.86
  5522.8  310.22  5532.9   310.8  5542.9  313.27  5597.4  315.85  5623.2  316.15
  5643.3  314.93  5673.4   316.4  5693.5  316.19  5723.6   318.8  5744.9  318.36
#Mann= 8 ,-1 , 0
  4421.4     .11       0  4633.6     .17       0  4822.1     .15       0
  4845.8     .06       0  5131.2     .11       0  5201.2     .15       0
  5348.9     .11       0  5453.7    .125       0
Bank Sta=4845.8,5131.2
XS Rating Curve= 0 ,0
Exp/Cntr=0.3,0.1

Type RM Length L Ch R = 1 ,1735    ,110,110,110
BEGIN DESCRIPTION:
Mapping XS b285c761
END DESCRIPTION:
XS GIS Cut Line= 3
      3829733.86     10143526.61      3829234.08     10143399.58
      3828588.58     10143280.89
#Sta/Elev= 30
  4465.7  310.23  4549.2  310.77  4657.6   308.5  4678.3  307.15  4707.8  307.05
  4712.9  305.72  4771.1  303.75  4789.6  304.25  4802.1   302.4  4876.6  298.86
  4912.4  298.67  4922.2  297.59  4946.5  297.77    4981  295.77  4981.4  295.77
    4986  293.87    5008  295.77  5113.1  298.61  5150.4  301.11  5292.7  306.99
  5323.2  307.29  5363.9  309.71  5536.8  312.79  5552.9  314.09  5575.2  312.97
  5590.2  313.18  5597.8  313.76    5611  312.84  5618.1  311.34  5637.7  311.19
#Mann= 7 ,-1 , 0
  4465.7     .11       0  4922.2     .15       0    4981     .11       0
  4981.4     .06       0    5008     .11       0  5575.2    .125       0
  5590.2     .11       0
Bank Sta=4981.4,5008
XS Rating Curve= 0 ,0
Exp/Cntr=0.3,0.1

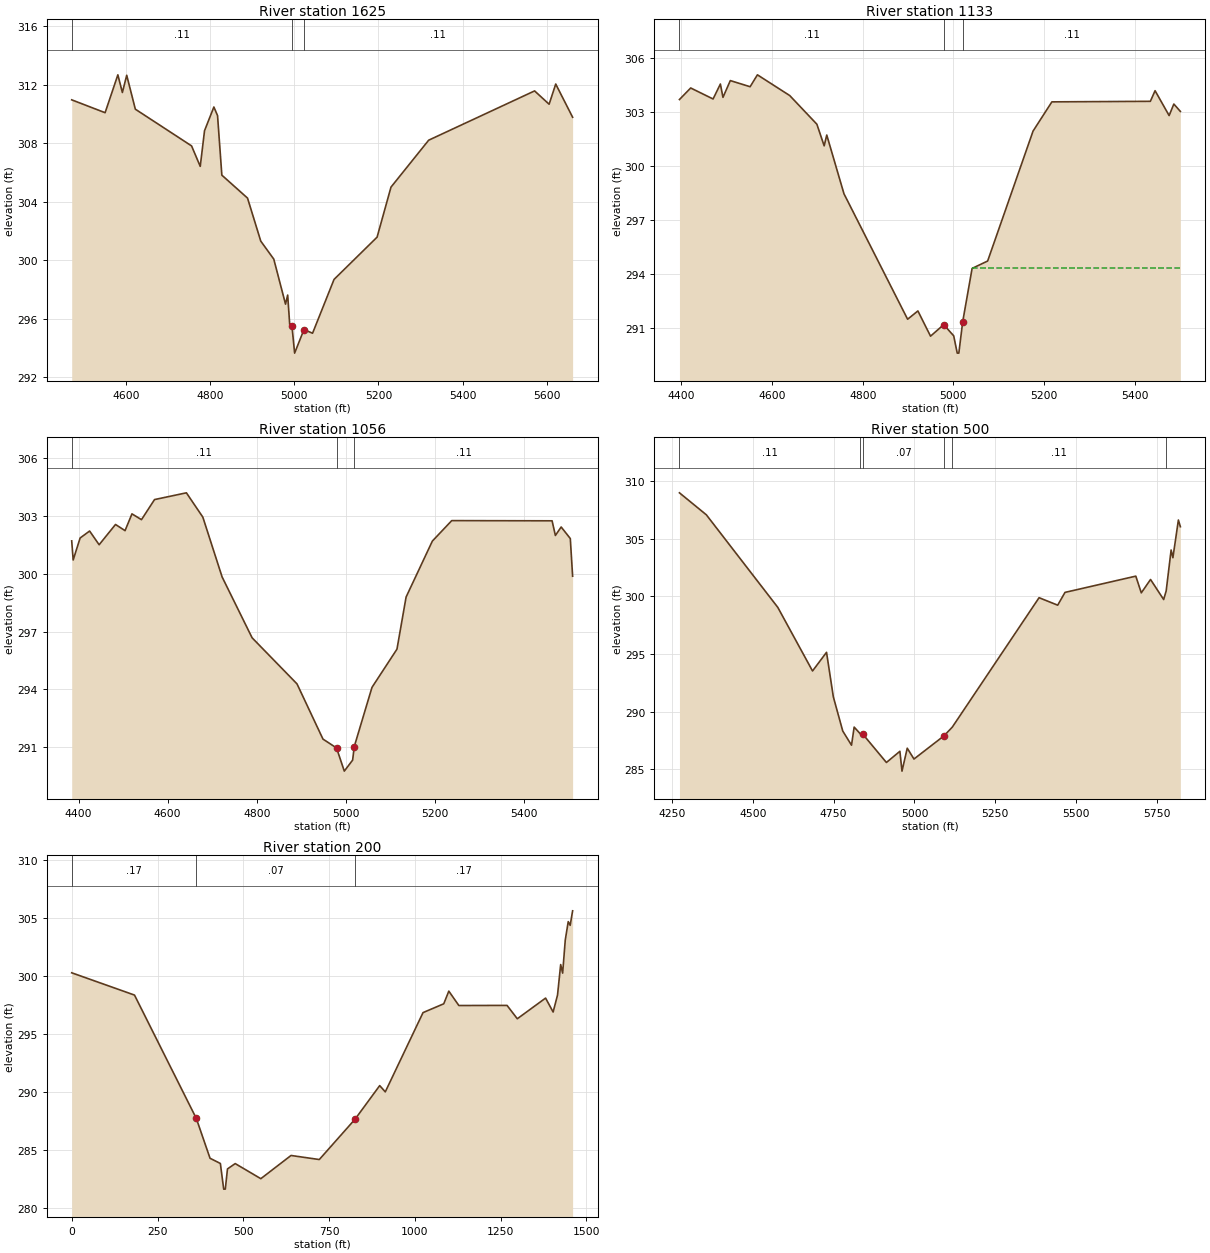
Type RM Length L Ch R = 1 ,1625    ,492,492,492
BEGIN DESCRIPTION:
CRYSTAL CREEK TRIBUTARY NO 9 3.0
END DESCRIPTION:
XS GIS Cut Line= 3
      3829765.03     10143412.07      3829258.57     10143293.77
      3828603.17     10143158.04
#Sta/Elev= 30
  4471.8  310.98  4551.1   310.1  4581.4  312.69  4592.1  311.48  4602.4  312.66
  4622.9  310.34  4756.4  307.83    4777  306.43  4787.2  308.87  4809.4  310.49
  4818.1   309.9  4828.3  305.83  4889.3  304.26  4920.7  301.32  4951.6  300.09
  4979.5  297.01  4984.6  297.63  4989.7  295.51  4994.8  295.51  5001.1  293.66
  5023.3  295.27  5043.7  295.02  5094.7   298.7  5196.9  301.59  5229.9  305.01
  5319.4  308.22  5570.9  311.59  5605.4  310.68  5621.1  312.06  5661.2  309.79
#Mann= 3 , 0 , 0
  4471.8     .11       0  4994.8     .07       0  5023.3     .11       0
#XS Ineff= 2 , 0
          4984.6  297.63
Permanent Ineff=
       F       F
Bank Sta=4994.8,5023.3
XS Rating Curve= 0 ,0
Exp/Cntr=0.3,0.1

Type RM Length L Ch R = 1 ,1133    ,77,77,77
BEGIN DESCRIPTION:
Mapping XS 5b33ae33
END DESCRIPTION:
XS GIS Cut Line= 3
       3829740.1     10143130.37      3829222.76     10142849.13
      3828723.92     10142715.76
#Sta/Elev= 30
  4395.7  303.67  4420.5  304.31  4469.9   303.7    4486  304.53  4491.7  303.79
  4507.9  304.72  4551.6  304.38  4567.7  305.04    4639  303.89  4698.9   302.3
    4715   301.1  4720.7   301.7  4758.7  298.44  4899.1  291.48  4921.8  291.94
  4949.7  290.54  4978.7  291.18  5000.8  290.56  5008.6   289.6  5012.1   289.6
  5020.7  291.35  5041.4   294.3  5075.7  294.71  5175.9  301.92  5217.4  303.54
  5434.7  303.57  5445.1  304.16  5476.1  302.78  5486.5  303.42  5500.9  303.01
#Mann= 3 , 0 , 0
  4395.7     .11       0  4978.7     .07       0  5020.7     .11       0
#XS Ineff= 2 , 0
                         5041.38           294.3
Permanent Ineff=
       F       F
Bank Sta=4978.7,5020.7
XS Rating Curve= 0 ,0
Exp/Cntr=0.3,0.1

Type RM Length L Ch R = 1 ,1056    ,556,556,556
BEGIN DESCRIPTION:
CRYSTAL CREEK TRIBUTARY NO 9 2.0
END DESCRIPTION:
XS GIS Cut Line= 3
      3829747.07     10143086.98      3829220.14      10142768.9
      3828722.81     10142658.17
#Sta/Elev= 30
  4384.5   301.7  4387.8  300.71  4403.4  301.85  4424.7  302.21  4446.1   301.5
  4482.9  302.55  4504.3  302.23  4519.8   303.1  4541.2   302.8  4570.5  303.84
  4642.1  304.19    4679  302.93  4722.3  299.83  4789.6  296.68  4890.5  294.29
  4948.8  291.43  4979.3  290.97  4996.7  289.77  5015.4  290.34 5019.13291.0457
  5058.9  294.11    5115  296.09  5135.5  298.79  5194.5  301.69    5238  302.75
  5463.4  302.74  5470.8  301.98  5483.8  302.42  5504.3  301.82  5509.5  299.87
#Mann= 3 , 0 , 0
  4384.5     .11       0  4979.3     .07       0 5019.13     .11       0
Bank Sta=4979.3,5019.13
XS Rating Curve= 0 ,0
Exp/Cntr=0.3,0.1

Type RM Length L Ch R = 1 ,500     ,418,418,418
BEGIN DESCRIPTION:
CRYSTAL CREEK TRIBUTARY NO 9 1.0
END DESCRIPTION:
XS GIS Cut Line= 3
      3829999.95     10142745.89      3829421.36     10142305.38
       3828672.3     10142645.84
#Sta/Elev= 30
  4272.8  308.99  4356.1  307.08  4577.1  299.05  4684.6  293.53  4727.9  295.15
    4749  291.28  4778.1  288.32  4805.2  287.09  4813.4  288.66  4832.6  288.07
    4841  288.02  4913.2  285.59  4954.9  286.56  4961.4  284.84  4977.7  286.83
  4998.5  285.89  5091.7  287.91  5117.1  288.66  5385.6  299.89  5443.2  299.24
  5465.8  300.35  5684.9  301.76  5701.9  300.31  5730.5  301.47  5771.1  299.73
  5778.9  300.48  5794.2  304.03  5799.7  303.36  5816.7  306.63  5822.8  306.05
#Mann= 6 ,-1 , 0
  4272.8     .11       0  4832.6     .17       0    4841     .07       0
  5091.7     .17       0  5117.1     .11       0  5778.9     .15       0
Bank Sta=4841,5091.7
XS Rating Curve= 0 ,0
Exp/Cntr=0.3,0.1

Type RM Length L Ch R = 1 ,200     ,0,0,0
XS GIS Cut Line= 3
      3830050.75     10142052.58      3829603.42     10142037.13
      3828708.98     10142510.67
#Sta/Elev= 30
       0  300.28     183  298.36   363.1  287.73   403.1   284.3   433.2  283.85
   442.9  281.64   447.6  281.64   453.9  283.38   476.5  283.84   551.1  282.54
   639.1  284.54   721.5  284.19   825.8  287.67   897.5  290.56   913.8  290.02
  1023.8  296.85  1084.2  297.61  1098.9   298.7  1128.2  297.46  1268.6  297.47
  1298.5  296.32  1380.9   298.1  1402.9   296.9  1415.7  298.36  1424.9  300.99
  1430.6  300.25  1438.3  303.11  1446.9  304.69  1452.6  304.37  1459.7  305.62
#Mann= 3 , 0 , 0
       0     .17       0   363.1     .07       0   825.8     .17       0
Bank Sta=363.1,825.8
XS Rating Curve= 0 ,0
Exp/Cntr=0.3,0.1

Chan Stop Cuts=-1
Use User Specified Reach Order=0
Composite Channel Slope=5

--- CRYSTAL CREEK TRIBUTARY NO 9.g10 (geometry) ---

Geom Title=Existing Conditions
Program Version=4.10

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
River Reach=CRYSTAL CREEK TR,Reach-1

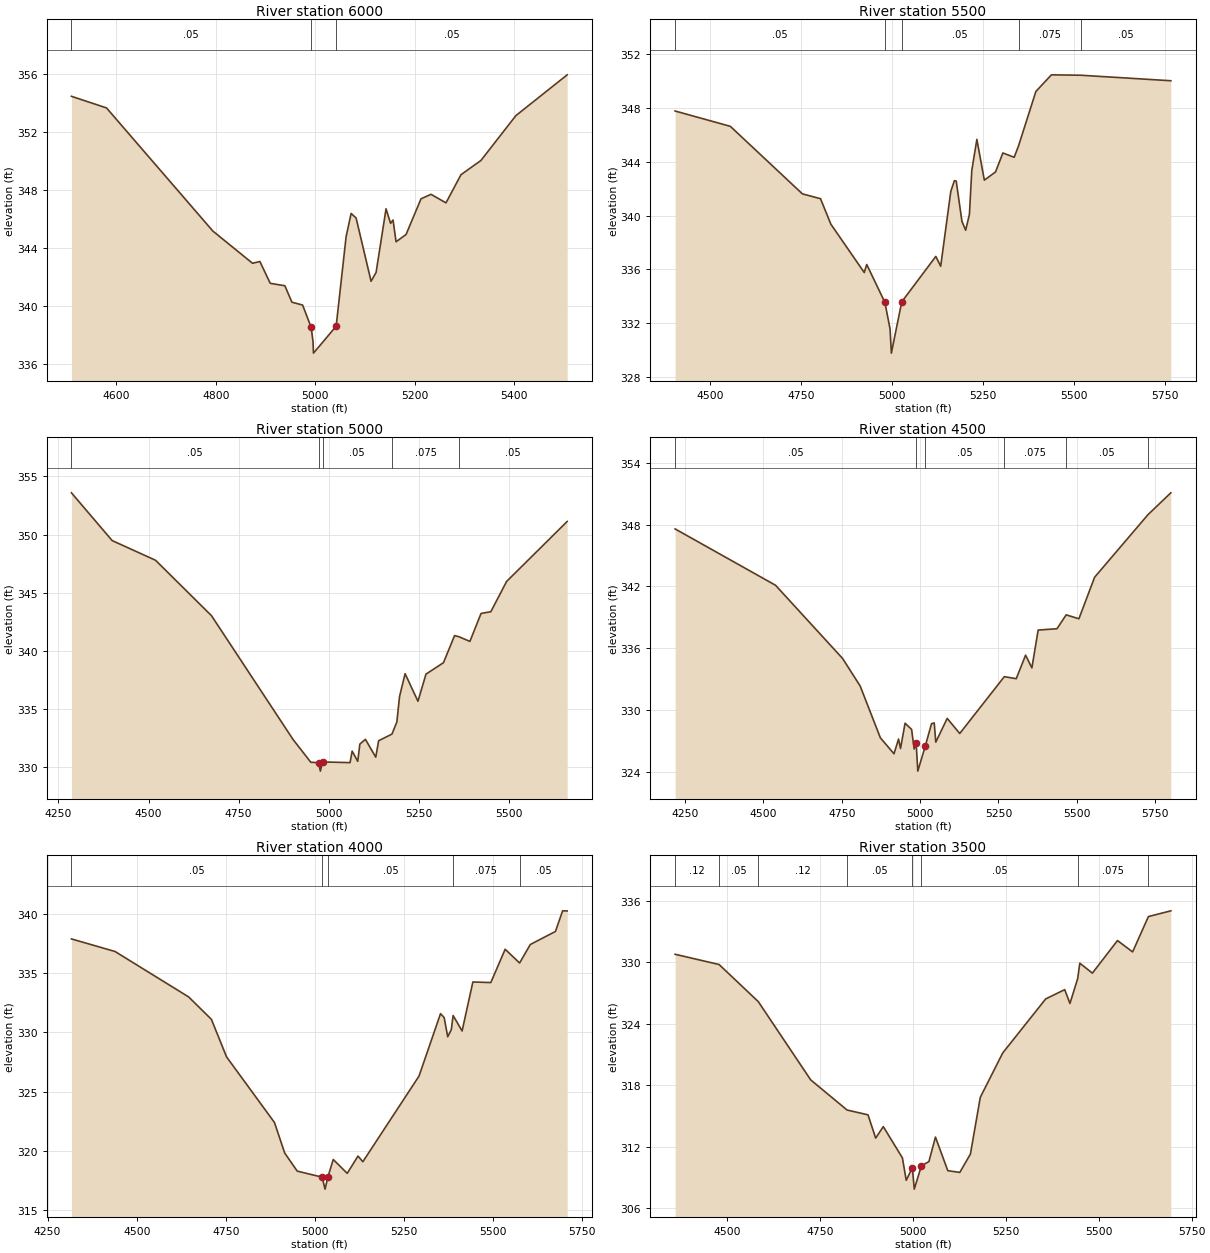
Type RM Length L Ch R = 1 ,6000    ,500,500,500
BEGIN DESCRIPTION:
CRYSTAL CREEK TRIBUTARY NO 9 12.0
END DESCRIPTION:
XS GIS Cut Line= 3
      3827937.91     10147488.75      3827539.38     10147202.98
      3827035.08     10147245.67
#Sta/Elev= 30
  4509.6  354.47  4580.1  353.67  4793.8  345.19  4873.6  342.97  4888.4  343.09
  4909.2  341.59  4938.7  341.42  4952.7  340.29  4974.3  340.09 4991.46 338.555
  4995.2  337.58  4996.1  336.78  5041.7  338.63  5061.7   344.8  5071.8   346.4
  5081.8  346.09  5111.9  341.73    5122  342.34    5142  346.72  5151.1  345.72
  5156.1  345.95  5162.1  344.45  5182.2  344.95  5212.3  347.41  5232.4  347.72
  5262.5  347.13  5292.6  349.07  5332.7  350.05    5403  353.14  5506.1  355.95
#Mann= 3 , 0 , 0
  4509.6     .05       0 4991.46     .03       0  5041.7     .05       0
Bank Sta=4991.46,5041.7
XS Rating Curve= 0 ,0
Exp/Cntr=0.3,0.1

Type RM Length L Ch R = 1 ,5500    ,500,500,500
BEGIN DESCRIPTION:
CRYSTAL CREEK TRIBUTARY NO 9 11.0
END DESCRIPTION:
XS GIS Cut Line= 3
      3828237.37     10147176.24      3827794.99     10146775.65
      3827048.12     10146603.31
#Sta/Elev= 30
  4403.2  347.78  4555.1  346.64  4753.3  341.62  4803.1  341.26  4831.5  339.37
  4923.4  335.77  4930.2  336.37  4980.2  333.55  4994.4  331.57  4997.9  329.78
 5026.53 333.595  5120.2  336.97  5133.6  336.24  5161.3  341.79  5171.2   342.6
  5176.3  342.57  5192.1  339.57  5202.3  338.92  5212.6   340.1  5219.1  343.36
  5233.1  345.67  5253.6  342.64  5284.4  343.25  5304.6  344.66  5335.7  344.34
  5347.7  345.19  5395.3  349.23  5438.1  350.47  5518.8  350.44  5766.5  350.03
#Mann= 5 ,-1 , 0
  4403.2     .05       0  4980.2     .03       0 5026.53     .05       0
  5347.7    .075       0  5518.8     .05       0
Bank Sta=4980.2,5026.53
XS Rating Curve= 0 ,0
Exp/Cntr=0.3,0.1

Type RM Length L Ch R = 1 ,5000    ,500,500,500
BEGIN DESCRIPTION:
CRYSTAL CREEK TRIBUTARY NO 9 10.0
END DESCRIPTION:
XS GIS Cut Line= 3
      3828517.82     10146811.04      3827999.68     10146319.78
      3827434.38     10145973.95
#Sta/Elev= 30
    4286  353.58    4399  349.48  4519.5  347.79  4674.9  343.03  4901.4   332.4
  4950.8  330.44  4972.2  330.41  4977.3  329.68 4983.23 330.469  5059.7  330.41
  5065.6   331.4  5081.1  330.52  5086.9     332  5102.4  332.41  5131.1  330.88
  5139.1  332.29  5176.1  332.86  5189.7   333.9  5197.2  336.09  5212.6  338.05
  5248.3  335.68  5270.6  338.01  5319.1  338.99    5350  341.32  5362.4  341.22
  5392.6  340.82  5423.5  343.22  5450.7  343.37  5494.5  345.97  5662.7  351.12
#Mann= 5 ,-1 , 0
    4286     .05       0  4972.2     .03       0 4983.23     .05       0
  5176.1    .075       0  5362.4     .05       0
Bank Sta=4972.2,4983.23
XS Rating Curve= 0 ,0
Exp/Cntr=0.3,0.1

Type RM Length L Ch R = 1 ,4500    ,500,500,500
BEGIN DESCRIPTION:
CRYSTAL CREEK TRIBUTARY NO 9 9.0
END DESCRIPTION:
XS GIS Cut Line= 3
      3828740.85     10146516.52      3828264.36     10145897.21
      3827464.78     10145878.48
#Sta/Elev= 30
  4218.6   347.6  4538.9  342.12  4752.8     335  4808.9  332.32  4873.3  327.28
  4916.8  325.73  4931.3  327.16  4937.6  326.24  4952.1   328.7  4972.9   328.1
  4981.1  326.19  4987.4  326.82  4992.7  324.04  5016.5  326.47  5036.5  328.65
  5045.1  328.73  5050.1  326.86  5086.5  329.17  5126.5   327.7  5268.7  333.23
  5306.6  333.03  5336.6  335.32  5356.6  334.08  5376.6  337.76  5436.6  337.89
    5466  339.24  5506.6  338.86  5556.7   342.9  5726.7  348.98  5799.8  351.11
#Mann= 6 ,-1 , 0
  4218.6     .05       0  4987.4     .03       0  5016.5     .05       0
  5268.7    .075       0    5466     .05       0  5726.7     .12       0
Bank Sta=4987.4,5016.5
XS Rating Curve= 0 ,0
Exp/Cntr=0.3,0.1

Type RM Length L Ch R = 1 ,4000    ,500,500,500
BEGIN DESCRIPTION:
CRYSTAL CREEK TRIBUTARY NO 9 8.0
END DESCRIPTION:
XS GIS Cut Line= 3
      3829011.64     10145889.74      3828487.68      10145451.6
      3827785.13     10145368.94
#Sta/Elev= 30
    4317  337.87  4439.3  336.81  4645.7  332.98  4709.5  331.09  4752.1  327.92
  4886.4  322.39  4915.1  319.82  4950.2  318.29    5020  317.78  5028.3  316.77
 5036.35 317.802  5051.3  319.27  5090.5   318.1  5120.7  319.56  5134.3  319.08
  5291.8   326.3  5352.2  331.57  5362.3  331.24  5372.4  329.62  5382.5  330.23
  5387.5  331.41  5412.7  330.11  5442.9  334.24  5493.2  334.19  5533.5     337
    5574  335.84    5604   337.4  5674.5   338.5  5694.6  340.24  5707.4  340.23
#Mann= 5 ,-1 , 0
    4317     .05       0    5020     .03       0 5036.35     .05       0
  5387.5    .075       0    5574     .05       0
Bank Sta=5020,5036.35
XS Rating Curve= 0 ,0
Exp/Cntr=0.3,0.1

Type RM Length L Ch R = 1 ,3500    ,500,500,500
BEGIN DESCRIPTION:
CRYSTAL CREEK TRIBUTARY NO 9 7.0
END DESCRIPTION:
XS GIS Cut Line= 3
      3829272.91     10145133.03      3828650.69     10144986.68
      3827966.49     10144870.45
#Sta/Elev= 30
  4360.8  330.77  4479.1  329.77  4584.5  326.15  4725.5  318.51  4823.3  315.57
  4879.6   315.1  4900.2  312.83  4920.7  313.95  4972.1   310.9  4982.4  308.71
  4998.9  309.94    5004  307.85  5023.2  310.12  5043.4  310.54    5061  312.93
  5094.2  309.65  5126.4  309.48    5155  311.27  5181.6  316.81  5241.9  321.14
  5357.4  326.41  5408.6  327.32  5422.7  325.97  5443.5   328.4  5449.2   329.9
    5483  328.93  5550.6  332.11  5591.2     331  5633.7  334.45    5694  335.01
#Mann= 8 ,-1 , 0
  4360.8     .12       0  4479.1     .05       0  4584.5     .12       0
  4823.3     .05       0  4998.9     .07       0  5023.2     .05       0
  5443.5    .075       0  5633.7     .05       0
Bank Sta=4998.9,5023.2
XS Rating Curve= 0 ,0
Exp/Cntr=0.3,0.1

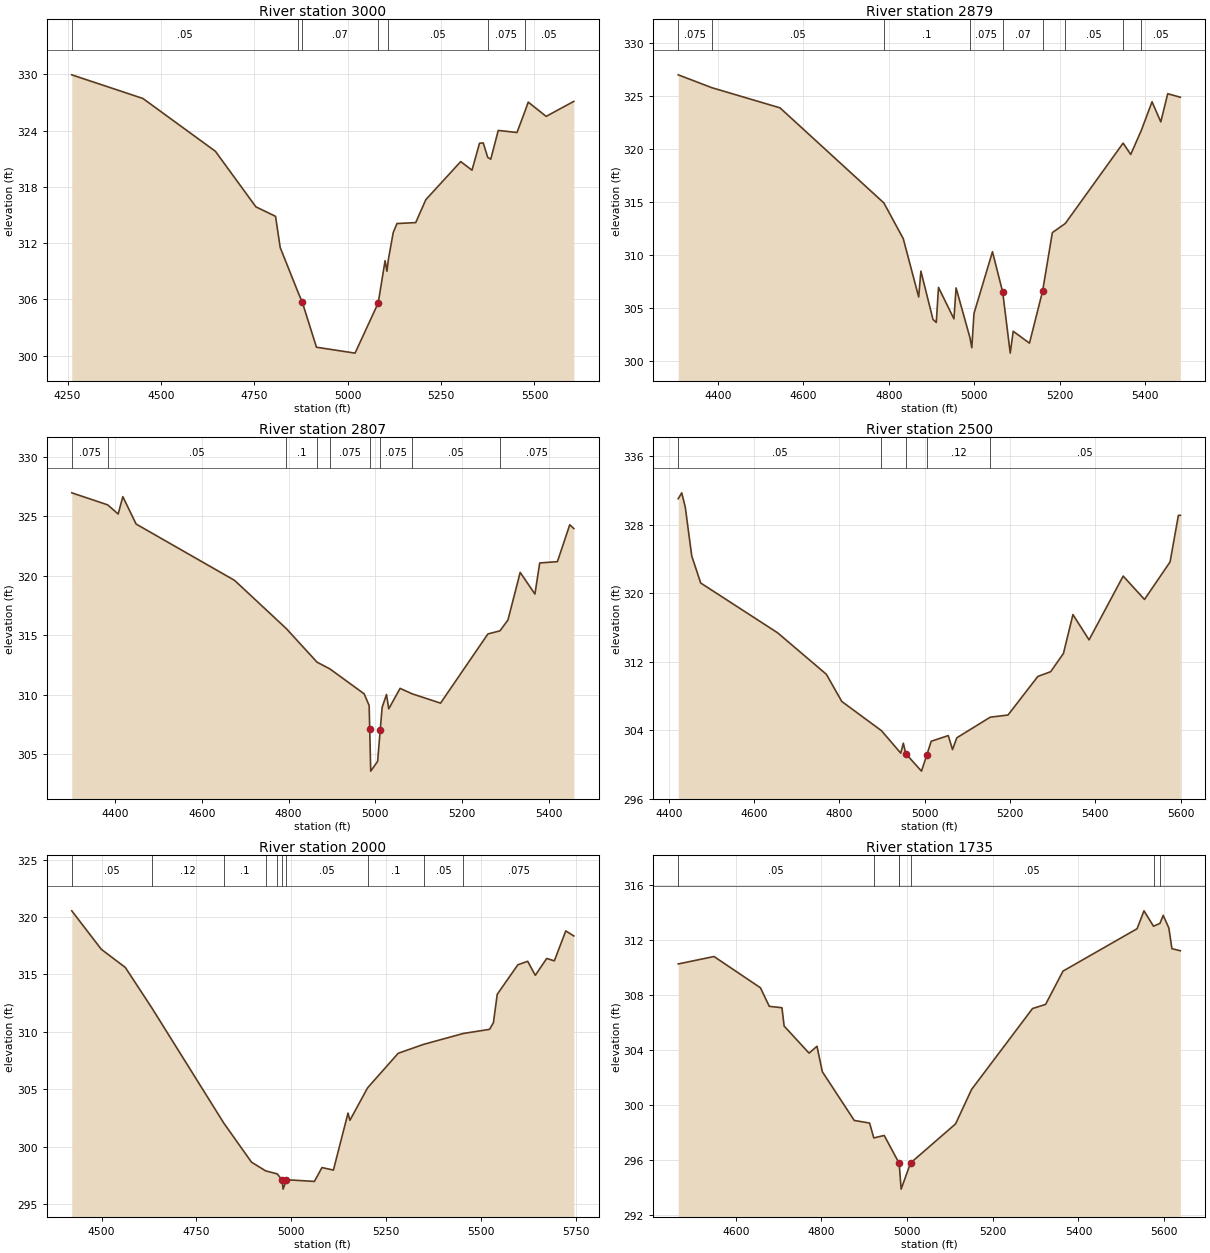
Type RM Length L Ch R = 1 ,3000    ,121,121,121
BEGIN DESCRIPTION:
CRYSTAL CREEK TRIBUTARY NO 9 6.0
END DESCRIPTION:
XS GIS Cut Line= 3
      3829364.09     10144866.11      3828719.18     10144505.67
      3828116.29     10144449.45
#Sta/Elev= 30
  4261.2  329.94  4451.6  327.42  4645.7  321.79  4754.2  315.86  4806.8  314.85
  4819.3  311.52  4866.8  306.78  4878.7  305.66  4916.4  300.89  5019.7  300.26
  5081.7  305.61  5100.1  310.12  5105.1  308.99  5108.8  310.22  5121.9  313.12
  5131.9  314.08  5182.1  314.18  5209.1  316.62  5302.6  320.69  5332.8  319.77
  5352.9  322.64  5362.9  322.68  5374.9  321.14    5383  320.94  5403.1  324.01
  5453.3  323.79  5473.6  325.94  5483.4  327.03  5531.4  325.51  5605.5  327.11
#Mann= 7 ,-1 , 0
  4261.2     .05       0  4866.8    .075       0  4878.7     .07       0
  5081.7      .1       0  5108.8     .05       0  5374.9    .075       0
  5473.6     .05       0
Bank Sta=4878.7,5081.7
XS Rating Curve= 0 ,0
Exp/Cntr=0.3,0.1

Type RM Length L Ch R = 1 ,2879    ,72,72,72
BEGIN DESCRIPTION:
Mapping XS 4734292c
END DESCRIPTION:
XS GIS Cut Line= 3
       3829406.5     10144553.26      3828750.22     10144389.19
      3828263.23     10144279.82
#Sta/Elev= 30
  4306.8  326.99  4385.4  325.78  4545.1  323.88  4788.4  314.92  4833.7  311.56
  4869.8  306.07    4875   308.5  4903.3  303.95    4911  303.67  4916.2  306.97
  4952.3  304.01  4957.4  306.92  4989.9  302.23  4994.2  301.29  4999.3  304.52
  5042.6  310.33 5066.49 306.531  5084.2  300.78  5091.1  302.84  5129.2  301.72
  5159.9  306.61  5182.8  312.13  5213.1  312.99  5348.5  320.56  5366.3  319.49
    5391  321.75  5416.2  324.45  5436.7  322.56  5452.9  325.21  5482.4  324.88
#Mann= 9 ,-1 , 0
  4306.8    .075       0  4385.4     .05       0  4788.4      .1       0
  4989.9    .075       0 5066.49     .07       0  5159.9    .075       0
  5213.1     .05       0  5348.5    .075       0    5391     .05       0
Bank Sta=5066.49,5159.9
XS Rating Curve= 0 ,0
Exp/Cntr=0.3,0.1

Type RM Length L Ch R = 1 ,2807    ,307,307,307
BEGIN DESCRIPTION:
Mapping XS b52ab322
END DESCRIPTION:
XS GIS Cut Line= 3
      3829422.12     10144482.95      3828760.63     10144318.88
      3828301.26     10144194.31
#Sta/Elev= 30
  4300.2  326.95    4383  325.94  4407.2  325.17  4417.9  326.63  4448.5  324.33
  4675.5   319.6  4794.8  315.55  4865.6  312.73  4895.5  312.16  4974.3  310.07
  4985.8  309.09 4987.11 307.101  4989.4  303.58  5005.3   304.4 5011.39 307.053
  5015.7  308.93  5025.8  310.02    5031  308.81  5057.1  310.53  5085.1  310.07
  5150.4  309.29  5259.6   315.1  5287.3  315.36  5305.8  316.27    5334  320.27
    5368  318.45    5379  321.06  5419.8  321.17  5448.3  324.27  5457.7  323.95
#Mann= 9 ,-1 , 0
  4300.2    .075       0    4383     .05       0  4794.8      .1       0
  4865.6     .05       0  4895.5    .075       0 4987.11     .07       0
 5011.39    .075       0  5085.1     .05       0  5287.3    .075       0
Bank Sta=4987.11,5011.39
XS Rating Curve= 0 ,0
Exp/Cntr=0.3,0.1

Type RM Length L Ch R = 1 ,2500    ,500,500,500
BEGIN DESCRIPTION:
CRYSTAL CREEK TRIBUTARY NO 9 5.0
END DESCRIPTION:
XS GIS Cut Line= 3
      3829294.69     10144336.62      3828812.91     10144016.93
      3828213.91     10143998.06
#Sta/Elev= 30
  4421.8  331.06    4430  331.75  4438.4  330.05  4453.5  324.37  4474.5  321.22
    4655   315.4  4769.2  310.56  4805.3  307.39  4898.5  303.97  4943.7  301.35
  4949.7  302.51 4955.29 301.299  4992.3  299.25  5005.1  301.19  5015.1  302.74
  5055.1   303.4  5065.1  301.77  5075.1  303.14  5153.5  305.55  5195.2   305.8
  5265.2  310.31  5295.2  310.86  5325.2  312.99  5347.5  317.53  5385.3  314.58
  5465.3  322.03  5515.3   319.3  5575.3  323.68  5594.8  329.12  5599.3  329.12
#Mann= 5 ,-1 , 0
  4421.8     .05       0  4898.5     .12       0 4955.29     .03       0
  5005.1     .12       0  5153.5     .05       0
Bank Sta=4955.29,5005.1
XS Rating Curve= 0 ,0
Exp/Cntr=0.3,0.1

Type RM Length L Ch R = 1 ,2000    ,265,265,265
BEGIN DESCRIPTION:
CRYSTAL CREEK TRIBUTARY NO 9 4.0
END DESCRIPTION:
XS GIS Cut Line= 3
      3829517.82     10144061.04      3829118.55     10143642.29
      3828376.68     10143709.43
#Sta/Elev= 30
  4421.4  320.55  4499.2   317.2  4562.7  315.61  4633.6  312.03  4822.1  302.05
  4895.2  298.64  4932.6  297.88    4963  297.62 4975.75 297.097  4978.4  296.29
  4987.4  297.11  5060.9  296.96    5081  298.17  5111.1  297.95  5149.6  302.92
  5154.6  302.29  5201.2  305.12  5281.8  308.13  5348.9  308.91  5453.7  309.86
  5522.8  310.22  5532.9   310.8  5542.9  313.27  5597.4  315.85  5623.2  316.15
  5643.3  314.93  5673.4   316.4  5693.5  316.19  5723.6   318.8  5744.9  318.36
#Mann= 10 ,-1 , 0
  4421.4     .05       0  4633.6     .12       0  4822.1      .1       0
  4932.6     .12       0    4963     .05       0 4975.75     .03       0
  4987.4     .05       0  5201.2      .1       0  5348.9     .05       0
  5453.7    .075       0
Bank Sta=4975.75,4987.4
XS Rating Curve= 0 ,0
Exp/Cntr=0.3,0.1

Type RM Length L Ch R = 1 ,1735    ,110,110,110
BEGIN DESCRIPTION:
Mapping XS b285c761
END DESCRIPTION:
XS GIS Cut Line= 3
      3829733.86     10143526.61      3829234.08     10143399.58
      3828588.58     10143280.89
#Sta/Elev= 30
  4465.7  310.23  4549.2  310.77  4657.6   308.5  4678.3  307.15  4707.8  307.05
  4712.9  305.72  4771.1  303.75  4789.6  304.25  4802.1   302.4  4876.6  298.86
  4912.4  298.67  4922.2  297.59  4946.5  297.77    4981  295.77  4981.4  295.77
    4986  293.87    5008  295.77  5113.1  298.61  5150.4  301.11  5292.7  306.99
  5323.2  307.29  5363.9  309.71  5536.8  312.79  5552.9  314.09  5575.2  312.97
  5590.2  313.18  5597.8  313.76    5611  312.84  5618.1  311.34  5637.7  311.19
#Mann= 7 ,-1 , 0
  4465.7     .05       0  4922.2      .1       0    4981     .05       0
  4981.4     .03       0    5008     .05       0  5575.2    .075       0
  5590.2     .05       0
Bank Sta=4981.4,5008
XS Rating Curve= 0 ,0
Exp/Cntr=0.3,0.1