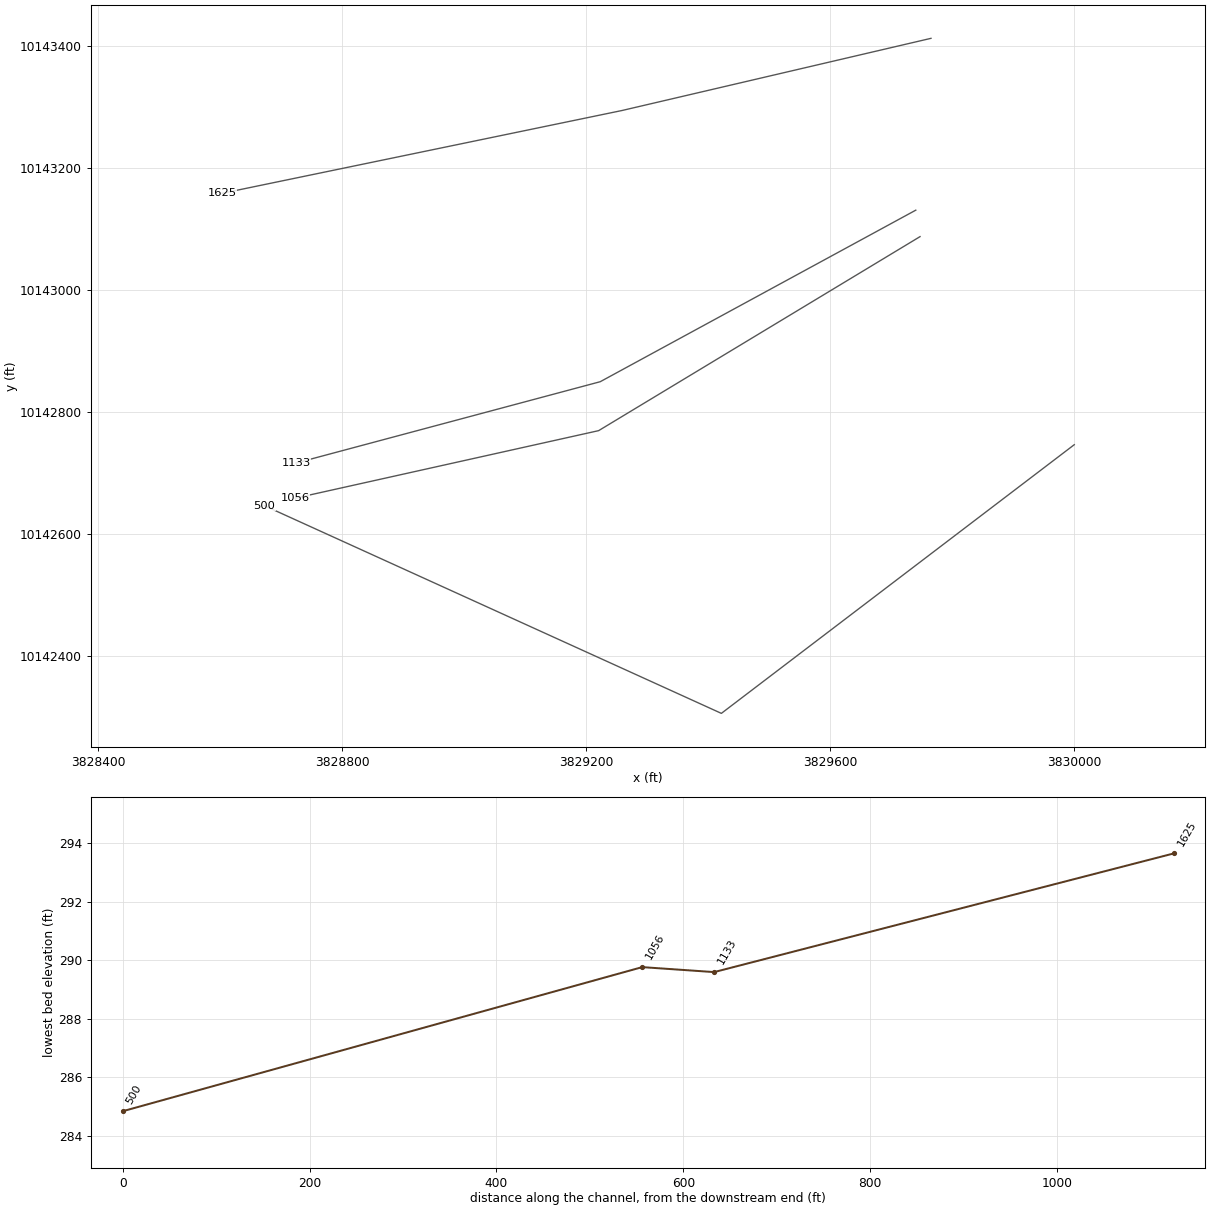
HEC-RAS study CRYSTAL CREEK TRIBUTARY NO 9.prj: CRYSTAL CREEK TRIBUTARY NO 9 Base Level Engineering

--- CRYSTAL CREEK TRIBUTARY NO 9.g10 (geometry) --- (continued)

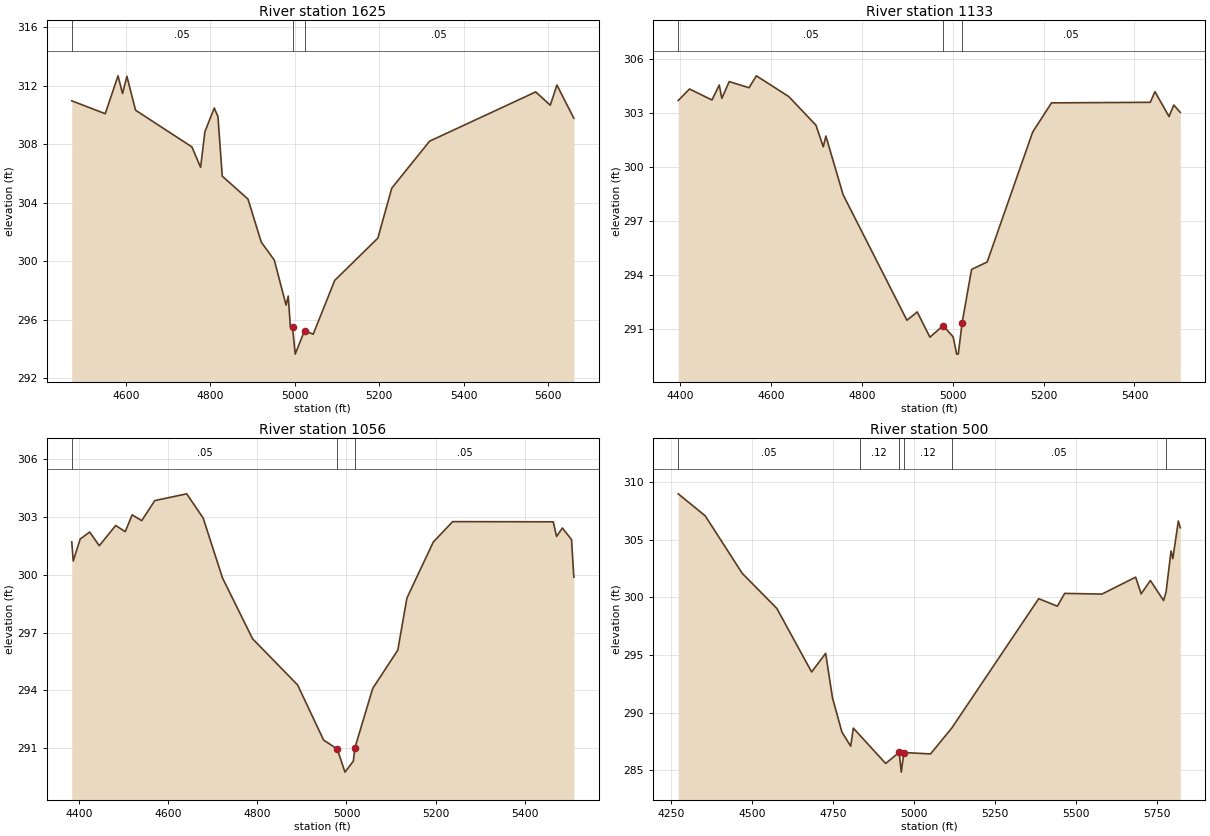
Type RM Length L Ch R = 1 ,1625    ,492,492,492
BEGIN DESCRIPTION:
CRYSTAL CREEK TRIBUTARY NO 9 3.0
END DESCRIPTION:
XS GIS Cut Line= 3
      3829765.03     10143412.07      3829258.57     10143293.77
      3828603.17     10143158.04
#Sta/Elev= 30
  4471.8  310.98  4551.1   310.1  4581.4  312.69  4592.1  311.48  4602.4  312.66
  4622.9  310.34  4756.4  307.83    4777  306.43  4787.2  308.87  4809.4  310.49
  4818.1   309.9  4828.3  305.83  4889.3  304.26  4920.7  301.32  4951.6  300.09
  4979.5  297.01  4984.6  297.63  4989.7  295.51  4994.8  295.51  5001.1  293.66
  5023.3  295.27  5043.7  295.02  5094.7   298.7  5196.9  301.59  5229.9  305.01
  5319.4  308.22  5570.9  311.59  5605.4  310.68  5621.1  312.06  5661.2  309.79
#Mann= 3 , 0 , 0
  4471.8     .05       0  4994.8     .07       0  5023.3     .05       0
Bank Sta=4994.8,5023.3
XS Rating Curve= 0 ,0
Exp/Cntr=0.3,0.1

Type RM Length L Ch R = 1 ,1133    ,77,77,77
BEGIN DESCRIPTION:
Mapping XS 5b33ae33
END DESCRIPTION:
XS GIS Cut Line= 3
       3829740.1     10143130.37      3829222.76     10142849.13
      3828723.92     10142715.76
#Sta/Elev= 30
  4395.7  303.67  4420.5  304.31  4469.9   303.7    4486  304.53  4491.7  303.79
  4507.9  304.72  4551.6  304.38  4567.7  305.04    4639  303.89  4698.9   302.3
    4715   301.1  4720.7   301.7  4758.7  298.44  4899.1  291.48  4921.8  291.94
  4949.7  290.54  4978.7  291.18  5000.8  290.56  5008.6   289.6  5012.1   289.6
  5020.7  291.35  5041.4   294.3  5075.7  294.71  5175.9  301.92  5217.4  303.54
  5434.7  303.57  5445.1  304.16  5476.1  302.78  5486.5  303.42  5500.9  303.01
#Mann= 3 , 0 , 0
  4395.7     .05       0  4978.7     .07       0  5020.7     .05       0
Bank Sta=4978.7,5020.7
XS Rating Curve= 0 ,0
Exp/Cntr=0.3,0.1

Type RM Length L Ch R = 1 ,1056    ,556,556,556
BEGIN DESCRIPTION:
CRYSTAL CREEK TRIBUTARY NO 9 2.0
END DESCRIPTION:
XS GIS Cut Line= 3
      3829747.07     10143086.98      3829220.14      10142768.9
      3828722.81     10142658.17
#Sta/Elev= 30
  4384.5   301.7  4387.8  300.71  4403.4  301.85  4424.7  302.21  4446.1   301.5
  4482.9  302.55  4504.3  302.23  4519.8   303.1  4541.2   302.8  4570.5  303.84
  4642.1  304.19    4679  302.93  4722.3  299.83  4789.6  296.68  4890.5  294.29
  4948.8  291.43  4979.3  290.97  4996.7  289.77  5015.4  290.34 5019.13 291.046
  5058.9  294.11    5115  296.09  5135.5  298.79  5194.5  301.69    5238  302.75
  5463.4  302.74  5470.8  301.98  5483.8  302.42  5504.3  301.82  5509.5  299.87
#Mann= 3 , 0 , 0
  4384.5     .05       0  4979.3     .07       0 5019.13     .05       0
Bank Sta=4979.3,5019.13
XS Rating Curve= 0 ,0
Exp/Cntr=0.3,0.1

Type RM Length L Ch R = 1 ,500     ,0,0,0
BEGIN DESCRIPTION:
CRYSTAL CREEK TRIBUTARY NO 9 1.0
END DESCRIPTION:
XS GIS Cut Line= 3
      3829999.95     10142745.89      3829421.36     10142305.38
       3828672.3     10142645.84
#Sta/Elev= 30
  4272.8  308.99  4356.1  307.08  4470.4  302.09  4577.1  299.05  4684.6  293.53
  4727.9  295.15    4749  291.28  4778.1  288.32  4805.2  287.09  4813.4  288.66
  4832.6  288.07  4913.2  285.59  4954.9  286.56  4961.4  284.84  4969.4  286.54
  5051.6  286.42  5117.1  288.66  5385.6  299.89  5443.2  299.24  5465.8  300.35
  5581.1  300.29  5684.9  301.76  5701.9  300.31  5730.5  301.47  5771.1  299.73
  5778.9  300.48  5794.2  304.03  5799.7  303.36  5816.7  306.63  5822.8  306.05
#Mann= 6 ,-1 , 0
  4272.8     .05       0  4832.6     .12       0  4954.9     .07       0
  4969.4     .12       0  5117.1     .05       0  5778.9      .1       0
Bank Sta=4954.9,4969.4
XS Rating Curve= 0 ,0
Exp/Cntr=0.3,0.1