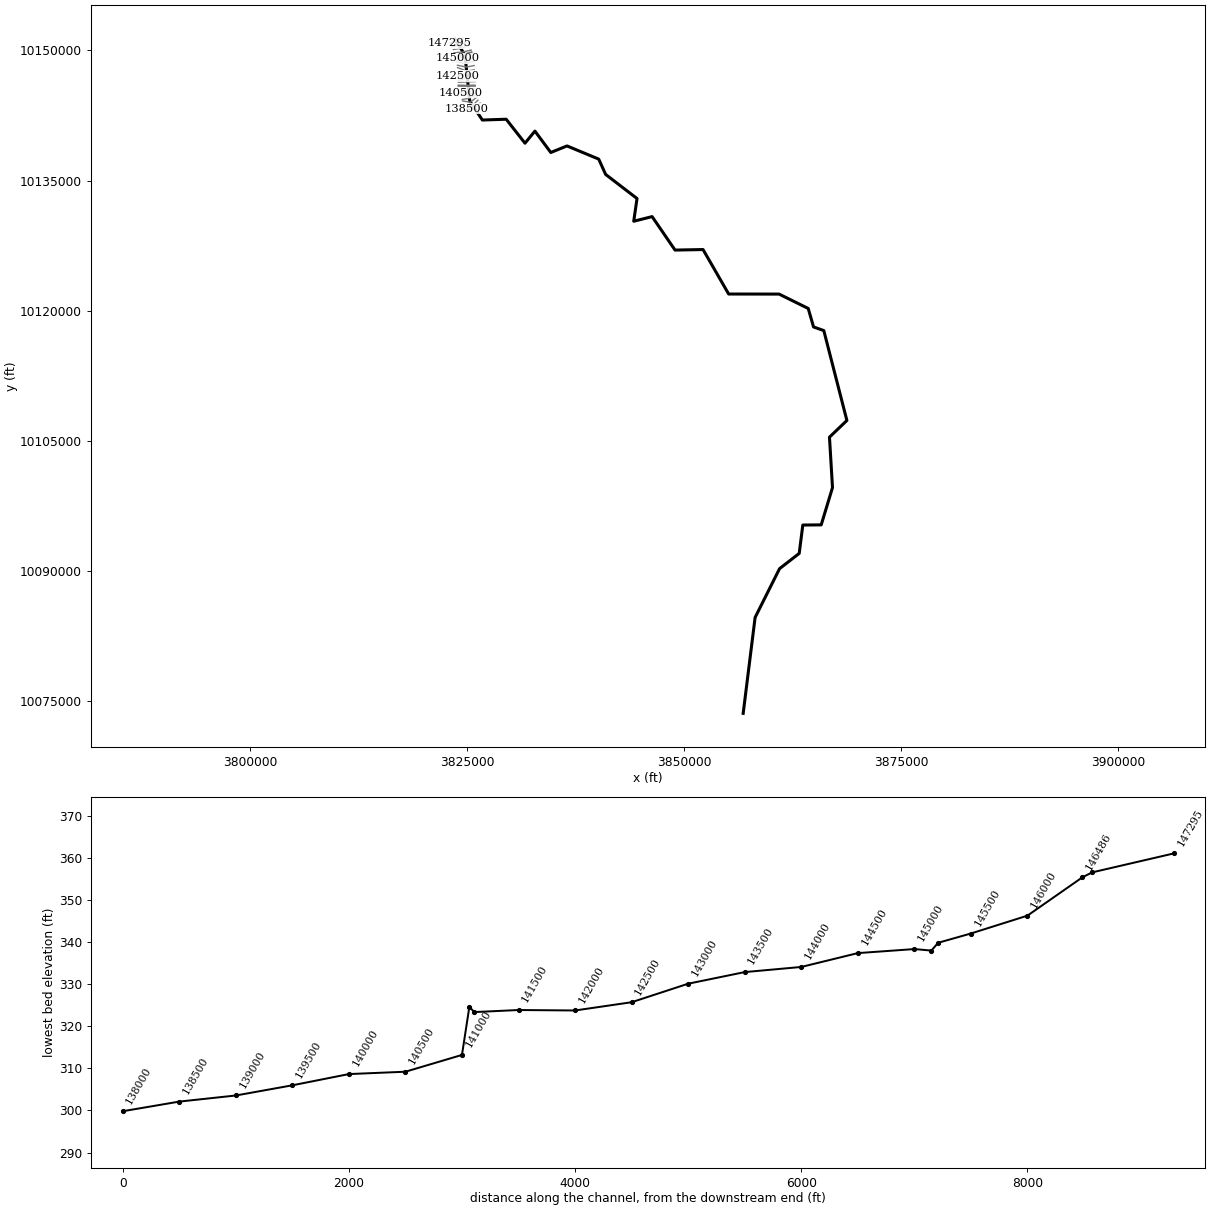
--- CRYSTAL CREEK.prj (project) ---

Proj Title=CRYSTAL CREEK Base Level Engineering
Current Plan=p01
Default Exp/Contr=0.3,0.1
English Units
Geom File=g01
Flow File=f01
Plan File=p01
Y Axis Title=Elevation
X Axis Title(PF)=Main Channel Distance
X Axis Title(XS)=Station
BEGIN DESCRIPTION:
CRYSTAL CREEK
END DESCRIPTION:
DSS Export Rating Curves= 0
DSS Export Rating Curve Sorted= 0
DSS Export Volume Flow Curves= 0
DXF OffsetX= 0
DXF OffsetY= 0
DXF ScaleX= 1
DXF ScaleY= 10

--- CRYSTAL CREEK.p01 (plan) ---

Plan Title=Multiple Run
Short Identifier=Multiple
Geom File=g01
Flow File=f01
Subcritical Flow
K Sum by GR= 0
Std Step Tol= 0.01
Critical Tol= 0.01
Num of Std Step Trials= 20
Max Error Tol= 0.3
Flow Tol Ratio= 0.001
Split Flow NTrial= 30
Split Flow Tol= 0.02
Split Flow Ratio= 0.02
Log Output Level= 0
Friction Slope Method= 1
Unsteady Friction Slope Method= 2
Unsteady Bridges Friction Slope Method= 1
Parabolic Critical Depth
Global Vel Dist=  1 , 1 , 1
Global Log Level= 0
CheckData=True
Encroach Param= -1, 0, 0, 0
BEGIN DESCRIPTION:
Multiple Run
END DESCRIPTION:

--- CRYSTAL CREEK.f01 (steady flow) ---

Flow Title=Multiple
Number of Profiles=7
Profile Names=10-year,25-year,50-year,1pct_min,100-year,1pct_plu,500-year
River Rch & RM= CRYSTAL CREEK,Reach-1,147295
     818    1097    1325     525    1584    4784    2261
River Rch & RM= CRYSTAL CREEK,Reach-1,140500
    1189    1623    1983     793    2396    7236    3494
River Rch & RM= CRYSTAL CREEK,Reach-1,132172
    1565    2164    2666    1074    3244    9796    4799
River Rch & RM= CRYSTAL CREEK,Reach-1,126991
    1714    2369    2916    1173    3544   10701    5229
River Rch & RM= CRYSTAL CREEK,Reach-1,118000
    2363    3299    4087    1653    4993   15078    7447
River Rch & RM= CRYSTAL CREEK,Reach-1,110500
    2457    3431    4252    1720    5193   15683    7743
River Rch & RM= CRYSTAL CREEK,Reach-1,107859
    2903    4073    5065    2054    6203   18733    9300
River Rch & RM= CRYSTAL CREEK,Reach-1,101500
    3048    4280    5324    2160    6522   19695    9782
River Rch & RM= CRYSTAL CREEK,Reach-1,97979
    3605    5079    6333    2574    7774   23476   11703
River Rch & RM= CRYSTAL CREEK,Reach-1,94500
    3684    5183    6456    2621    7914   23901   11885
River Rch & RM= CRYSTAL CREEK,Reach-1,85500
    4081    5742    7153    2903    8766   26474   13154
River Rch & RM= CRYSTAL CREEK,Reach-1,78142
    4059    5700    7092    2874    8680   26212   12989
River Rch & RM= CRYSTAL CREEK,Reach-1,73500
    4391    6174    7688    3117    9415   28432   14103
River Rch & RM= CRYSTAL CREEK,Reach-1,65242
    4374    6145    7646    3098    9357   28257   13997
River Rch & RM= CRYSTAL CREEK,Reach-1,62390
    4782    6731    8386    3401   10272   31022   15397
River Rch & RM= CRYSTAL CREEK,Reach-1,58500
    4903    6903    8603    3490   10540   31831   15804
River Rch & RM= CRYSTAL CREEK,Reach-1,54985
    4919    6922    8624    3497   10562   31896   15823
River Rch & RM= CRYSTAL CREEK,Reach-1,51500
    5008    7048    8781    3561   10753   32474   16108
River Rch & RM= CRYSTAL CREEK,Reach-1,47218
    5107    7187    8954    3631   10965   33112   16422
River Rch & RM= CRYSTAL CREEK,Reach-1,37000
    5101    7177    8939    3624   10944   33049   16383
River Rch & RM= CRYSTAL CREEK,Reach-1,35872
    5143    7237    9015    3655   11036   33330   16523
River Rch & RM= CRYSTAL CREEK,Reach-1,34500
    6470    9162   11464    4666   14092   42558   21265
River Rch & RM= CRYSTAL CREEK,Reach-1,28000
    6472    9156   11448    4656   14061   42464   21185
River Rch & RM= CRYSTAL CREEK,Reach-1,21023
    6510    9209   11515    4683   14144   42713   21310
River Rch & RM= CRYSTAL CREEK,Reach-1,20500
    7149   10137   12696    5172   15619   47167   23600
River Rch & RM= CRYSTAL CREEK,Reach-1,15876
    7207   10218   12797    5213   15742   47539   23782
River Rch & RM= CRYSTAL CREEK,Reach-1,11000
    7246   10270   12858    5236   15811   47749   23871
River Rch & RM= CRYSTAL CREEK,Reach-1,10000
    7555   10719   13431    5472   16527   49909   24984
Boundary for River Rch & Prof#=CRYSTAL CREEK,Reach-1,1
Up Type=0
Dn Type=3
Dn Slope=0.005
Boundary for River Rch & Prof#=CRYSTAL CREEK,Reach-1,2
Up Type=0
Dn Type=3
Dn Slope=0.005
Boundary for River Rch & Prof#=CRYSTAL CREEK,Reach-1,3
Up Type=0
Dn Type=3
Dn Slope=0.005
Boundary for River Rch & Prof#=CRYSTAL CREEK,Reach-1,4
Up Type=0
Dn Type=3
Dn Slope=0.005
Boundary for River Rch & Prof#=CRYSTAL CREEK,Reach-1,5
Up Type=0
Dn Type=3
Dn Slope=0.005
Boundary for River Rch & Prof#=CRYSTAL CREEK,Reach-1,6
Up Type=0
Dn Type=3
Dn Slope=0.005
Boundary for River Rch & Prof#=CRYSTAL CREEK,Reach-1,7
Up Type=0
Dn Type=3
Dn Slope=0.005

--- CRYSTAL CREEK.f02 (steady flow) ---

Flow Title=Orig_BLE_Flow
Program Version=4.10
Number of Profiles= 7
Profile Names=10-year,25-year,50-year,1pct_min,100-year,1pct_plu,500-year
River Rch & RM=CRYSTAL CREEK,Reach-1         ,147295
     818    1097    1325     525    1584    4784    2261
River Rch & RM=CRYSTAL CREEK,Reach-1         ,140500
    1189    1623    1983     793    2396    7236    3494
River Rch & RM=CRYSTAL CREEK,Reach-1         ,132660
    1565    2164    2666    1074    3244    9796    4799
River Rch & RM=CRYSTAL CREEK,Reach-1         ,132172
    1565    2164    2666    1074    3244    9796    4799
River Rch & RM=CRYSTAL CREEK,Reach-1         ,126991
    1714    2369    2916    1173    3544   10701    5229
River Rch & RM=CRYSTAL CREEK,Reach-1         ,118000
    2363    3299    4087    1653    4993   15078    7447
River Rch & RM=CRYSTAL CREEK,Reach-1         ,110500
    2457    3431    4252    1720    5193   15683    7743
River Rch & RM=CRYSTAL CREEK,Reach-1         ,110000
    2903    4073    5065    2054    6203   18733    9300
River Rch & RM=CRYSTAL CREEK,Reach-1         ,109387
    2903    4073    5065    2054    6203   18733    9300
River Rch & RM=CRYSTAL CREEK,Reach-1         ,108500
    2903    4073    5065    2054    6203   18733    9300
River Rch & RM=CRYSTAL CREEK,Reach-1         ,107859
    2903    4073    5065    2054    6203   18733    9300
River Rch & RM=CRYSTAL CREEK,Reach-1         ,102979
    3048    4280    5324    2160    6522   19695    9782
River Rch & RM=CRYSTAL CREEK,Reach-1         ,102500
    3048    4280    5324    2160    6522   19695    9782
River Rch & RM=CRYSTAL CREEK,Reach-1         ,102000
    3048    4280    5324    2160    6522   19695    9782
River Rch & RM=CRYSTAL CREEK,Reach-1         ,101500
    3048    4280    5324    2160    6522   19695    9782
River Rch & RM=CRYSTAL CREEK,Reach-1         ,101000
    3605    5079    6333    2574    7774   23476   11703
River Rch & RM=CRYSTAL CREEK,Reach-1         ,100515
    3605    5079    6333    2574    7774   23476   11703
River Rch & RM=CRYSTAL CREEK,Reach-1         ,99500
    3605    5079    6333    2574    7774   23476   11703
River Rch & RM=CRYSTAL CREEK,Reach-1         ,99000
    3605    5079    6333    2574    7774   23476   11703
River Rch & RM=CRYSTAL CREEK,Reach-1         ,98472
    3605    5079    6333    2574    7774   23476   11703
River Rch & RM=CRYSTAL CREEK,Reach-1         ,97979
    3605    5079    6333    2574    7774   23476   11703
River Rch & RM=CRYSTAL CREEK,Reach-1         ,94500
    3684    5183    6456    2621    7914   23901   11885
River Rch & RM=CRYSTAL CREEK,Reach-1         ,87512
    4081    5742    7153    2903    8766   26474   13154
River Rch & RM=CRYSTAL CREEK,Reach-1         ,87051
    4081    5742    7153    2903    8766   26474   13154
River Rch & RM=CRYSTAL CREEK,Reach-1         ,86500
    4081    5742    7153    2903    8766   26474   13154
River Rch & RM=CRYSTAL CREEK,Reach-1         ,86000
    4081    5742    7153    2903    8766   26474   13154
River Rch & RM=CRYSTAL CREEK,Reach-1         ,85500
    4081    5742    7153    2903    8766   26474   13154
River Rch & RM=CRYSTAL CREEK,Reach-1         ,78142
    4059    5700    7092    2874    8680   26212   12989
River Rch & RM=CRYSTAL CREEK,Reach-1         ,76606
    4391    6174    7688    3117    9415   28432   14103
River Rch & RM=CRYSTAL CREEK,Reach-1         ,76040
    4391    6174    7688    3117    9415   28432   14103
River Rch & RM=CRYSTAL CREEK,Reach-1         ,75500
    4391    6174    7688    3117    9415   28432   14103
River Rch & RM=CRYSTAL CREEK,Reach-1         ,75000
    4391    6174    7688    3117    9415   28432   14103
River Rch & RM=CRYSTAL CREEK,Reach-1         ,74231
    4391    6174    7688    3117    9415   28432   14103
River Rch & RM=CRYSTAL CREEK,Reach-1         ,74000
    4391    6174    7688    3117    9415   28432   14103
River Rch & RM=CRYSTAL CREEK,Reach-1         ,73500
    4391    6174    7688    3117    9415   28432   14103
River Rch & RM=CRYSTAL CREEK,Reach-1         ,65242
    4374    6145    7646    3098    9357   28257   13997
River Rch & RM=CRYSTAL CREEK,Reach-1         ,64500
    4782    6731    8386    3401   10272   31022   15397
River Rch & RM=CRYSTAL CREEK,Reach-1         ,64000
    4782    6731    8386    3401   10272   31022   15397
River Rch & RM=CRYSTAL CREEK,Reach-1         ,63500
    4782    6731    8386    3401   10272   31022   15397
River Rch & RM=CRYSTAL CREEK,Reach-1         ,63000
    4782    6731    8386    3401   10272   31022   15397
River Rch & RM=CRYSTAL CREEK,Reach-1         ,62390
    4782    6731    8386    3401   10272   31022   15397
River Rch & RM=CRYSTAL CREEK,Reach-1         ,58500
    4903    6903    8603    3490   10540   31831   15804
River Rch & RM=CRYSTAL CREEK,Reach-1         ,54985
    4919    6922    8624    3497   10562   31896   15823
River Rch & RM=CRYSTAL CREEK,Reach-1         ,51500
    5008    7048    8781    3561   10753   32474   16108
River Rch & RM=CRYSTAL CREEK,Reach-1         ,47218
    5107    7187    8954    3631   10965   33112   16422
River Rch & RM=CRYSTAL CREEK,Reach-1         ,37000
    5101    7177    8939    3624   10944   33049   16383
River Rch & RM=CRYSTAL CREEK,Reach-1         ,35872
    5143    7237    9015    3655   11036   33330   16523
River Rch & RM=CRYSTAL CREEK,Reach-1         ,35639
    6470    9162   11464    4666   14092   42558   21265
River Rch & RM=CRYSTAL CREEK,Reach-1         ,35386
    6470    9162   11464    4666   14092   42558   21265
River Rch & RM=CRYSTAL CREEK,Reach-1         ,35025
    6470    9162   11464    4666   14092   42558   21265
River Rch & RM=CRYSTAL CREEK,Reach-1         ,34500
    6470    9162   11464    4666   14092   42558   21265
River Rch & RM=CRYSTAL CREEK,Reach-1         ,28000
    6472    9156   11448    4656   14061   42464   21185
River Rch & RM=CRYSTAL CREEK,Reach-1         ,21023
    6510    9209   11515    4683   14144   42713   21310
River Rch & RM=CRYSTAL CREEK,Reach-1         ,20500
    7149   10137   12696    5172   15619   47167   23600
River Rch & RM=CRYSTAL CREEK,Reach-1         ,15876
    7207   10218   12797    5213   15742   47539   23782
River Rch & RM=CRYSTAL CREEK,Reach-1         ,11000
    7246   10270   12858    5236   15811   47749   23871
River Rch & RM=CRYSTAL CREEK,Reach-1         ,10000
    7555   10719   13431    5472   16527   49909   24984
Boundary for River Rch & Prof#=CRYSTAL CREEK,Reach-1         , 1
Up Type= 0
Dn Type= 3
Dn Slope=0.007
Boundary for River Rch & Prof#=CRYSTAL CREEK,Reach-1         , 2
Up Type= 0
Dn Type= 3
Dn Slope=0.007
Boundary for River Rch & Prof#=CRYSTAL CREEK,Reach-1         , 3
Up Type= 0
Dn Type= 3
Dn Slope=0.007
Boundary for River Rch & Prof#=CRYSTAL CREEK,Reach-1         , 4
Up Type= 0
Dn Type= 3
Dn Slope=0.007
Boundary for River Rch & Prof#=CRYSTAL CREEK,Reach-1         , 5
Up Type= 0
Dn Type= 3
Dn Slope=0.007
Boundary for River Rch & Prof#=CRYSTAL CREEK,Reach-1         , 6
Up Type= 0
Dn Type= 3
Dn Slope=0.007
Boundary for River Rch & Prof#=CRYSTAL CREEK,Reach-1         , 7
Up Type= 0
Dn Type= 3
Dn Slope=0.007
DSS Import GetInterval= 0
DSS Import GetPeak= 0
DSS Import FillOption= 0

--- CRYSTAL CREEK.g01 (geometry) ---

Geom Title=Existing Conditions
Program Version=4.10

River Reach=CRYSTAL CREEK   ,Reach-1
Reach XY= 30
      3823608.24     10151306.86      3824757.37     10149442.66
      3825299.65     10144159.36      3826756.89     10141978.86
      3829502.44     10142071.69      3831668.03     10139306.83
        3832812.     10140701.77      3834640.81     10138235.87
      3836510.42     10138991.69      3840163.13     10137471.61
      3840959.57     10135705.56      3844575.16     10132928.39
      3844196.35     10130306.37      3846314.12     10130840.71
        3848955.     10126980.86      3852182.94     10127041.61
      3855132.79      10121912.8      3860945.49     10121904.29
      3864300.35     10120245.62       3864915.3     10118113.96
      3866095.72     10117696.19      3868756.53     10107329.19
      3866748.98     10105402.82      3867098.09     10099585.86
       3865796.3     10095287.67      3863677.12     10095266.65
      3863261.85     10091996.64      3860998.24     10090237.84
      3858180.32     10084606.02      3856806.04     10073546.92

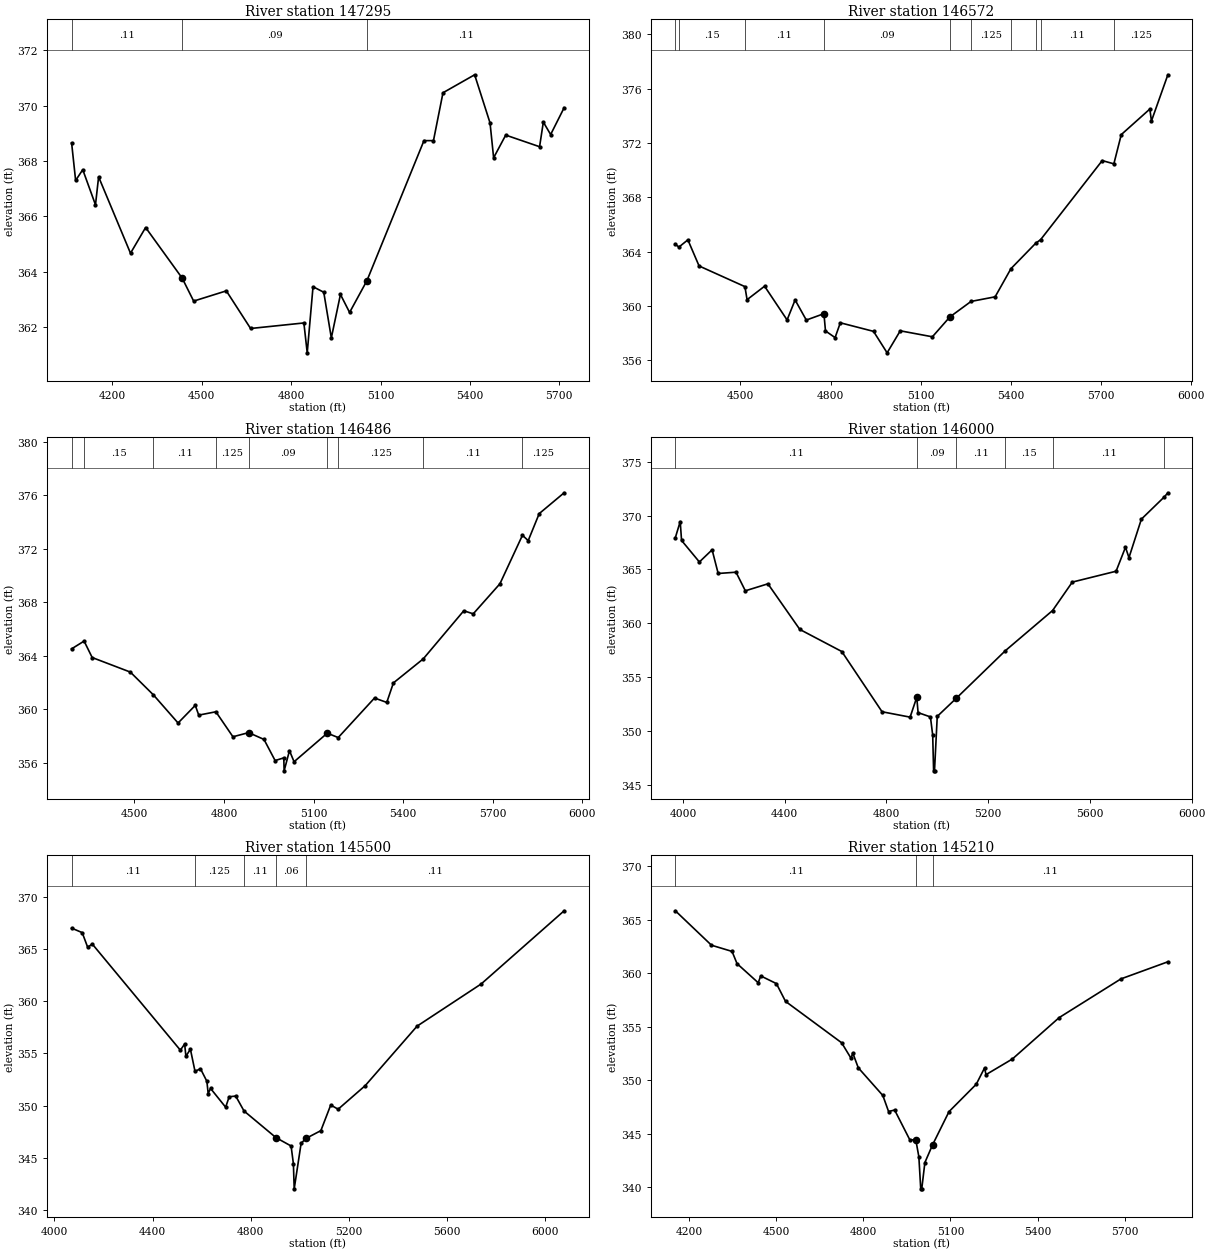
Type RM Length L Ch R = 1 ,147295  ,723,723,723
BEGIN DESCRIPTION:
CRYSTAL CREEK 289.0
END DESCRIPTION:
XS GIS Cut Line= 3
      3824553.07     10151401.52      3823672.12     10151083.78
      3822991.51     10150861.45
#Sta/Elev= 30
  4063.5  368.66    4077   367.3  4100.9  367.69  4143.6  366.42  4154.1  367.43
  4261.1  364.67  4311.8   365.6  4434.5  363.77    4473  362.94  4582.6  363.31
    4664  361.95  4842.8  362.15    4854  361.07  4873.5  363.46  4909.5  363.26
  4934.9  361.61  4965.5  363.18  4996.2  362.53  5054.4  363.68  5245.7  368.74
  5277.6  368.74  5309.5  370.47  5415.7  371.12  5467.4  369.38  5479.4  368.12
    5520  368.94  5633.6  368.52  5646.2  369.41  5670.7  368.96    5716  369.93
#Mann= 3 , 0 , 0
  4063.5     .11       0  4434.5     .09       0  5054.4     .11       0
Bank Sta=4434.5,5054.4
XS Rating Curve= 0 ,0
Exp/Cntr=0.3,0.1

Type RM Length L Ch R = 1 ,146572  ,86,86,86
BEGIN DESCRIPTION:
CRYSTAL CREEK 288.0
END DESCRIPTION:
XS GIS Cut Line= 3
      3824830.67     10151009.59      3824148.55     10150788.66
      3823271.56     10150498.67
#Sta/Elev= 30
    4283  364.54    4295  364.34  4324.8  364.87  4362.1  362.95  4514.8  361.43
    4522  360.47  4580.3  361.46  4655.3  358.98    4682  360.45  4719.3  358.97
    4778  359.44  4783.2  358.17  4815.2  357.68  4832.6  358.77  4943.2  358.14
  4988.5  356.56  5032.3  358.18  5139.3  357.74  5197.5   359.2    5268  360.34
  5348.3  360.68    5401  362.75  5483.9  364.63  5499.7  364.88  5705.1   370.7
  5743.8  370.46  5768.5  372.61  5863.7  374.49    5869  373.61  5923.7  377.01
#Mann= 10 ,-1 , 0
    4283    .125       0    4295     .15       0  4514.8     .11       0
    4778     .09       0  5197.5     .11       0    5268    .125       0
    5401     .11       0  5483.9    .125       0  5499.7     .11       0
  5743.8    .125       0
Bank Sta=4778,5197.5
XS Rating Curve= 0 ,0
Exp/Cntr=0.3,0.1

Type RM Length L Ch R = 1 ,146486  ,486,486,486
BEGIN DESCRIPTION:
CRYSTAL CREEK 287.0
END DESCRIPTION:
XS GIS Cut Line= 3
      3824851.69     10150936.24      3824175.91     10150716.86
      3823285.76     10150418.89
#Sta/Elev= 30
  4289.5  364.52  4331.3   365.1  4358.4  363.87  4486.2  362.78  4563.6  361.07
    4646  358.97  4703.6  360.29  4715.2  359.56  4772.6  359.81  4829.7  357.94
  4882.3  358.25  4933.7  357.74  4970.9  356.16    5000  356.36  5001.1  355.39
    5019   356.9  5034.4  356.07  5145.6  358.21  5182.2  357.88  5303.8  360.84
  5344.8  360.51    5367  361.97    5467  363.77  5602.7  367.37  5634.3  367.14
  5723.7  369.39  5799.1  373.02  5818.4  372.62  5855.2  374.64  5938.7   376.2
#Mann= 9 ,-1 , 0
  4289.5    .125       0  4331.3     .15       0  4563.6     .11       0
  4772.6    .125       0  4882.3     .09       0  5145.6     .11       0
  5182.2    .125       0    5467     .11       0  5799.1    .125       0
Bank Sta=4882.3,5145.6
XS Rating Curve= 0 ,0
Exp/Cntr=0.3,0.1

Type RM Length L Ch R = 1 ,146000  ,500,500,500
BEGIN DESCRIPTION:
CRYSTAL CREEK 286.0
END DESCRIPTION:
XS GIS Cut Line= 3
       3825287.4     10150593.49       3824312.1     10150261.35
      3823416.73      10150120.4
#Sta/Elev= 30
  3969.7  367.94  3988.9  369.45  3994.2  367.69  4064.3  365.69  4114.3  366.82
  4138.2  364.62  4208.4  364.74    4245  363.01  4333.8  363.66  4459.2  359.42
  4624.2  357.37  4782.6  351.77  4892.9  351.27    4919  353.11  4924.3  351.69
  4972.8  351.29  4981.7   349.6  4985.3  346.28  4988.8  346.28  4999.6  351.34
  5075.2  353.04  5267.2  357.44  5453.2  361.18  5530.7  363.82  5702.8  364.83
  5739.8  367.06  5753.4  366.09  5802.3  369.67    5893  371.75  5906.4  372.12
#Mann= 6 ,-1 , 0
  3969.7     .11       0    4919     .09       0  5075.2     .11       0
  5267.2     .15       0  5453.2     .11       0    5893    .125       0
Bank Sta=4919,5075.2
XS Rating Curve= 0 ,0
Exp/Cntr=0.3,0.1

Type RM Length L Ch R = 1 ,145500  ,290,290,290
BEGIN DESCRIPTION:
CRYSTAL CREEK 285.0
END DESCRIPTION:
XS GIS Cut Line= 3
      3825469.92     10150050.03      3824563.75     10149841.26
      3823491.68     10149725.56
#Sta/Elev= 30
  4070.1  366.99  4113.3  366.56  4135.6  365.16  4154.3  365.47  4513.5  355.31
    4531   355.9  4536.1  354.73  4554.5   355.4  4573.2  353.29  4595.6  353.53
  4621.7  352.33  4626.9  351.16  4636.6  351.65  4698.2  349.85  4712.5  350.85
  4739.2  350.92  4773.1  349.49  4903.4  346.94    4965  346.14  4974.4  344.45
  4977.7  342.04  5005.9   346.4  5026.1  346.87  5086.4  347.61  5126.6  350.06
  5156.8  349.66  5267.4  351.92  5478.7  357.61  5740.2  361.65  6078.3  368.65
#Mann= 5 ,-1 , 0
  4070.1     .11       0  4573.2    .125       0  4773.1     .11       0
  4903.4     .06       0  5026.1     .11       0
Bank Sta=4903.4,5026.1
XS Rating Curve= 0 ,0
Exp/Cntr=0.3,0.1

Type RM Length L Ch R = 1 ,145210  ,59,59,59
BEGIN DESCRIPTION:
Mapping XS 576f1f03
END DESCRIPTION:
XS GIS Cut Line= 3
      3825521.41     10149842.42      3824736.69     10149604.57
      3823892.46     10149362.93
#Sta/Elev= 30
  4151.3  365.83  4275.9  362.61  4346.9  362.03    4364  360.89  4437.1   359.1
  4445.7  359.74  4499.8  359.02  4531.2  357.36  4724.6  353.49  4757.5  352.02
  4762.8  352.55    4782  351.15  4866.7  348.56  4886.5  347.06  4907.4   347.2
  4959.6  344.42  4980.5  344.39  4990.9  342.83  4997.4  339.83  5000.9  339.83
  5011.7  342.29  5038.1  343.94  5094.9  347.05  5188.8  349.61  5217.3  351.13
  5222.5  350.51  5313.3  351.97  5474.6  355.84  5687.6  359.46  5849.4  361.06
#Mann= 3 , 0 , 0
  4151.3     .11       0  4980.5     .06       0  5038.1     .11       0
Bank Sta=4980.5,5038.1
XS Rating Curve= 0 ,0
Exp/Cntr=0.3,0.1

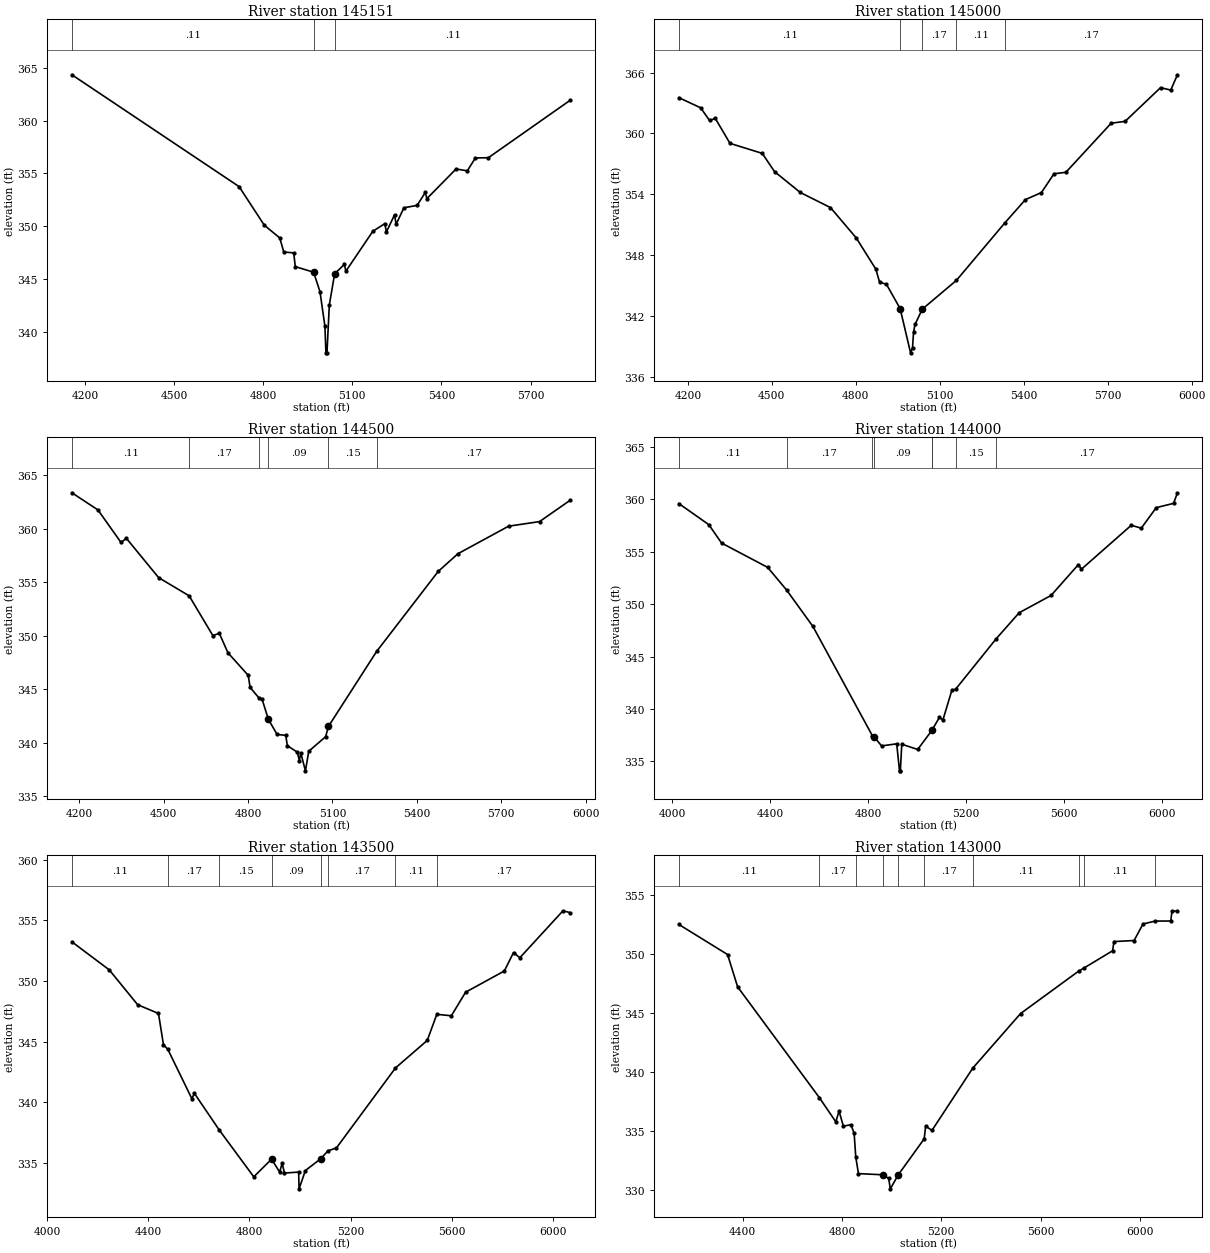
Type RM Length L Ch R = 1 ,145151  ,151,151,151
BEGIN DESCRIPTION:
Mapping XS b6c69840
END DESCRIPTION:
XS GIS Cut Line= 3
      3825530.14     10149772.99      3824759.26     10149550.75
      3823921.77     10149294.13
#Sta/Elev= 30
  4156.1  364.36  4718.9  353.75  4803.7  350.09  4855.8  348.88  4869.2  347.55
  4902.8  347.46    4908  346.16  4969.7  345.63  4991.2  343.78  5007.7  340.52
  5011.2  337.98  5014.7  337.98  5022.6  342.52  5040.5  345.48  5073.2  346.37
  5078.4  345.73    5169  349.51  5209.5  350.24  5214.7  349.44  5242.2  351.08
  5247.4  350.17  5273.6  351.74  5318.2  351.97  5345.7   353.2  5350.9  352.61
  5449.2  355.42  5487.2  355.25  5514.2  356.47  5557.9  356.49  5834.3  361.96
#Mann= 3 , 0 , 0
  4156.1     .11       0  4969.7     .09       0  5040.5     .11       0
Bank Sta=4969.7,5040.5
XS Rating Curve= 0 ,0
Exp/Cntr=0.3,0.1

Type RM Length L Ch R = 1 ,145000  ,500,500,500
BEGIN DESCRIPTION:
CRYSTAL CREEK 284.0
END DESCRIPTION:
XS GIS Cut Line= 3
      3825552.12      10149647.3      3824758.21     10149398.44
      3823861.11     10149087.99
#Sta/Elev= 30
    4168  363.53  4245.8  362.53  4277.5  361.28  4298.2  361.48  4350.6  359.02
  4465.9  358.03  4509.7  356.23  4601.8  354.17  4709.6  352.68  4801.3   349.7
  4871.8   346.6  4885.1  345.31  4909.5  345.11  4958.5  342.71  4995.8  338.34
  5002.8  338.84  5006.5   340.4  5011.7  341.14  5037.6  342.65  5159.5  345.49
  5333.6   351.2  5406.3  353.47  5463.3  354.16  5508.3  356.02  5550.6  356.16
  5712.6  361.01  5762.3  361.19    5889  364.52  5925.4  364.28  5949.3  365.79
#Mann= 5 ,-1 , 0
    4168     .11       0  4958.5     .09       0  5037.6     .17       0
  5159.5     .11       0  5333.6     .17       0
Bank Sta=4958.5,5037.6
XS Rating Curve= 0 ,0
Exp/Cntr=0.3,0.1

Type RM Length L Ch R = 1 ,144500  ,500,500,500
BEGIN DESCRIPTION:
CRYSTAL CREEK 283.0
END DESCRIPTION:
XS GIS Cut Line= 3
      3825617.89     10149111.08       3824813.5     10148922.47
      3823868.09      10148892.1
#Sta/Elev= 30
  4173.8  363.34  4266.3  361.74  4348.4   358.7  4367.4  359.09    4482  355.42
  4590.5  353.72  4674.8  350.01  4697.7  350.22  4728.5   348.4  4800.4   346.3
  4807.3  345.17  4838.1   344.2  4849.7  344.07  4872.3  342.18  4903.1  340.78
  4933.9  340.69  4939.7  339.73    4975  339.12  4982.2  338.34  4987.3  339.05
  5003.9  337.38  5015.7  339.21  5075.7  340.57  5085.7  341.53    5257  348.53
  5475.9     356  5545.9  357.65    5726  360.22  5836.1  360.65  5945.9  362.66
#Mann= 6 ,-1 , 0
  4173.8     .11       0  4590.5     .17       0  4838.1     .15       0
  4872.3     .09       0  5085.7     .15       0    5257     .17       0
Bank Sta=4872.3,5085.7
XS Rating Curve= 0 ,0
Exp/Cntr=0.3,0.1

Type RM Length L Ch R = 1 ,144000  ,500,500,500
BEGIN DESCRIPTION:
CRYSTAL CREEK 282.0
END DESCRIPTION:
XS GIS Cut Line= 3
      3825756.16     10148748.88      3824817.57     10148497.38
      3823772.73     10148688.09
#Sta/Elev= 30
  4028.3   359.6  4150.3  357.59  4202.5  355.83  4390.5  353.51  4467.6  351.35
  4575.1  347.87  4817.4  337.45  4823.7  337.36  4855.2  336.47  4916.9  336.67
  4928.3  334.09  4931.8  334.09  4937.6  336.63  5002.4  336.13  5060.7  337.96
  5062.7  338.05  5091.2  339.19  5105.3  338.94    5142  341.79  5156.8  341.87
  5323.2  346.71  5416.5  349.18  5546.6  350.83  5658.2  353.78  5670.6  353.34
  5873.9  357.53  5914.6  357.25  5975.6  359.21  6046.3  359.62  6062.1  360.63
#Mann= 8 ,-1 , 0
  4028.3     .11       0  4467.6     .17       0  4817.4     .15       0
  4823.7     .09       0  5060.7     .15       0  5062.7     .17       0
  5156.8     .15       0  5323.2     .17       0
Bank Sta=4823.7,5060.7
XS Rating Curve= 0 ,0
Exp/Cntr=0.3,0.1

Type RM Length L Ch R = 1 ,143500  ,500,500,500
BEGIN DESCRIPTION:
CRYSTAL CREEK 281.0
END DESCRIPTION:
XS GIS Cut Line= 3
       3825812.6     10148262.77      3824928.56     10148084.71
        3823882.     10148301.64
#Sta/Elev= 30
  4098.2  353.22  4245.9  350.91  4358.1  348.04  4440.4  347.32  4460.1  344.74
  4477.2  344.37  4572.3   340.3  4582.5  340.73  4681.2   337.7  4817.1  333.86
  4887.6  335.32  4919.1  334.25  4929.3  334.97  4938.4  334.17  4994.4  334.25
  4996.1  332.87  5021.1  334.38  5082.4  335.36  5110.1     336  5143.7  336.24
  5377.2  342.83  5502.8   345.1  5540.6  347.25    5598  347.13  5654.3  349.07
  5807.5  350.82  5843.8  352.34  5868.8  351.91  6039.3  355.78  6068.8  355.62
#Mann= 8 ,-1 , 0
  4098.2     .11       0  4477.2     .17       0  4681.2     .15       0
  4887.6     .09       0  5082.4     .15       0  5110.1     .17       0
  5377.2     .11       0  5540.6     .17       0
Bank Sta=4887.6,5082.4
XS Rating Curve= 0 ,0
Exp/Cntr=0.3,0.1

Type RM Length L Ch R = 1 ,143000  ,500,500,500
BEGIN DESCRIPTION:
CRYSTAL CREEK 280.0
END DESCRIPTION:
XS GIS Cut Line= 3
      3825821.22     10147772.31      3824976.29     10147630.78
      3823894.13     10148024.05
#Sta/Elev= 30
  4143.3  352.52  4339.4  349.97  4379.9  347.23  4709.1  337.84  4775.4  335.79
  4788.5   336.7  4805.8  335.42  4836.2  335.55  4849.2  334.82  4855.7  332.81
  4866.6   331.4  4965.5   331.3  4988.3  330.99  4994.9  330.11 5027.35331.3124
  5131.4  334.35  5137.3  335.43  5162.6  335.06  5327.3  340.35  5519.7  344.97
  5753.2  348.56  5775.2  348.83  5890.3  350.29  5895.6  351.07  5976.8  351.16
  6012.7  352.56  6062.4  352.81  6124.4  352.81  6129.8  353.68  6151.4  353.64
#Mann= 10 ,-1 , 0
  4143.3     .11       0  4709.1     .17       0  4855.7     .15       0
  4965.5     .09       0 5027.35     .15       0  5131.4     .17       0
  5327.3     .11       0  5753.2     .17       0  5775.2     .11       0
  6062.4     .17       0
Bank Sta=4965.5,5027.35
XS Rating Curve= 0 ,0
Exp/Cntr=0.3,0.1

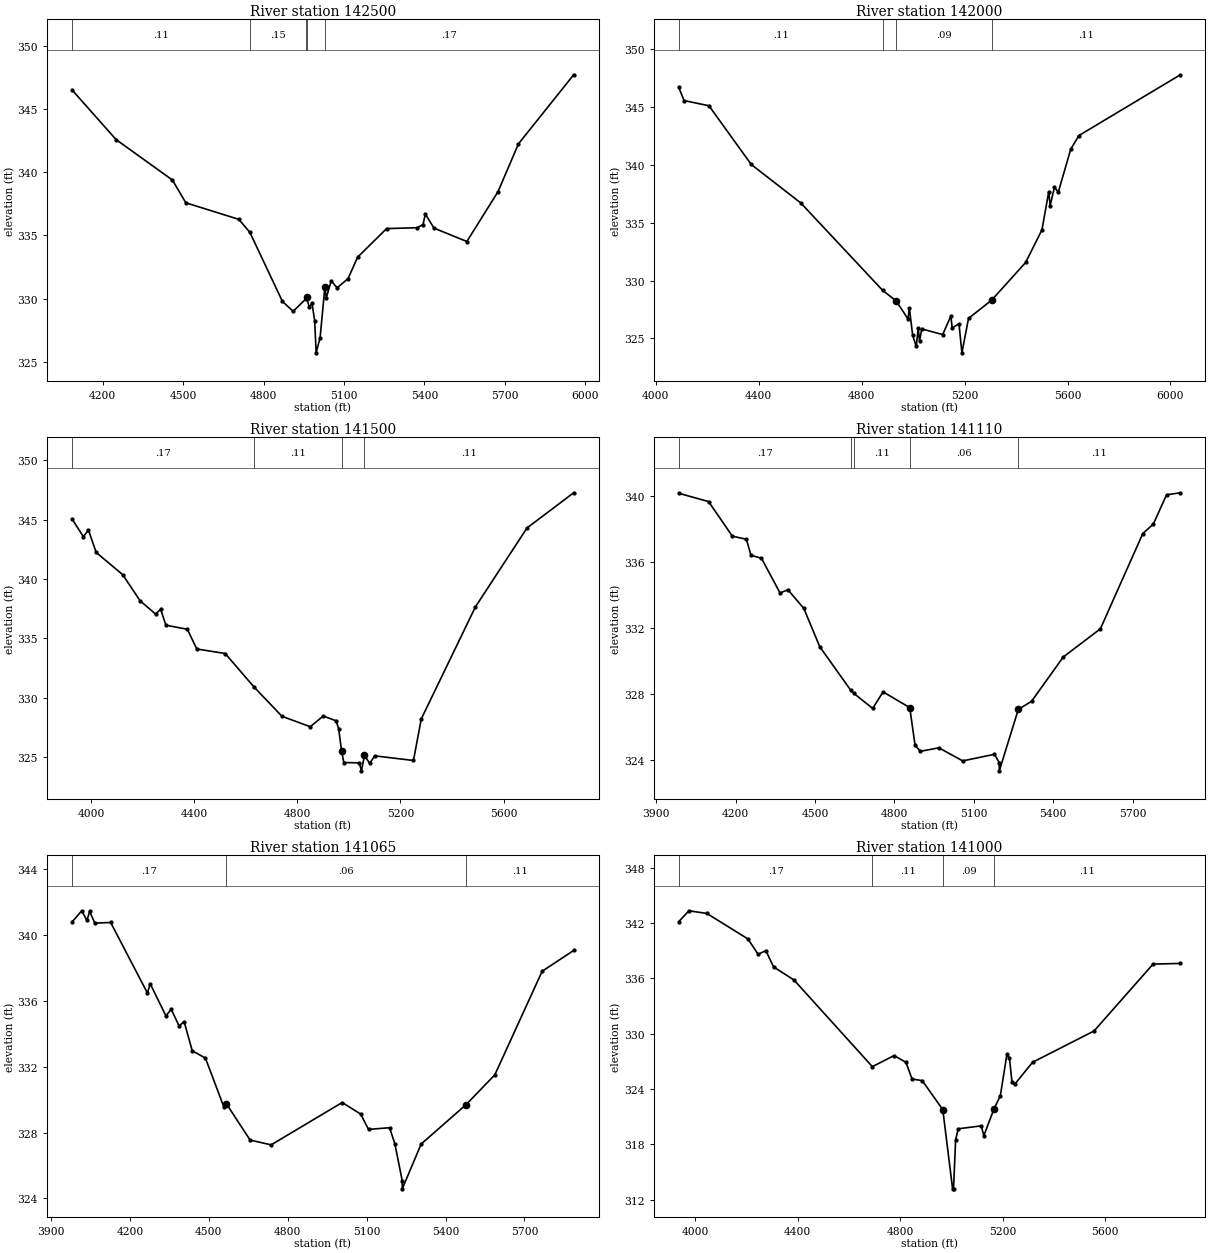
Type RM Length L Ch R = 1 ,142500  ,500,500,500
BEGIN DESCRIPTION:
CRYSTAL CREEK 279.0
END DESCRIPTION:
XS GIS Cut Line= 3
      3825751.79     10147342.62      3824838.22     10147303.76
       3823912.2     10147065.02
#Sta/Elev= 30
  4085.6  346.49  4249.7  342.57  4459.9  339.37  4509.9  337.57  4707.7  336.26
  4748.8  335.23  4870.3  329.77  4910.3  328.99  4957.8  329.98  4960.3  330.12
  4970.3  329.31  4980.4  329.63  4990.4  328.26  4995.9  325.71  5010.7  326.92
  5028.5  330.91  5033.7  330.05    5052   331.4  5074.3  330.85    5115  331.58
  5150.5  333.27  5258.6  335.53  5372.2   335.6  5394.6  335.85  5403.1  336.68
  5435.3  335.57    5558  334.51  5674.2  338.45  5750.4  342.23  5956.3  347.69
#Mann= 5 ,-1 , 0
  4085.6     .11       0  4748.8     .15       0  4957.8     .17       0
  4960.3     .09       0  5028.5     .17       0
Bank Sta=4960.3,5028.5
XS Rating Curve= 0 ,0
Exp/Cntr=0.3,0.1

Type RM Length L Ch R = 1 ,142000  ,500,500,500
BEGIN DESCRIPTION:
CRYSTAL CREEK 278.0
END DESCRIPTION:
XS GIS Cut Line= 3
      3825842.98     10147030.13      3824949.37     10146852.98
      3823963.58     10146526.64
#Sta/Elev= 30
    4089  346.72  4109.7  345.58  4206.4  345.13  4370.8  340.05  4563.2  336.72
  4881.7  329.15    4934  328.24  4980.1  326.68  4985.2  327.64  4998.2  325.26
  5012.1   324.3  5019.7  325.87    5025  324.77  5033.2  325.82  5114.8  325.33
  5146.5  326.93  5151.8  325.91  5178.2  326.26  5189.5  323.75  5215.2  326.73
  5305.1  328.31  5437.2  331.57  5500.6  334.39  5527.1   337.7  5532.3  336.49
  5549.3  338.08    5564  337.65  5612.6  341.38  5644.2  342.55  6038.4  347.81
#Mann= 4 ,-1 , 0
    4089     .11       0  4881.7     .17       0    4934     .09       0
  5305.1     .11       0
Bank Sta=4934,5305.1
XS Rating Curve= 0 ,0
Exp/Cntr=0.3,0.1

Type RM Length L Ch R = 1 ,141500  ,390,390,390
BEGIN DESCRIPTION:
CRYSTAL CREEK 277.0
END DESCRIPTION:
XS GIS Cut Line= 3
      3825951.49      10146413.8      3824878.24     10146371.07
      3824007.05     10146331.34
#Sta/Elev= 30
  3925.9  345.05  3969.6  343.56  3989.6  344.11  4019.6  342.23  4122.5  340.36
  4189.7  338.17  4249.8  337.05  4269.8  337.45  4289.8  336.11  4373.2  335.77
  4409.9  334.11    4520  333.73  4630.8  330.94  4740.2  328.45  4850.3  327.57
  4900.3  328.47  4950.4  328.07  4960.4  327.39  4971.6325.5368  4980.4  324.56
  5040.4  324.53  5048.7  323.86  5060.5  325.17  5080.5  324.49  5100.5  325.12
  5250.6  324.73  5280.7  328.22  5490.9  337.65  5691.1  344.29  5872.1  347.25
#Mann= 4 ,-1 , 0
  3925.9     .17       0  4630.8     .11       0  4971.6     .06       0
  5060.5     .11       0
Bank Sta=4971.6,5060.5
XS Rating Curve= 0 ,0
Exp/Cntr=0.3,0.1

Type RM Length L Ch R = 1 ,141110  ,45,45,45
BEGIN DESCRIPTION:
Mapping XS a8c04ae3
END DESCRIPTION:
XS GIS Cut Line= 3
      3825890.41     10146000.93      3824870.46      10145981.4
      3823995.91     10146000.93
#Sta/Elev= 30
  3985.2  340.14  4097.8  339.64  4187.8  337.55  4240.9  337.36  4257.8   336.4
  4297.8  336.21  4367.8  334.12  4397.8  334.31  4457.8  333.18  4517.9  330.87
  4634.9  328.24  4646.7  328.05  4717.9  327.14  4757.1  328.14  4857.9  327.19
  4877.9  324.93  4897.9  324.55  4967.9  324.76    5058  323.97    5178  324.37
    5196  323.87  5196.2  323.37    5268  327.08    5318  327.57    5438  330.25
  5578.1  331.95  5738.1   337.7  5778.1  338.28  5828.1  340.05  5880.1  340.17
#Mann= 5 ,-1 , 0
  3985.2     .17       0  4634.9     .15       0  4646.7     .11       0
  4857.9     .06       0    5268     .11       0
Bank Sta=4857.9,5268
XS Rating Curve= 0 ,0
Exp/Cntr=0.3,0.1

Type RM Length L Ch R = 1 ,141065  ,65,65,65
BEGIN DESCRIPTION:
Mapping XS 33ce5f02
END DESCRIPTION:
XS GIS Cut Line= 3
      3825894.55     10145953.03      3824896.99      10145936.9
      3823988.18     10145950.34
#Sta/Elev= 30
  3980.3  340.78    4017  341.46    4037  340.87    4047  341.42    4067  340.71
    4127  340.75    4267  336.46    4277  337.04  4337.1  335.08  4357.1  335.48
  4387.1  334.47  4406.3  334.73  4437.1  332.96  4487.1  332.52  4557.1  329.56
  4567.1  329.74  4657.1  327.54  4737.1  327.25  5007.1  329.82  5077.1  329.12
  5107.1  328.19  5187.2  328.29  5207.2  327.32  5235.2  325.08  5235.4  324.58
  5307.2   327.3  5477.2  329.68  5587.2   331.5  5767.2  337.79  5886.9  339.05
#Mann= 3 , 0 , 0
  3980.3     .17       0  4567.1     .06       0  5477.2     .11       0
Bank Sta=4567.1,5477.2
XS Rating Curve= 0 ,0
Exp/Cntr=0.3,0.1

Type RM Length L Ch R = 1 ,141000  ,500,500,500
BEGIN DESCRIPTION:
CRYSTAL CREEK 276.0
END DESCRIPTION:
XS GIS Cut Line= 3
      3825937.52     10145896.56       3824873.8       10145872.
      3823981.51     10145891.16
#Sta/Elev= 30
    3936  342.16  3975.7  343.34  4045.7  343.05  4205.7  340.29  4245.8  338.62
  4275.8  339.02  4305.8  337.26  4385.7  335.83  4691.2  326.44  4775.9  327.64
  4822.3  326.91  4845.9   325.1  4885.9  324.92  4965.9  321.78  5004.2  313.19
  5007.8  313.19    5016   318.5    5026   319.7    5116  320.02    5126  318.94
    5166  321.89  5190.3  323.26    5216  327.77    5226  327.34    5236  324.73
    5246  324.51    5316  326.91  5556.1  330.31  5786.1  337.56  5892.5  337.63
#Mann= 4 ,-1 , 0
    3936     .17       0  4691.2     .11       0  4965.9     .09       0
    5166     .11       0
Bank Sta=4965.9,5166
XS Rating Curve= 0 ,0
Exp/Cntr=0.3,0.1

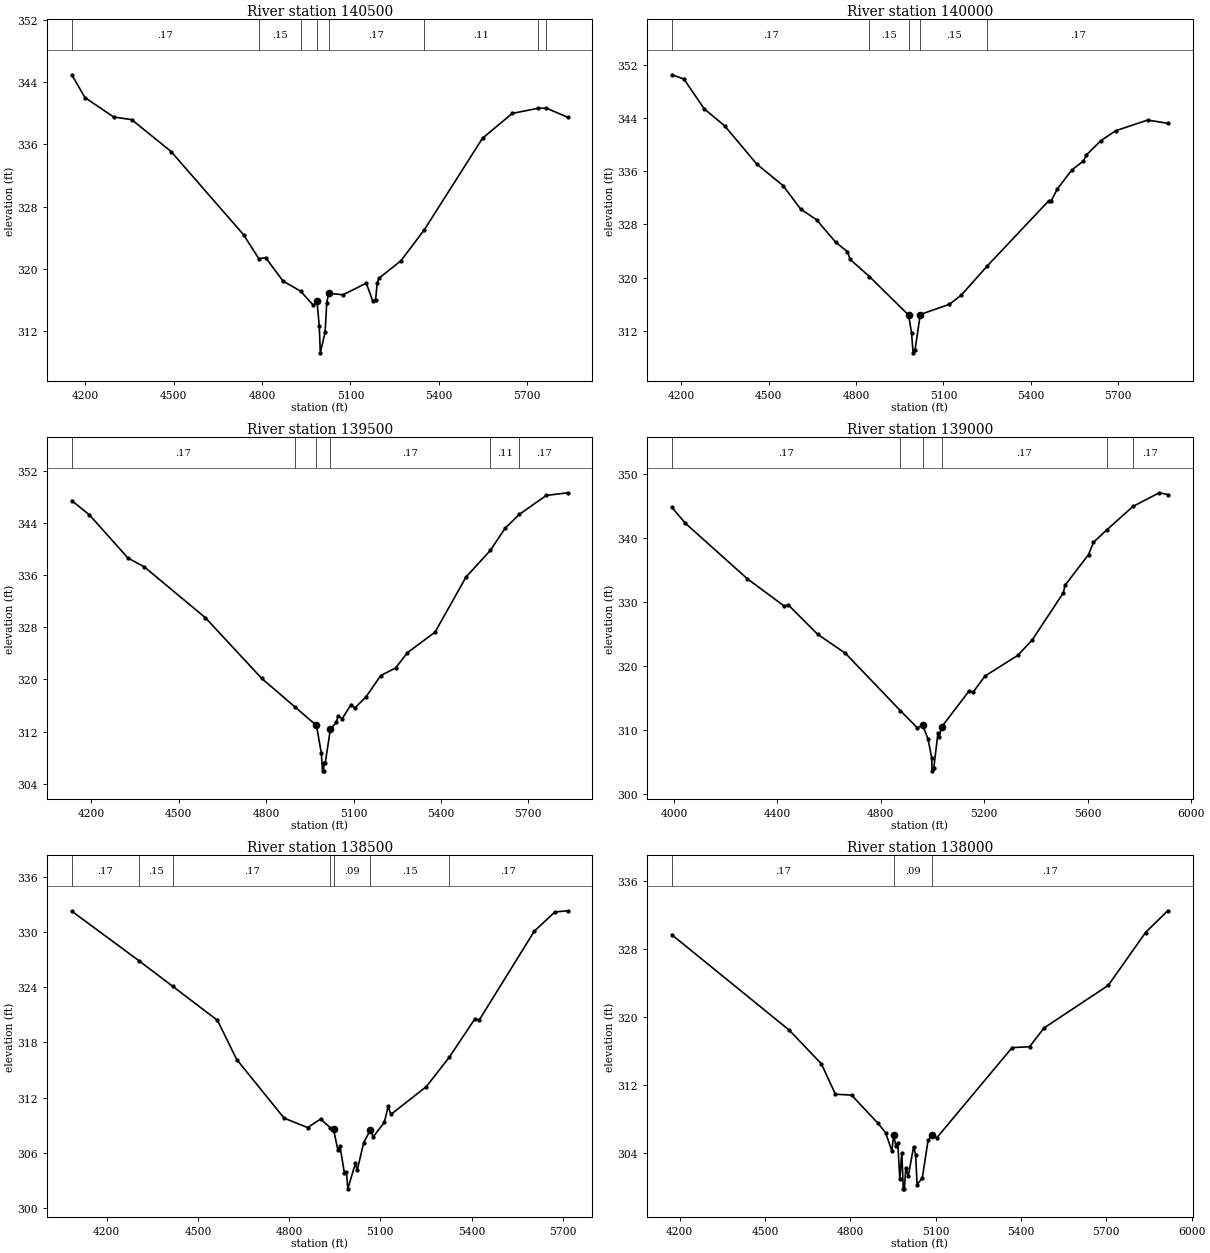
Type RM Length L Ch R = 1 ,140500  ,500,500,500
BEGIN DESCRIPTION:
CRYSTAL CREEK 275.0
END DESCRIPTION:
XS GIS Cut Line= 3
       3825816.2      10145606.4      3824992.32     10145412.47
      3824206.65      10145120.4
#Sta/Elev= 30
  4153.6  344.93  4198.4     342  4295.7  339.51  4357.4  339.16  4490.9  335.07
  4737.5  324.36    4789   321.3  4812.1  321.43    4871  318.43    4931  317.12
  4973.8  315.32  4986.7  315.81  4994.3  312.63  4997.9   309.2  5014.2  311.87
  5019.6  315.59  5026.1  316.86  5074.9  316.66  5154.1  318.15  5175.5  315.91
  5185.7  316.04    5191  318.13  5196.8  318.78  5271.4  321.02  5350.7  324.99
  5548.9  336.78    5650  339.97  5738.3  340.63  5765.9  340.64  5838.2  339.47
#Mann= 8 ,-1 , 0
  4153.6     .17       0    4789     .15       0    4931     .17       0
  4986.7     .09       0  5026.1     .17       0  5350.7     .11       0
  5738.3     .17       0  5765.9     .11       0
Bank Sta=4986.7,5026.1
XS Rating Curve= 0 ,0
Exp/Cntr=0.3,0.1

Type RM Length L Ch R = 1 ,140000  ,500,500,500
BEGIN DESCRIPTION:
CRYSTAL CREEK 274.0
END DESCRIPTION:
XS GIS Cut Line= 3
      3825999.15     10145020.57      3825168.25     10144962.75
      3824298.84     10144925.84
#Sta/Elev= 30
  4167.1  350.58  4208.5  349.95  4278.7  345.43  4348.8  342.87  4459.1   337.1
  4549.3  333.86  4609.5  330.33  4664.3  328.71  4729.8  325.33  4769.8  323.92
  4779.9  322.72  4845.7  320.15  4980.4  314.33  4990.4  311.67  4995.8  308.64
  5002.7  309.14  5020.4  314.42  5120.5  315.96  5161.5  317.35  5251.2  321.78
  5460.8  331.54  5470.8   331.6  5490.8  333.34  5540.9  336.22  5580.9  337.58
  5590.9  338.49    5641  340.65    5691  342.13  5801.1  343.75  5870.2  343.26
#Mann= 5 ,-1 , 0
  4167.1     .17       0  4845.7     .15       0  4980.4     .09       0
  5020.4     .15       0  5251.2     .17       0
Bank Sta=4980.4,5020.4
XS Rating Curve= 0 ,0
Exp/Cntr=0.3,0.1

Type RM Length L Ch R = 1 ,139500  ,500,500,500
BEGIN DESCRIPTION:
CRYSTAL CREEK 273.0
END DESCRIPTION:
XS GIS Cut Line= 3
      3826042.61     10144864.33      3825258.27     10144494.42
      3824436.72     10144343.49
#Sta/Elev= 30
  4132.8  347.44  4193.3  345.25    4326  338.61  4381.2  337.29  4591.4  329.47
    4785  320.15  4899.7  315.75  4972.8  312.93  4989.4  308.73  4993.6  305.97
  4997.4  305.97  4998.1  307.17  5002.8  307.17  5020.8   312.4  5041.1  313.39
  5046.2  314.34  5061.4     314  5091.9  316.15  5104.4  315.61  5142.8  317.31
  5193.6   320.6  5244.4  321.75  5285.1   324.1    5380  327.26  5486.2  335.71
  5569.8   339.8  5620.6  343.21  5669.4  345.33  5761.8  348.23  5835.3  348.64
#Mann= 6 ,-1 , 0
  4132.8     .17       0  4899.7     .15       0  4972.8     .09       0
  5020.8     .17       0  5569.8     .11       0  5669.4     .17       0
Bank Sta=4972.8,5020.8
XS Rating Curve= 0 ,0
Exp/Cntr=0.3,0.1

Type RM Length L Ch R = 1 ,139000  ,500,500,500
BEGIN DESCRIPTION:
CRYSTAL CREEK 272.0
END DESCRIPTION:
XS GIS Cut Line= 3
      3826168.49     10144651.67      3825372.53     10144032.54
      3824475.75      10144182.9
#Sta/Elev= 30
  3991.6  344.77  4043.1   342.3  4283.9  333.58  4426.8   329.3  4441.3  329.53
  4555.3  324.91    4663  321.93  4875.3  312.97  4940.8  310.29  4961.6   310.7
  4982.4  308.53  4996.9  305.53  4997.9  303.55  5004.9  304.05  5020.7  309.46
  5025.7  308.86  5035.2  310.42    5142  316.08  5156.8  315.85  5202.6  318.37
  5329.2   321.6  5384.6  323.98  5505.9   331.4  5511.7  332.54    5603  337.36
  5622.2  339.29  5674.5  341.26  5775.2   344.9  5876.8  347.03  5909.3  346.75
#Mann= 6 ,-1 , 0
  3991.6     .17       0  4875.3     .15       0  4961.6     .09       0
  5035.2     .17       0  5674.5     .11       0  5775.2     .17       0
Bank Sta=4961.6,5035.2
XS Rating Curve= 0 ,0
Exp/Cntr=0.3,0.1

Type RM Length L Ch R = 1 ,138500  ,500,500,500
BEGIN DESCRIPTION:
CRYSTAL CREEK 271.0
END DESCRIPTION:
XS GIS Cut Line= 3
      3826250.94     10144265.38      3825585.68     10143637.02
      3824971.65     10143267.77
#Sta/Elev= 30
  4084.9  332.25  4304.9  326.89  4416.4   324.1  4564.1   320.4  4627.6  316.14
  4783.4  309.78    4861  308.75  4903.5  309.68    4936  308.72    4946  308.57
  4960.2  306.34  4967.4  306.71  4981.6  303.86  4988.5  303.89  4993.1   302.1
  5018.1  304.88  5023.9  304.11  5045.3  307.11  5067.5  308.52  5076.4  307.74
  5113.3  309.32  5125.8  311.05  5134.7  310.18  5251.2  313.19  5326.2  316.36
  5410.5  320.52  5426.1  320.46  5606.7  330.08  5674.3  332.16  5716.5  332.29
#Mann= 7 ,-1 , 0
  4084.9     .17       0  4304.9     .15       0  4416.4     .17       0
    4936     .15       0    4946     .09       0  5067.5     .15       0
  5326.2     .17       0
Bank Sta=4946,5067.5
XS Rating Curve= 0 ,0
Exp/Cntr=0.3,0.1

Type RM Length L Ch R = 1 ,138000  ,500,500,500
BEGIN DESCRIPTION:
CRYSTAL CREEK 270.0
END DESCRIPTION:
XS GIS Cut Line= 3
      3826506.97     10143935.48      3825909.66     10143362.21
      3825011.18     10143184.95
#Sta/Elev= 30
  4172.1  329.73  4584.9   318.5  4697.8  314.54  4747.5  310.95  4804.1  310.85
  4895.9  307.57  4924.2  306.41  4945.6  304.27  4952.5  306.11  4959.8  304.89
  4966.7  305.26  4973.9  300.97  4980.8  304.07  4986.1  299.81  4990.1  299.81
    4995  302.32  5003.5  301.29  5022.2  304.75  5029.5  303.83  5034.6  300.32
  5052.8  301.07  5073.2  305.51  5085.9  306.14  5103.8  305.82  5368.8  316.44
  5429.9  316.54  5480.9  318.75  5706.8  323.77  5837.7  329.99  5915.8  332.55
#Mann= 3 , 0 , 0
  4172.1     .17       0  4952.5     .09       0  5085.9     .17       0
Bank Sta=4952.5,5085.9
XS Rating Curve= 0 ,0
Exp/Cntr=0.3,0.1