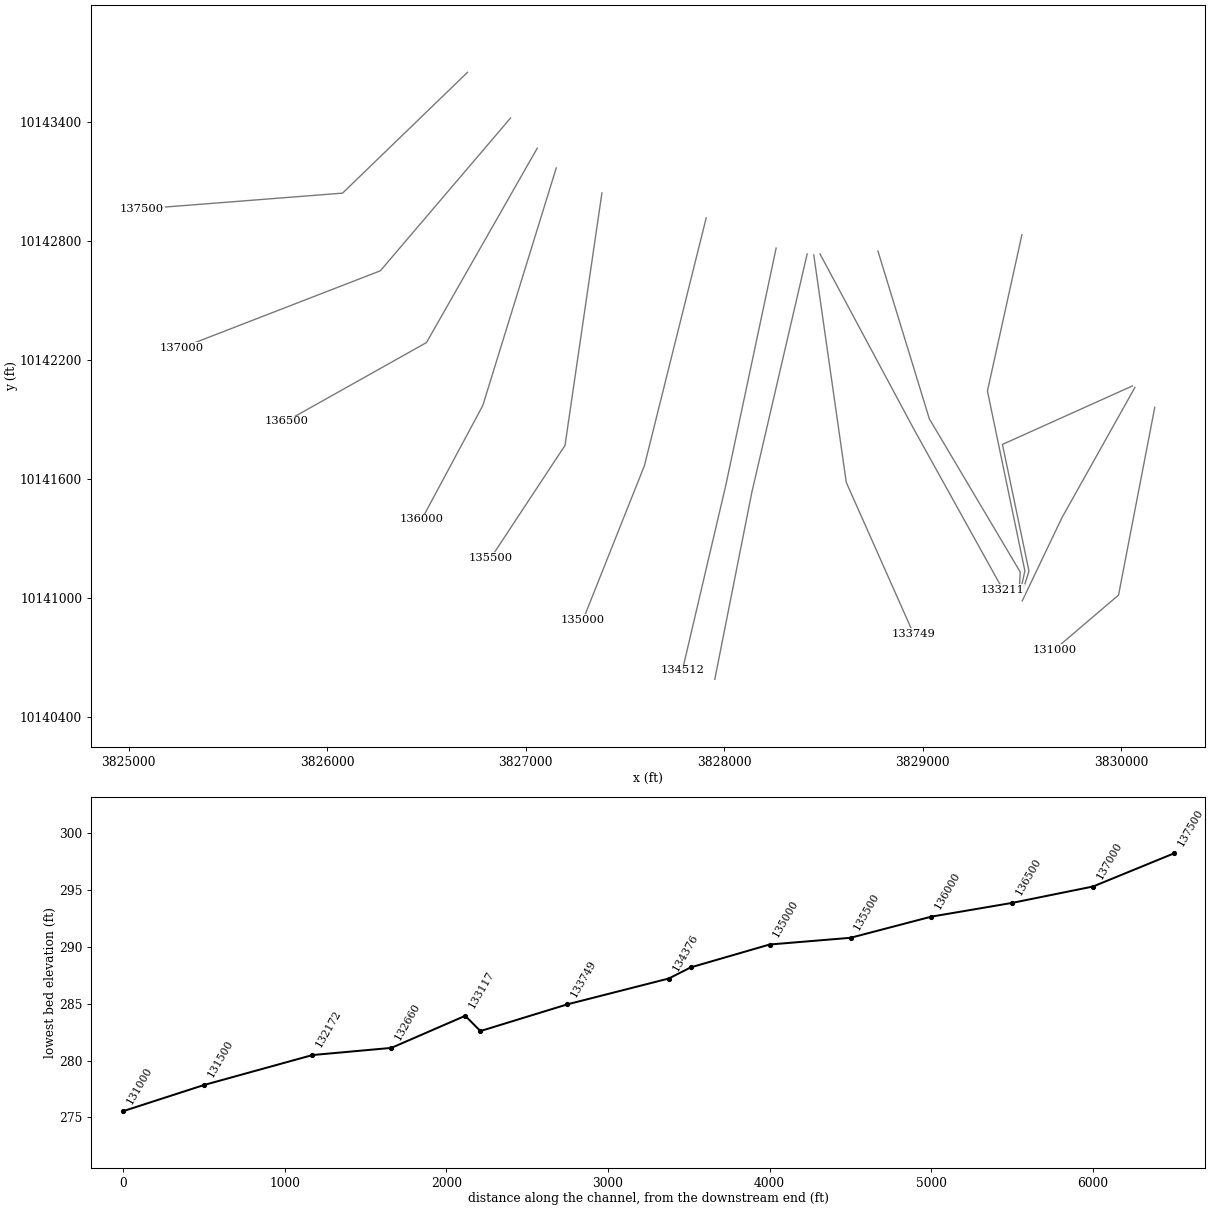
HEC-RAS study CRYSTAL CREEK.prj: CRYSTAL CREEK Base Level Engineering

--- CRYSTAL CREEK.g01 (geometry) --- (continued)

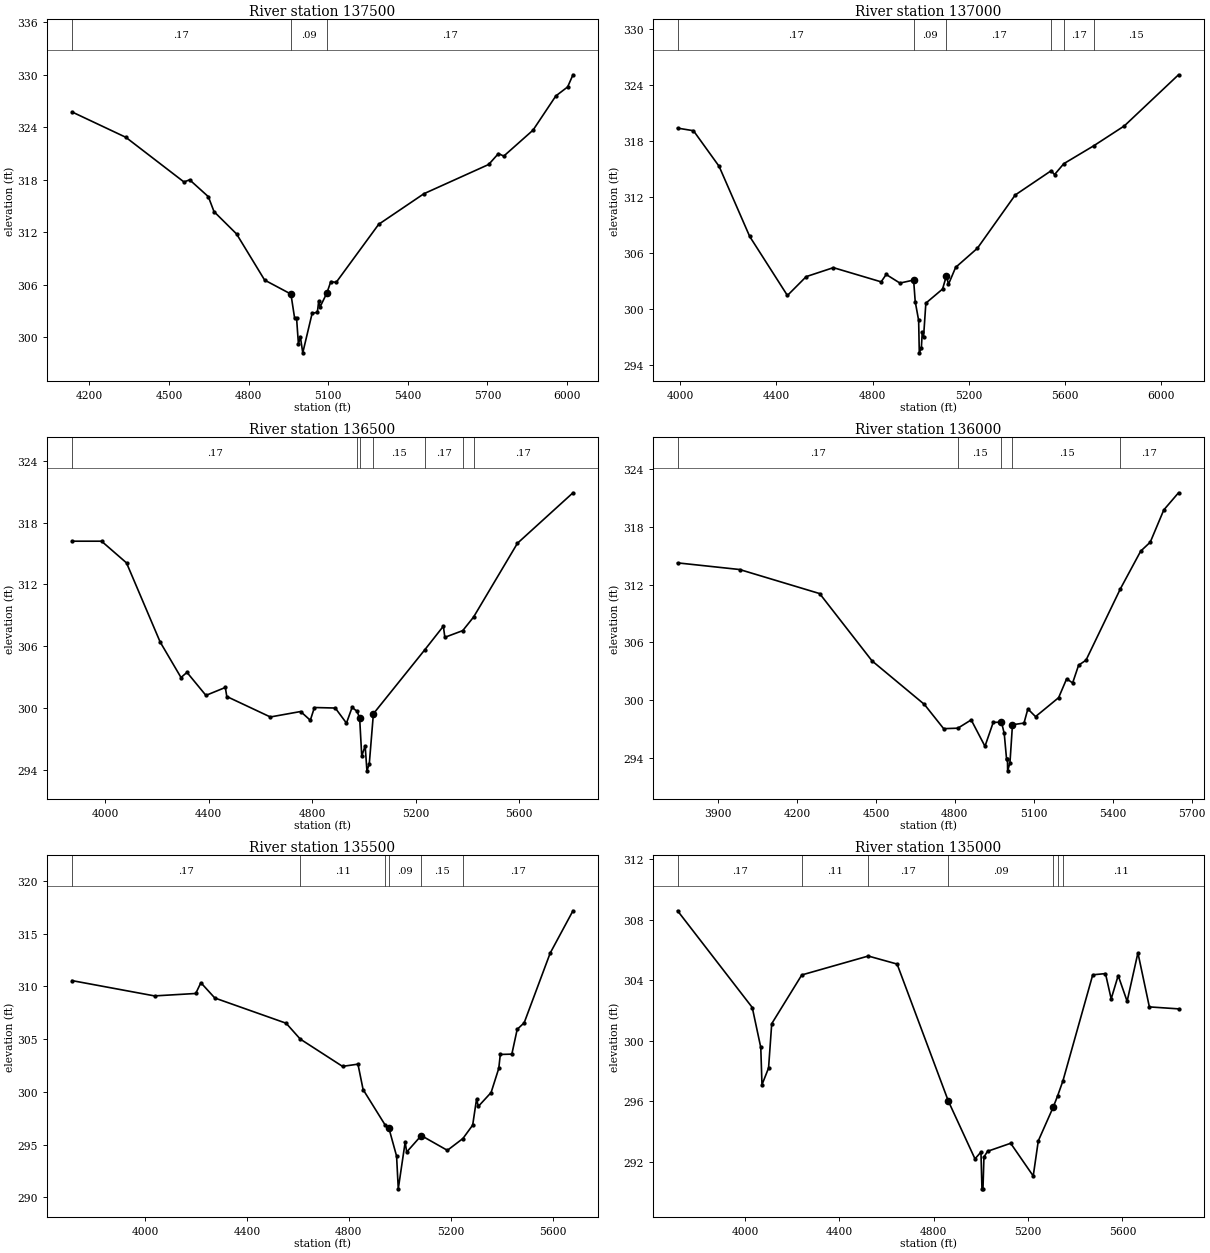
Type RM Length L Ch R = 1 ,137500  ,500,500,500
BEGIN DESCRIPTION:
CRYSTAL CREEK 269.0
END DESCRIPTION:
XS GIS Cut Line= 3
      3826706.62     10143649.01      3826077.58     10143040.28
      3825067.84     10142961.07
#Sta/Elev= 30
  4134.3  325.77  4337.1  322.87  4556.3  317.76  4577.6  318.01  4648.1  316.08
  4669.5  314.37  4754.4  311.82  4860.3  306.54  4959.4  304.94  4973.5  302.15
  4980.7  302.19  4987.7   299.2  4994.9  300.07    5004  298.22  5039.5  302.76
    5059  302.84    5064  304.13  5069.6  303.49    5095305.0717  5109.7  306.37
  5129.8  306.27  5290.2  312.92  5460.8  316.42  5704.7  319.76  5741.6  321.01
  5761.7  320.72    5872  323.69  5957.9   327.6  6002.4  328.63  6022.5  330.02
#Mann= 3 , 0 , 0
  4134.3     .17       0  4959.4     .09       0    5095     .17       0
Bank Sta=4959.4,5095
XS Rating Curve= 0 ,0
Exp/Cntr=0.3,0.1

Type RM Length L Ch R = 1 ,137000  ,500,500,500
BEGIN DESCRIPTION:
CRYSTAL CREEK 268.0
END DESCRIPTION:
XS GIS Cut Line= 3
      3826923.66     10143419.01       3826267.9     10142648.87
      3825267.86     10142261.07
#Sta/Elev= 30
  3988.5  319.37  4054.7  319.09  4161.3  315.28  4288.6  307.77  4445.5  301.45
  4523.7  303.47  4636.8  304.43  4835.5  302.91  4856.4   303.7  4913.5  302.78
  4970.6   303.1  4977.2   300.8  4991.5  298.78  4994.2  295.31  5002.7  295.81
  5006.6  297.56  5011.9  296.99  5021.5  300.63    5091  302.14  5107.3  303.58
  5115.5  302.64  5145.4  304.46    5236  306.51  5393.3  312.21    5543  314.81
  5556.7  314.39  5595.3  315.56  5720.1  317.48  5847.4  319.61  6072.6  325.08
#Mann= 6 ,-1 , 0
  3988.5     .17       0  4970.6     .09       0  5107.3     .17       0
    5543     .15       0  5595.3     .17       0  5720.1     .15       0
Bank Sta=4970.6,5107.3
XS Rating Curve= 0 ,0
Exp/Cntr=0.3,0.1

Type RM Length L Ch R = 1 ,136500  ,500,500,500
BEGIN DESCRIPTION:
CRYSTAL CREEK 267.0
END DESCRIPTION:
XS GIS Cut Line= 3
      3827058.22      10143267.1      3826500.02     10142287.01
      3825795.23     10141891.25
#Sta/Elev= 30
  3872.1  316.21  3986.2  316.21  4082.7   314.1  4212.8   306.4  4293.3  302.95
  4316.4  303.45  4389.6  301.21  4464.6  301.98  4470.3   301.1  4638.6  299.11
  4755.6  299.64  4793.1  298.79  4808.9  300.03  4889.6  299.98  4932.8  298.51
  4954.5  300.04    4974  299.66  4983.8  298.99  4991.9   295.3  5005.1  296.31
  5011.9  293.87    5021  294.54  5036.9  299.42  5235.7  305.65  5307.3  307.94
  5313.1  306.86  5382.2  307.51  5424.1  308.83  5593.7  316.01  5808.3  320.92
#Mann= 7 ,-1 , 0
  3872.1     .17       0    4974     .15       0  4983.8     .09       0
  5036.9     .15       0  5235.7     .17       0  5382.2     .15       0
  5424.1     .17       0
Bank Sta=4983.8,5036.9
XS Rating Curve= 0 ,0
Exp/Cntr=0.3,0.1

Type RM Length L Ch R = 1 ,136000  ,500,500,500
BEGIN DESCRIPTION:
CRYSTAL CREEK 266.0
END DESCRIPTION:
XS GIS Cut Line= 3
       3827153.7     10143167.29       3826783.7     10141969.43
      3826476.61     10141396.43
#Sta/Elev= 30
  3746.3  314.26  3982.1  313.57  4286.3  311.07  4485.4  304.08  4684.3  299.56
  4757.6  297.04  4811.5  297.09  4862.2  297.95  4914.6  295.21  4945.9  297.69
  4977.3  297.72  4987.8  296.54  4996.5  293.92    5000  293.92  5000.7  292.66
  5009.5  293.48  5019.1  297.45  5062.9  297.62  5077.6  299.09  5106.8  298.29
  5194.5  300.26    5225  302.22  5247.7  301.79  5270.4  303.63  5298.5  304.15
  5429.3  311.57  5506.4  315.48  5542.7  316.41  5594.2  319.76  5650.1  321.54
#Mann= 5 ,-1 , 0
  3746.3     .17       0  4811.5     .15       0  4977.3     .09       0
  5019.1     .15       0  5429.3     .17       0
Bank Sta=4977.3,5019.1
XS Rating Curve= 0 ,0
Exp/Cntr=0.3,0.1

Type RM Length L Ch R = 1 ,135500  ,500,500,500
BEGIN DESCRIPTION:
CRYSTAL CREEK 265.0
END DESCRIPTION:
XS GIS Cut Line= 3
      3827383.74     10143041.41      3827197.82     10141768.72
      3826823.85     10141201.15
#Sta/Elev= 30
  3713.8  310.54  4037.5  309.09  4199.2  309.32  4219.5  310.34  4274.2  308.89
    4554   306.5  4609.3     305  4775.3  302.41  4835.9  302.62  4856.1  300.21
  4942.6  296.85  4957.2  296.56  4987.5   293.9  4994.1   290.8  5021.1  295.22
  5027.2  294.29  5084.4  295.85  5186.8  294.45  5247.8  295.57  5286.1  296.84
  5301.2  299.29  5308.5  298.62  5358.4  299.93  5388.5  302.22  5394.5  303.54
  5439.8  303.57  5460.8  305.92  5488.2  306.54  5590.3  313.15  5679.7  317.16
#Mann= 6 ,-1 , 0
  3713.8     .17       0  4609.3     .11       0  4942.6     .15       0
  4957.2     .09       0  5084.4     .15       0  5247.8     .17       0
Bank Sta=4957.2,5084.4
XS Rating Curve= 0 ,0
Exp/Cntr=0.3,0.1

Type RM Length L Ch R = 1 ,135000  ,488,488,488
BEGIN DESCRIPTION:
CRYSTAL CREEK 264.0
END DESCRIPTION:
XS GIS Cut Line= 3
      3827908.91     10142915.53      3827597.85      10141667.1
      3827288.24     10140888.61
#Sta/Elev= 30
  3713.4  308.58  4030.2  302.19  4066.3  299.55  4071.4  297.09  4099.3  298.19
  4112.7  301.12  4240.2  304.34  4522.1  305.59  4644.4  305.06  4861.9     296
  4974.7  292.19    5000  292.64  5004.3  290.21  5008.6  290.21  5012.7  292.31
    5028  292.69    5126  293.22  5221.7  291.06  5243.2  293.38  5306.8  295.62
  5325.3  296.36  5347.6  297.34  5474.1  304.35  5528.1  304.43  5552.3  302.76
    5582   304.3  5619.9   302.6  5665.7   305.8  5714.2  302.23  5837.8   302.1
#Mann= 7 ,-1 , 0
  3713.4     .17       0  4240.2     .11       0  4522.1     .17       0
  4861.9     .09       0  5306.8     .11       0  5325.3     .17       0
  5347.6     .11       0
Bank Sta=4861.9,5306.8
XS Rating Curve= 0 ,0
Exp/Cntr=0.3,0.1

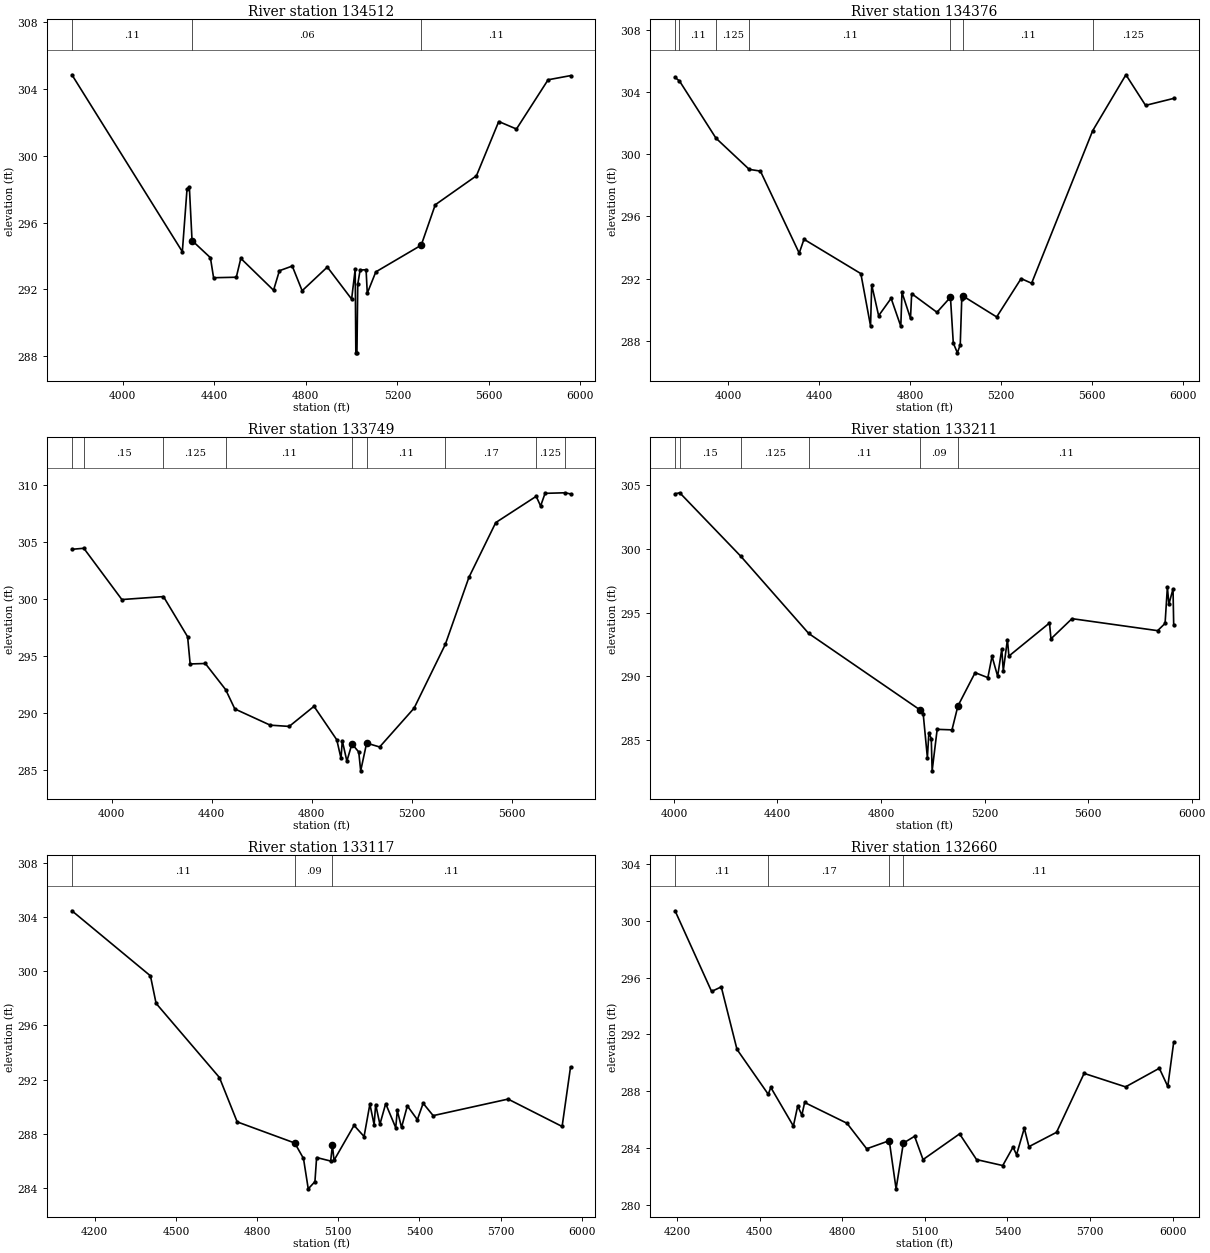
Type RM Length L Ch R = 1 ,134512  ,136,136,136
BEGIN DESCRIPTION:
CRYSTAL CREEK 263.0
END DESCRIPTION:
XS GIS Cut Line= 3
      3828261.06     10142763.29      3828007.38      10141567.2
      3827788.98     10140635.45
#Sta/Elev= 30
  3777.3  304.86    4260  294.26  4280.5  298.02  4290.7  298.13  4302.4  294.93
  4382.7   293.9  4396.6   292.7  4495.9  292.73  4515.6  293.86  4658.7  291.95
  4684.3  293.12  4740.5   293.4  4783.7  291.92  4893.8  293.34    5000  291.42
  5015.6  293.21  5018.4   288.2  5023.2   288.2  5026.8  292.31  5037.1  293.16
  5063.2  293.18  5068.4  291.77  5105.7  293.05  5304.2  294.65  5365.5  297.07
  5545.6  298.81  5643.1  302.06  5720.5  301.61  5858.8  304.56    5957  304.81
#Mann= 3 , 0 , 0
  3777.3     .11       0  4302.4     .06       0  5304.2     .11       0
Bank Sta=4302.4,5304.2
XS Rating Curve= 0 ,0
Exp/Cntr=0.3,0.1

Type RM Length L Ch R = 1 ,134376  ,627,627,627
BEGIN DESCRIPTION:
CRYSTAL CREEK 262.0
END DESCRIPTION:
XS GIS Cut Line= 3
       3828417.3     10142733.77      3828138.49     10141531.58
      3827952.02     10140589.66
#Sta/Elev= 30
  3765.9  304.95  3785.4  304.72  3945.9  301.04  4092.4  299.03  4141.5  298.92
  4312.2  293.64  4333.3  294.53  4583.5  292.32  4626.2  288.95  4631.3  291.59
  4661.8  289.61  4716.7  290.73  4759.3  288.93  4764.5  291.11    4802  289.44
  4807.1  291.03  4918.4  289.83  4977.8   290.8  4990.3  287.85  5008.3  287.22
  5020.9  287.74  5027.5  290.68  5032.6  290.88  5181.2  289.53  5288.8     292
  5334.9   291.7  5603.7  301.52  5749.9  305.12  5836.4  303.15  5960.2   303.6
#Mann= 7 ,-1 , 0
  3765.9    .125       0  3785.4     .11       0  3945.9    .125       0
  4092.4     .11       0  4977.8     .07       0  5032.6     .11       0
  5603.7    .125       0
Bank Sta=4977.8,5032.6
XS Rating Curve= 0 ,0
Exp/Cntr=0.3,0.1

Type RM Length L Ch R = 1 ,133749  ,538,538,538
BEGIN DESCRIPTION:
CRYSTAL CREEK 261.0
END DESCRIPTION:
XS GIS Cut Line= 3
      3828450.61     10142728.69      3828614.32     10141582.12
      3828952.79     10140819.78
#Sta/Elev= 30
  3841.8  304.35  3889.4  304.44  4041.4  299.95  4207.6  300.21  4304.1  296.69
  4314.2  294.31  4374.8  294.35  4456.1  292.06  4492.7  290.37  4634.1  288.95
  4709.9  288.84  4809.1   290.6    4900  287.67    4917  286.04  4922.1  287.59
  4940.4   285.8  4960.7  287.31  4987.8   286.6  4995.6  284.95  5019.3  287.38
  5071.3  287.04    5209  290.44  5333.8  296.03  5427.9  301.89  5535.2  306.69
  5696.8  308.99  5714.4  308.14  5732.2  309.25  5811.5   309.3  5834.1   309.2
#Mann= 9 ,-1 , 0
  3841.8    .125       0  3889.4     .15       0  4207.6    .125       0
  4456.1     .11       0  4960.7     .06       0  5019.3     .11       0
  5333.8     .17       0  5696.8    .125       0  5811.5     .11       0
Bank Sta=4960.7,5019.3
XS Rating Curve= 0 ,0
Exp/Cntr=0.3,0.1

Type RM Length L Ch R = 1 ,133211  ,94,94,94
BEGIN DESCRIPTION:
Mapping XS acd5d741
END DESCRIPTION:
XS GIS Cut Line= 3
      3828481.87     10142733.84      3828951.77     10141855.88
      3829403.09     10141041.94
#Sta/Elev= 30
  4004.2   304.3  4022.3  304.38    4259  299.39  4520.6  293.36  4948.7   287.4
  4962.8  287.09  4979.1  283.63  4984.8  285.58  4994.1  285.13  4997.4   282.6
  5016.9  285.85  5074.1  285.81    5097  287.68  5163.5  290.29  5212.7   289.9
  5228.8  291.57  5250.5  290.01  5266.5  292.14  5272.3  290.44  5288.3  292.88
    5294  291.59  5450.8  294.18  5456.5  292.94  5537.8  294.52  5868.6  293.58
  5897.4  294.15  5906.3     297  5912.1  295.65  5928.1  296.85  5930.7     294
#Mann= 6 ,-1 , 0
  4004.2    .125       0  4022.3     .15       0    4259    .125       0
  4520.6     .11       0  4948.7     .09       0    5097     .11       0
Bank Sta=4948.7,5097
XS Rating Curve= 0 ,0
Exp/Cntr=0.3,0.1

Type RM Length L Ch R = 1 ,133117  ,457,457,457
BEGIN DESCRIPTION:
CRYSTAL CREEK 260.0
END DESCRIPTION:
XS GIS Cut Line= 4
      3828773.64     10142748.53       3829032.5     10141902.86
        3829490.     10141131.13      3829487.23     10141069.94
#Sta/Elev= 30
  4115.6  304.45  4405.8  299.65  4426.7  297.62  4660.8  292.15  4726.3  288.88
  4939.1  287.32  4971.4  286.18    4989  283.94  5013.7  284.47  5019.9  286.25
  5071.8  285.99  5078.4  287.15  5084.2  286.04  5158.3  288.62  5195.3   287.8
  5216.8  290.19  5232.4  288.67  5238.2  290.16  5253.8   288.7  5275.2  290.22
  5312.3  288.45  5318.1  289.72  5333.7  288.47  5355.2  290.06  5392.2  289.04
  5413.6  290.25  5450.7  289.34  5727.5  290.56  5927.2  288.54  5958.4  292.94
#Mann= 3 , 0 , 0
  4115.6     .11       0  4939.1     .09       0  5078.4     .11       0
Bank Sta=4939.1,5078.4
XS Rating Curve= 0 ,0
Exp/Cntr=0.3,0.1

Type RM Length L Ch R = 1 ,132660  ,488,488,488
BEGIN DESCRIPTION:
CRYSTAL CREEK 259.0
END DESCRIPTION:
XS GIS Cut Line= 4
      3829498.82     10142830.65      3829325.18     10142042.86
      3829513.72     10141136.14      3829497.05     10141060.06
#Sta/Elev= 30
  4193.3   300.7    4326  295.02  4361.1  295.34  4418.2  290.94  4531.7  287.78
    4541  288.26    4623  285.54  4638.7  286.96  4653.7  286.31  4663.9   287.2
  4817.5  285.74  4889.2  283.94  4971.1  284.51  4995.9  281.12  5022.3  284.34
  5063.1  284.82  5093.8  283.18  5226.5  284.99  5288.1  283.18  5383.2  282.76
  5420.6  284.06  5433.3  283.52  5461.5  285.39  5478.3  284.09  5578.5   285.1
  5678.7  289.25  5829.2   288.3  5951.8  289.61  5982.5  288.33    6004  291.45
#Mann= 4 ,-1 , 0
  4193.3     .11       0  4531.7     .17       0  4971.1     .09       0
  5022.3     .11       0
Bank Sta=4971.1,5022.3
XS Rating Curve= 0 ,0
Exp/Cntr=0.3,0.1

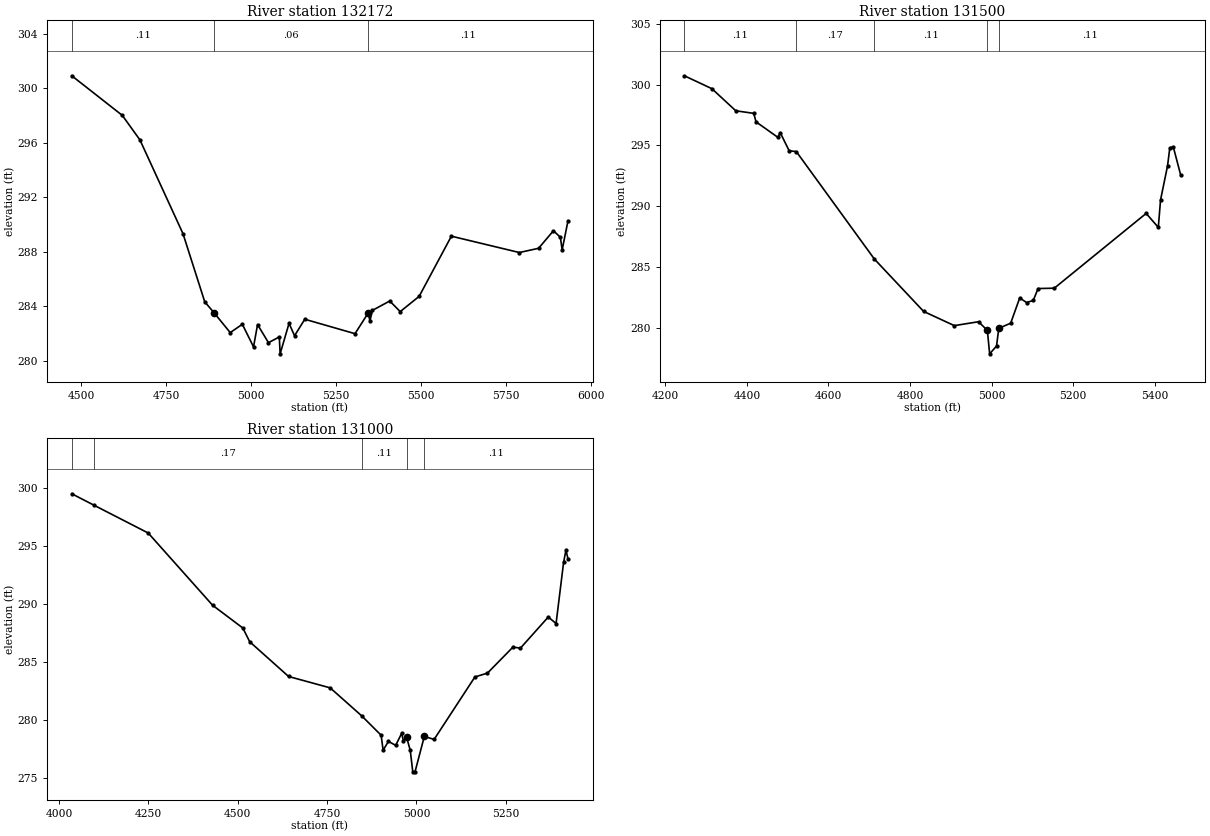
Type RM Length L Ch R = 1 ,132172  ,672,672,672
BEGIN DESCRIPTION:
Mapping XS 53fef309
END DESCRIPTION:
XS GIS Cut Line= 4
      3830055.23     10142068.48      3829400.73     10141773.78
      3829534.34     10141135.19      3829507.46     10141050.24
#Sta/Elev= 30
  4472.1  300.91  4620.7     298  4672.5   296.2  4799.2  289.31  4863.1  284.31
  4891.7  283.47    4938  282.05  4973.7  282.66  5006.6     281  5018.4  282.64
  5050.5  281.31  5082.4  281.73  5084.8  280.49    5111  282.73  5127.2  281.82
  5157.3  283.03    5305  281.97  5343.8  283.49  5348.9   282.9  5356.1  283.68
  5407.2  284.37  5437.9  283.59  5493.6  284.71  5588.4  289.13  5788.3  287.93
  5844.8  288.24  5888.6  289.53  5908.9  289.05  5914.2  288.13  5931.4  290.26
#Mann= 3 , 0 , 0
  4472.1     .11       0  4891.7     .06       0  5343.8     .11       0
Bank Sta=4891.7,5343.8
XS Rating Curve= 0 ,0
Exp/Cntr=0.3,0.1

Type RM Length L Ch R = 1 ,131500  ,500,500,500
BEGIN DESCRIPTION:
CRYSTAL CREEK 257.0
END DESCRIPTION:
XS GIS Cut Line= 3
      3830067.85     10142061.07      3829699.89     10141403.52
       3829500.2     10140984.81
#Sta/Elev= 30
  4246.5  300.72  4313.9  299.66  4372.6  297.84  4416.6  297.63  4422.3  296.93
  4475.7  295.66  4481.7  296.04  4503.4  294.56  4521.2  294.48  4712.5  285.65
  4833.4  281.34  4908.7  280.17  4968.1  280.49  4989.8  279.78  4995.4  277.85
  5012.3  278.49  5017.8  279.95    5047  280.37  5069.2  282.45  5085.9  282.07
  5102.4  282.24  5114.2  283.22    5154  283.25  5379.4   289.4  5409.2  288.25
  5414.7  290.51  5431.9  293.32  5437.4  294.79  5445.9  294.88  5463.9  292.58
#Mann= 5 ,-1 , 0
  4246.5     .11       0  4521.2     .17       0  4712.5     .11       0
  4989.8     .06       0  5017.8     .11       0
Bank Sta=4989.8,5017.8
XS Rating Curve= 0 ,0
Exp/Cntr=0.3,0.1

Type RM Length L Ch R = 1 ,131000  ,500,500,500
BEGIN DESCRIPTION:
CRYSTAL CREEK 256.0
END DESCRIPTION:
XS GIS Cut Line= 3
      3830167.86     10141961.11      3829985.29     10141014.25
      3829662.41     10140738.96
#Sta/Elev= 30
  4035.7  299.49  4098.2   298.5  4249.6  296.11  4429.8  289.89  4514.4  287.93
  4533.6  286.75  4642.4  283.76  4758.8  282.78    4847  280.37  4901.4   278.7
  4906.9  277.41  4921.8  278.17  4942.1  277.83  4958.7  278.86  4963.8  278.22
  4972.7  278.52  4982.9  277.39  4989.9  275.55  4996.2  275.55  5022.2   278.6
  5049.6  278.34  5163.8  283.72  5198.9  284.05  5270.3  286.29  5291.2   286.2
  5369.1  288.88  5390.9  288.32    5412  293.59  5418.5  294.64  5424.3  293.89
#Mann= 5 ,-1 , 0
  4035.7     .11       0  4098.2     .17       0    4847     .11       0
  4972.7     .07       0  5022.2     .11       0
Bank Sta=4972.7,5022.2
XS Rating Curve= 0 ,0
Exp/Cntr=0.3,0.1