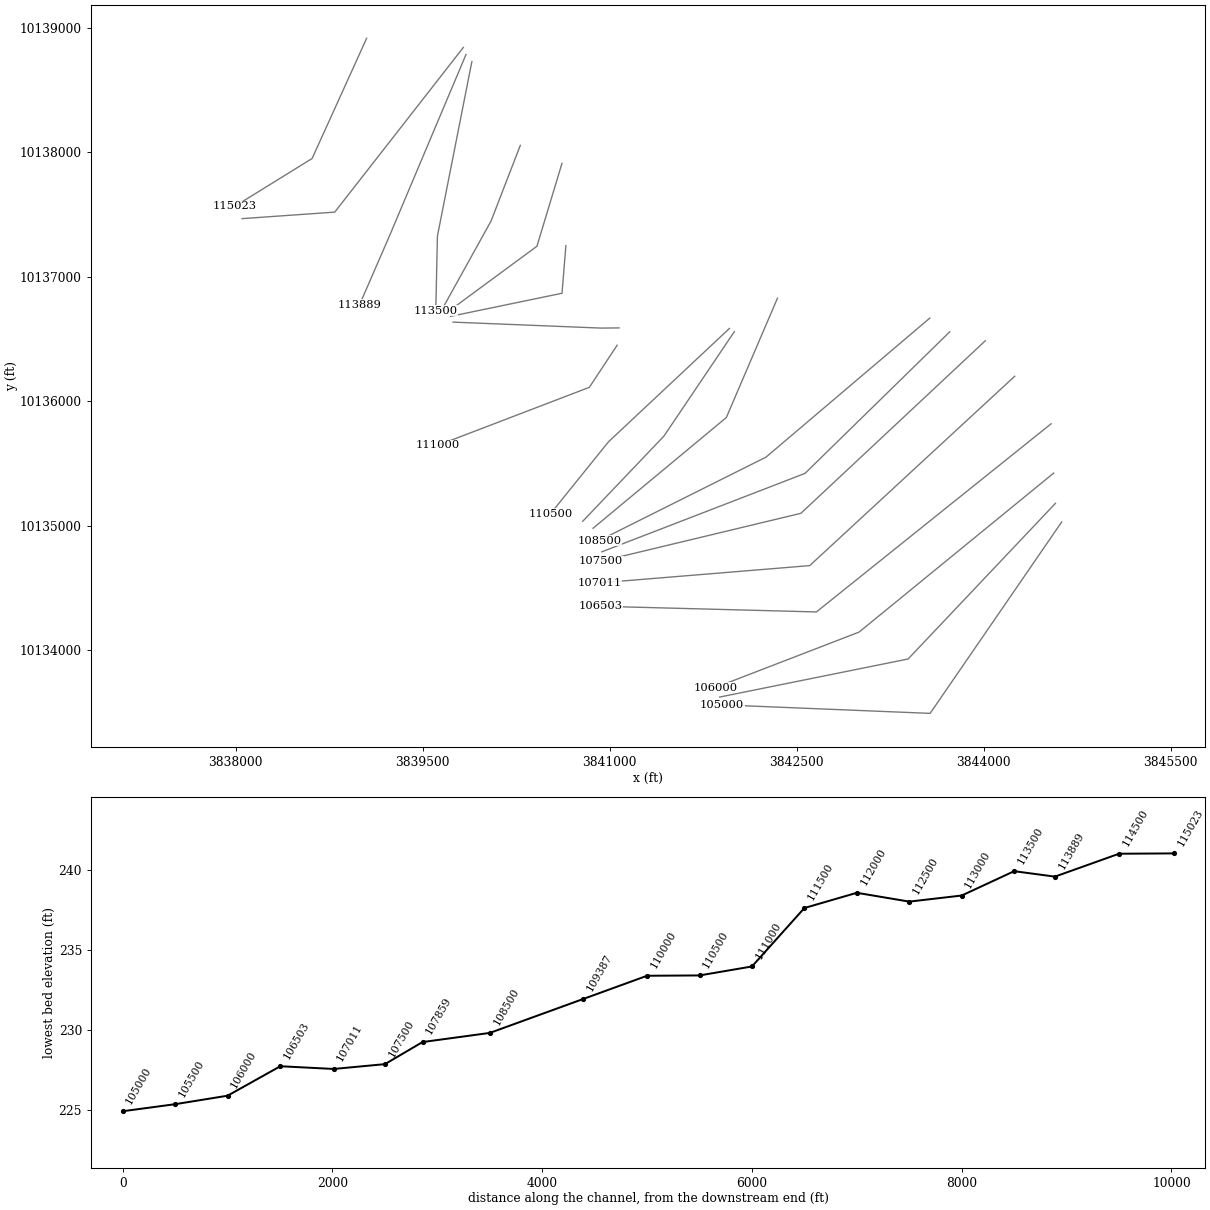
HEC-RAS study CRYSTAL CREEK.prj: CRYSTAL CREEK Base Level Engineering

--- CRYSTAL CREEK.g01 (geometry) --- (continued)

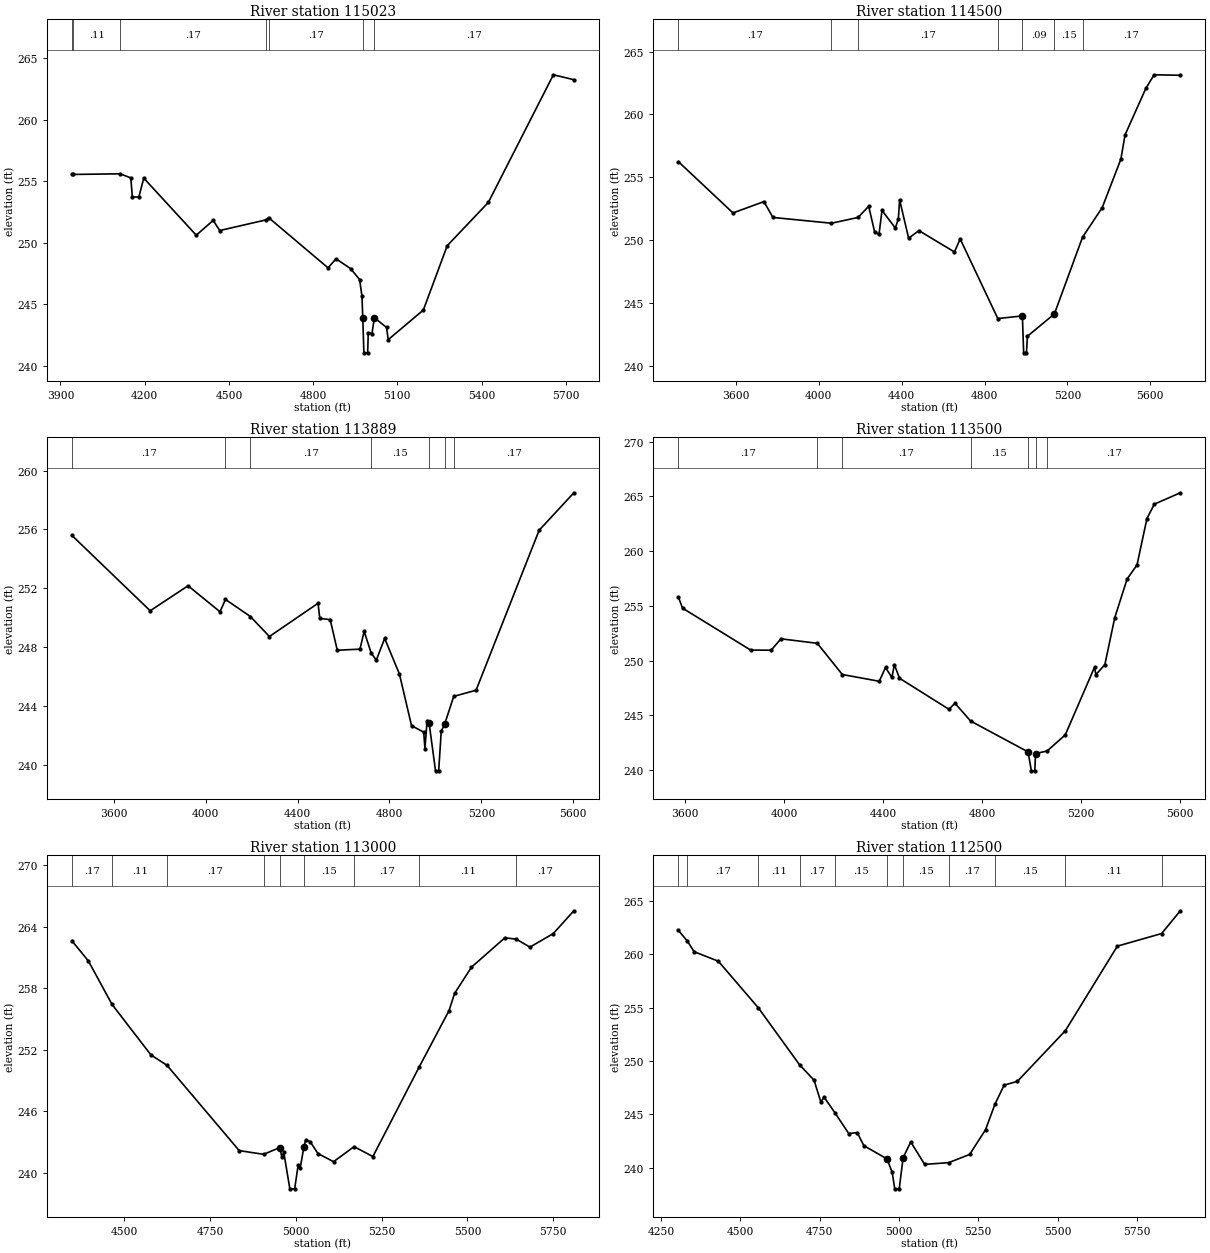
Type RM Length L Ch R = 1 ,115023  ,523,523,523
BEGIN DESCRIPTION:
CRYSTAL CREEK 226.0
END DESCRIPTION:
XS GIS Cut Line= 3
      3839050.56     10138914.51      3838613.38     10137949.74
      3837993.67     10137565.82
#Sta/Elev= 30
  3940.8  255.54  3944.2  255.54  4112.5  255.59  4150.5  255.26    4156  253.71
  4179.1   253.7  4196.7  255.24  4383.7   250.6  4444.1  251.81  4467.2  250.98
    4633  251.85  4641.4  252.03  4853.1  247.95  4881.7  248.68  4933.4  247.89
  4965.6     247  4974.1  245.64 4976.97243.9075  4980.9  241.04  4994.3  241.04
  4996.5  242.64  5009.7  242.61  5018.3   243.9  5061.7   243.1  5067.6  242.11
  5192.8  244.52  5277.9  249.75  5424.4  253.27    5656  263.64    5729  263.24
#Mann= 7 ,-1 , 0
  3940.8     .17       0  3944.2     .11       0  4112.5     .17       0
    4633     .11       0  4641.4     .17       0 4976.97     .09       0
  5018.3     .17       0
Bank Sta=4976.97,5018.3
XS Rating Curve= 0 ,0
Exp/Cntr=0.3,0.1

Type RM Length L Ch R = 1 ,114500  ,611,611,611
BEGIN DESCRIPTION:
CRYSTAL CREEK 225.0
END DESCRIPTION:
XS GIS Cut Line= 3
       3839826.6      10138841.6      3838794.85     10137519.16
       3838051.7     10137466.69
#Sta/Elev= 30
  3322.7  256.24  3586.1  252.16  3735.4  253.06  3778.8   251.8  4061.2  251.34
  4189.7   251.8    4241  252.69    4270  250.62  4290.8  250.46  4305.3  252.36
  4369.5  250.96    4384  251.67  4390.3   253.2  4433.7  250.15  4483.5  250.75
  4655.1  249.05  4682.5  250.09  4864.2  243.75  4982.8  243.96  4988.9  241.02
  5002.4  241.02    5007  242.34  5137.3  244.12  5272.9  250.22  5367.9  252.58
  5458.1  256.44  5478.2  258.37  5578.4  262.07  5618.5  263.16    5745  263.12
#Mann= 7 ,-1 , 0
  3322.7     .17       0  4061.2     .11       0  4189.7     .17       0
  4864.2     .15       0  4982.8     .09       0  5137.3     .15       0
  5272.9     .17       0
Bank Sta=4982.8,5137.3
XS Rating Curve= 0 ,0
Exp/Cntr=0.3,0.1

Type RM Length L Ch R = 1 ,113889  ,389,389,389
BEGIN DESCRIPTION:
Mapping XS 47638649
END DESCRIPTION:
XS GIS Cut Line= 3
      3839847.84     10138784.74      3839233.66     10137327.37
      3838993.76     10136775.02
#Sta/Elev= 30
  3418.5  255.59  3758.9  250.47  3923.8  252.17  4062.7   250.4  4086.4  251.24
  4194.8  250.08  4277.7  248.72  4489.2  250.98  4496.8  249.95  4542.1  249.87
  4572.8  247.79  4671.6  247.86  4689.9  249.07  4720.5  247.59  4742.8  247.12
    4779  248.59  4843.1  246.18    4896  242.66  4948.9  242.22  4954.3   241.1
  4963.4  242.95  4972.6  242.82  5000.3  239.59  5014.1  239.59  5025.2  242.28
  5039.6  242.74  5079.5  244.65  5176.8  245.07  5451.1  255.94  5602.2  258.49
#Mann= 7 ,-1 , 0
  3418.5     .17       0  4086.4     .11       0  4194.8     .17       0
  4720.5     .15       0  4972.6     .09       0  5039.6     .15       0
  5079.5     .17       0
Bank Sta=4972.6,5039.6
XS Rating Curve= 0 ,0
Exp/Cntr=0.3,0.1

Type RM Length L Ch R = 1 ,113500  ,500,500,500
BEGIN DESCRIPTION:
CRYSTAL CREEK 224.0
END DESCRIPTION:
XS GIS Cut Line= 3
      3839894.73     10138727.51      3839618.58     10137327.18
      3839605.25     10136726.13
#Sta/Elev= 30
  3572.7  255.79  3589.5  254.79  3864.7  250.96  3947.7  250.95    3987  251.99
    4134  251.58    4235  248.73  4384.5  248.11  4409.7  249.37  4435.4  248.46
  4445.6  249.63  4466.1  248.39  4666.3  245.55  4690.3  246.11  4753.6  244.48
  4985.8  241.66  4999.2  239.93    5013  239.93  5016.1  241.51  5062.7  241.74
  5136.1  243.21  5254.7  249.41  5259.7  248.71  5296.2  249.63  5336.2  253.92
  5386.2  257.46  5426.2  258.74  5466.2  262.97  5496.2  264.29  5601.2  265.33
#Mann= 7 ,-1 , 0
  3572.7     .17       0    4134     .11       0    4235     .17       0
  4753.6     .15       0  4985.8     .09       0  5016.1     .15       0
  5062.7     .17       0
Bank Sta=4985.8,5016.1
XS Rating Curve= 0 ,0
Exp/Cntr=0.3,0.1

Type RM Length L Ch R = 1 ,113000  ,500,500,500
BEGIN DESCRIPTION:
CRYSTAL CREEK 223.0
END DESCRIPTION:
XS GIS Cut Line= 3
       3840283.6     10138055.56      3840048.77     10137447.53
      3839656.16     10136739.15
#Sta/Elev= 30
  4348.2  262.62  4395.9  260.67  4465.1  256.41  4578.1  251.49    4625  250.47
  4835.4  242.14  4906.6  241.78  4953.3  242.44  4959.8   241.5  4965.2  241.96
  4982.8  238.41  4996.8  238.41  5006.9  240.72  5012.7   240.4 5023.58242.4725
  5028.7  243.15  5041.7  243.03  5064.5  241.86    5110  241.06  5169.9  242.53
  5224.6  241.56  5359.3   250.3  5446.5  255.82  5462.5  257.49  5511.7  260.05
    5609  262.92  5642.3  262.79  5681.9  262.01  5749.8  263.33  5809.9  265.56
#Mann= 9 ,-1 , 0
  4348.2     .17       0  4465.1     .11       0    4625     .17       0
  4906.6     .15       0  4953.3     .09       0 5023.58     .15       0
  5169.9     .17       0  5359.3     .11       0  5642.3     .17       0
Bank Sta=4953.3,5023.58
XS Rating Curve= 0 ,0
Exp/Cntr=0.3,0.1

Type RM Length L Ch R = 1 ,112500  ,500,500,500
BEGIN DESCRIPTION:
CRYSTAL CREEK 222.0
END DESCRIPTION:
XS GIS Cut Line= 3
      3840617.86      10137911.1      3840416.83     10137245.08
       3839702.5     10136718.58
#Sta/Elev= 30
  4304.3  262.22  4332.4  261.23  4353.8  260.23  4430.2  259.34  4556.8  254.96
  4686.5  249.64  4732.1   248.2  4753.5  246.17  4763.9  246.61  4797.5  245.17
  4841.5  243.21  4868.4  243.29  4889.3  242.07  4962.4  240.83  4978.6  239.56
  4986.7  238.03  5000.8  238.03 5013.03240.9376  5037.1  242.42    5081  240.32
  5156.7  240.48    5223  241.25  5273.1  243.57  5302.7  245.95  5331.7  247.74
  5373.4  248.09  5524.9  252.84  5688.8  260.75  5828.4  261.93  5887.4  264.06
#Mann= 11 ,-1 , 0
  4304.3     .11       0  4332.4     .17       0  4556.8     .11       0
  4686.5     .17       0  4797.5     .15       0  4962.4     .09       0
 5013.03     .15       0  5156.7     .17       0  5302.7     .15       0
  5524.9     .11       0  5828.4     .17       0
Bank Sta=4962.4,5013.03
XS Rating Curve= 0 ,0
Exp/Cntr=0.3,0.1

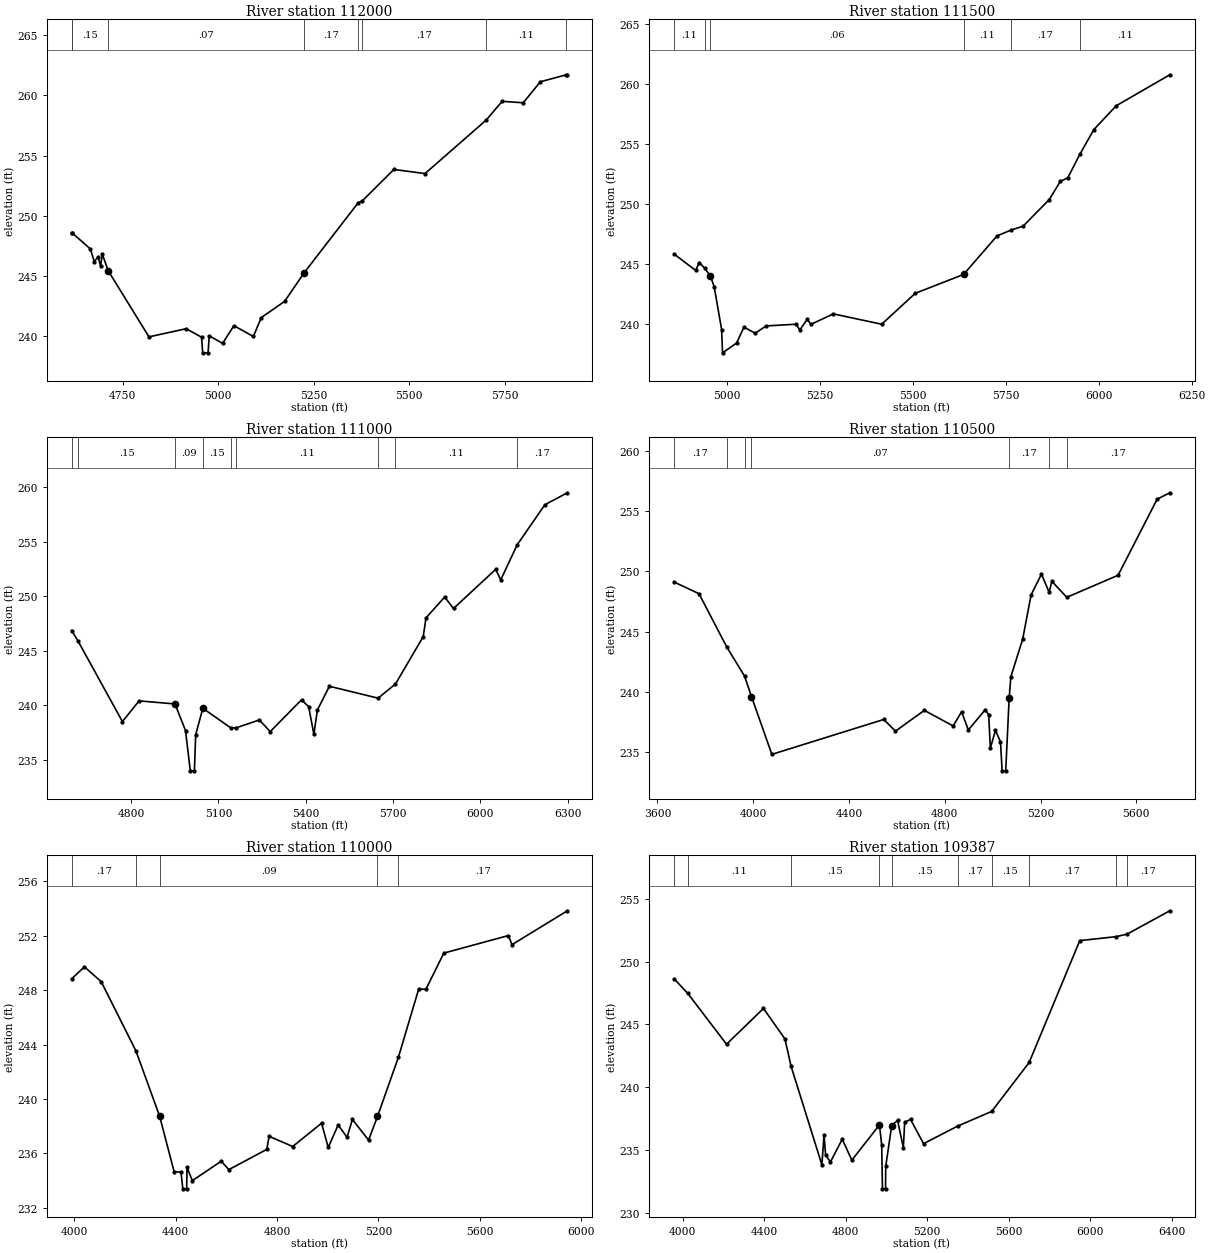
Type RM Length L Ch R = 1 ,112000  ,500,500,500
BEGIN DESCRIPTION:
CRYSTAL CREEK 221.0
END DESCRIPTION:
XS GIS Cut Line= 3
      3840649.08      10137250.1      3840617.98     10136867.56
      3839723.03     10136681.89
#Sta/Elev= 30
  4616.2  248.54  4618.3  248.54  4665.4  247.22  4675.4  246.18  4685.5  246.56
  4691.8  245.83  4696.8  246.77  4711.9245.4132  4818.7  239.91  4916.2  240.59
  4956.3  239.88  4959.3  238.58  4973.4  238.58  4976.4  239.99  5011.4  239.37
    5041  240.84    5092  239.94  5112.5  241.51  5173.7  242.86  5224.8  245.24
  5366.9  251.09  5375.9  251.19  5459.7  253.84  5541.4   253.5  5701.5  257.95
  5743.2  259.51  5798.4  259.39  5843.4  261.14  5911.4  261.72    5914  261.72
#Mann= 8 ,-1 , 0
  4616.2     .11       0  4618.3     .15       0  4711.9     .07       0
  5224.8     .17       0  5366.9     .15       0  5375.9     .17       0
  5701.5     .11       0  5911.4     .17       0
Bank Sta=4711.9,5224.8
XS Rating Curve= 0 ,0
Exp/Cntr=0.3,0.1

Type RM Length L Ch R = 1 ,111500  ,500,500,500
BEGIN DESCRIPTION:
CRYSTAL CREEK 220.0
END DESCRIPTION:
XS GIS Cut Line= 3
      3841075.79     10136589.36       3840933.9     10136587.74
      3839743.86     10136635.71
#Sta/Elev= 30
  4858.1  245.85    4916  244.49    4926  245.14  4940.7  244.66    4956  244.01
    4966  243.13    4986  239.57  4988.5  237.63  5026.1  238.44  5046.1  239.77
  5076.1  239.26  5106.1  239.87  5186.2  240.01  5196.2  239.54  5216.2  240.41
  5226.2     240  5286.3  240.87  5416.4  240.01  5506.5  242.58  5636.6  244.15
  5726.6  247.36  5764.1  247.84  5796.7  248.17  5866.7  250.37  5896.8  251.89
  5916.8  252.19  5949.3  254.15  5986.8   256.2  6046.9  258.18    6191  260.76
#Mann= 6 ,-1 , 0
  4858.1     .11       0  4940.7     .15       0    4956     .06       0
  5636.6     .11       0  5764.1     .17       0  5949.3     .11       0
Bank Sta=4956,5636.6
XS Rating Curve= 0 ,0
Exp/Cntr=0.3,0.1

Type RM Length L Ch R = 1 ,111000  ,500,500,500
BEGIN DESCRIPTION:
CRYSTAL CREEK 219.0
END DESCRIPTION:
XS GIS Cut Line= 3
      3841060.02     10136450.22       3840837.3      10136112.2
      3839624.03     10135647.27
#Sta/Elev= 30
  4595.2  246.86    4617   245.9  4769.8   238.5    4827   240.4  4950.5  240.12
  4986.6  237.68  5003.1  233.98  5017.2  233.98  5021.6   237.3  5046.3  239.72
  5141.9  237.93  5159.8  237.92  5240.5  238.65  5277.8  237.58  5385.4   240.5
    5410  239.87  5427.8  237.34  5440.1  239.57  5481.3  241.74  5648.8  240.65
  5708.4  241.95  5803.8   246.3  5813.3  248.02  5877.5  249.93  5907.9  248.88
  6052.7  252.47  6070.3  251.51  6126.9  254.73  6222.2  258.41  6299.3   259.5
#Mann= 9 ,-1 , 0
  4595.2     .11       0    4617     .15       0  4950.5     .09       0
  5046.3     .15       0  5141.9     .17       0  5159.8     .11       0
  5648.8     .17       0  5708.4     .11       0  6126.9     .17       0
Bank Sta=4950.5,5046.3
XS Rating Curve= 0 ,0
Exp/Cntr=0.3,0.1

Type RM Length L Ch R = 1 ,110500  ,500,500,500
BEGIN DESCRIPTION:
CRYSTAL CREEK 218.0
END DESCRIPTION:
XS GIS Cut Line= 3
      3841961.19     10136585.05      3840990.77     10135674.68
      3840526.84     10135098.68
#Sta/Elev= 30
  3669.4  249.12  3773.5  248.15  3890.3  243.69  3963.7   241.3  3992.8   239.6
  4077.8  234.79  4544.8  237.69  4594.1  236.72  4714.7  238.45  4834.9  237.15
  4870.1  238.33  4898.4  236.82  4969.2  238.51  4983.4  238.07  4990.3  235.32
  5011.8  236.78  5032.6  235.83  5039.5  233.42  5054.5  233.42  5068.8  239.46
  5075.8  241.23  5125.4  244.38  5160.6  248.06  5203.8  249.77    5236  248.26
    5247  249.18  5309.5  247.85  5523.7  249.68  5686.9  256.01  5739.6  256.54
#Mann= 7 ,-1 , 0
  3669.4     .17       0  3890.3     .11       0  3963.7     .15       0
  3992.8     .07       0  5068.8     .17       0    5236     .11       0
  5309.5     .17       0
Bank Sta=3992.8,5068.8
XS Rating Curve= 0 ,0
Exp/Cntr=0.3,0.1

Type RM Length L Ch R = 1 ,110000  ,613,613,613
BEGIN DESCRIPTION:
CRYSTAL CREEK 217.0
END DESCRIPTION:
XS GIS Cut Line= 3
      3842000.23     10136558.99      3841436.01     10135721.04
      3840783.75     10135036.14
#Sta/Elev= 30
  3989.8  248.83  4040.2  249.71  4106.1  248.63  4243.4  243.54  4336.9  238.74
    4394  234.67  4421.3  234.62  4428.5   233.4  4443.6   233.4    4445  234.99
    4466     234    4580  235.43    4610  234.81  4759.9   236.3  4768.9  237.26
  4861.9  236.51  4975.9  238.22  5002.3  236.44  5041.3  238.09  5076.5  237.19
  5097.6   238.5  5161.4  236.98  5196.6  238.72    5279  243.06  5359.2  248.08
  5387.6  248.06  5458.3  250.72  5713.1  252.01  5727.3  251.34  5945.8  253.83
#Mann= 5 ,-1 , 0
  3989.8     .17       0  4243.4     .15       0  4336.9     .09       0
  5196.6     .15       0    5279     .17       0
Bank Sta=4336.9,5196.6
XS Rating Curve= 0 ,0
Exp/Cntr=0.3,0.1

Type RM Length L Ch R = 1 ,109387  ,887,887,887
BEGIN DESCRIPTION:
CRYSTAL CREEK 216.0
END DESCRIPTION:
XS GIS Cut Line= 3
      3842346.28     10136827.83      3841936.16     10135869.61
       3840867.1      10134980.6
#Sta/Elev= 30
  3957.7  248.63  4024.4  247.48  4215.2  243.43  4396.6  246.27  4501.8  243.85
  4532.3  241.66  4683.2  233.85  4693.8  236.21  4701.4  234.64  4724.9  234.07
    4783  235.88  4830.2  234.22  4965.8  237.02  4976.7  235.43  4980.4  231.94
  4995.5  231.94  4996.5  233.72  5025.7  236.96  5054.4  237.38    5083  235.21
  5089.5  237.22  5118.2  237.46    5182  235.53  5348.9  236.92  5516.4  238.09
  5700.4  241.98  5948.8  251.66  6124.6  251.97  6180.5  252.17  6390.4  254.03
#Mann= 10 ,-1 , 0
  3957.7     .17       0  4024.4     .11       0  4532.3     .15       0
  4965.8     .09       0  5025.7     .15       0  5348.9     .17       0
  5516.4     .15       0  5700.4     .17       0  6124.6     .11       0
  6180.5     .17       0
Bank Sta=4965.8,5025.7
XS Rating Curve= 0 ,0
Exp/Cntr=0.3,0.1

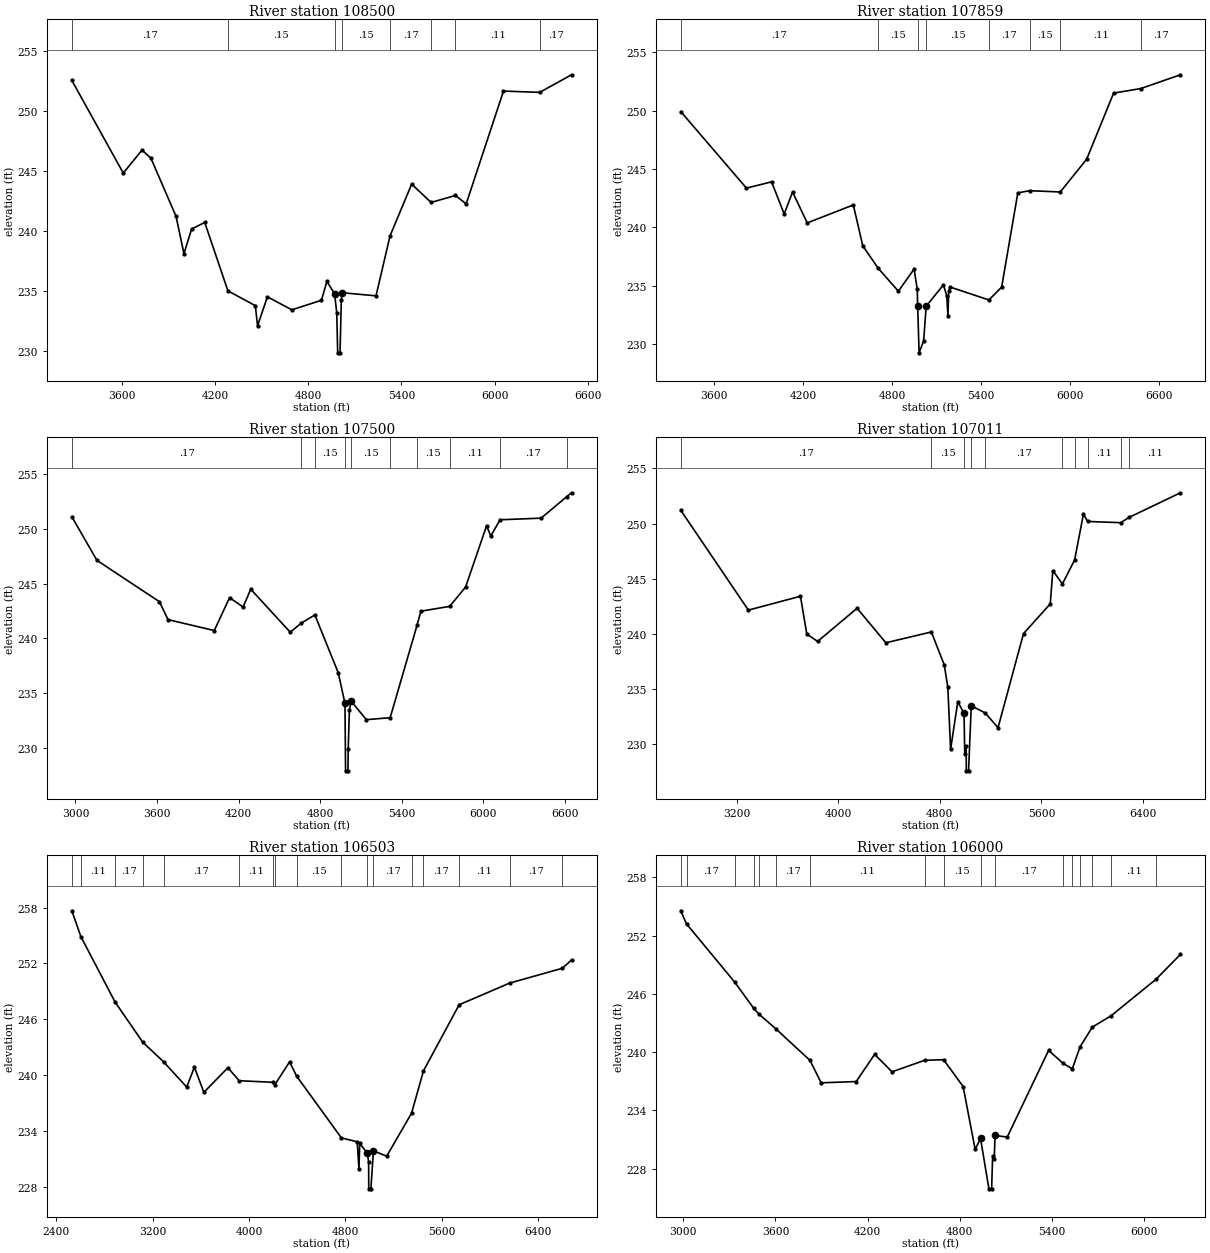
Type RM Length L Ch R = 1 ,108500  ,641,641,641
BEGIN DESCRIPTION:
CRYSTAL CREEK 215.0
END DESCRIPTION:
XS GIS Cut Line= 3
      3843568.49     10136668.11      3842254.37     10135551.57
      3840916.42     10134881.86
#Sta/Elev= 30
  3275.6  252.58  3607.1  244.84  3727.9  246.76    3785  246.09  3947.5  241.22
  3998.1  238.11  4047.5  240.17  4132.1  240.72  4281.4  235.01  4458.2  233.77
  4472.5  232.09  4536.2  234.51  4693.3  233.42  4884.4  234.22  4919.5  235.79
  4969.2  234.77  4983.2  233.13    4989  229.83  5004.1  229.83  5012.6  234.27
  5018.5  234.85  5236.1  234.59  5326.6   239.6  5465.8  243.92    5591  242.39
  5747.7  242.97  5817.3  242.27  6057.6  251.69    6291  251.58  6496.2  253.05
#Mann= 8 ,-1 , 0
  3275.6     .17       0  4281.4     .15       0  4969.2     .09       0
  5018.5     .15       0  5326.6     .17       0    5591     .15       0
  5747.7     .11       0    6291     .17       0
Bank Sta=4969.2,5018.5
XS Rating Curve= 0 ,0
Exp/Cntr=0.3,0.1

Type RM Length L Ch R = 1 ,107859  ,359,359,359
BEGIN DESCRIPTION:
Mapping XS eeb99dc1
END DESCRIPTION:
XS GIS Cut Line= 3
      3843728.09     10136557.79      3842567.07     10135420.98
      3840937.29     10134791.27
#Sta/Elev= 30
  3375.1  249.93  3818.5  243.37  3988.2  243.91  4073.1  241.15  4129.6  243.04
  4228.7  240.39  4539.7  241.93  4603.4  238.43  4707.2  236.51  4843.9  234.54
  4949.9  236.44    4971  234.72    4974233.2992  4983.5  229.26  5014.4  230.29
  5031.3  233.25  5148.1  235.09  5170.7   234.1  5178.1  232.42  5183.4  234.55
  5192.1   234.9  5454.5  233.79  5540.7  234.89  5649.8  242.96  5729.3  243.15
  5936.2  243.04  6114.1  245.84  6296.3  251.51  6479.6   251.9  6747.2  253.08
#Mann= 8 ,-1 , 0
  3375.1     .17       0  4707.2     .15       0    4974     .09       0
  5031.3     .15       0  5454.5     .17       0  5729.3     .15       0
  5936.2     .11       0  6479.6     .17       0
Bank Sta=4974,5031.3
XS Rating Curve= 0 ,0
Exp/Cntr=0.3,0.1

Type RM Length L Ch R = 1 ,107500  ,489,489,489
BEGIN DESCRIPTION:
CRYSTAL CREEK 214.0
END DESCRIPTION:
XS GIS Cut Line= 3
      3844013.63     10136486.01      3842534.26     10135100.44
      3840930.28     10134715.19
#Sta/Elev= 30
  2973.1  251.12  3157.7  247.13  3617.4  243.35  3680.9  241.71  4020.9  240.71
  4133.7  243.72  4232.9  242.86  4289.5  244.49  4579.7  240.56  4662.8   241.4
  4761.1  242.14  4933.3  236.85  4982.7  234.04  4987.1  227.88  5004.7  227.88
  5006.6  229.92  5015.2   233.4  5027.2  234.26  5140.3  232.56  5315.2  232.74
    5513  241.19  5541.4  242.48  5752.8  242.92  5870.2  244.69  6024.8   250.3
  6055.6  249.35  6123.2  250.84  6425.8  250.99  6614.1  252.95  6649.6  253.31
#Mann= 10 ,-1 , 0
  2973.1     .17       0  4662.8     .11       0  4761.1     .15       0
  4982.7     .09       0  5027.2     .15       0  5315.2     .17       0
    5513     .15       0  5752.8     .11       0  6123.2     .17       0
  6614.1     .11       0
Bank Sta=4982.7,5027.2
XS Rating Curve= 0 ,0
Exp/Cntr=0.3,0.1

Type RM Length L Ch R = 1 ,107011  ,508,508,508
BEGIN DESCRIPTION:
CRYSTAL CREEK 213.0
END DESCRIPTION:
XS GIS Cut Line= 3
      3844249.78     10136201.33      3842605.04     10134680.52
      3840916.45     10134541.58
#Sta/Elev= 30
  2759.9  251.21  3292.4  242.15  3702.4  243.41  3752.2  239.99  3837.3  239.31
  4148.6  242.32  4374.8  239.19  4733.1  240.17  4834.7  237.19    4863  235.14
  4884.6  229.53  4941.3  233.85  4990.6  232.78  4995.9  229.12  5007.2  229.85
  5008.4  227.58    5026  227.58  5047.4  233.48  5158.2  232.82  5258.1  231.49
  5458.7  240.02  5669.4  242.72  5689.5  245.73  5764.9  244.53  5861.1  246.69
  5930.3  250.85  5964.2  250.19    6224  250.08    6292  250.57  6694.3  252.79
#Mann= 10 ,-1 , 0
  2759.9     .17       0  4733.1     .15       0  4990.6     .09       0
  5047.4     .15       0  5158.2     .17       0  5764.9     .11       0
  5861.1     .17       0  5964.2     .11       0    6224     .17       0
    6292     .11       0
Bank Sta=4990.6,5047.4
XS Rating Curve= 0 ,0
Exp/Cntr=0.3,0.1

Type RM Length L Ch R = 1 ,106503  ,503,503,503
BEGIN DESCRIPTION:
CRYSTAL CREEK 212.0
END DESCRIPTION:
XS GIS Cut Line= 3
      3844541.42     10135819.36      3842658.65     10134308.58
      3840923.32     10134354.08
#Sta/Elev= 30
    2529  257.66  2604.1  254.88  2887.8  247.85  3116.9  243.54    3291  241.41
  3482.9   238.7  3546.9  240.84  3625.3  238.13  3825.3  240.78  3918.5  239.38
  4201.3  239.21  4215.9  238.97  4337.4  241.41  4396.6  239.86  4767.6  233.23
  4899.1  232.81  4913.5  229.88  4919.9  232.63  4983.8  231.57  4993.8  230.63
  4994.9  227.75  5012.6  227.75  5033.8  231.84  5143.8  231.26  5350.5  235.89
  5449.3  240.44  5745.7  247.55  6164.5  249.88  6603.7  251.48  6678.9  252.37
#Mann= 17 ,-1 , 0
    2529     .17       0  2604.1     .11       0  2887.8     .17       0
  3116.9     .11       0    3291     .17       0  3918.5     .11       0
  4201.3     .17       0  4215.9     .11       0  4396.6     .15       0
  4767.6     .17       0  4983.8     .09       0  5033.8     .17       0
  5350.5     .11       0  5449.3     .17       0  5745.7     .11       0
  6164.5     .17       0  6603.7     .11       0
Bank Sta=4983.8,5033.8
XS Rating Curve= 0 ,0
Exp/Cntr=0.3,0.1

Type RM Length L Ch R = 1 ,106000  ,500,500,500
BEGIN DESCRIPTION:
CRYSTAL CREEK 211.0
END DESCRIPTION:
XS GIS Cut Line= 3
      3844562.28     10135423.55       3843001.3     10134146.84
      3841846.99     10133701.31
#Sta/Elev= 30
  2983.4  254.55  3021.4  253.19  3335.4  247.19    3459  244.49  3495.1  243.87
  3602.7  242.39  3825.1  239.14  3897.7  236.83    4126  236.96  4245.9  239.76
  4359.3  237.96  4571.6  239.15  4695.3  239.21  4822.3  236.44  4900.5  229.97
  4935.7   231.1  4990.1  225.91  5007.8  225.91  5014.4   229.3  5024.8     229
  5030.2  231.41  5109.4  231.24  5378.9  240.17  5472.7  238.84  5533.2  238.27
  5583.7  240.54  5663.7  242.57  5785.4  243.73  6078.6   247.5  6237.3  250.06
#Mann= 17 ,-1 , 0
  2983.4     .11       0  3021.4     .17       0  3335.4     .11       0
    3459     .17       0  3495.1     .11       0  3602.7     .17       0
  3825.1     .11       0  4571.6     .17       0  4695.3     .15       0
  4935.7     .09       0  5030.2     .17       0  5472.7     .11       0
  5533.2     .17       0  5583.7     .11       0  5663.7     .17       0
  5785.4     .11       0  6078.6     .17       0
Bank Sta=4935.7,5030.2
XS Rating Curve= 0 ,0
Exp/Cntr=0.3,0.1

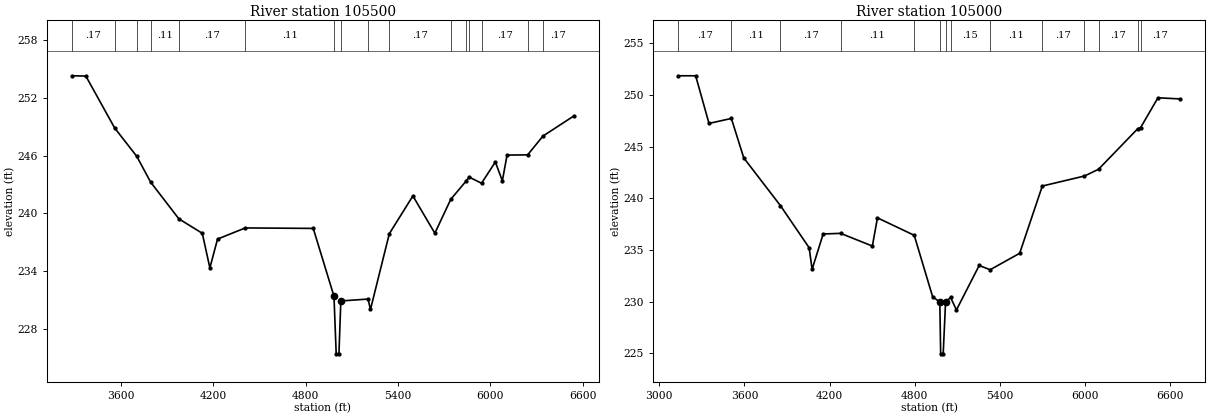
Type RM Length L Ch R = 1 ,105500  ,500,500,500
BEGIN DESCRIPTION:
CRYSTAL CREEK 210.0
END DESCRIPTION:
XS GIS Cut Line= 3
      3844576.13     10135180.46      3843394.42     10133930.81
      3841882.23     10133625.02
#Sta/Elev= 30
  3280.1  254.31  3370.5  254.28  3557.7  248.88  3701.3  245.93  3791.4  243.25
  3974.9  239.43  4127.4  237.92  4176.7  234.32  4226.5  237.32    4407  238.48
  4848.7  238.43  4983.4  231.37  4997.9  225.38  5015.6  225.38  5028.1  230.88
  5204.6  231.08  5220.8     230  5343.2  237.88  5496.4  241.81  5639.2  237.93
  5742.8  241.46  5842.7  243.36    5862  243.77  5942.6  243.13  6032.5  245.34
    6078  243.38  6108.6  246.06  6242.3  246.08  6342.2  248.04  6542.8  250.13
#Mann= 16 ,-1 , 0
  3280.1     .17       0  3557.7     .11       0  3701.3     .17       0
  3791.4     .11       0  3974.9     .17       0    4407     .11       0
  4983.4     .07       0  5028.1     .11       0  5204.6     .11       0
  5343.2     .17       0  5742.8     .11       0  5842.7     .17       0
    5862     .11       0  5942.6     .17       0  6242.3     .11       0
  6342.2     .17       0
Bank Sta=4983.4,5028.1
XS Rating Curve= 0 ,0
Exp/Cntr=0.3,0.1

Type RM Length L Ch R = 1 ,105000  ,500,500,500
BEGIN DESCRIPTION:
CRYSTAL CREEK 209.0
END DESCRIPTION:
XS GIS Cut Line= 3
      3844626.48     10135031.15      3843570.85     10133494.03
      3841902.65     10133562.41
#Sta/Elev= 30
  3135.3  251.85  3256.7  251.85  3350.7  247.24  3508.1  247.72  3595.6   243.9
  3853.9  239.28  4055.8  235.21  4076.7  233.12  4154.5  236.54  4277.7   236.6
    4501  235.37  4536.9   238.1  4795.9  236.41  4925.3  230.47    4976  229.95
    4982  224.94  4999.8  224.94 5016.51229.9487  5051.7   230.4  5093.1  229.19
  5253.2  233.49  5330.5  233.08  5538.3  234.67  5697.8  241.18  5994.6  242.15
  6093.5   242.8  6369.3  246.72  6390.2  246.84  6512.1  249.72  6669.6  249.61
#Mann= 14 ,-1 , 0
  3135.3     .17       0  3508.1     .11       0  3853.9     .17       0
  4277.7     .11       0  4795.9     .17       0    4976     .09       0
 5016.51     .17       0  5051.7     .15       0  5330.5     .11       0
  5697.8     .17       0  5994.6     .11       0  6093.5     .17       0
  6369.3     .11       0  6390.2     .17       0
Bank Sta=4976,5016.51
XS Rating Curve= 0 ,0
Exp/Cntr=0.3,0.1