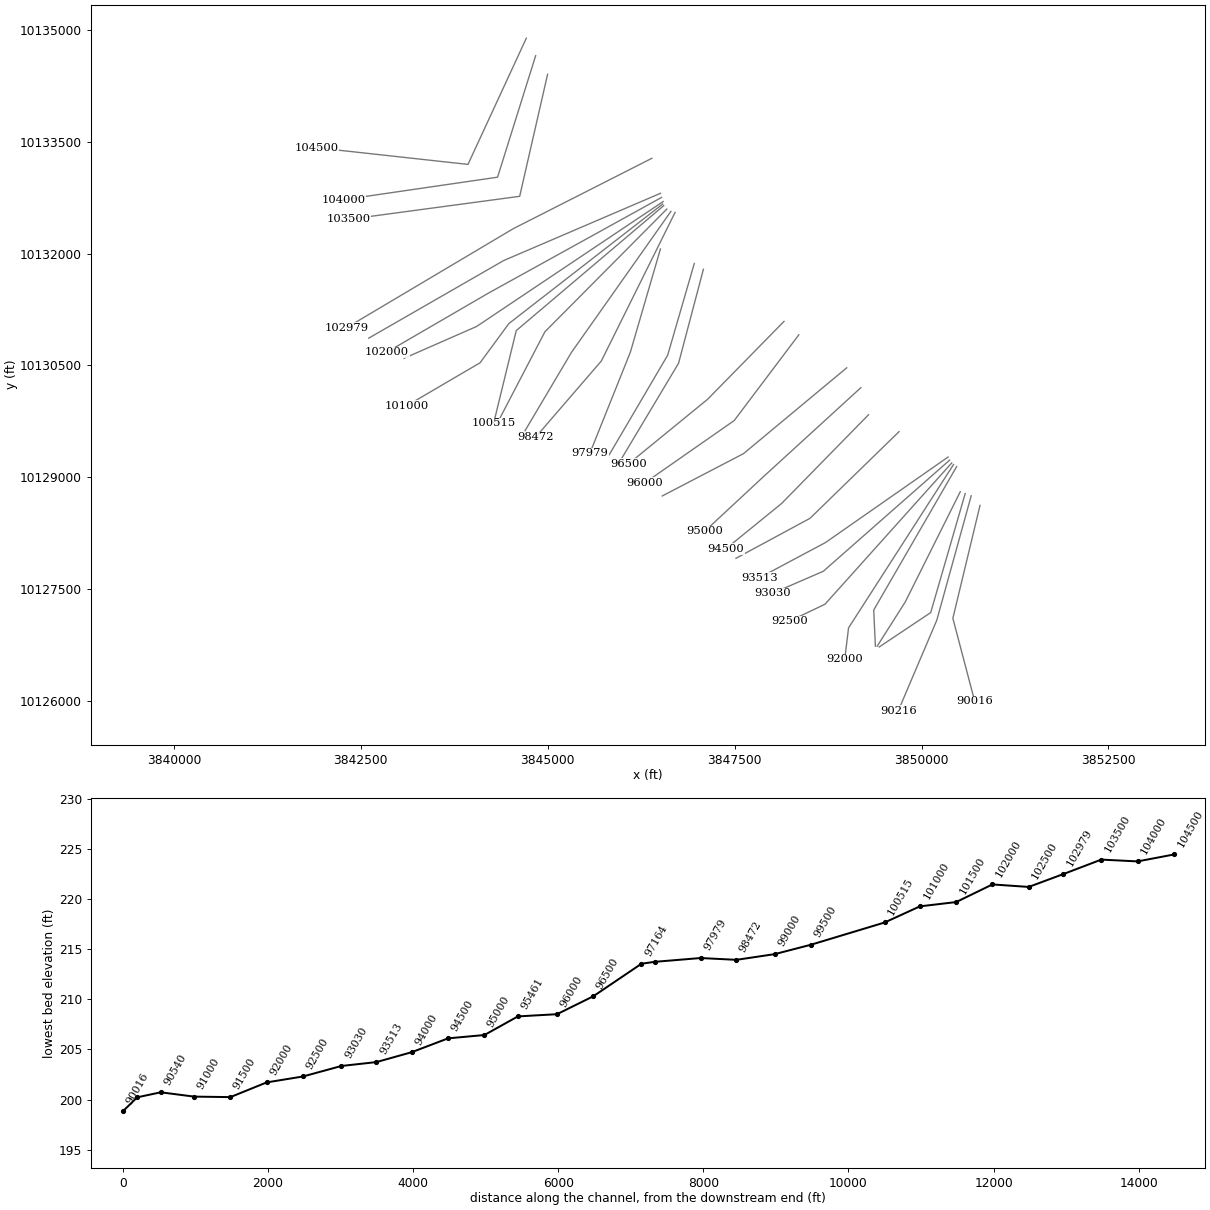
HEC-RAS study CRYSTAL CREEK.prj: CRYSTAL CREEK Base Level Engineering

--- CRYSTAL CREEK.g01 (geometry) --- (continued)

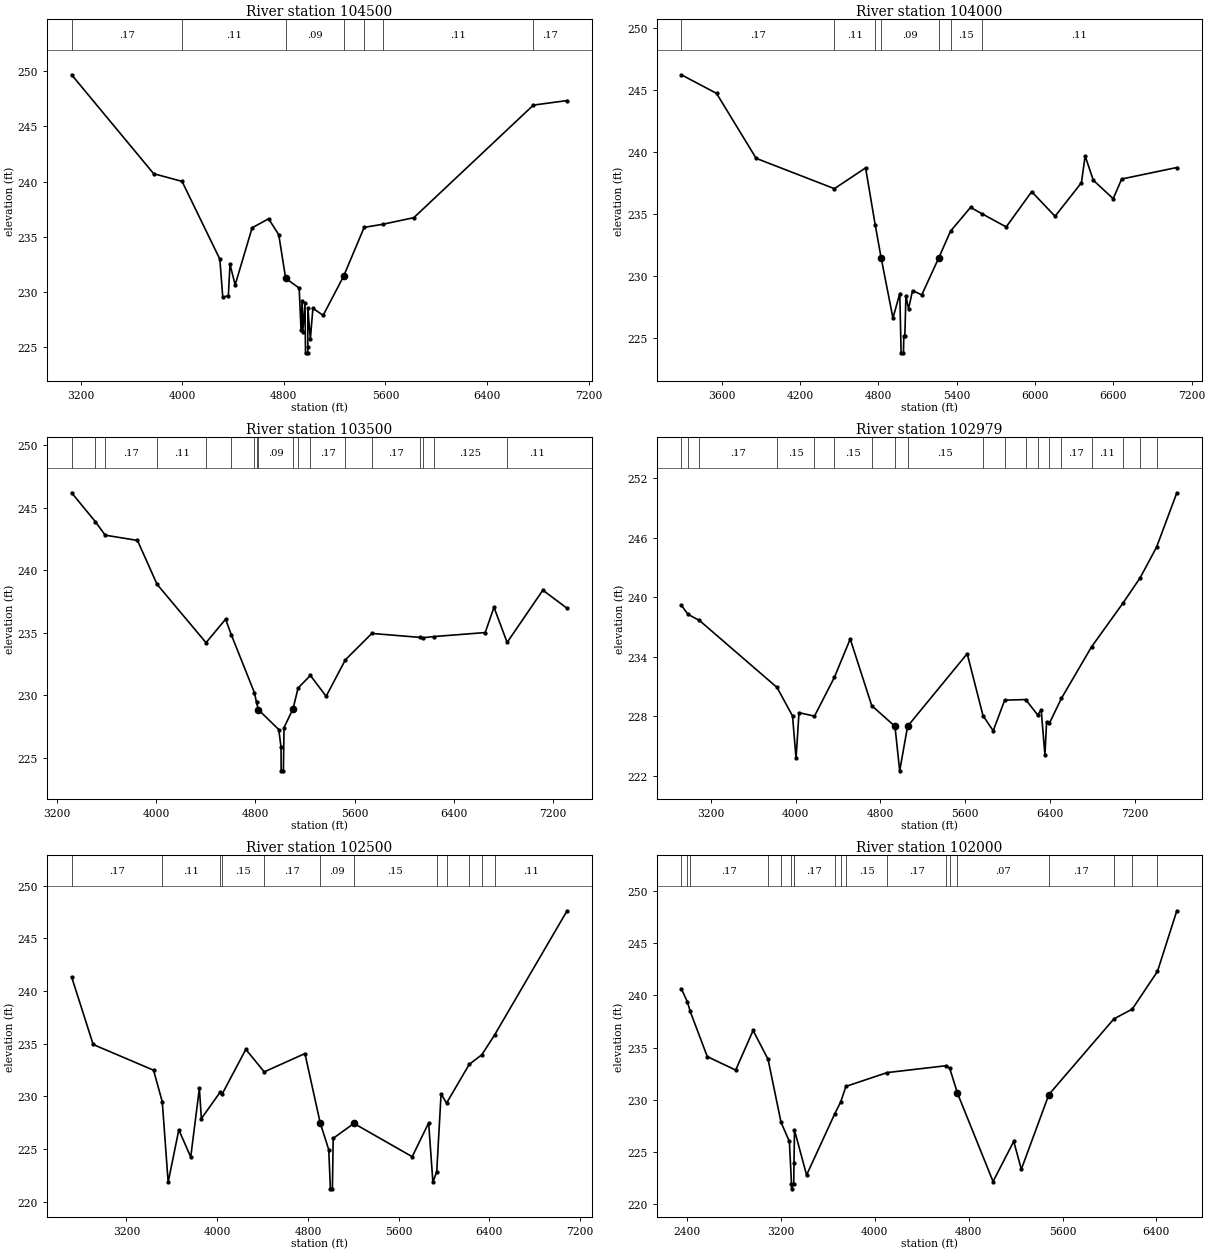
Type RM Length L Ch R = 1 ,104500  ,500,500,500
BEGIN DESCRIPTION:
CRYSTAL CREEK 208.0
END DESCRIPTION:
XS GIS Cut Line= 3
       3844713.3     10134892.29      3843933.22      10133198.5
      3841907.78     10133421.78
#Sta/Elev= 30
  3128.7  249.69  3774.7  240.72  3998.5  240.02  4296.3  232.96  4319.1  229.51
  4363.1  229.66  4376.2   232.5  4416.7  230.63  4550.3  235.81  4680.2  236.63
  4760.1  235.18  4814.5  231.23  4920.9  230.34  4935.6  226.56  4943.8  229.18
  4949.3  226.36  4966.8  228.99  4970.8  224.47  4988.6  224.47  4989.1  224.97
  4989.3  228.56    5009  225.73  5029.1  228.51  5109.6  227.87  5270.5  231.41
  5432.9  235.85  5579.3  236.13  5823.9  236.73  6765.8  246.94  7031.2  247.35
#Mann= 7 ,-1 , 0
  3128.7     .17       0  3998.5     .11       0  4814.5     .09       0
  5270.5     .15       0  5432.9     .17       0  5579.3     .11       0
  6765.8     .17       0
Bank Sta=4814.5,5270.5
XS Rating Curve= 0 ,0
Exp/Cntr=0.3,0.1

Type RM Length L Ch R = 1 ,104000  ,500,500,500
BEGIN DESCRIPTION:
CRYSTAL CREEK 207.0
END DESCRIPTION:
XS GIS Cut Line= 3
      3844838.29      10134657.9      3844328.98     10133026.87
      3842264.85      10132724.9
#Sta/Elev= 30
  3291.3  246.24  3560.4  244.74  3864.2  239.49  4463.5  237.04  4702.3  238.72
  4776.2   234.1    4821  231.47  4911.8  226.59  4964.2  228.57  4974.4  223.78
  4992.4  223.78  4995.2  225.16  5002.8  225.16  5011.2  228.36  5031.5  227.34
  5061.8  228.81  5132.5  228.46  5263.9  231.48  5352.9  233.61  5506.5  235.53
  5590.9  235.03  5779.3  233.95  5974.5   236.8  6153.3  234.81  6355.4  237.52
  6383.9  239.68  6446.4  237.72  6598.7  236.23  6663.6  237.82  7086.1  238.75
#Mann= 7 ,-1 , 0
  3291.3     .17       0  4463.5     .11       0  4776.2     .15       0
    4821     .09       0  5263.9     .11       0  5352.9     .15       0
  5590.9     .11       0
Bank Sta=4821,5263.9
XS Rating Curve= 0 ,0
Exp/Cntr=0.3,0.1

Type RM Length L Ch R = 1 ,103500  ,521,521,521
BEGIN DESCRIPTION:
CRYSTAL CREEK 206.0
END DESCRIPTION:
XS GIS Cut Line= 3
      3844998.03     10134407.94       3844624.6     10132770.07
      3842334.26     10132461.01
#Sta/Elev= 30
  3320.1   246.2  3512.1  243.88  3590.4  242.81  3850.2  242.39  4008.3  238.88
  4402.6  234.21  4560.5  236.09    4606  234.85  4792.9   230.2  4809.4  229.44
  4823.7  228.86  4988.7  227.26  5006.8  225.85  5007.9  223.96  5025.9  223.96
    5031  227.42  5103.7  228.93  5144.2  230.58  5243.2  231.59  5370.1  229.92
    5525  232.84  5738.5  234.95  6130.1  234.63  6154.1  234.61  6237.8   234.7
  6651.6  235.02  6722.2  237.04  6828.1  234.23  7115.8  238.41  7311.1  236.96
#Mann= 18 ,-1 , 0
  3320.1     .17       0  3512.1     .11       0  3590.4     .17       0
  4008.3     .11       0  4402.6    .125       0    4606     .15       0
  4792.9     .17       0  4809.4     .15       0  4823.7     .09       0
  5103.7     .15       0  5144.2     .11       0  5243.2     .17       0
    5525     .15       0  5738.5     .17       0  6130.1     .15       0
  6154.1     .11       0  6237.8    .125       0  6828.1     .11       0
Bank Sta=4823.7,5103.7
XS Rating Curve= 0 ,0
Exp/Cntr=0.3,0.1

Type RM Length L Ch R = 1 ,102979  ,479,479,479
BEGIN DESCRIPTION:
CRYSTAL CREEK 205.0
END DESCRIPTION:
XS GIS Cut Line= 3
      3846392.45     10133280.26      3844540.79     10132336.73
      3842307.85      10131005.6
#Sta/Elev= 30
  2921.8   239.2  2983.6  238.29  3092.2  237.67  3825.1  230.92  3971.3  228.05
  4004.4  223.77  4032.4  228.38  4178.6  228.03  4366.4  231.94    4516   235.8
  4719.1  229.09  4938.5     227  4983.1  222.52  5057.8  227.01  5620.4  234.32
  5769.4  228.09  5865.7  226.55  5974.5  229.64  6172.5   229.7  6284.9  228.16
    6319  228.65  6354.3   224.1  6369.8   227.4  6397.2  227.33  6509.5  229.81
  6794.9  235.02  7088.7  239.38  7252.9  241.96  7408.1  245.05  7599.6  250.53
#Mann= 19 ,-1 , 0
  2921.8     .17       0  2983.6    .125       0  3092.2     .17       0
  3825.1     .15       0  4178.6     .17       0  4366.4     .15       0
  4719.1     .17       0  4938.5     .09       0  5057.8     .15       0
  5769.4     .15       0  5974.5     .11       0  6172.5     .17       0
  6284.9     .15       0  6397.2     .15       0  6509.5     .17       0
  6794.9     .11       0  7088.7     .17       0  7252.9     .11       0
  7408.1     .17       0
Bank Sta=4938.5,5057.8
XS Rating Curve= 0 ,0
Exp/Cntr=0.3,0.1

Type RM Length L Ch R = 1 ,102500  ,500,500,500
BEGIN DESCRIPTION:
CRYSTAL CREEK 204.0
END DESCRIPTION:
XS GIS Cut Line= 3
      3846508.43     10132810.68      3844411.37     10131908.21
      3842605.64     10130866.23
#Sta/Elev= 30
    2717  241.34  2906.9  234.93  3439.3  232.49  3516.3  229.48  3567.9  221.86
    3662  226.83    3767  224.25  3843.1  230.77  3860.7   227.9  4029.3  230.45
  4042.3  230.19  4252.7  234.47  4414.9  232.33  4773.8  234.07  4907.8  227.51
  4983.8  224.94  4998.1  221.23  5016.1  221.23  5022.8  226.02  5205.2  227.44
  5719.3  224.28  5864.4  227.49  5901.7  221.86  5935.6  222.87  5973.9  230.25
  6021.8  229.36  6221.9  233.04  6333.4  233.96  6444.9  235.82  7084.8  247.62
#Mann= 12 ,-1 , 0
    2717     .17       0  3516.3     .11       0  4029.3     .17       0
  4042.3     .15       0  4414.9     .17       0  4907.8     .09       0
  5205.2     .15       0  5935.6     .11       0  6021.8     .17       0
  6221.9     .11       0  6333.4     .17       0  6444.9     .11       0
Bank Sta=4907.8,5205.2
XS Rating Curve= 0 ,0
Exp/Cntr=0.3,0.1

Type RM Length L Ch R = 1 ,102000  ,500,500,500
BEGIN DESCRIPTION:
CRYSTAL CREEK 203.0
END DESCRIPTION:
XS GIS Cut Line= 3
      3846522.35     10132755.14      3844208.23      10131471.5
      3842848.69     10130678.72
#Sta/Elev= 30
  2353.7  240.62  2405.7  239.35  2429.1  238.45  2574.5  234.13  2816.3  232.84
  2964.7  236.63  3092.2  233.87  3202.7  227.84  3273.7  226.01  3291.6  221.98
  3292.1  221.48  3310.7  221.98  3313.2  223.95  3317.2   227.1  3420.2   222.8
  3658.2  228.61  3711.5  229.81  3755.2  231.28  4106.4   232.6  4610.3  233.26
  4639.2  233.02  4705.4  230.63  5008.5  222.18  5184.7  226.02  5249.2  223.35
    5484   230.5  6037.9  237.74    6194  238.67  6408.9  242.28  6573.8  248.08
#Mann= 19 ,-1 , 0
  2353.7     .17       0  2405.7     .11       0  2429.1     .17       0
  3092.2     .15       0  3202.7     .11       0  3291.6     .12       0
  3310.7     .15       0  3313.2     .17       0  3658.2     .15       0
  3711.5     .17       0  3755.2     .15       0  4106.4     .17       0
  4610.3     .11       0  4639.2     .17       0  4705.4     .07       0
    5484     .17       0  6037.9     .11       0    6194     .11       0
  6408.9     .17       0
Bank Sta=4705.4,5484
XS Rating Curve= 0 ,0
Exp/Cntr=0.3,0.1

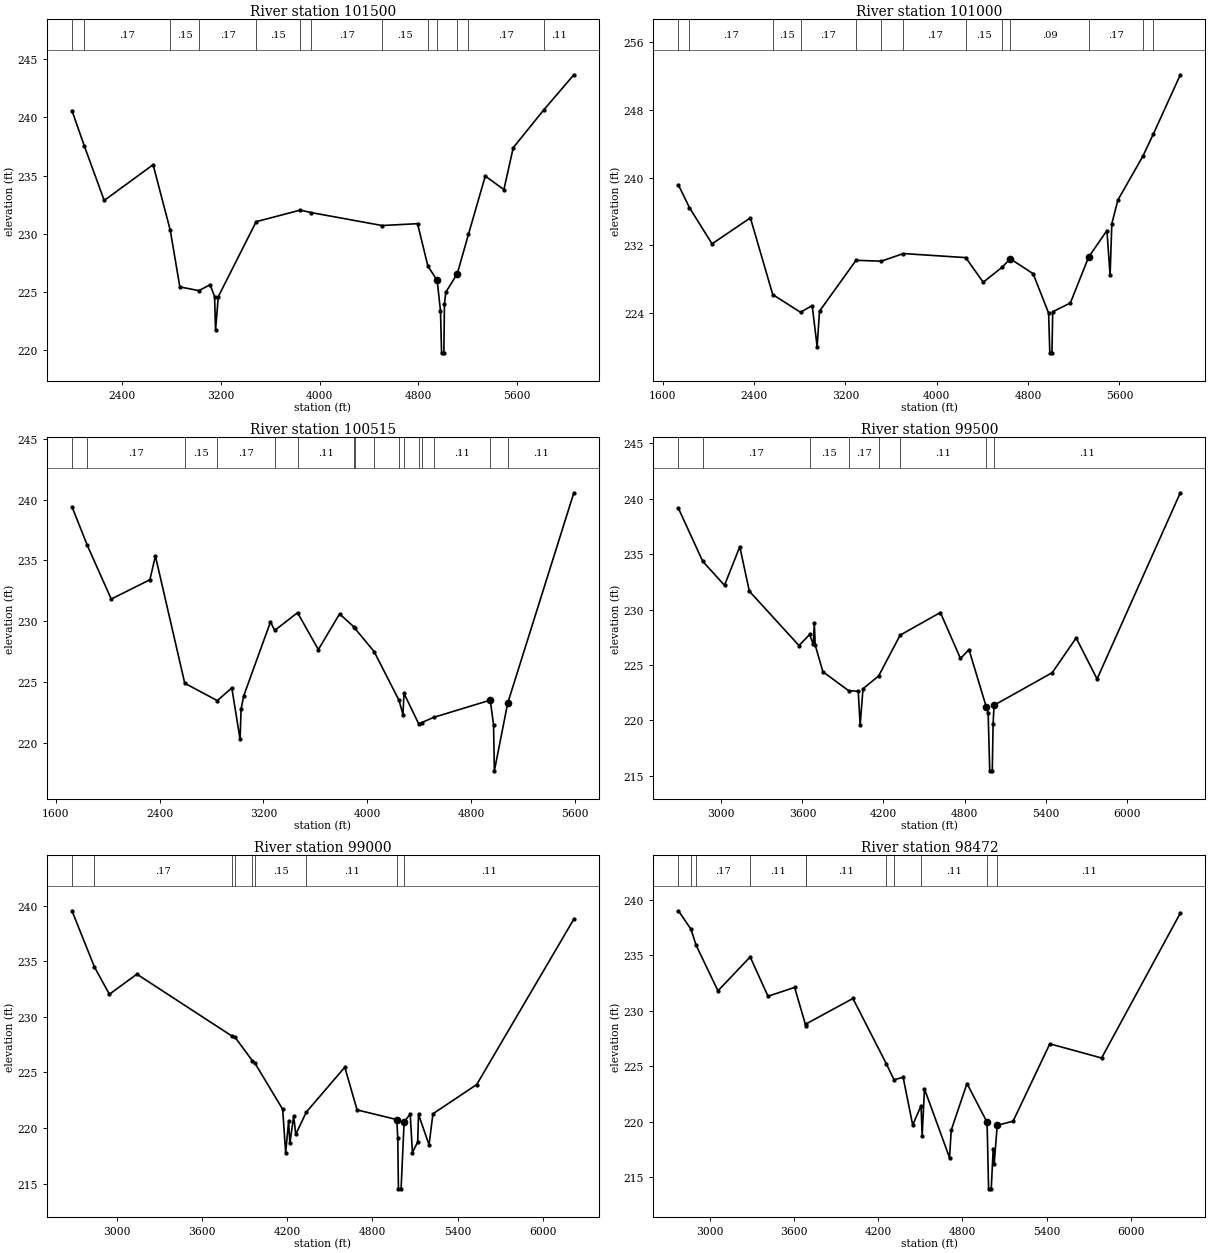
Type RM Length L Ch R = 1 ,101500  ,500,500,500
BEGIN DESCRIPTION:
CRYSTAL CREEK 202.0
END DESCRIPTION:
XS GIS Cut Line= 3
      3846543.16     10132699.57      3844048.25     10131022.83
      3843078.64     10130595.74
#Sta/Elev= 30
    1994   240.6  2095.1  237.52  2255.4  232.85  2651.4  235.93  2790.6  230.27
  2867.9   225.4  3022.5  225.08  3113.3  225.59  3149.3  224.57  3157.1  221.68
  3179.3  224.56  3486.1  231.02  3843.8  232.02    3930  231.81  4506.2  230.69
  4793.3  230.85  4877.1   227.2  4952.3  225.96  4979.3  223.34  4987.9  219.72
  5006.6  219.72  5011.3  223.94  5022.3  224.94  5115.6  226.55  5205.7  229.93
    5342  234.95  5492.9  233.79  5568.6   237.4  5816.3  240.66  6059.5  243.68
#Mann= 13 ,-1 , 0
    1994     .11       0  2095.1     .17       0  2790.6     .15       0
  3022.5     .17       0  3486.1     .15       0  3843.8     .11       0
    3930     .17       0  4506.2     .15       0  4877.1     .17       0
  4952.3     .09       0  5115.6     .15       0  5205.7     .17       0
  5816.3     .11       0
Bank Sta=4952.3,5115.6
XS Rating Curve= 0 ,0
Exp/Cntr=0.3,0.1

Type RM Length L Ch R = 1 ,101000  ,485,485,485
BEGIN DESCRIPTION:
CRYSTAL CREEK 201.0
END DESCRIPTION:
XS GIS Cut Line= 4
      3846536.91      10132665.7      3844479.61     10131061.42
      3844094.17     10130535.01      3843117.87     10129961.08
#Sta/Elev= 30
  1738.7  239.14  1835.4  236.46  2033.2  232.18  2368.8  235.25  2564.5  226.18
  2807.5  224.09  2909.7  224.88  2953.1  220.03    2974  224.22  3293.6  230.23
  3515.8  230.13  3708.2  231.03  4253.6  230.55  4406.8  227.64  4573.5  229.42
    4643  230.42  4843.7  228.65  4979.6  223.98    4990  219.29  5008.7  219.29
  5015.4  224.15  5169.7  225.18  5329.8  230.61    5490  233.75  5517.7  228.46
  5532.9  234.55  5585.7  237.35  5805.7  242.57  5897.1  245.19  6132.5  252.17
#Mann= 13 ,-1 , 0
  1738.7     .11       0  1835.4     .17       0  2564.5     .15       0
  2807.5     .17       0  3293.6     .15       0  3515.8     .11       0
  3708.2     .17       0  4253.6     .15       0  4573.5     .17       0
    4643     .09       0  5329.8     .17       0  5805.7     .11       0
  5897.1     .17       0
Bank Sta=4643,5329.8
XS Rating Curve= 0 ,0
Exp/Cntr=0.3,0.1

Type RM Length L Ch R = 1 ,100515  ,1015,1015,1015
BEGIN DESCRIPTION:
CRYSTAL CREEK 200.0
END DESCRIPTION:
XS GIS Cut Line= 3
      3846550.77     10132644.43      3844578.57     10130967.36
       3844276.7     10129725.16
#Sta/Elev= 30
  1724.7  239.43  1841.1  236.29  2027.4  231.82    2325  233.41  2367.8  235.36
  2593.9  224.89  2844.8  223.46  2956.5  224.51  3020.2  220.26  3027.9  222.77
  3048.7  223.87  3254.1  229.93  3287.3  229.24  3463.1   230.7  3623.1  227.66
  3786.8   230.6  3899.1  229.51  3904.1  229.42  4052.8   227.5  4244.8  223.48
  4275.4  222.31    4283  224.06    4396  221.56  4419.6  221.65  4511.1  222.08
  4947.8   223.5  4973.2  221.46  4979.5  217.68  5081.6  223.23  5591.9  240.57
#Mann= 16 ,-1 , 0
  1724.7     .11       0  1841.1     .17       0  2593.9     .15       0
  2844.8     .17       0  3287.3     .15       0  3463.1     .11       0
  3899.1     .17       0  3904.1     .11       0  4052.8     .17       0
  4244.8     .15       0    4283     .11       0    4396     .15       0
  4419.6     .17       0  4511.1     .11       0  4947.8     .09       0
  5081.6     .11       0
Bank Sta=4947.8,5081.6
XS Rating Curve= 0 ,0
Exp/Cntr=0.3,0.1

Type RM Length L Ch R = 1 ,99500   ,500,500,500
BEGIN DESCRIPTION:
CRYSTAL CREEK 198.0
END DESCRIPTION:
XS GIS Cut Line= 3
      3846592.61     10132598.85      3844961.94     10130951.41
      3844317.85     10129711.07
#Sta/Elev= 30
    2682  239.12  2862.2  234.34  3023.2  232.18  3136.3  235.66  3207.1  231.65
  3574.8  226.75  3653.3  227.75  3680.8  226.85  3687.9  228.75  3694.9  226.79
  3751.5  224.39  3942.8  222.68  4013.2  222.64  4027.3  219.58  4048.5  222.86
  4164.1  224.01  4323.6  227.69  4621.3  229.73  4769.8  225.59  4833.4  226.38
  4960.7  221.23  4974.8  220.71  4986.7  215.46  5005.5  215.46  5011.6  219.65
  5018.5  221.37  5449.6  224.31  5626.5  227.44  5781.3  223.74  6397.6  240.52
#Mann= 8 ,-1 , 0
    2682     .11       0  2862.2     .17       0  3653.3     .15       0
  3942.8     .17       0  4164.1     .15       0  4323.6     .11       0
  4960.7     .09       0  5018.5     .11       0
Bank Sta=4960.7,5018.5
XS Rating Curve= 0 ,0
Exp/Cntr=0.3,0.1

Type RM Length L Ch R = 1 ,99000   ,528,528,528
BEGIN DESCRIPTION:
CRYSTAL CREEK 197.0
END DESCRIPTION:
XS GIS Cut Line= 3
      3846647.35     10132567.66      3845316.31     10130673.82
      3844696.76     10129624.58
#Sta/Elev= 30
  2685.2  239.53  2843.7  234.47  2948.9  232.02  3142.3  233.83  3815.3  228.23
  3831.4  228.19  3954.9  226.05  3973.5  225.82  4168.7  221.68  4189.6  217.76
  4210.5  220.61  4219.2   218.6  4246.2  221.06    4261  219.42  4334.8  221.42
  4606.1  225.46  4692.3  221.62    4972  220.75  4978.9  219.09  4983.5  214.52
  5002.3  214.52  5023.5  220.53  5066.4  221.25  5082.1  217.78  5119.2  218.74
    5125  221.21  5199.1  218.48  5226.4  221.27  5534.7   223.9  6218.5  238.78
#Mann= 9 ,-1 , 0
  2685.2     .11       0  2843.7     .17       0  3815.3     .15       0
  3831.4     .17       0  3954.9     .11       0  3973.5     .15       0
  4334.8     .11       0    4972     .07       0  5023.5     .11       0
Bank Sta=4972,5023.5
XS Rating Curve= 0 ,0
Exp/Cntr=0.3,0.1

Type RM Length L Ch R = 1 ,98472   ,493,493,493
BEGIN DESCRIPTION:
CRYSTAL CREEK 196.0
END DESCRIPTION:
XS GIS Cut Line= 3
      3846702.88     10132553.74      3845717.15     10130559.78
      3844834.81     10129532.89
#Sta/Elev= 30
  2775.7  239.03  2865.6  237.36  2900.9  235.95  3057.6  231.81  3287.2  234.87
  3414.5  231.32  3604.2  232.12  3683.4  228.68  3688.1  228.84  4019.7  231.12
  4257.2  225.25  4312.7  223.79  4377.9  224.01    4446   219.7  4505.6  221.45
  4513.3  218.74    4530  222.96  4708.5  216.76  4720.8  219.25    4833  223.45
  4976.3  219.95    4987  213.95  5005.9  213.95    5020  217.58  5026.6  216.15
  5048.5  219.68  5161.6  220.05  5423.8  227.03  5792.6  225.75  6353.9  238.82
#Mann= 11 ,-1 , 0
  2775.7     .17       0  2865.6     .11       0  2900.9     .17       0
  3287.2     .11       0  3683.4     .17       0  3688.1     .11       0
  4257.2     .17       0  4312.7     .15       0  4505.6     .11       0
  4976.3     .07       0  5048.5     .11       0
Bank Sta=4976.3,5048.5
XS Rating Curve= 0 ,0
Exp/Cntr=0.3,0.1

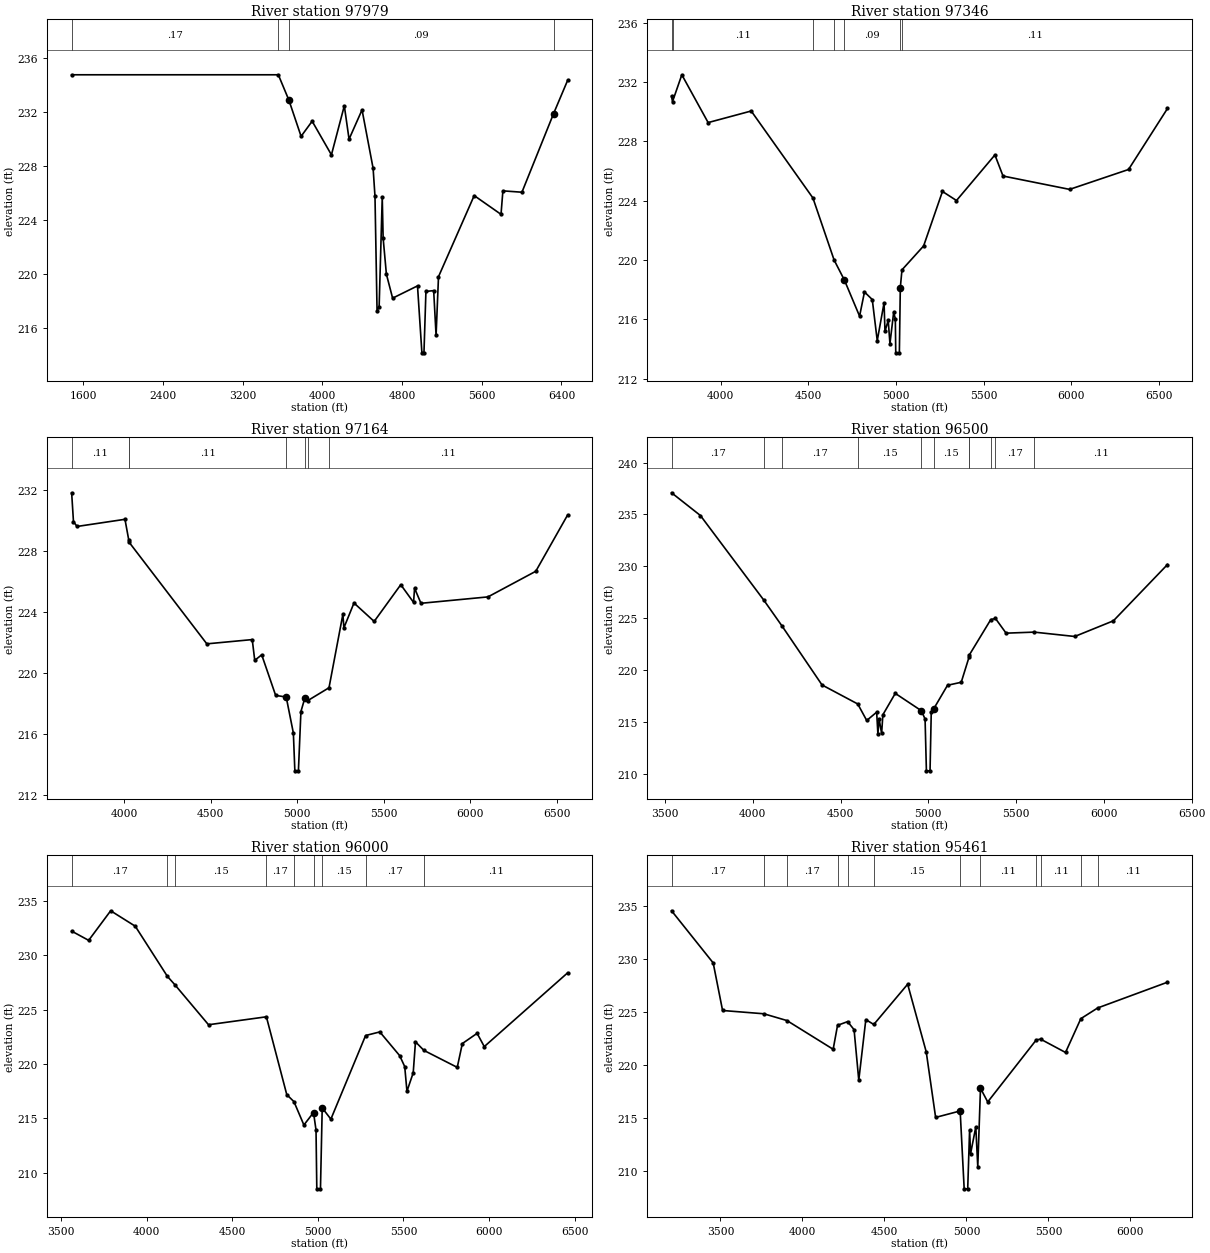
Type RM Length L Ch R = 1 ,97979   ,633,633,633
BEGIN DESCRIPTION:
CRYSTAL CREEK 195.0
END DESCRIPTION:
XS GIS Cut Line= 3
      3846507.39     10132063.38      3846105.07      10130677.6
      3845562.93     10129320.27
#Sta/Elev= 30
  1482.3  234.73  3557.3  234.73  3663.5  232.85  3785.9  230.17    3897  231.29
  4090.5   228.8  4219.8  232.43  4267.5  229.96  4397.9  232.13    4509   227.8
  4527.8  225.73  4548.6  217.25  4569.5  217.55  4600.7  225.65  4609.7  222.63
  4642.3  219.96  4704.8  218.18  4954.7  219.09  4998.9  214.13  5019.5  214.13
  5039.3  218.68    5117  218.74  5141.2  215.42  5165.5  219.77  5523.9  225.78
  5793.2  224.39    5812  226.13  6003.3  226.03  6320.7  231.85  6461.6  234.31
#Mann= 4 ,-1 , 0
  1482.3     .17       0  3557.3     .11       0  3663.5     .09       0
  6320.7     .11       0
Bank Sta=3663.5,6320.7
XS Rating Curve= 0 ,0
Exp/Cntr=0.3,0.1

Type RM Length L Ch R = 1 ,97346   ,182,182,182
BEGIN DESCRIPTION:
CRYSTAL CREEK 194.0
END DESCRIPTION:
XS GIS Cut Line= 3
       3846960.2     10131868.63      3846604.46     10130637.81
      3845822.47     10129301.04
#Sta/Elev= 30
  3718.8  231.03  3724.2  230.67  3777.4  232.48  3927.5  229.26  4173.3  230.04
  4525.5  224.18  4646.4     220  4705.1  218.65  4791.7  216.22  4819.6  217.85
  4864.1  217.34  4892.5  214.57  4931.4  217.12  4936.6  215.19    4955  215.94
    4965  214.37  4986.2  216.48  4995.7  216.05  4998.1  213.75  5018.7  213.75
  5024.1  218.14  5033.6  219.34  5157.1  220.95  5264.6  224.62  5344.7  224.01
  5563.9  227.08  5610.2  225.66  5990.1  224.76  6326.4   226.1  6548.7  230.21
#Mann= 7 ,-1 , 0
  3718.8     .15       0  3724.2     .11       0  4525.5     .17       0
  4646.4     .15       0  4705.1     .09       0  5024.1     .11       0
  5033.6     .11       0
Bank Sta=4705.1,5024.1
XS Rating Curve= 0 ,0
Exp/Cntr=0.3,0.1

Type RM Length L Ch R = 1 ,97164   ,664,664,664
BEGIN DESCRIPTION:
CRYSTAL CREEK 193.0
END DESCRIPTION:
XS GIS Cut Line= 3
      3847082.17     10131791.18        3846750.     10130529.37
      3845949.78     10129185.95
#Sta/Elev= 30
  3695.2   231.8  3705.7  229.91  3726.3  229.59  4003.6  230.06  4025.5   228.7
  4028.6  228.54  4477.1  221.89  4739.7  222.17  4754.2  220.81  4794.5  221.17
  4875.1  218.51  4936.2   218.4  4977.6  216.04  4986.2  213.56  5006.8  213.56
  5021.3  217.45  5044.6  218.36  5059.8  218.16  5183.7  219.01    5264  223.83
  5269.8  222.94  5328.2  224.57    5445  223.36  5598.8  225.77  5672.8  224.61
  5678.6  225.54  5715.6  224.55  6103.1  224.97  6379.6  226.65  6563.7  230.34
#Mann= 7 ,-1 , 0
  3695.2     .11       0  4025.5     .17       0  4028.6     .11       0
  4936.2     .09       0  5044.6     .11       0  5059.8     .15       0
  5183.7     .11       0
Bank Sta=4936.2,5044.6
XS Rating Curve= 0 ,0
Exp/Cntr=0.3,0.1

Type RM Length L Ch R = 1 ,96500   ,500,500,500
BEGIN DESCRIPTION:
CRYSTAL CREEK 192.0
END DESCRIPTION:
XS GIS Cut Line= 3
      3848160.25      10131091.1      3847137.47     10130044.88
      3846083.82     10129181.35
#Sta/Elev= 30
  3536.9  237.09  3701.3   234.9  4062.1  226.76  4167.4  224.23  4394.2  218.58
  4597.6  216.75  4648.8  215.16  4705.4  215.96  4712.4  213.87  4719.6  215.28
  4733.7  213.91  4740.7  215.71  4811.4  217.77    4960   216.1  4981.2   215.3
  4988.8  210.31  5009.5  210.31  5016.4  215.96  5030.7  216.29    5109  218.55
  5187.2  218.84  5231.5  221.25    5233  221.46  5355.3  224.87    5382  224.99
  5442.7  223.57  5602.7  223.67  5833.8  223.25  6054.2  224.76  6362.3  230.18
#Mann= 11 ,-1 , 0
  3536.9     .17       0  4062.1     .11       0  4167.4     .17       0
  4597.6     .15       0    4960     .09       0  5030.7     .15       0
  5231.5     .11       0    5233     .17       0  5355.3     .15       0
    5382     .17       0  5602.7     .11       0
Bank Sta=4960,5030.7
XS Rating Curve= 0 ,0
Exp/Cntr=0.3,0.1

Type RM Length L Ch R = 1 ,96000   ,539,539,539
BEGIN DESCRIPTION:
CRYSTAL CREEK 191.0
END DESCRIPTION:
XS GIS Cut Line= 3
      3848358.15     10130910.53      3847494.43     10129760.33
      3846298.95     10128923.42
#Sta/Elev= 30
  3561.6  232.22    3661  231.37  3789.6  234.09  3933.3  232.67    4121  228.06
  4164.6  227.29  4361.3  223.61  4699.4  224.34  4818.6  217.18  4860.4  216.54
  4918.6  214.39  4974.8  215.54  4989.4  213.93    4994  208.52  5015.4  208.52
  5025.6  215.96  5076.2  214.93  5279.2  222.62  5362.1  222.95  5478.1  220.77
  5507.7  219.76  5520.7  217.49  5557.3  219.19  5570.5  222.04  5619.9  221.25
  5814.6  219.69  5844.3  221.88  5930.6  222.82  5972.5   221.6  6459.3  228.38
#Mann= 9 ,-1 , 0
  3561.6     .17       0    4121     .11       0  4164.6     .15       0
  4699.4     .17       0  4860.4     .15       0  4974.8     .09       0
  5025.6     .15       0  5279.2     .17       0  5619.9     .11       0
Bank Sta=4974.8,5025.6
XS Rating Curve= 0 ,0
Exp/Cntr=0.3,0.1

Type RM Length L Ch R = 1 ,95461   ,461,461,461
BEGIN DESCRIPTION:
CRYSTAL CREEK 190.0
END DESCRIPTION:
XS GIS Cut Line= 3
      3848998.77     10130467.82      3847618.57     10129315.95
      3846532.13     10128747.88
#Sta/Elev= 30
  3202.3  234.54  3456.1  229.62  3513.4  225.13    3765  224.82  3905.8  224.18
  4187.6  221.47  4214.3  223.73  4275.7  224.08  4315.1  223.32  4343.8  218.55
  4386.7  224.27  4435.3  223.81  4641.8  227.61    4755  221.23  4812.3  215.04
  4961.9  215.65  4986.4   208.3  5007.9   208.3  5019.5  213.87  5025.2   211.6
  5057.2  214.14  5069.3   210.4  5085.8  217.79  5129.9   216.5  5425.7  222.35
  5451.9  222.43  5604.3  221.17  5697.7  224.36  5800.4  225.37    6226   227.8
#Mann= 12 ,-1 , 0
  3202.3     .17       0    3765     .11       0  3905.8     .17       0
  4214.3     .11       0  4275.7     .17       0  4435.3     .15       0
  4961.9     .09       0  5085.8     .11       0  5425.7    .125       0
  5451.9     .11       0  5697.7    .125       0  5800.4     .11       0
Bank Sta=4961.9,5085.8
XS Rating Curve= 0 ,0
Exp/Cntr=0.3,0.1

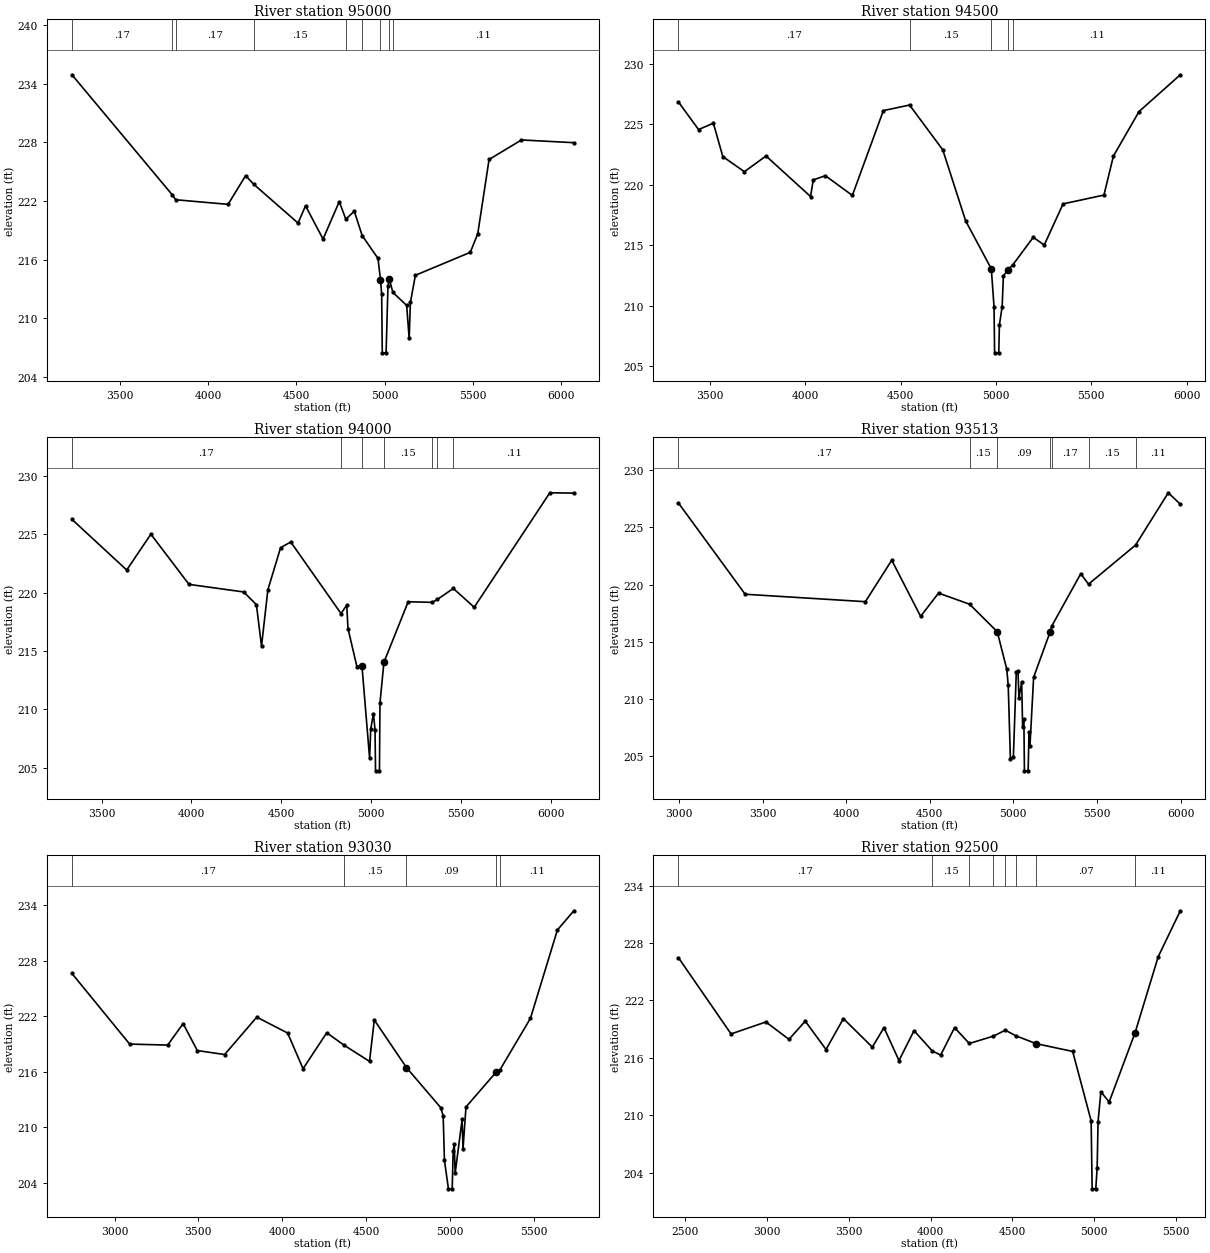
Type RM Length L Ch R = 1 ,95000   ,500,500,500
BEGIN DESCRIPTION:
CRYSTAL CREEK 189.0
END DESCRIPTION:
XS GIS Cut Line= 3
      3849188.31     10130201.42      3847881.85     10129003.24
      3847097.74     10128271.65
#Sta/Elev= 30
  3227.3  234.94  3796.6  222.62  3815.5  222.13  4112.4  221.66  4211.7   224.6
  4258.3  223.71  4508.9  219.74  4551.4  221.51  4650.7   218.1  4742.6  221.94
  4779.8  220.14  4827.7  220.96  4872.4  218.46  4962.1  216.12  4976.3  213.94
    4983  212.45  4986.4  206.44    5008  206.44  5018.7  213.26  5025.6  214.04
  5046.7  212.63  5124.7   211.3  5138.9  207.91  5145.8   211.6  5174.1  214.39
  5485.3  216.74  5527.8  218.66  5591.8  226.26  5775.5  228.26  6072.4  227.98
#Mann= 9 ,-1 , 0
  3227.3     .17       0  3796.6     .11       0  3815.5     .17       0
  4258.3     .15       0  4779.8     .17       0  4872.4     .15       0
  4976.3     .09       0  5025.6     .15       0  5046.7     .11       0
Bank Sta=4976.3,5025.6
XS Rating Curve= 0 ,0
Exp/Cntr=0.3,0.1

Type RM Length L Ch R = 1 ,94500   ,500,500,500
BEGIN DESCRIPTION:
CRYSTAL CREEK 188.0
END DESCRIPTION:
XS GIS Cut Line= 3
      3849290.44     10129837.61      3848128.07     10128646.76
      3847379.31      10128035.8
#Sta/Elev= 30
  3335.9  226.85  3441.4  224.56  3519.1  225.09  3568.6  222.33  3681.7  221.08
  3794.9  222.38  4028.4  219.03  4042.5   220.4  4106.1  220.75  4247.5  219.12
  4410.1  226.13  4547.3  226.59  4721.3  222.89  4841.5  217.01  4975.9  213.05
  4990.1   209.9    4993  206.11  5014.8  206.11  5018.3  208.43  5032.6  209.93
  5039.1  212.47  5061.4  212.94  5089.9  213.41  5195.6  215.66  5253.1  215.02
  5352.1  218.42  5566.1  219.15  5615.7  222.37  5749.9  226.05  5966.4  229.09
#Mann= 5 ,-1 , 0
  3335.9     .17       0  4547.3     .15       0  4975.9     .09       0
  5061.4     .15       0  5089.9     .11       0
Bank Sta=4975.9,5061.4
XS Rating Curve= 0 ,0
Exp/Cntr=0.3,0.1

Type RM Length L Ch R = 1 ,94000   ,487,487,487
BEGIN DESCRIPTION:
CRYSTAL CREEK 187.0
END DESCRIPTION:
XS GIS Cut Line= 3
      3849698.75     10129610.68      3848507.93     10128447.41
      3847517.87     10127911.08
#Sta/Elev= 30
  3335.3  226.28  3639.8  221.94  3774.1  225.01  3986.2  220.71  4290.3  220.06
    4361  218.97  4389.3  215.42  4424.7  220.25  4495.5  223.86    4552  224.34
  4831.5  218.21  4863.1  218.93  4870.2  216.92  4919.6  213.67  4947.9  213.72
  4990.4  205.79  4996.6  208.32  5011.5  209.63  5020.5  208.27  5023.3  204.73
  5045.1  204.73    5048  210.54  5069.9  214.03  5204.8  219.22  5338.9  219.17
  5366.9  219.42  5455.7  220.36    5572  218.75  5992.4  228.56    6126  228.53
#Mann= 7 ,-1 , 0
  3335.3     .17       0  4831.5     .15       0  4947.9     .09       0
  5069.9     .15       0  5338.9     .11       0  5366.9     .15       0
  5455.7     .11       0
Bank Sta=4947.9,5069.9
XS Rating Curve= 0 ,0
Exp/Cntr=0.3,0.1

Type RM Length L Ch R = 1 ,93513   ,483,483,483
BEGIN DESCRIPTION:
CRYSTAL CREEK 186.0
END DESCRIPTION:
XS GIS Cut Line= 3
      3850354.97     10129270.41      3848713.29     10128121.28
      3847832.49     10127650.33
#Sta/Elev= 30
  2996.1  227.13  3395.4  219.16  4114.6  218.51  4272.4  222.13    4445  217.23
  4552.3  219.26    4738  218.29  4903.6215.8861  4960.3  212.63  4969.1  211.23
  4982.2  204.81    5000  204.92  5017.5  212.37  5027.7  212.48  5033.4  210.07
  5049.7  211.52  5055.3  207.58  5062.9  208.27  5066.1  203.74  5088.4  203.74
  5093.5  207.13  5099.2  205.91  5121.2  211.91  5219.5  215.86  5230.3   216.4
  5403.1  220.95  5449.6  220.04  5730.9  223.45  5926.7  228.02  5998.8  227.02
#Mann= 7 ,-1 , 0
  2996.1     .17       0    4738     .15       0  4903.6     .09       0
  5219.5     .15       0  5230.3     .17       0  5449.6     .15       0
  5730.9     .11       0
Bank Sta=4903.6,5219.5
XS Rating Curve= 0 ,0
Exp/Cntr=0.3,0.1

Type RM Length L Ch R = 1 ,93030   ,530,530,530
BEGIN DESCRIPTION:
CRYSTAL CREEK 185.0
END DESCRIPTION:
XS GIS Cut Line= 3
       3850375.8     10129228.75      3848686.14     10127736.92
       3848007.9     10127441.72
#Sta/Elev= 30
    2746   226.6  3090.1  218.98  3316.9  218.87  3409.2  221.19  3493.7  218.28
  3656.8  217.85  3848.4  221.89  4032.4  220.17  4124.5  216.32  4265.8   220.2
  4369.8  218.85    4521  217.11  4549.4  221.58    4741  216.45  4945.9  212.11
  4960.2  211.24  4967.7  206.43  4991.7  203.35    5014  203.35  5019.9  207.42
  5026.3  208.19  5031.7  205.04  5073.2  210.84  5078.6  207.66  5096.3  212.19
    5277  215.97    5297  216.14  5480.8  221.76  5641.6   231.3  5739.7  233.37
#Mann= 5 ,-1 , 0
    2746     .17       0  4369.8     .15       0    4741     .09       0
    5277     .17       0    5297     .11       0
Bank Sta=4741,5277
XS Rating Curve= 0 ,0
Exp/Cntr=0.3,0.1

Type RM Length L Ch R = 1 ,92500   ,500,500,500
BEGIN DESCRIPTION:
CRYSTAL CREEK 184.0
END DESCRIPTION:
XS GIS Cut Line= 3
      3850403.57     10129190.54      3848708.61     10127294.37
      3848233.16      10127066.8
#Sta/Elev= 30
  2456.7  226.46  2778.7  218.49  2991.9  219.74  3133.2  217.92  3232.6  219.83
  3359.7  216.86  3465.9  220.09  3643.1  217.11  3714.1  219.15  3806.1  215.71
  3898.1  218.83  4010.4   216.7  4061.1  216.28    4146  219.15  4236.3  217.49
  4383.9  218.26  4456.3  218.88  4521.7  218.29  4646.1217.4682  4868.6  216.66
  4981.5  209.41  4987.7   202.3    5010   202.3  5018.3  204.49  5023.9  209.32
    5041  212.44  5091.9  211.38  5250.6  218.63  5392.1  226.57  5527.1  231.36
#Mann= 8 ,-1 , 0
  2456.7     .17       0  4010.4     .15       0  4236.3     .11       0
  4383.9     .15       0  4456.3     .11       0  4521.7     .15       0
  4646.1     .07       0  5250.6     .11       0
Bank Sta=4646.1,5250.6
XS Rating Curve= 0 ,0
Exp/Cntr=0.3,0.1

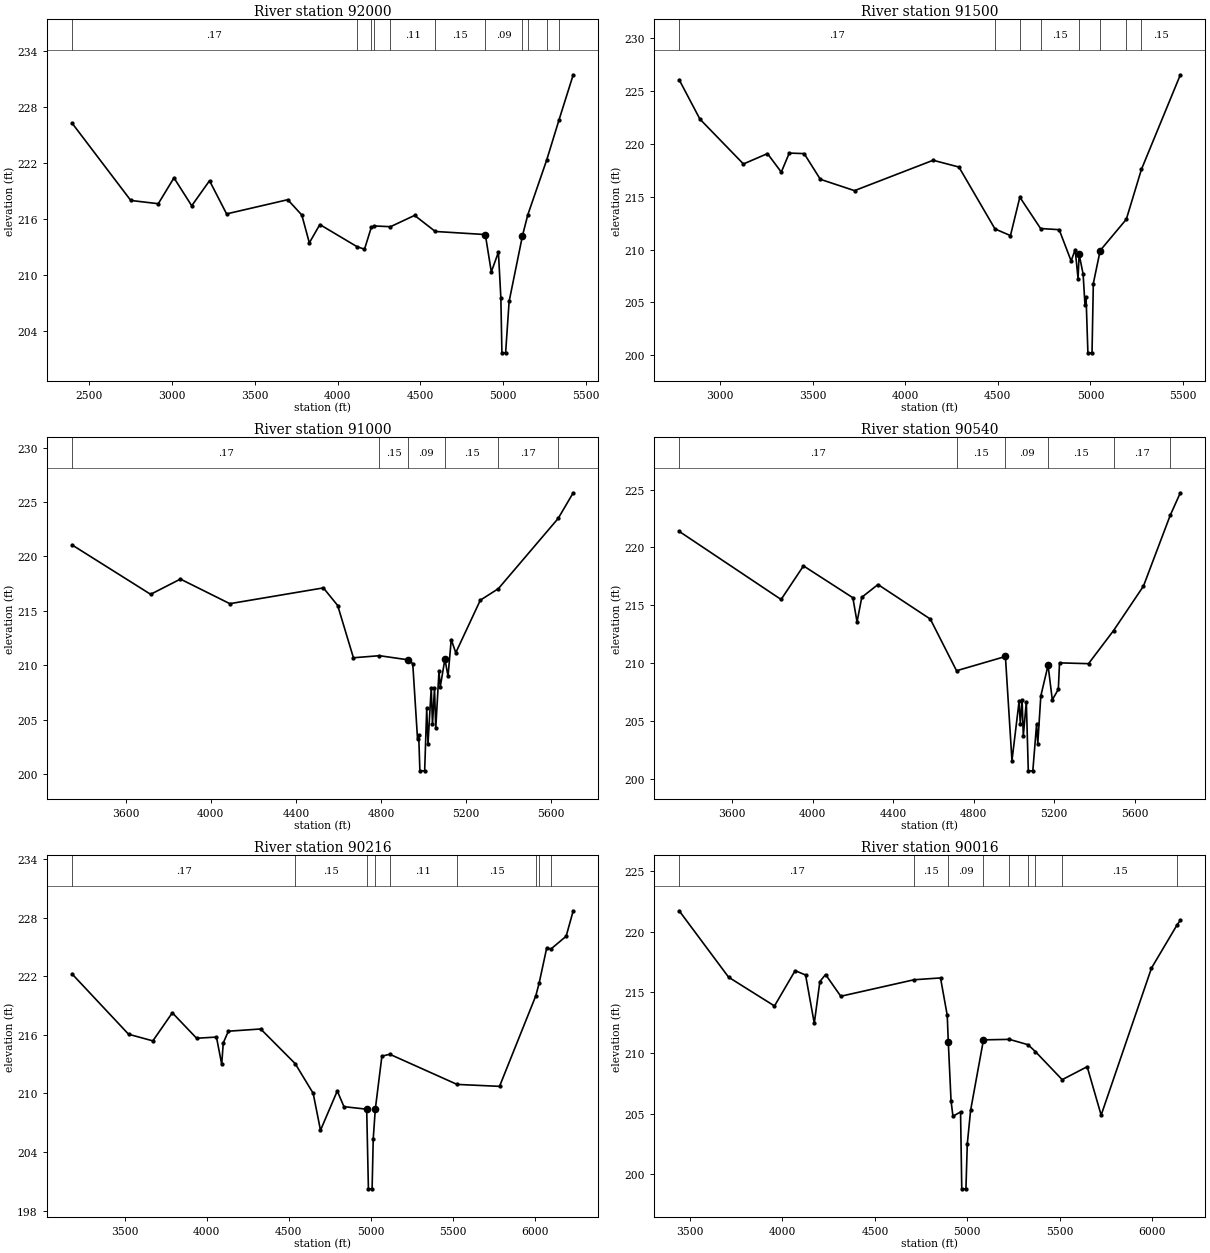
Type RM Length L Ch R = 1 ,92000   ,500,500,500
BEGIN DESCRIPTION:
CRYSTAL CREEK 183.0
END DESCRIPTION:
XS GIS Cut Line= 3
      3850427.89     10129169.74      3849023.61     10126976.83
       3848972.8      10126556.8
#Sta/Elev= 30
    2396   226.3  2750.7  218.02  2916.9  217.67  3011.6  220.44  3118.8  217.45
  3226.4  220.13  3329.5  216.58    3699   218.1  3783.8  216.46  3829.2  213.48
  3892.7  215.44  4116.6  213.08  4162.4   212.8  4203.4  215.13  4222.3  215.29
  4319.4  215.21  4465.1  216.42  4589.9   214.7  4892.1  214.37  4928.4  210.37
  4971.2  212.48    4986  207.62  4992.4  201.71  5014.7  201.71    5036  207.22
  5116.6  214.25  5148.7  216.48  5263.1  222.36  5337.4  226.65  5423.1  231.47
#Mann= 11 ,-1 , 0
    2396     .17       0  4116.6     .15       0  4203.4     .17       0
  4222.3     .15       0  4319.4     .11       0  4589.9     .15       0
  4892.1     .09       0  5116.6     .15       0  5148.7     .11       0
  5263.1     .15       0  5337.4     .11       0
Bank Sta=4892.1,5116.6
XS Rating Curve= 0 ,0
Exp/Cntr=0.3,0.1

Type RM Length L Ch R = 1 ,91500   ,500,500,500
BEGIN DESCRIPTION:
CRYSTAL CREEK 182.0
END DESCRIPTION:
XS GIS Cut Line= 3
      3850469.53     10129141.91      3849360.37     10127216.77
      3849382.47     10126731.37
#Sta/Elev= 30
  2778.2  226.05  2890.3  222.33  3125.4  218.09  3255.2  219.07  3329.9  217.32
    3373  219.12  3453.5  219.07  3540.9  216.64  3725.5  215.57  4150.2  218.44
  4289.6   217.8  4484.4  211.95    4568  211.32  4618.7  214.95  4730.8  211.99
  4831.2  211.88  4895.9  208.92  4917.5     210  4933.2  207.26    4939  209.55
  4960.6  207.68  4970.6  204.75  4976.4  205.54  4986.4  200.24  5008.7  200.24
  5015.7  206.79  5052.7  209.91  5193.9  212.86  5275.6  217.58  5485.9  226.52
#Mann= 8 ,-1 , 0
  2778.2     .17       0  4484.4     .15       0  4618.7     .17       0
  4730.8     .15       0    4939     .09       0  5052.7     .15       0
  5193.9     .11       0  5275.6     .15       0
Bank Sta=4939,5052.7
XS Rating Curve= 0 ,0
Exp/Cntr=0.3,0.1

Type RM Length L Ch R = 1 ,91000   ,460,460,460
BEGIN DESCRIPTION:
CRYSTAL CREEK 181.0
END DESCRIPTION:
XS GIS Cut Line= 3
      3850518.16     10128805.13      3849782.59     10127325.93
      3849406.76     10126731.35
#Sta/Elev= 30
    3348  221.05  3717.4  216.51  3857.3  217.91  4089.6  215.65  4529.3   217.1
  4596.5  215.48  4670.4  210.68  4792.7  210.87  4924.8210.4985  4949.2  210.15
  4971.6  203.26  4977.2  203.57  4982.8  200.29  5005.2  200.29  5014.9  206.02
  5020.9  202.78  5036.1  207.92    5042  204.56  5051.4  207.89  5057.3  204.19
  5072.6  209.43  5078.5  208.02  5100.4  210.55    5115  208.99  5130.2  212.35
  5151.4  211.14  5266.7  215.97  5351.6  217.03  5632.5  223.48  5703.4  225.84
#Mann= 6 ,-1 , 0
    3348     .17       0  4792.7     .15       0  4924.8     .09       0
  5100.4     .15       0  5351.6     .17       0  5632.5     .15       0
Bank Sta=4924.8,5100.4
XS Rating Curve= 0 ,0
Exp/Cntr=0.3,0.1

Type RM Length L Ch R = 1 ,90540   ,324,324,324
BEGIN DESCRIPTION:
CRYSTAL CREEK 180.0
END DESCRIPTION:
XS GIS Cut Line= 3
      3850584.13     10128780.84      3850122.26     10127182.12
      3849434.57     10126720.97
#Sta/Elev= 30
  3335.9  221.39  3842.7  215.51    3954  218.41  4199.6  215.66  4220.4  213.57
  4243.9   215.7  4324.5   216.8  4584.7  213.82  4715.1  209.36  4958.1  210.59
  4990.7   201.6  5026.1  206.72  5032.1   204.8  5041.1  206.86  5047.1  203.74
  5062.1  206.69  5071.9  200.72  5094.4  200.72  5113.1  204.74  5119.1  203.06
  5134.1  207.18  5170.2  209.83  5191.2  206.85  5221.2  207.75  5227.2  210.04
  5371.3  209.97  5495.6  212.82  5644.4  216.66    5778  222.79    5828  224.72
#Mann= 6 ,-1 , 0
  3335.9     .17       0  4715.1     .15       0  4958.1     .09       0
  5170.2     .15       0  5495.6     .17       0    5778     .15       0
Bank Sta=4958.1,5170.2
XS Rating Curve= 0 ,0
Exp/Cntr=0.3,0.1

Type RM Length L Ch R = 1 ,90216   ,200,200,200
BEGIN DESCRIPTION:
Mapping XS 095e7c73
END DESCRIPTION:
XS GIS Cut Line= 3
        3850664.     10128749.62      3850204.01     10127079.65
      3849687.75     10125862.15
#Sta/Elev= 30
  3179.8  222.24  3524.4  216.06  3672.3  215.38    3791  218.26    3939  215.65
    4060  215.77  4092.1  212.98  4101.4  215.17  4132.6  216.37  4329.6   216.6
  4539.8  213.05  4649.4  210.01  4694.1  206.22  4796.4  210.25  4836.9  208.64
  4975.6  208.38  4986.1  200.22  5008.6  200.22  5015.5  205.34    5028208.3668
  5068.3  213.81  5116.2  214.01  5526.4  210.92  5785.3  210.72  6006.4     220
  6026.9  221.32  6072.9  224.91  6098.3  224.79  6191.2   226.1  6234.4  228.71
#Mann= 9 ,-1 , 0
  3179.8     .17       0  4539.8     .15       0  4975.6     .09       0
    5028     .15       0  5116.2     .11       0  5526.4     .15       0
  6006.4     .11       0  6026.9     .17       0  6098.3     .11       0
Bank Sta=4975.6,5028
XS Rating Curve= 0 ,0
Exp/Cntr=0.3,0.1

Type RM Length L Ch R = 1 ,90016   ,516,516,516
BEGIN DESCRIPTION:
CRYSTAL CREEK 179.0
END DESCRIPTION:
XS GIS Cut Line= 3
      3850782.05     10128621.13      3850418.95     10127105.21
      3850711.45     10125990.97
#Sta/Elev= 30
  3441.2  221.71  3708.6  216.24  3956.7  213.87  4068.5  216.78  4124.9  216.42
    4172  212.44  4202.2  215.88    4233  216.46  4315.3  214.67  4711.8  216.03
  4854.8  216.18  4891.1   213.1  4896.8  210.91  4911.7  206.06    4922  204.79
  4963.1  205.14  4969.7  198.81  4992.2  198.81  4999.6  202.51  5017.6  205.28
    5087  211.08  5227.4  211.12  5328.1  210.68  5367.5  210.12  5512.9   207.8
    5648  208.87  5723.6  204.88  5995.8  216.99  6133.2  220.52    6152  220.93
#Mann= 9 ,-1 , 0
  3441.2     .17       0  4711.8     .15       0  4896.8     .09       0
    5087     .15       0  5227.4     .17       0  5328.1     .15       0
  5367.5     .17       0  5512.9     .15       0  6133.2     .11       0
Bank Sta=4896.8,5087
XS Rating Curve= 0 ,0
Exp/Cntr=0.3,0.1