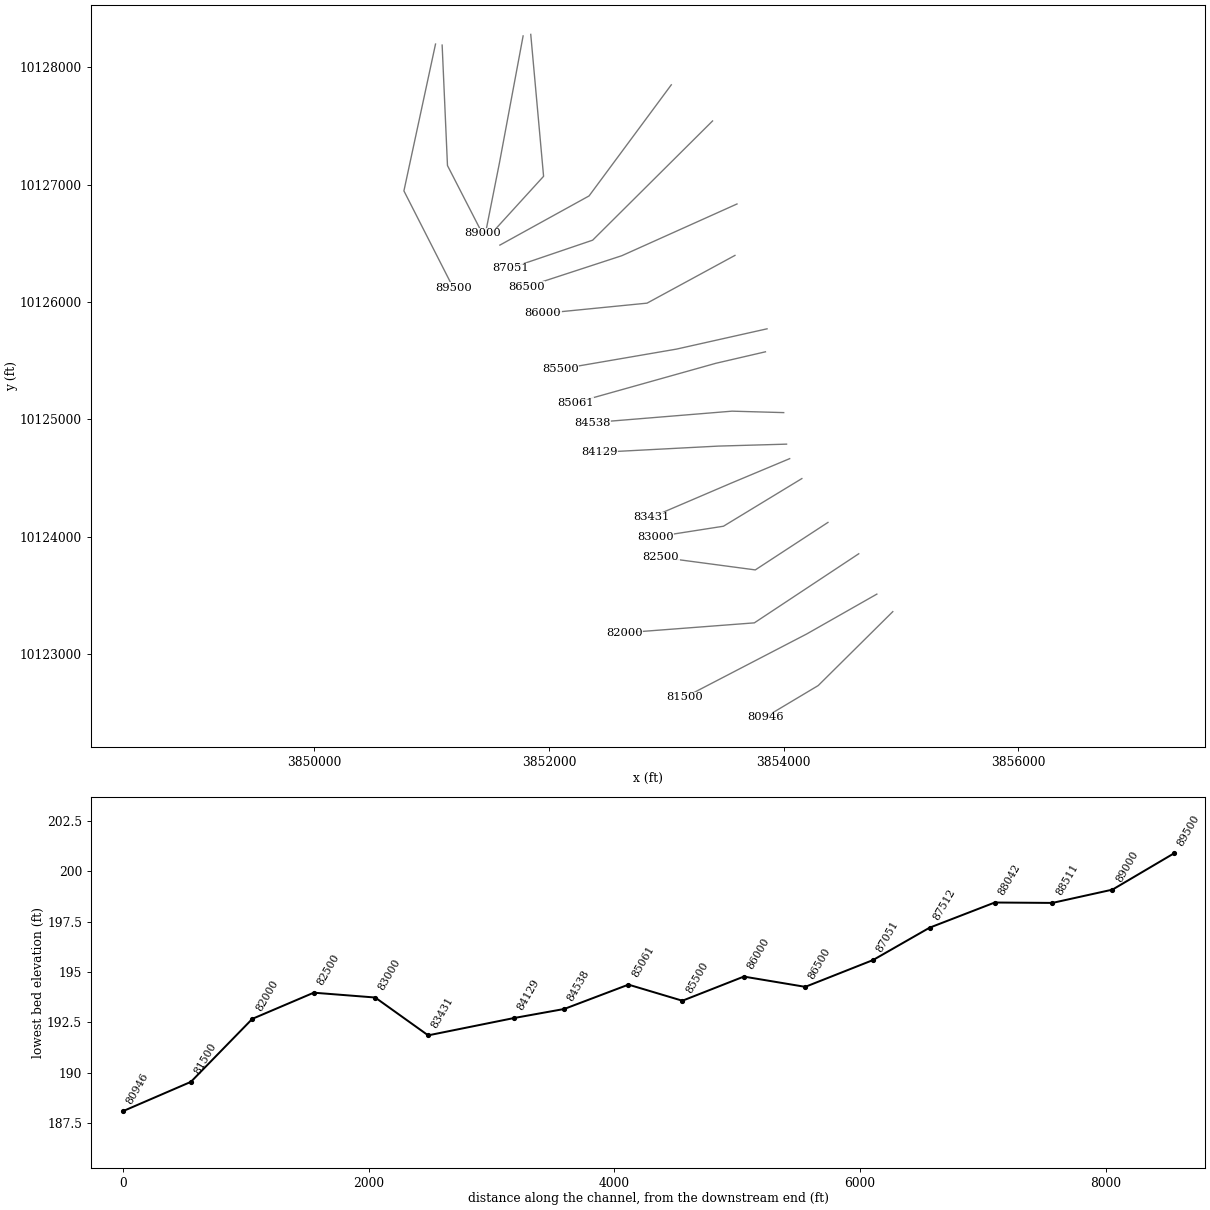
HEC-RAS study CRYSTAL CREEK.prj: CRYSTAL CREEK Base Level Engineering

--- CRYSTAL CREEK.g01 (geometry) --- (continued)

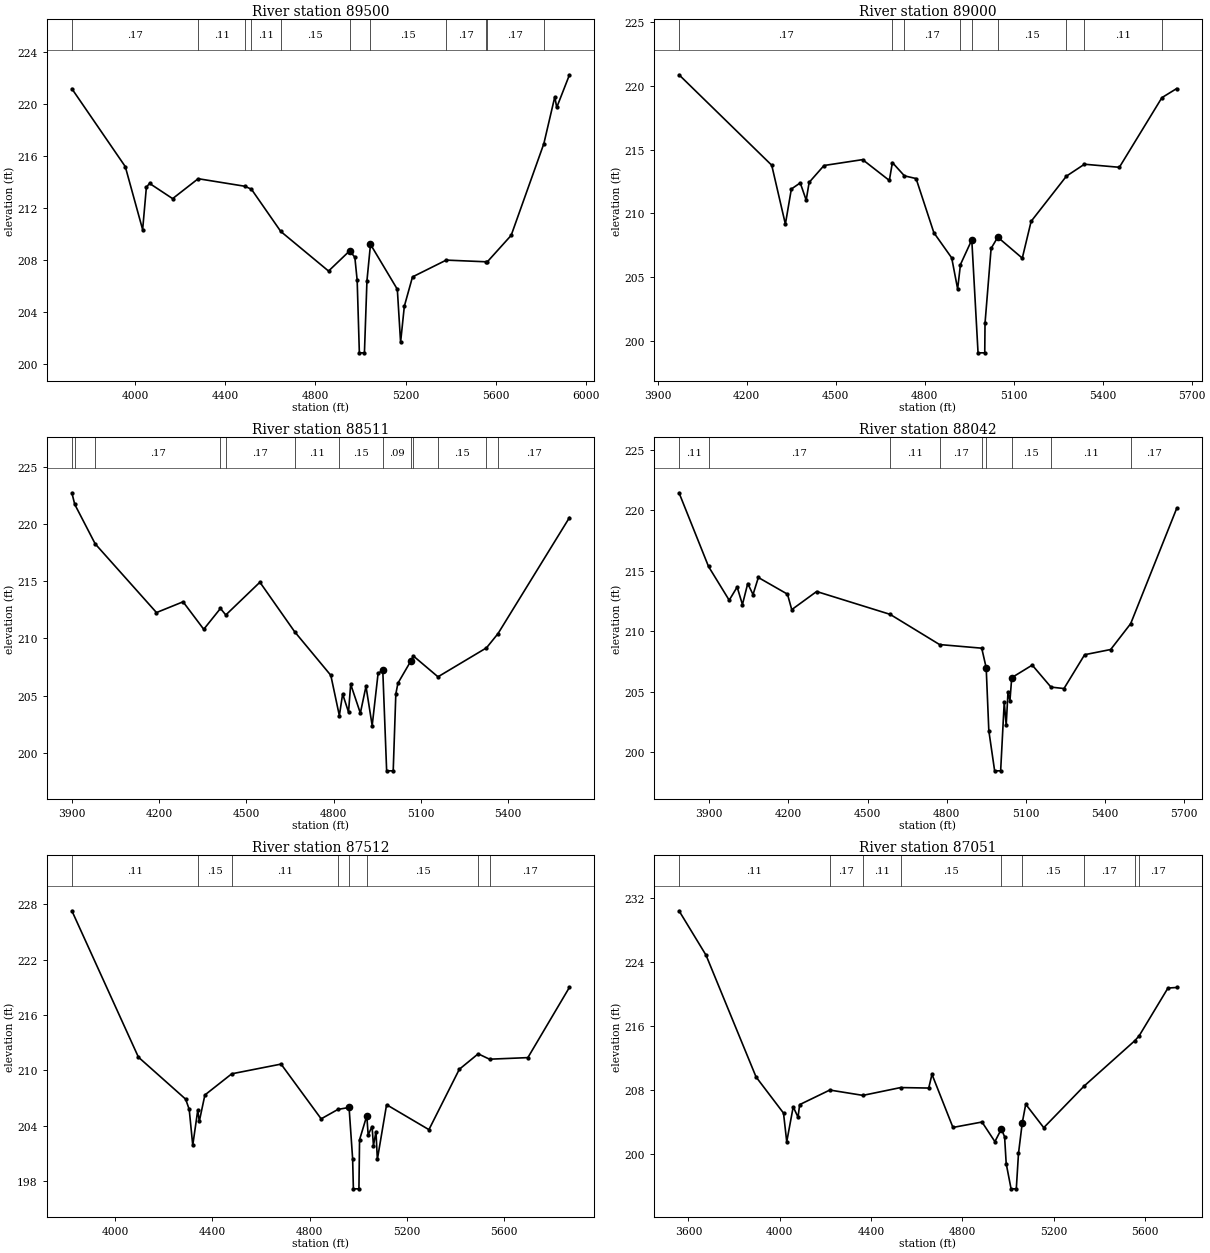
Type RM Length L Ch R = 1 ,89500   ,500,500,500
BEGIN DESCRIPTION:
CRYSTAL CREEK 178.0
END DESCRIPTION:
XS GIS Cut Line= 3
      3851032.65     10128197.99      3850763.23     10126946.56
      3851183.71     10126120.63
#Sta/Elev= 30
  3719.9  221.17  3956.8  215.19  4033.8  210.35  4050.4  213.61  4064.5   213.9
  4166.8  212.73  4280.1  214.26  4487.3  213.68  4516.4  213.45  4646.4  210.21
  4858.3  207.17  4951.8  208.72  4974.9  208.23  4985.2  206.46  4994.9  200.89
  5017.4  200.89  5028.6  206.43  5044.3  209.22  5163.3  205.77  5177.8   201.7
  5194.4  204.47  5230.6  206.72  5380.2  208.01  5557.8  207.88  5560.4  207.84
  5668.2  209.91  5813.1  216.95  5861.7  220.55  5870.2  219.73  5926.8  222.24
#Mann= 11 ,-1 , 0
  3719.9     .17       0  4280.1     .11       0  4487.3     .17       0
  4516.4     .11       0  4646.4     .15       0  4951.8     .09       0
  5044.3     .15       0  5380.2     .17       0  5557.8     .11       0
  5560.4     .17       0  5813.1     .11       0
Bank Sta=4951.8,5044.3
XS Rating Curve= 0 ,0
Exp/Cntr=0.3,0.1

Type RM Length L Ch R = 1 ,89000   ,489,489,489
BEGIN DESCRIPTION:
CRYSTAL CREEK 177.0
END DESCRIPTION:
XS GIS Cut Line= 3
      3851089.07     10128189.26      3851134.55     10127162.47
      3851431.27     10126584.71
#Sta/Elev= 30
  3972.2  220.85  4284.7  213.77  4330.7  209.16  4350.8  211.91  4380.8  212.39
  4400.8  211.04  4410.8  212.43  4460.9  213.75    4591  214.21  4681.1  212.58
  4691.4  213.98    4732  212.94  4771.2  212.73  4831.2  208.49  4891.3  206.52
  4911.3  204.09  4920.8     206    4959  207.93  4980.1  199.09  5002.7  199.09
  5003.6   201.4  5024.1  207.26  5046.5  208.14  5129.2   206.5    5159  209.38
  5278.1  212.92  5338.7  213.85  5456.4  213.61  5599.8  219.06  5649.5  219.77
#Mann= 9 ,-1 , 0
  3972.2     .17       0  4691.4     .11       0    4732     .17       0
  4920.8     .15       0    4959     .09       0  5046.5     .15       0
  5278.1     .17       0  5338.7     .11       0  5599.8     .17       0
Bank Sta=4959,5046.5
XS Rating Curve= 0 ,0
Exp/Cntr=0.3,0.1

Type RM Length L Ch R = 1 ,88511   ,469,469,469
BEGIN DESCRIPTION:
CRYSTAL CREEK 176.0
END DESCRIPTION:
XS GIS Cut Line= 3
      3851779.17     10128267.39      3851577.42     10127185.14
      3851458.26     10126584.75
#Sta/Elev= 30
  3899.1  222.71    3909   221.7  3979.4  218.25  4190.4  212.25  4281.9  213.19
  4353.1  210.79  4410.6  212.61    4429  212.04  4546.4   214.9  4665.9  210.58
  4790.5  206.77  4819.9  203.25  4831.2  205.14  4851.5  203.56  4858.9  205.99
  4892.2  203.47  4911.6  205.81  4932.9  202.38  4953.3  206.95  4969.4   207.2
  4982.7  198.43  5005.3  198.43  5014.3  205.14  5021.5  206.08  5065.3  207.99
  5074.6  208.46  5159.4  206.64  5326.4  209.17    5366  210.41  5612.1  220.55
#Mann= 13 ,-1 , 0
  3899.1     .17       0    3909     .11       0  3979.4     .17       0
  4410.6     .11       0    4429     .17       0  4665.9     .11       0
  4819.9     .15       0  4969.4     .09       0  5065.3     .15       0
  5074.6     .11       0  5159.4     .15       0  5326.4     .11       0
    5366     .17       0
Bank Sta=4969.4,5065.3
XS Rating Curve= 0 ,0
Exp/Cntr=0.3,0.1

Type RM Length L Ch R = 1 ,88042   ,530,530,530
BEGIN DESCRIPTION:
CRYSTAL CREEK 175.0
END DESCRIPTION:
XS GIS Cut Line= 3
      3851844.27     10128280.44      3851953.64     10127070.87
      3851501.37     10126574.67
#Sta/Elev= 30
  3785.5  221.46  3897.3  215.36  3975.6  212.57  4005.8  213.66  4025.8  212.21
  4045.9  213.95    4066  213.04  4086.1  214.45  4196.5  213.07  4212.7  211.79
    4307  213.29  4585.4   211.4  4772.9   208.9  4932.7   208.6  4949.6  206.98
  4959.6  201.77  4981.6  198.45  5004.4  198.45    5018  204.14  5025.4  202.23
  5032.2  204.95  5039.6  204.25  5046.4  206.16  5124.1   207.2  5195.1  205.38
  5244.4  205.26  5322.7  208.06  5421.4  208.49  5497.2  210.63  5671.4  220.16
#Mann= 9 ,-1 , 0
  3785.5     .11       0  3897.3     .17       0  4585.4     .11       0
  4772.9     .17       0  4932.7     .11       0  4949.6     .09       0
  5046.4     .15       0  5195.1     .11       0  5497.2     .17       0
Bank Sta=4949.6,5046.4
XS Rating Curve= 0 ,0
Exp/Cntr=0.3,0.1

Type RM Length L Ch R = 1 ,87512   ,461,461,461
BEGIN DESCRIPTION:
CRYSTAL CREEK 174.0
END DESCRIPTION:
XS GIS Cut Line= 3
      3853042.19     10127850.73      3852341.27      10126903.7
      3851581.21     10126484.49
#Sta/Elev= 30
  3821.8  227.27  4095.5  211.44  4289.6   206.9  4304.3   205.8  4318.9  201.91
  4339.4  205.69  4345.9  204.51  4368.8  207.35  4479.3  209.64    4682  210.69
  4846.9  204.77    4916  205.79  4961.7     206  4976.3  200.46  4979.4   197.2
  5002.2   197.2  5004.8  202.51  5034.5   205.1  5040.2  203.04  5056.2  203.94
    5062  201.87  5072.3  203.39    5078  200.39  5115.9   206.3    5290   203.6
    5415  210.13  5492.6   211.8  5539.2  211.22  5696.9  211.39    5868     219
#Mann= 8 ,-1 , 0
  3821.8     .11       0  4339.4     .15       0  4479.3     .11       0
    4916     .15       0  4961.7     .09       0  5034.5     .15       0
  5492.6     .11       0  5539.2     .17       0
Bank Sta=4961.7,5034.5
XS Rating Curve= 0 ,0
Exp/Cntr=0.3,0.1

Type RM Length L Ch R = 1 ,87051   ,551,551,551
BEGIN DESCRIPTION:
CRYSTAL CREEK 173.0
END DESCRIPTION:
XS GIS Cut Line= 3
      3853393.78     10127542.61      3852371.91      10126526.6
      3851671.76     10126288.61
#Sta/Elev= 30
    3559  230.46  3677.4  224.89  3896.6  209.62  4016.8  205.09    4031  201.49
  4059.3  205.87  4080.5  204.58  4087.6  206.15  4219.7  207.98  4364.7  207.31
    4530  208.29  4653.2  208.23  4667.4  209.95  4759.3  203.29  4886.6  203.97
  4943.1  201.51  4971.4  203.09  4985.6  202.12  4992.6  198.76    5014  195.59
  5036.9  195.59  5046.5  200.03  5063.1  203.89  5078.2   206.2  5157.2  203.26
  5333.7  208.47  5556.7  214.18  5575.4  214.79  5701.4  220.77  5739.5  220.84
#Mann= 9 ,-1 , 0
    3559     .11       0  4219.7     .17       0  4364.7     .11       0
    4530     .15       0  4971.4     .09       0  5063.1     .15       0
  5333.7     .17       0  5556.7     .11       0  5575.4     .17       0
Bank Sta=4971.4,5063.1
XS Rating Curve= 0 ,0
Exp/Cntr=0.3,0.1

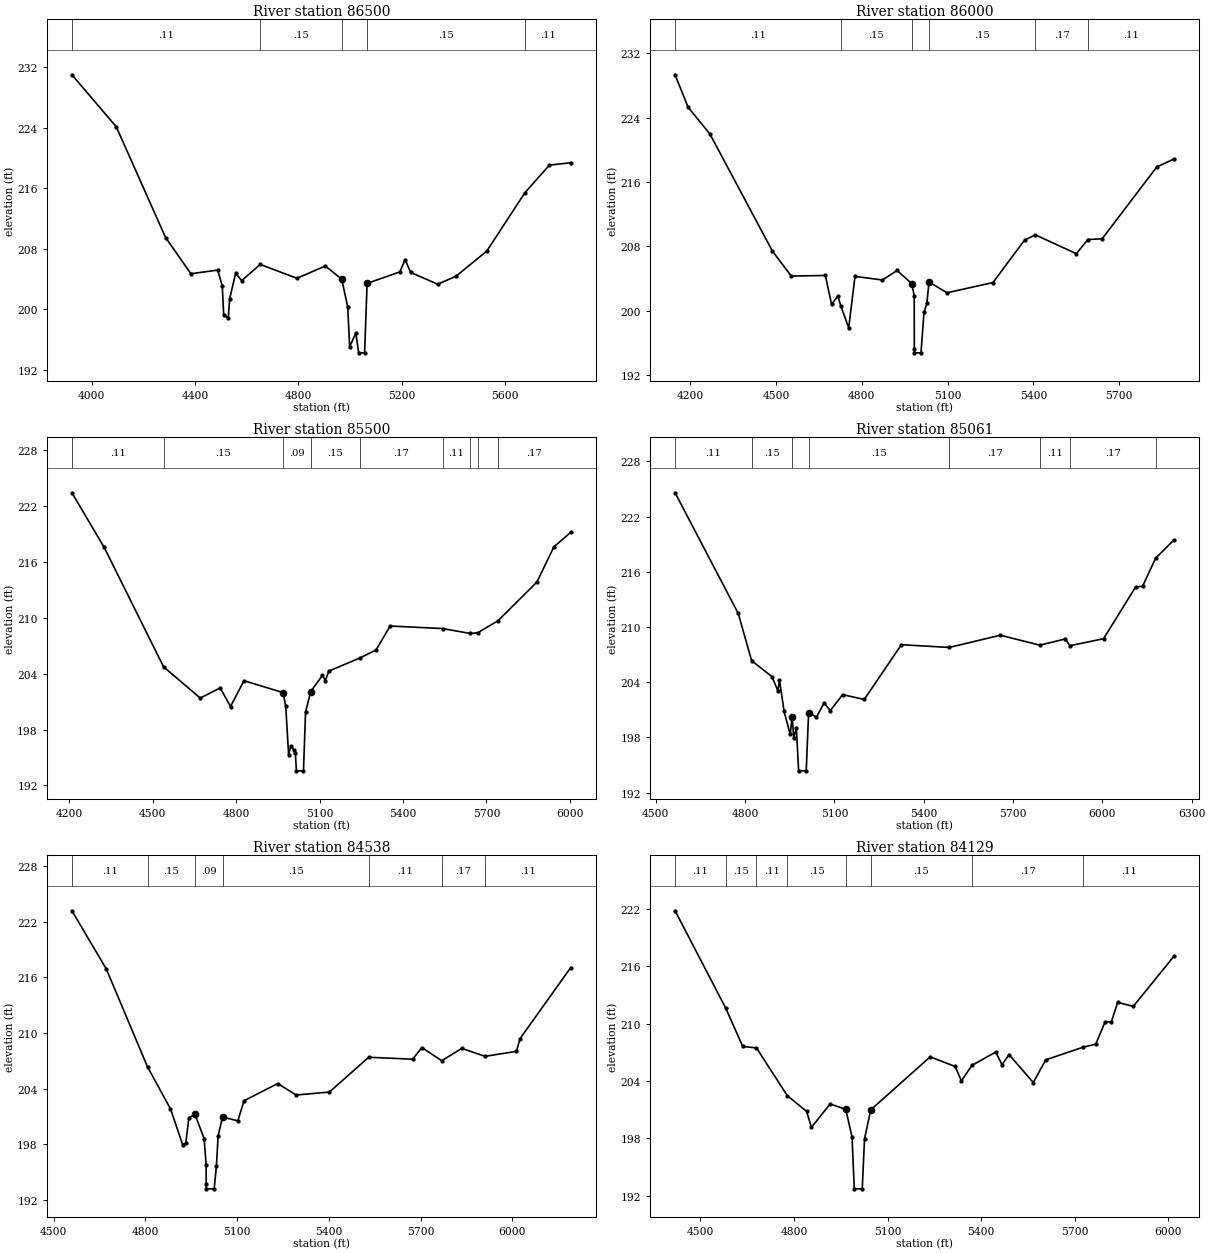
Type RM Length L Ch R = 1 ,86500   ,500,500,500
BEGIN DESCRIPTION:
CRYSTAL CREEK 172.0
END DESCRIPTION:
XS GIS Cut Line= 3
      3853602.06      10126835.1      3852620.74     10126394.25
      3851808.98       10126129.
#Sta/Elev= 30
  3924.2  231.03  4095.7  224.16  4286.5  209.51  4384.6  204.72  4488.2   205.2
  4505.9   203.1  4511.4  199.28  4529.1  198.87  4534.6  201.42  4557.7  204.79
  4580.9  203.81  4652.7  205.95  4794.9  204.12  4904.5  205.74    4968  204.01
  4991.1  200.35  4998.8  195.06  5022.6  196.87  5033.7  194.26  5056.6  194.26
  5066.2  203.44  5192.5  204.96  5213.4   206.6  5234.5   204.9  5339.7  203.33
  5410.4   204.4  5529.1  207.71  5676.9  215.44  5771.6  219.08    5854   219.4
#Mann= 5 ,-1 , 0
  3924.2     .11       0  4652.7     .15       0    4968     .09       0
  5066.2     .15       0  5676.9     .11       0
Bank Sta=4968,5066.2
XS Rating Curve= 0 ,0
Exp/Cntr=0.3,0.1

Type RM Length L Ch R = 1 ,86000   ,500,500,500
BEGIN DESCRIPTION:
CRYSTAL CREEK 171.0
END DESCRIPTION:
XS GIS Cut Line= 3
      3853584.69     10126396.72      3852835.46     10125989.81
       3851948.4     10125901.95
#Sta/Elev= 30
  4147.4  229.35  4192.8  225.32  4268.9     222  4487.4  207.44  4553.5  204.32
  4672.8  204.39  4694.6   200.8  4716.5  201.85  4726.6  200.63  4754.5  197.88
  4776.4  204.28  4872.1  203.83  4923.7  205.01  4974.5  203.39  4983.5  201.88
  4983.8  195.27  4984.3  194.77  5007.2  194.77  5017.7   199.8  5027.7  200.92
  5035.3  203.58  5098.1  202.24  5258.9  203.51  5369.4   208.8  5407.2  209.44
  5550.3   207.1  5590.6  208.86  5640.7  208.96  5831.7  217.89  5891.4  218.87
#Mann= 6 ,-1 , 0
  4147.4     .11       0  4726.6     .15       0  4974.5     .09       0
  5035.3     .15       0  5407.2     .17       0  5590.6     .11       0
Bank Sta=4974.5,5035.3
XS Rating Curve= 0 ,0
Exp/Cntr=0.3,0.1

Type RM Length L Ch R = 1 ,85500   ,439,439,439
BEGIN DESCRIPTION:
CRYSTAL CREEK 170.0
END DESCRIPTION:
XS GIS Cut Line= 3
      3853858.21     10125771.03      3853086.75     10125598.13
      3852098.16     10125428.13
#Sta/Elev= 30
  4209.4  223.41  4325.6  217.54    4539  204.73  4670.9  201.38  4742.7  202.47
  4779.7  200.47  4828.1  203.24  4968.5  201.97  4978.4  200.48  4988.6  195.31
  4996.9  196.26  5008.1   195.8  5013.1  195.44  5016.6  193.57  5042.1  193.57
  5049.6  199.87    5068  202.07  5110.5  203.83  5120.6  203.24    5133  204.27
    5244  205.67  5302.7  206.53    5354  209.11  5542.4  208.84  5641.8  208.31
  5668.8  208.39  5741.3  209.67  5881.6  213.83  5942.5   217.6  6003.1  219.16
#Mann= 9 ,-1 , 0
  4209.4     .11       0    4539     .15       0  4968.5     .09       0
    5068     .15       0    5244     .17       0  5542.4     .11       0
  5641.8     .17       0  5668.8     .11       0  5741.3     .17       0
Bank Sta=4968.5,5068
XS Rating Curve= 0 ,0
Exp/Cntr=0.3,0.1

Type RM Length L Ch R = 1 ,85061   ,523,523,523
BEGIN DESCRIPTION:
CRYSTAL CREEK 169.0
END DESCRIPTION:
XS GIS Cut Line= 3
       3853844.6     10125575.15      3853420.74     10125476.93
      3852226.53     10125141.95
#Sta/Elev= 30
  4564.9  224.59  4777.1  211.47    4822  206.34    4890  204.62  4910.3  203.06
  4915.5  204.25  4931.1  200.82  4951.6  198.32  4958.1  200.25  4963.3  197.97
  4972.2  199.01  4979.9  194.37  5005.4  194.37  5013.4   200.7  5039.8   200.2
  5065.3  201.75  5086.1  200.92  5127.6  202.65  5200.3  202.13    5325  208.08
  5485.8  207.78  5657.3  209.11    5790  208.03  5875.4   208.7  5891.4  207.97
  6004.1  208.73  6111.5  214.34  6135.1  214.43  6179.1  217.48  6240.3  219.46
#Mann= 8 ,-1 , 0
  4564.9     .11       0    4822     .15       0  4958.1     .09       0
  5013.4     .15       0  5485.8     .17       0    5790     .11       0
  5891.4     .17       0  6179.1     .11       0
Bank Sta=4958.1,5013.4
XS Rating Curve= 0 ,0
Exp/Cntr=0.3,0.1

Type RM Length L Ch R = 1 ,84538   ,409,409,409
BEGIN DESCRIPTION:
CRYSTAL CREEK 168.0
END DESCRIPTION:
XS GIS Cut Line= 3
      3854000.23     10125056.88       3853559.7     10125069.18
      3852372.59     10124971.82
#Sta/Elev= 30
  4559.3  223.21  4671.7  216.93  4806.6  206.34  4881.8   201.8  4921.8  197.91
  4931.8  198.11  4941.8  200.83  4961.8   201.2  4991.8  198.59  4998.4  195.77
  4998.6  193.66  4999.1  193.16  5024.6  193.16    5032  195.59  5037.5  198.85
    5052  200.92  5102.2  200.51  5122.3  202.68  5232.6  204.54  5292.8   203.3
  5401.6  203.62  5530.3  207.38  5674.1  207.17  5704.2  208.43  5769.2     207
  5834.6  208.34  5910.9  207.48  6013.5  208.02  6025.3  209.39  6191.1  217.07
#Mann= 7 ,-1 , 0
  4559.3     .11       0  4806.6     .15       0  4961.8     .09       0
    5052     .15       0  5530.3     .11       0  5769.2     .17       0
  5910.9     .11       0
Bank Sta=4961.8,5052
XS Rating Curve= 0 ,0
Exp/Cntr=0.3,0.1

Type RM Length L Ch R = 1 ,84129   ,698,698,698
BEGIN DESCRIPTION:
CRYSTAL CREEK 167.0
END DESCRIPTION:
XS GIS Cut Line= 3
      3854024.57     10124788.06      3853443.81     10124771.51
       3852427.9     10124718.33
#Sta/Elev= 30
    4419  221.79  4581.2  211.61  4635.8   207.6  4679.8  207.45  4778.4  202.46
  4840.4  200.81  4855.9  199.14  4915.9  201.59  4965.9  201.02    4986  198.14
  4993.2  192.71  5018.7  192.71    5026  197.94    5046  200.97  5236.3  206.51
  5316.4  205.51  5336.4     204  5370.1  205.62  5446.6  207.02  5466.6  205.68
  5489.1  206.75  5566.7  203.83  5606.8   206.2  5726.9  207.53    5767  207.84
    5797  210.18  5817.1  210.18  5837.1  212.21  5887.2  211.79  6017.3  217.03
#Mann= 8 ,-1 , 0
    4419     .11       0  4581.2     .15       0  4679.8     .11       0
  4778.4     .15       0  4965.9     .09       0    5046     .15       0
  5370.1     .17       0  5726.9     .11       0
Bank Sta=4965.9,5046
XS Rating Curve= 0 ,0
Exp/Cntr=0.3,0.1

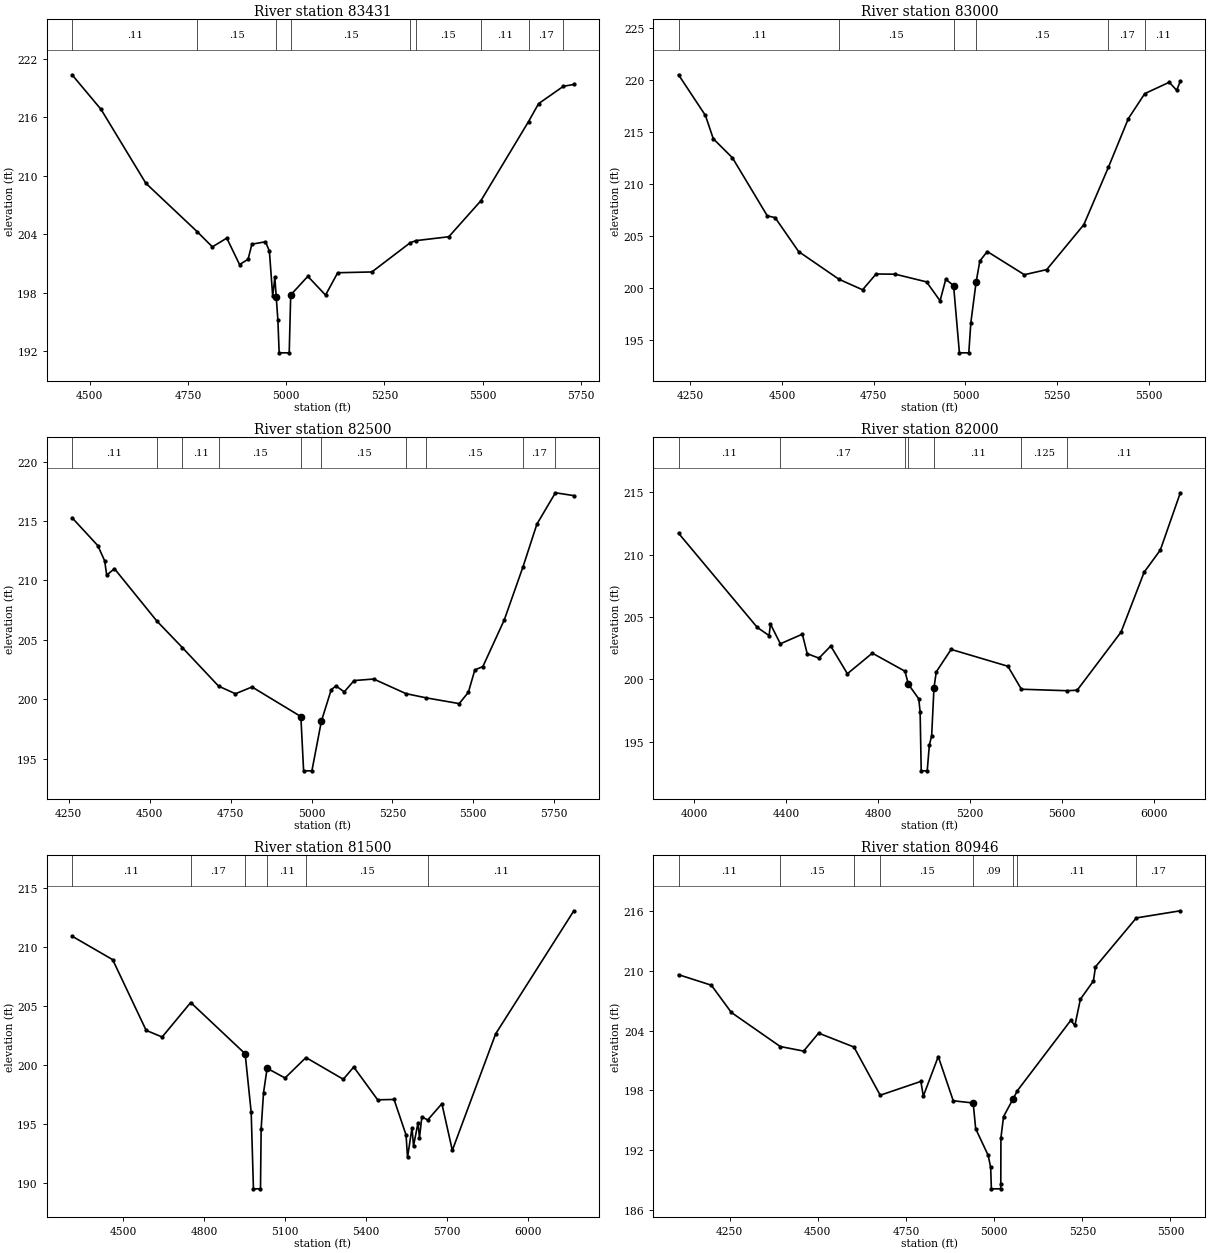
Type RM Length L Ch R = 1 ,83431   ,431,431,431
BEGIN DESCRIPTION:
CRYSTAL CREEK 166.0
END DESCRIPTION:
XS GIS Cut Line= 3
      3854051.12     10124664.49      3853548.31     10124453.97
      3852875.26     10124165.91
#Sta/Elev= 30
  4454.9  220.35  4528.7   216.8  4642.7  209.23  4773.6  204.26    4812  202.71
  4848.7  203.61  4881.2   200.9  4902.9  201.44  4912.6  202.99  4947.2  203.23
  4957.1  202.29  4965.6  197.65    4971  199.58  4974.5197.6056  4978.8  195.18
    4982  191.85  5007.6  191.85  5011.4  197.78  5054.9  199.69  5100.1  197.77
    5131  200.06    5218  200.14  5315.8  203.14  5330.3  203.35  5413.8  203.75
  5495.3  207.43  5616.8  215.56  5642.3  217.39  5705.5  219.17  5732.1  219.36
#Mann= 9 ,-1 , 0
  4454.9     .11       0  4773.6     .15       0  4974.5     .09       0
  5011.4     .15       0  5315.8     .11       0  5330.3     .15       0
  5495.3     .11       0  5616.8     .17       0  5705.5     .11       0
Bank Sta=4974.5,5011.4
XS Rating Curve= 0 ,0
Exp/Cntr=0.3,0.1

Type RM Length L Ch R = 1 ,83000   ,500,500,500
BEGIN DESCRIPTION:
CRYSTAL CREEK 165.0
END DESCRIPTION:
XS GIS Cut Line= 3
      3854154.83     10124494.57      3853486.65     10124088.49
      3852907.98     10123998.02
#Sta/Elev= 30
  4218.1  220.46  4291.4  216.55  4312.8  214.31    4365  212.48    4460   206.9
  4481.3  206.73  4545.3  203.47  4655.5   200.8  4719.7  199.79  4756.5  201.31
  4808.8  201.29  4894.1  200.55  4930.9  198.73  4946.4   200.8  4967.7   200.2
  4983.6  193.73  5009.2  193.73  5014.8  196.64  5029.1  200.52  5039.3  202.56
  5059.5  203.47  5160.7  201.24  5221.5  201.73  5322.7  206.05  5389.6  211.56
  5444.1  216.25  5488.8  218.65  5555.5  219.74  5575.7  218.97  5585.7  219.84
#Mann= 6 ,-1 , 0
  4218.1     .11       0  4655.5     .15       0  4967.7     .09       0
  5029.1     .15       0  5389.6     .17       0  5488.8     .11       0
Bank Sta=4967.7,5029.1
XS Rating Curve= 0 ,0
Exp/Cntr=0.3,0.1

Type RM Length L Ch R = 1 ,82500   ,500,500,500
BEGIN DESCRIPTION:
CRYSTAL CREEK 164.0
END DESCRIPTION:
XS GIS Cut Line= 3
      3854377.41     10124120.98      3853758.17      10123716.2
      3852954.67     10123823.25
#Sta/Elev= 30
  4260.2  215.28  4339.8  212.93  4360.9  211.65  4367.2  210.45  4391.1  210.99
  4522.2  206.58  4601.2  204.34    4713   201.1    4765  200.46  4816.3  201.03
  4967.1  198.54  4975.6  193.97  5001.2  193.97  5030.6  198.16  5060.9   200.8
  5075.4  201.12  5101.2  200.62  5131.5  201.57    5192   201.7  5291.9  200.47
  5353.4  200.12  5456.3  199.63  5484.6  200.58  5504.7  202.47  5529.5  202.75
  5595.5  206.67  5653.5  211.15  5696.4  214.74  5753.6  217.38  5810.6  217.14
#Mann= 10 ,-1 , 0
  4260.2     .11       0  4522.2     .15       0  4601.2     .11       0
    4713     .15       0  4967.1     .09       0  5030.6     .15       0
  5291.9     .11       0  5353.4     .15       0  5653.5     .17       0
  5753.6     .11       0
Bank Sta=4967.1,5030.6
XS Rating Curve= 0 ,0
Exp/Cntr=0.3,0.1

Type RM Length L Ch R = 1 ,82000   ,500,500,500
BEGIN DESCRIPTION:
CRYSTAL CREEK 163.0
END DESCRIPTION:
XS GIS Cut Line= 3
      3854639.72     10123853.76      3853750.15     10123264.92
      3852641.18     10123180.14
#Sta/Elev= 30
  3933.2  211.71  4275.2  204.16  4326.4  203.51  4332.4  204.43  4375.4  202.85
  4470.8  203.62  4491.9  202.06    4543   201.7  4594.2  202.67  4666.4  200.45
  4774.7   202.1  4916.6  200.65  4931.1  199.61  4976.3  198.44  4982.3  197.39
    4987  192.67  5013.1  192.67  5022.4  194.74  5032.4  195.48  5042.4  199.32
  5052.4   200.6  5116.9   202.4  5363.4  201.05    5422  199.21  5619.4  199.09
  5664.2  199.13  5854.8  203.79  5955.1  208.59  6025.3  210.36  6112.2  214.95
#Mann= 7 ,-1 , 0
  3933.2     .11       0  4375.4     .17       0  4916.6     .15       0
  4931.1     .09       0  5042.4     .11       0    5422    .125       0
  5619.4     .11       0
Bank Sta=4931.1,5042.4
XS Rating Curve= 0 ,0
Exp/Cntr=0.3,0.1

Type RM Length L Ch R = 1 ,81500   ,554,554,554
BEGIN DESCRIPTION:
CRYSTAL CREEK 162.0
END DESCRIPTION:
XS GIS Cut Line= 3
       3854794.1     10123509.88      3854195.65     10123169.86
      3853158.71     10122631.43
#Sta/Elev= 30
  4311.7  210.94  4461.9  208.95  4585.9  202.96    4645   202.4  4750.7  205.32
  4952.1  200.98  4974.5  196.01  4982.8  189.54  5008.9  189.54  5011.3  194.63
  5020.1  197.67  5033.4  199.75  5099.8  198.93  5177.1  200.66  5315.3  198.82
  5353.9  199.86  5442.4  197.08  5503.1  197.11  5547.4  194.11    5553   192.2
  5569.5  194.71  5575.1  193.17  5591.6  195.12  5597.2  193.87    5606  195.64
  5627.5  195.37  5680.1  196.75  5718.7   192.8  5879.1  202.67  6168.4  213.09
#Mann= 6 ,-1 , 0
  4311.7     .11       0  4750.7     .17       0  4952.1     .09       0
  5033.4     .11       0  5177.1     .15       0  5627.5     .11       0
Bank Sta=4952.1,5033.4
XS Rating Curve= 0 ,0
Exp/Cntr=0.3,0.1

Type RM Length L Ch R = 1 ,80946   ,446,446,446
BEGIN DESCRIPTION:
CRYSTAL CREEK 161.0
END DESCRIPTION:
XS GIS Cut Line= 3
      3854930.01     10123360.57      3854294.34     10122730.54
      3853841.14     10122459.81
#Sta/Elev= 30
    4105  209.63  4198.1  208.57  4254.7  205.83  4393.5   202.4  4459.8  201.94
  4502.2  203.75  4602.4  202.35  4676.9   197.5  4792.1  198.89  4799.1  197.41
  4841.5  201.39    4884  196.94  4940.5  196.72  4947.6  194.13    4983  191.45
  4990.1  190.23  4992.1  188.08  5018.3  188.08  5018.8  188.58  5019.2  193.21
  5026.6  195.35  5054.1  197.16  5065.9  197.96  5217.2  205.03  5228.9  204.52
  5244.5  207.16  5281.5     209  5287.3  210.42  5403.1  215.34  5527.9  216.06
#Mann= 8 ,-1 , 0
    4105     .11       0  4393.5     .15       0  4602.4     .17       0
  4676.9     .15       0  4940.5     .09       0  5054.1     .15       0
  5065.9     .11       0  5403.1     .17       0
Bank Sta=4940.5,5054.1
XS Rating Curve= 0 ,0
Exp/Cntr=0.3,0.1