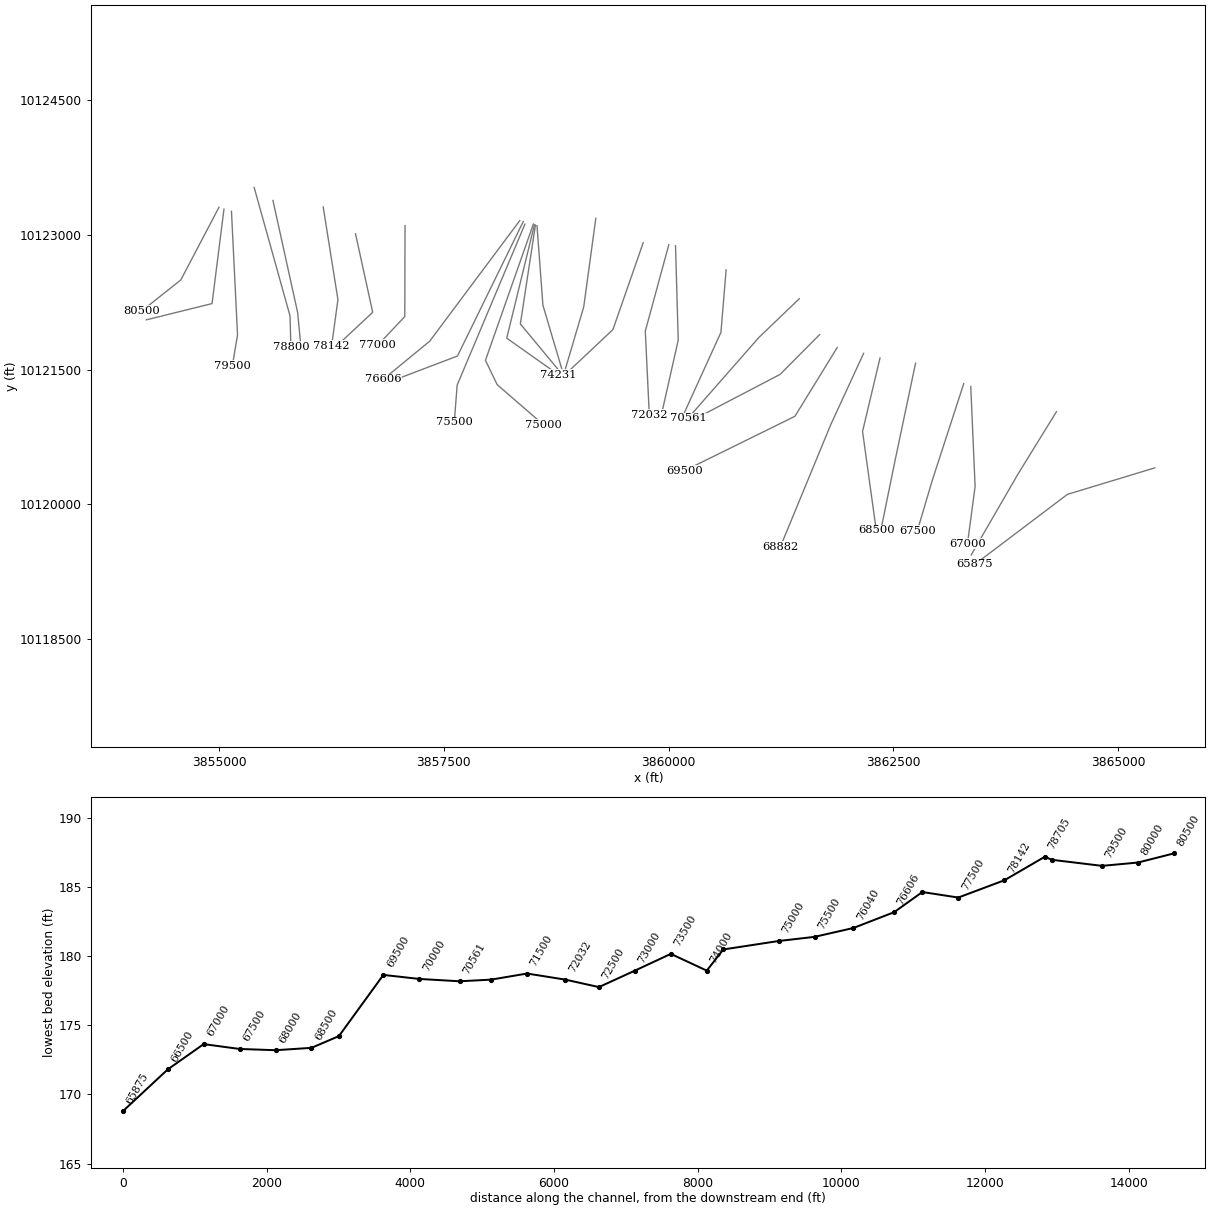
HEC-RAS study CRYSTAL CREEK.prj: CRYSTAL CREEK Base Level Engineering

--- CRYSTAL CREEK.g01 (geometry) --- (continued)

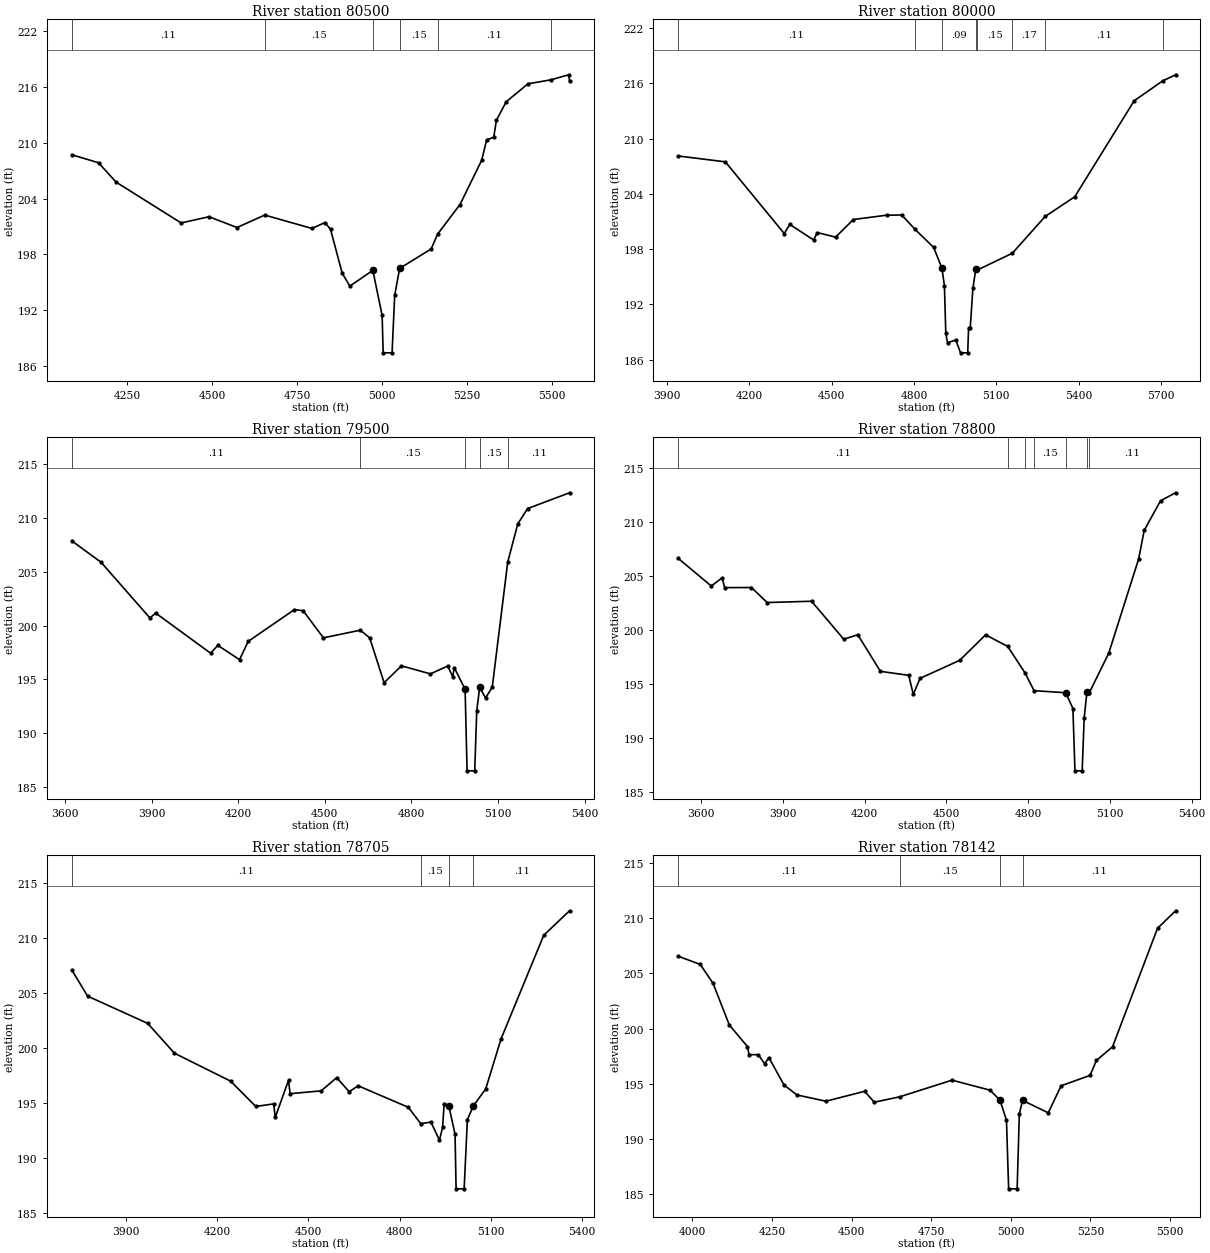
Type RM Length L Ch R = 1 ,80500   ,500,500,500
BEGIN DESCRIPTION:
CRYSTAL CREEK 160.0
END DESCRIPTION:
XS GIS Cut Line= 3
       3854999.2     10123306.04      3854574.71     10122496.82
      3854142.23     10122153.79
#Sta/Elev= 30
  4086.2  208.73  4164.8  207.87    4216   205.8    4408  201.39    4490  202.06
  4572.6   200.9  4654.2  202.24  4793.2   200.8  4831.6  201.43    4848  200.71
  4882.3  195.99  4904.9  194.59  4972.6  196.29    5000  191.45  5003.1  187.41
  5029.3  187.41    5037  193.59  5051.5   196.5  5144.4  198.59  5163.6   200.2
  5229.3  203.37  5293.4  208.15  5307.8  210.34  5328.6  210.61  5336.7  212.45
  5365.5  214.44  5429.6  216.37  5496.3  216.79  5549.8  217.34    5552  216.64
#Mann= 6 ,-1 , 0
  4086.2     .11       0  4654.2     .15       0  4972.6     .09       0
  5051.5     .15       0  5163.6     .11       0  5496.3     .17       0
Bank Sta=4972.6,5051.5
XS Rating Curve= 0 ,0
Exp/Cntr=0.3,0.1

Type RM Length L Ch R = 1 ,80000   ,500,500,500
BEGIN DESCRIPTION:
CRYSTAL CREEK 159.0
END DESCRIPTION:
XS GIS Cut Line= 3
      3855054.75      10123285.2      3854922.19     10122233.92
      3854191.48     10122052.89
#Sta/Elev= 30
  3940.4  208.12  4113.2  207.48  4327.6   199.7  4347.7  200.69  4434.3  199.01
  4448.5   199.8  4514.6  199.31  4579.5  201.22  4700.5  201.69  4755.4  201.71
  4803.9  200.16  4871.8  198.19  4902.1  195.92    4911  194.02    4916   188.9
  4922.2  187.85  4952.5  188.14  4969.6  186.75  4995.8  186.75  4998.9  189.41
  5004.8  189.41  5014.8  193.77  5025.1  195.81    5031  195.74  5158.3  197.56
  5277.8  201.55  5385.7  203.69    5602  214.11    5706  216.27  5752.8  216.93
#Mann= 8 ,-1 , 0
  3940.4     .11       0  4803.9     .15       0  4902.1     .09       0
  5025.1     .11       0    5031     .15       0  5158.3     .17       0
  5277.8     .11       0    5706     .17       0
Bank Sta=4902.1,5025.1
XS Rating Curve= 0 ,0
Exp/Cntr=0.3,0.1

Type RM Length L Ch R = 1 ,79500   ,700,700,700
BEGIN DESCRIPTION:
CRYSTAL CREEK 158.0
END DESCRIPTION:
XS GIS Cut Line= 3
      3855138.08     10123260.91      3855205.52     10121886.67
      3855148.83     10121544.13
#Sta/Elev= 30
  3624.1  207.88  3725.2  205.89  3894.3  200.72  3914.3  201.17  4104.5  197.44
  4129.5  198.17  4204.6  196.84  4234.7  198.54  4394.9   201.5  4424.9  201.39
    4495  198.87  4622.6  199.58  4655.2  198.87  4705.2   194.7  4765.3  196.27
  4865.4  195.52  4925.5  196.25    4943  195.24    4948  196.11  4985.6  194.08
  4992.4  186.51  5018.9  186.51  5025.9  192.09  5036.1  194.27  5056.4  193.28
  5079.6  194.28  5133.1   205.9  5167.8  209.45  5201.7  210.88  5347.2  212.35
#Mann= 5 ,-1 , 0
  3624.1     .11       0  4622.6     .15       0  4985.6     .09       0
  5036.1     .15       0  5133.1     .11       0
Bank Sta=4985.6,5036.1
XS Rating Curve= 0 ,0
Exp/Cntr=0.3,0.1

Type RM Length L Ch R = 1 ,78800   ,95,95,95
BEGIN DESCRIPTION:
CRYSTAL CREEK 157.0
END DESCRIPTION:
XS GIS Cut Line= 3
      3855390.62     10123526.55      3855789.47     10122096.64
      3855798.96     10121755.87
#Sta/Elev= 30
  3515.5  206.64    3638  204.06  3677.4  204.81  3687.3  203.91  3785.1  203.92
    3843  202.53  4005.8  202.65  4123.9  199.13  4175.2  199.55  4258.3  196.16
  4362.1  195.79  4378.8  194.03  4403.6  195.51    4549  197.18    4644  199.54
  4725.1  198.47  4789.1     196  4821.9  194.37  4938.2  194.18  4964.3  192.72
  4971.8  186.95  4998.3  186.95  5005.6  191.82  5015.6  194.22  5023.5  194.13
  5095.6  197.83  5205.6  206.58  5225.7  209.21  5285.7  211.95  5340.9  212.69
#Mann= 7 ,-1 , 0
  3515.5     .11       0  4725.1     .15       0  4789.1     .11       0
  4821.9     .15       0  4938.2     .09       0  5015.6     .15       0
  5023.5     .11       0
Bank Sta=4938.2,5015.6
XS Rating Curve= 0 ,0
Exp/Cntr=0.3,0.1

Type RM Length L Ch R = 1 ,78705   ,563,563,563
BEGIN DESCRIPTION:
CRYSTAL CREEK 156.0
END DESCRIPTION:
XS GIS Cut Line= 3
      3855599.64     10123381.67      3855874.39     10122133.45
      3855908.33     10121776.56
#Sta/Elev= 30
  3721.9  207.08  3773.7  204.71  3971.4  202.23  4058.9  199.52  4244.1  196.97
  4326.6  194.67  4385.5   194.9  4390.6  193.67  4434.4  197.05  4439.5  195.83
  4541.7  196.09  4592.9  197.29  4633.8  196.01  4663.3  196.55  4828.4  194.59
  4869.2   193.1  4902.5  193.25  4930.8   191.6    4941  192.77  4946.2  194.93
  4961.5  194.72    4982  192.13  4985.4  187.17  5011.9  187.17  5022.5  193.46
  5042.6  194.74  5082.8  196.26    5133   200.8  5273.6  210.25  5358.5  212.48
#Mann= 4 ,-1 , 0
  3721.9     .11       0  4869.2     .15       0  4961.5     .09       0
  5042.6     .11       0
Bank Sta=4961.5,5042.6
XS Rating Curve= 0 ,0
Exp/Cntr=0.3,0.1

Type RM Length L Ch R = 1 ,78142   ,642,642,642
BEGIN DESCRIPTION:
CRYSTAL CREEK 155.0
END DESCRIPTION:
XS GIS Cut Line= 3
      3856158.34     10123310.36      3856322.41     10122277.71
      3856252.26     10121764.78
#Sta/Elev= 30
  3954.4  206.56  4024.6  205.81  4065.1  204.08  4115.7  200.33  4172.9  198.36
  4177.9  197.63  4206.8  197.63  4227.1   196.8  4240.2  197.36  4287.8  194.88
  4328.3  193.98  4419.4  193.41    4541  194.31  4571.3  193.32  4651.1  193.81
  4815.5  195.32  4934.9  194.41  4966.2  193.51  4986.5  191.68  4993.3  185.47
    5020  185.47  5026.9  192.26    5037  193.49  5117.7  192.36  5158.1  194.81
  5248.9  195.75  5269.1  197.11  5319.6  198.34  5460.9  209.08  5517.7  210.67
#Mann= 4 ,-1 , 0
  3954.4     .11       0  4651.1     .15       0  4966.2     .09       0
    5037     .11       0
Bank Sta=4966.2,5037
XS Rating Curve= 0 ,0
Exp/Cntr=0.3,0.1

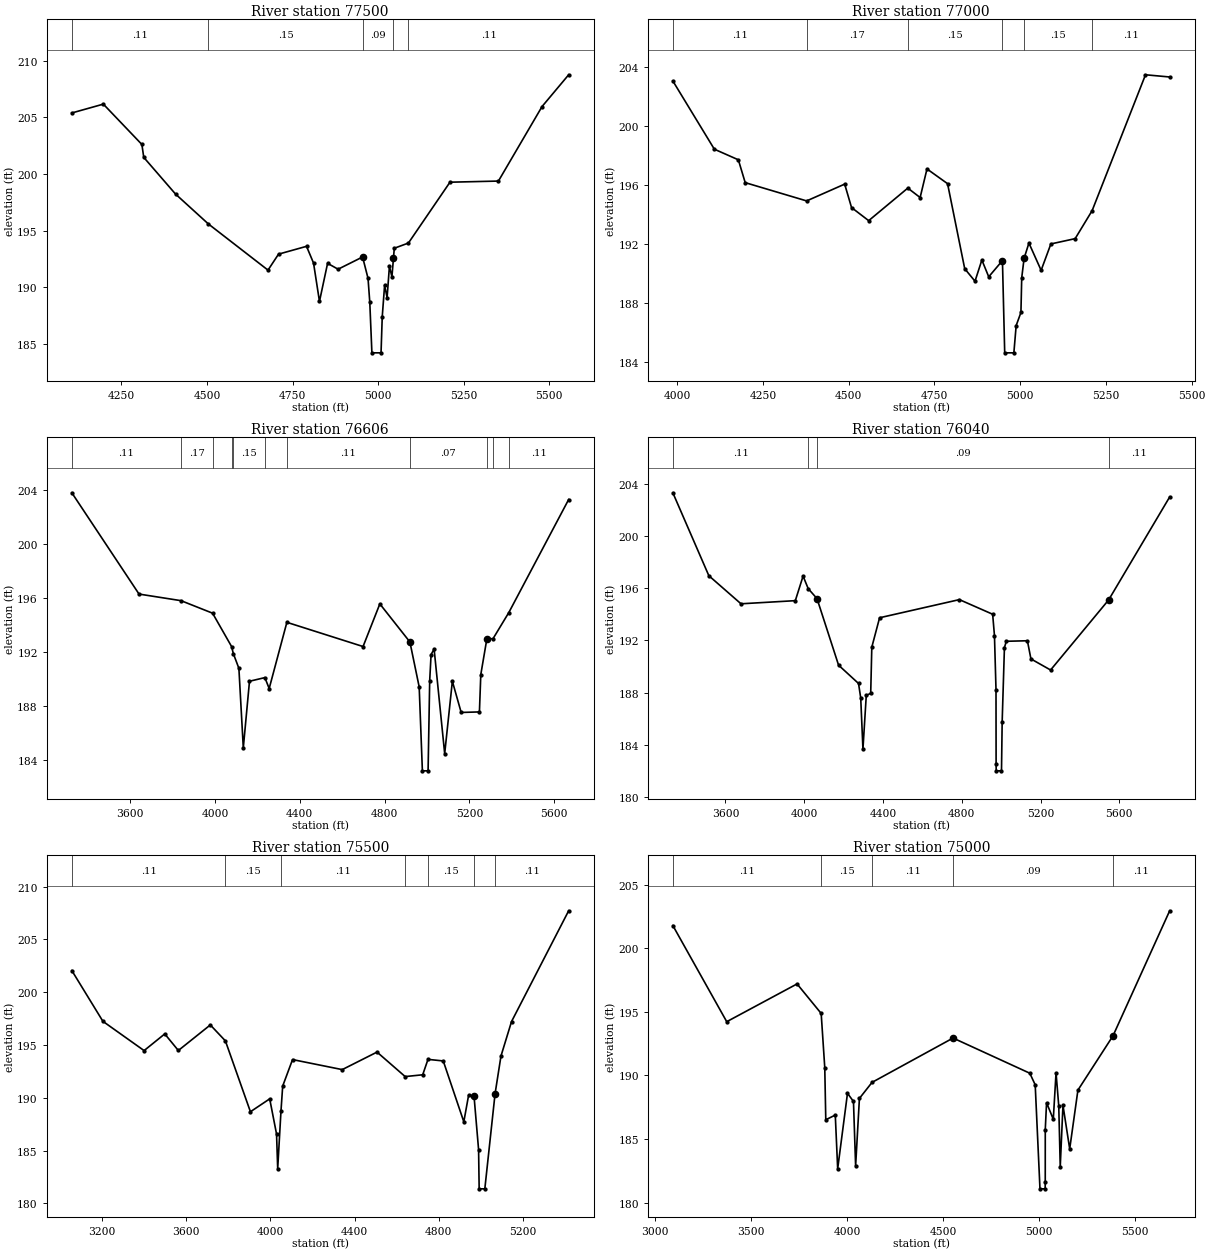
Type RM Length L Ch R = 1 ,77500   ,500,500,500
BEGIN DESCRIPTION:
CRYSTAL CREEK 154.0
END DESCRIPTION:
XS GIS Cut Line= 3
      3856517.85     10123011.08      3856709.03     10122136.84
       3856302.4     10121756.47
#Sta/Elev= 30
  4105.1  205.39  4197.2  206.17  4309.8  202.61  4315.3  201.47  4408.2  198.23
  4503.9   195.6  4678.3  191.52  4709.1  192.93  4790.9  193.62  4811.4  192.14
  4828.7  188.76  4852.4  192.12  4883.1   191.6  4954.7  192.68  4970.6  190.79
  4975.7  188.69  4981.9  184.22  5008.6  184.22  5012.1   187.4    5019  190.18
  5026.3   189.1  5033.1  191.86  5040.4  190.93  5044.9192.5735  5047.3  193.45
  5088.6  193.91    5210  199.28  5351.6  199.38  5479.1  205.96  5556.8  208.76
#Mann= 5 ,-1 , 0
  4105.1     .11       0  4503.9     .15       0  4954.7     .09       0
  5044.9     .15       0  5088.6     .11       0
Bank Sta=4954.7,5044.9
XS Rating Curve= 0 ,0
Exp/Cntr=0.3,0.1

Type RM Length L Ch R = 1 ,77000   ,394,394,394
BEGIN DESCRIPTION:
CRYSTAL CREEK 153.0
END DESCRIPTION:
XS GIS Cut Line= 3
      3857068.93     10123102.05      3857065.93     10122089.36
      3856766.88     10121772.22
#Sta/Elev= 30
  3987.3  203.07  4108.3  198.44  4178.3  197.72  4198.3  196.17  4377.4  194.93
  4488.3  196.07  4508.3  194.48  4558.3  193.59  4672.4   195.8  4708.3  195.16
  4728.3   197.1  4788.3   196.1  4838.3  190.33  4868.3  189.48  4888.3  190.92
  4908.3  189.78  4948.3  190.88  4954.9  184.62  4981.6  184.62  4988.3  186.47
  5002.2  187.36  5004.5  189.71  5011.4  191.03  5025.5  192.07  5061.1  190.22
  5089.5  192.01  5160.3  192.37  5209.8  194.27  5365.4  203.49  5435.9  203.34
#Mann= 6 ,-1 , 0
  3987.3     .11       0  4377.4     .17       0  4672.4     .15       0
  4948.3     .09       0  5011.4     .15       0  5209.8     .11       0
Bank Sta=4948.3,5011.4
XS Rating Curve= 0 ,0
Exp/Cntr=0.3,0.1

Type RM Length L Ch R = 1 ,76606   ,566,566,566
BEGIN DESCRIPTION:
CRYSTAL CREEK 152.0
END DESCRIPTION:
XS GIS Cut Line= 3
      3858344.65     10123157.27      3857342.38     10121814.48
      3856825.87     10121390.24
#Sta/Elev= 30
  3324.4  203.83  3641.5   196.3  3839.6  195.81  3988.4  194.88  4078.1   192.4
  4086.5  191.87  4112.6  190.78  4133.4  184.87  4162.6  189.82  4235.1  190.09
  4255.5  189.28    4339   194.2  4698.4   192.4  4777.6  195.57  4919.4  192.74
  4963.2   189.4  4978.3  183.16  5005.2  183.16  5012.8  189.87  5019.3   191.8
  5033.6  192.22  5083.5  184.44  5119.7  189.82  5161.3   187.5  5247.4  187.54
  5253.9  190.32  5282.6  192.98  5311.4  192.98  5386.2  194.93  5668.4  203.33
#Mann= 11 ,-1 , 0
  3324.4     .11       0  3839.6     .17       0  3988.4     .11       0
  4078.1     .17       0  4086.5     .15       0  4235.1     .17       0
    4339     .11       0  4919.4     .07       0  5282.6     .11       0
  5311.4     .15       0  5386.2     .11       0
Bank Sta=4919.4,5282.6
XS Rating Curve= 0 ,0
Exp/Cntr=0.3,0.1

Type RM Length L Ch R = 1 ,76040   ,540,540,540
BEGIN DESCRIPTION:
CRYSTAL CREEK 151.0
END DESCRIPTION:
XS GIS Cut Line= 3
      3858384.26       10123148.      3857652.27     10121650.42
      3856852.83     10121346.11
#Sta/Elev= 30
  3333.1  203.31  3515.9  196.96  3679.1  194.81  3954.9  195.05  3994.3  196.93
  4020.3  195.97    4065195.2078  4174.5  190.11  4275.8  188.71  4286.9   187.6
  4298.2  183.69  4315.1  187.79  4337.6  187.96  4343.2  191.49  4382.7  193.74
  4787.8  195.13  4956.7  194.01  4965.9  192.37  4973.7  188.24  4974.2  182.52
  4974.7  182.02  5001.6  182.02    5005  185.78  5016.5  191.46  5026.1  191.94
  5133.1  191.98    5151  190.59  5250.8  189.74  5545.7  195.11  5855.4  202.99
#Mann= 4 ,-1 , 0
  3333.1     .11       0  4020.3     .17       0    4065     .09       0
  5545.7     .11       0
Bank Sta=4065,5545.7
XS Rating Curve= 0 ,0
Exp/Cntr=0.3,0.1

Type RM Length L Ch R = 1 ,75500   ,500,500,500
BEGIN DESCRIPTION:
CRYSTAL CREEK 150.0
END DESCRIPTION:
XS GIS Cut Line= 3
      3858402.15     10123117.61      3857648.61     10121326.46
      3857616.23     10120910.52
#Sta/Elev= 30
  3056.8  202.05  3204.6  197.24  3400.2  194.47  3498.3  196.05  3562.9  194.48
  3714.8   196.9  3786.4  195.39  3905.3  188.68  3996.9   189.9  4029.4  186.57
  4034.9   183.3  4050.4  188.72  4058.6  191.11  4105.4  193.62  4341.5  192.67
  4506.8  194.33  4640.5  192.01  4723.8  192.18  4748.9  193.64  4821.4  193.49
  4919.1  187.73  4941.8  190.24  4967.6190.1634  4989.3  185.09    4992  181.38
  5018.9  181.38  5067.6  190.39  5095.7  193.96  5145.8  197.22  5417.2  207.71
#Mann= 7 ,-1 , 0
  3056.8     .11       0  3786.4     .15       0  4050.4     .11       0
  4640.5     .17       0  4748.9     .15       0  4967.6     .09       0
  5067.6     .11       0
Bank Sta=4967.6,5067.6
XS Rating Curve= 0 ,0
Exp/Cntr=0.3,0.1

Type RM Length L Ch R = 1 ,75000   ,769,769,769
BEGIN DESCRIPTION:
CRYSTAL CREEK 149.0
END DESCRIPTION:
XS GIS Cut Line= 4
      3858496.32     10123119.75      3857963.45     10121602.37
      3858093.43     10121331.69      3858607.59     10120885.75
#Sta/Elev= 30
  3091.5  201.78  3372.3  194.22  3738.8  197.19  3864.5  194.87  3883.2  190.61
  3888.5  186.51    3938  186.88  3950.5  182.66  4001.6  188.59  4032.8  187.95
    4044  182.88  4063.8  188.19  4129.6  189.45  4551.8192.9351  4951.6  190.17
  4979.8  189.26  5004.7  181.08  5031.7  181.08  5032.2  181.58  5032.3  185.74
    5039  187.85  5074.1  186.55  5088.4   190.2  5102.6  187.59  5110.3  182.83
  5124.5  187.65  5159.6  184.22  5202.4  188.84  5385.4193.1147  5680.6  202.94
#Mann= 5 ,-1 , 0
  3091.5     .11       0  3864.5     .15       0  4129.6     .11       0
  4551.8     .09       0  5385.4     .11       0
Bank Sta=4551.8,5385.4
XS Rating Curve= 0 ,0
Exp/Cntr=0.3,0.1

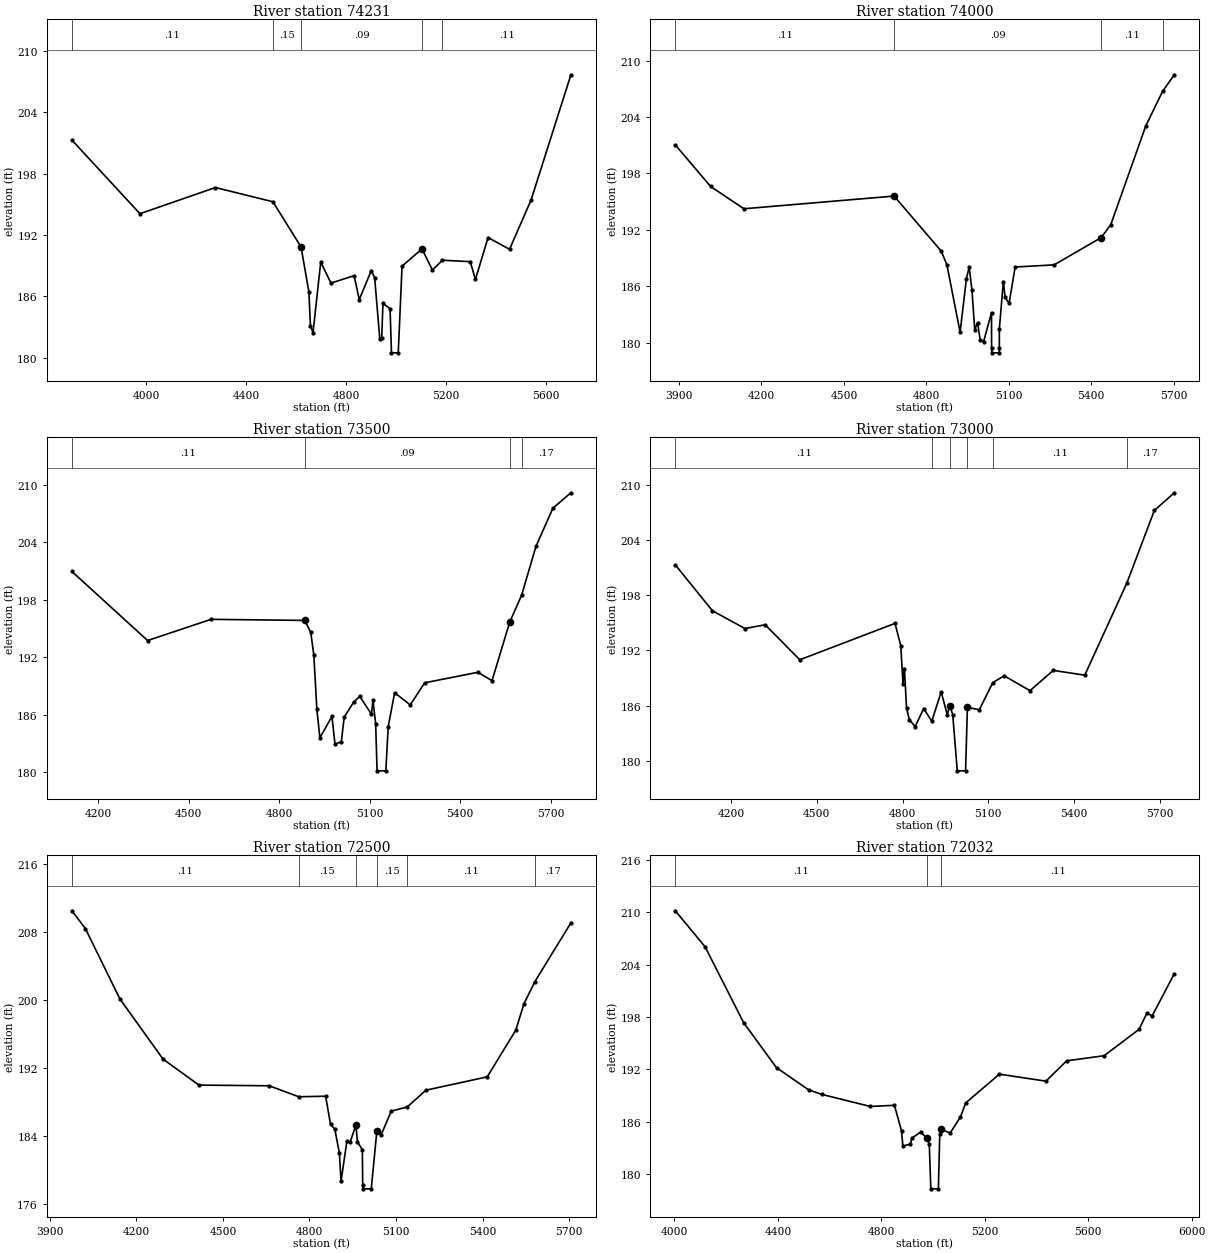
Type RM Length L Ch R = 1 ,74231   ,231,231,231
BEGIN DESCRIPTION:
CRYSTAL CREEK 148.0
END DESCRIPTION:
XS GIS Cut Line= 3
      3858507.76     10123109.81      3858200.01     10121848.62
      3858773.09      10121443.7
#Sta/Elev= 30
  3701.8  201.28  3974.4  194.08  4276.9  196.64  4507.3  195.25  4620.1190.8305
  4651.6  186.43  4657.8  183.08  4668.1  182.45    4699  189.35  4740.1  187.29
  4832.8  188.02  4853.4  185.68  4901.7  188.52  4915.1  187.82  4935.7  181.85
  4943.3  181.88  4948.5   185.3  4976.9   184.8  4982.6  180.47  5009.7  180.47
  5024.9  188.95  5104.9  190.64  5146.7  188.57  5186.6  189.53  5298.2  189.39
  5319.1  187.65  5369.6  191.75  5455.7   190.6  5541.9  195.41  5701.7  207.67
#Mann= 5 ,-1 , 0
  3701.8     .11       0  4507.3     .15       0  4620.1     .09       0
  5104.9     .15       0  5186.6     .11       0
Bank Sta=4620.1,5104.9
XS Rating Curve= 0 ,0
Exp/Cntr=0.3,0.1

Type RM Length L Ch R = 1 ,74000   ,500,500,500
BEGIN DESCRIPTION:
CRYSTAL CREEK 147.0
END DESCRIPTION:
XS GIS Cut Line= 3
      3858519.14     10123107.96      3858351.58     10122007.34
      3858799.37     10121466.97
#Sta/Elev= 30
  3886.7  201.04  4015.1  196.62  4136.4  194.25  4682.7   195.6  4854.1  189.75
  4874.8  188.28  4922.7  181.14  4945.7  186.83  4955.8  188.05  4965.9  185.58
    4976   181.4  4986.1  182.15  4995.8  180.34  5008.3  180.14    5037  183.22
  5037.3  179.44  5037.8  178.94  5064.9  178.94  5065.4  179.44  5065.6  181.52
    5080  186.51  5086.5  184.84  5100.8  184.19    5123  188.06  5264.9  188.29
  5435.5  191.18  5470.7  192.55  5598.3  203.07  5659.3  206.73  5701.8  208.49
#Mann= 4 ,-1 , 0
  3886.7     .11       0  4682.7     .09       0  5435.5     .11       0
  5659.3     .17       0
Bank Sta=4682.7,5435.5
XS Rating Curve= 0 ,0
Exp/Cntr=0.3,0.1

Type RM Length L Ch R = 1 ,73500   ,500,500,500
BEGIN DESCRIPTION:
CRYSTAL CREEK 146.0
END DESCRIPTION:
XS GIS Cut Line= 3
      3858536.67     10123101.34      3858602.43     10122215.98
      3858820.21     10121480.02
#Sta/Elev= 30
  4112.2  200.94  4363.2  193.74  4573.7  195.95  4884.6  195.84  4904.6  194.58
  4914.7   192.2  4924.7  186.58  4934.7   183.6  4974.8  185.82  4984.9  182.92
  5005.9   183.2  5015.5  185.75  5046.8  187.31  5067.2  187.92  5105.7  186.06
  5110.9  187.49  5119.8  185.04  5124.5  180.15  5153.5  180.15  5161.5  184.77
  5182.7  188.29  5234.5  187.03  5282.4  189.33  5459.2  190.43  5505.7  189.55
  5564.2  195.63  5604.1  198.48  5651.7  203.57  5707.7  207.54  5767.5  209.15
#Mann= 4 ,-1 , 0
  4112.2     .11       0  4884.6     .09       0  5564.2     .11       0
  5604.1     .17       0
Bank Sta=4884.6,5564.2
XS Rating Curve= 0 ,0
Exp/Cntr=0.3,0.1

Type RM Length L Ch R = 1 ,73000   ,500,500,500
BEGIN DESCRIPTION:
CRYSTAL CREEK 145.0
END DESCRIPTION:
XS GIS Cut Line= 3
      3859190.68     10123182.34      3859056.43     10122196.84
      3858843.65     10121477.35
#Sta/Elev= 30
  4005.4  201.29  4135.2  196.31  4248.9  194.38  4319.5  194.79  4440.7  190.99
  4773.7  194.94  4793.9  192.51  4801.6   188.4  4806.7  190.04  4814.1  185.73
  4824.2  184.46  4844.3  183.75    4874   185.7  4902.3  184.32  4935.2  187.51
  4956.4  185.04  4965.5  186.01  4975.5  185.05  4991.5  178.94  5020.5  178.94
  5026.9  185.82  5068.6  185.57  5115.8  188.52  5155.5  189.25  5245.9  187.64
    5327  189.84  5437.3  189.32    5584  199.28  5680.6  207.19  5750.3  209.11
#Mann= 6 ,-1 , 0
  4005.4     .11       0  4902.3     .15       0  4965.5     .09       0
  5026.9     .15       0  5115.8     .11       0    5584     .17       0
Bank Sta=4965.5,5026.9
XS Rating Curve= 0 ,0
Exp/Cntr=0.3,0.1

Type RM Length L Ch R = 1 ,72500   ,468,468,468
BEGIN DESCRIPTION:
CRYSTAL CREEK 144.0
END DESCRIPTION:
XS GIS Cut Line= 3
      3859717.85     10122911.08      3859381.39     10121944.99
      3858867.87     10121461.09
#Sta/Elev= 30
    3977  210.45  4023.6  208.36  4142.7  200.11  4292.8     193  4417.2  189.95
  4660.6  189.87  4762.7  188.58  4855.9  188.64  4872.9  185.33  4887.7  184.76
  4903.6  181.95  4909.2  178.64  4929.7  183.38  4940.6  183.22  4960.8  185.25
  4966.1  183.26    4983  182.37  4984.4  178.25  4984.9  177.75    5014  177.75
  5033.4  184.56  5047.6  184.04  5083.2  186.89  5138.8  187.38  5203.3  189.35
  5415.7  190.92  5514.5   196.4  5542.8   199.5    5581  202.13  5705.6  209.03
#Mann= 6 ,-1 , 0
    3977     .11       0  4762.7     .15       0  4960.8     .09       0
  5033.4     .15       0  5138.8     .11       0    5581     .17       0
Bank Sta=4960.8,5033.4
XS Rating Curve= 0 ,0
Exp/Cntr=0.3,0.1

Type RM Length L Ch R = 1 ,72032   ,532,532,532
BEGIN DESCRIPTION:
CRYSTAL CREEK 143.0
END DESCRIPTION:
XS GIS Cut Line= 3
      3860002.66     10122888.69      3859741.29     10121927.18
      3859785.78     10120995.44
#Sta/Elev= 30
  4003.6  210.18  4118.8  206.05  4267.6  197.36  4394.9  192.18  4519.3  189.64
  4570.3  189.12  4757.6  187.74  4850.9  187.87  4878.2  184.93  4883.4   183.2
  4912.8  183.42    4918  184.11  4952.6   184.8  4975.2  184.13  4985.6  183.43
  4991.5  178.29  5020.7  178.29  5026.1  184.54    5032  185.12  5066.2  184.69
  5106.2  186.54  5126.3  188.14  5256.4  191.44  5436.6  190.64  5516.7  192.97
  5661.8  193.56    5797  196.59  5827.1  198.45  5847.1  198.12  5932.8  202.95
#Mann= 3 , 0 , 0
  4003.6     .11       0  4975.2     .06       0    5032     .11       0
Bank Sta=4975.2,5032
XS Rating Curve= 0 ,0
Exp/Cntr=0.3,0.1

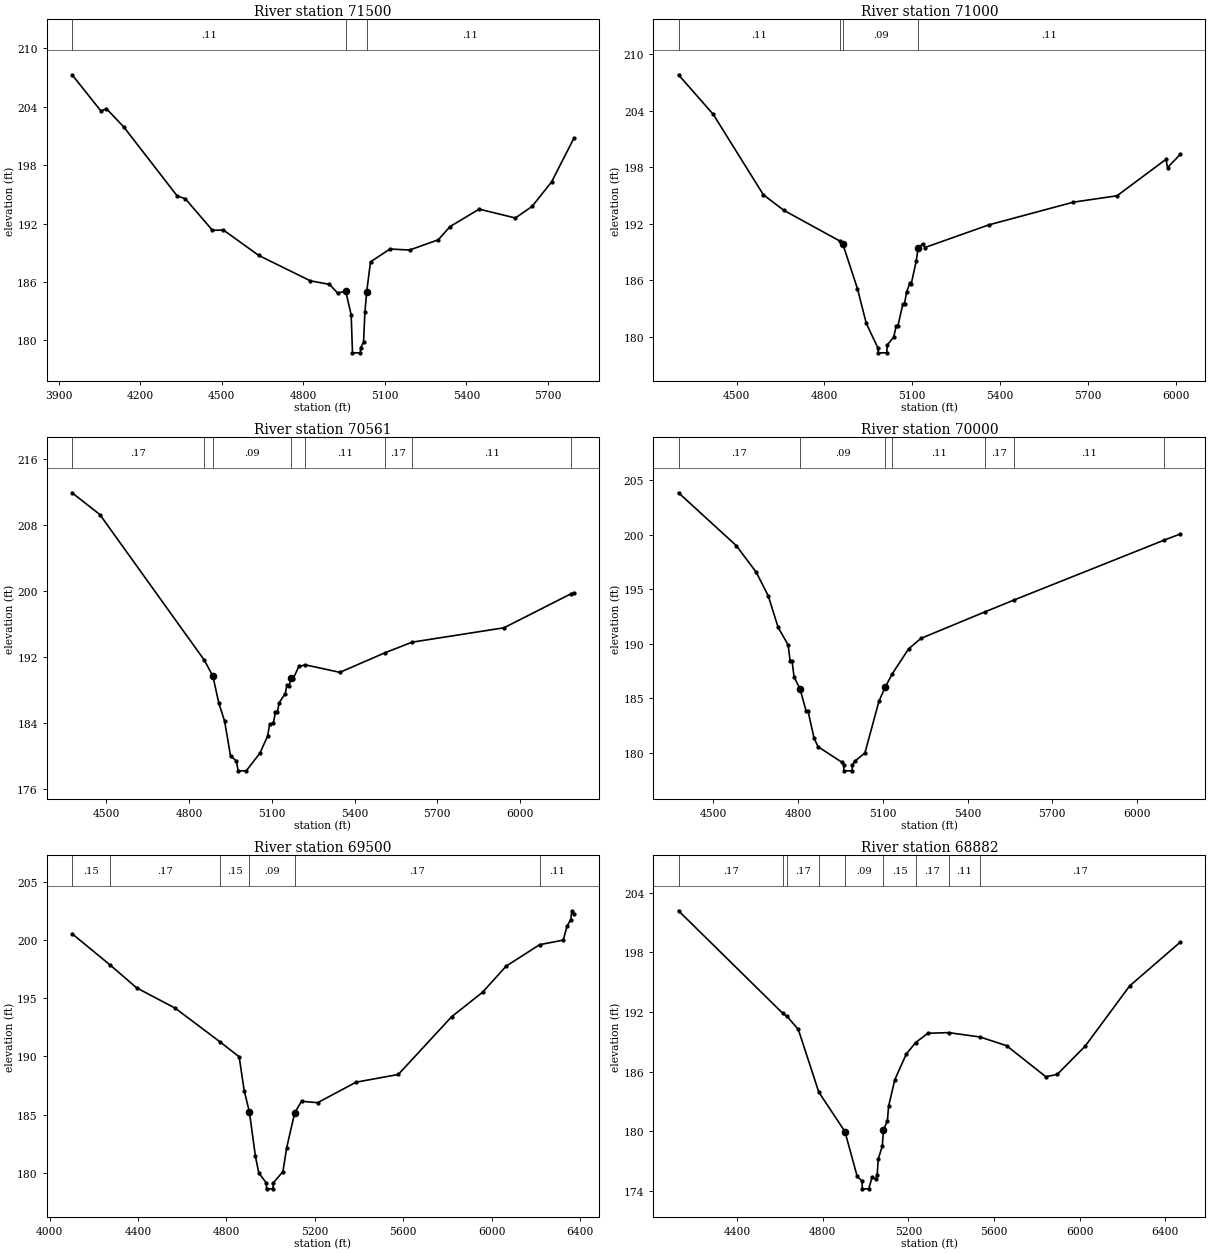
Type RM Length L Ch R = 1 ,71500   ,500,500,500
BEGIN DESCRIPTION:
CRYSTAL CREEK 142.0
END DESCRIPTION:
XS GIS Cut Line= 3
      3860077.44     10122877.41      3860107.56     10121827.24
      3859932.86     10121051.26
#Sta/Elev= 30
  3949.4  207.27  4055.8  203.55  4075.8  203.79  4139.5  201.92  4335.9  194.84
  4365.9  194.55    4466   191.3    4506  191.34    4636  188.73  4826.1  186.12
  4896.1  185.76  4926.1  184.88  4956.2  185.04  4976.2  182.63    4981  178.73
  5010.2  178.73  5010.7  179.23  5021.6  179.81  5026.8  182.96 5033.09184.9508
  5047.3  188.07  5119.1  189.39  5190.8  189.28  5296.5  190.33  5339.8  191.69
  5447.1  193.48  5580.3  192.57  5641.8  193.76  5713.6  196.28  5795.4  200.75
#Mann= 3 , 0 , 0
  3949.4     .11       0  4956.2     .09       0 5033.09     .11       0
Bank Sta=4956.2,5033.09
XS Rating Curve= 0 ,0
Exp/Cntr=0.3,0.1

Type RM Length L Ch R = 1 ,71000   ,439,439,439
BEGIN DESCRIPTION:
CRYSTAL CREEK 141.0
END DESCRIPTION:
XS GIS Cut Line= 3
      3860640.34     10122609.46      3860582.68     10121914.04
      3860162.92     10120990.57
#Sta/Elev= 30
  4302.2  207.84    4421  203.62  4591.6  195.09  4661.8  193.43    4854  190.15
  4862.5  189.88  4912.7  185.11  4942.8  181.42  4982.8  178.79  4983.3  178.29
  5012.7  178.29  5014.2  179.12  5036.2  179.96  5044.8   181.1  5050.3  181.09
  5067.9  183.51  5073.4   183.5  5080.2  184.75    5091  185.66  5096.4  185.65
  5113.1  188.01  5119.5   189.4  5135.1   189.9  5142.6  189.48  5361.2  191.89
    5649   194.3  5798.4  194.98  5965.3  198.85  5970.8  197.98  6014.4  199.39
#Mann= 4 ,-1 , 0
  4302.2     .11       0    4854     .15       0  4862.5     .09       0
  5119.5     .11       0
Bank Sta=4862.5,5119.5
XS Rating Curve= 0 ,0
Exp/Cntr=0.3,0.1

Type RM Length L Ch R = 1 ,70561   ,561,561,561
BEGIN DESCRIPTION:
CRYSTAL CREEK 140.0
END DESCRIPTION:
XS GIS Cut Line= 3
      3861453.67      10122287.7      3861003.14     10121855.09
       3860215.1     10120955.95
#Sta/Elev= 30
  4375.4  211.88  4476.2  209.24  4855.7  191.56  4886.3  189.64  4907.7  186.38
  4928.7  184.19  4950.1     180  4971.2  179.37  4977.9  178.17  5007.3  178.17
  5056.5   180.3    5085   182.4  5091.6   183.8  5105.9  183.93  5112.5  185.25
  5120.1   185.3  5126.7  186.43  5148.6  187.54  5155.2  188.59  5162.8  188.46
  5169.4  189.47    5177  189.31  5197.9  190.82  5221.5  191.02  5346.9  190.11
  5508.8  192.46    5609  193.77  5941.9  195.51    6185  199.63  6195.6  199.77
#Mann= 8 ,-1 , 0
  4375.4     .17       0  4855.7     .15       0  4886.3     .09       0
  5169.4     .15       0  5221.5     .11       0  5508.8     .17       0
    5609     .11       0    6185     .17       0
Bank Sta=4886.3,5169.4
XS Rating Curve= 0 ,0
Exp/Cntr=0.3,0.1

Type RM Length L Ch R = 1 ,70000   ,500,500,500
BEGIN DESCRIPTION:
CRYSTAL CREEK 139.0
END DESCRIPTION:
XS GIS Cut Line= 3
      3861679.93     10121887.96      3861240.41     10121445.57
      3860217.88     10120911.09
#Sta/Elev= 30
  4376.4  203.84  4580.7     199  4651.5  196.56  4693.9  194.41  4729.2  191.49
  4764.6  189.89  4771.6  188.42  4778.7  188.39  4785.8  186.92    4807  185.85
  4828.2  183.82  4835.3  183.79  4856.5  181.33  4870.6  180.55  4955.5  179.12
  4961.5  178.84    4962  178.34  4991.4  178.34  4991.9  178.84    5000  179.21
  5036.6  179.98  5086.4  184.73  5108.5  186.02    5134  187.26  5191.1  189.52
  5235.3  190.49    5462  192.92  5563.2  193.99  6097.7  199.51  6153.8  200.06
#Mann= 7 ,-1 , 0
  4376.4     .17       0    4807     .09       0  5108.5     .15       0
    5134     .11       0    5462     .17       0  5563.2     .11       0
  6097.7     .17       0
Bank Sta=4807,5108.5
XS Rating Curve= 0 ,0
Exp/Cntr=0.3,0.1

Type RM Length L Ch R = 1 ,69500   ,618,618,618
BEGIN DESCRIPTION:
CRYSTAL CREEK 138.0
END DESCRIPTION:
XS GIS Cut Line= 3
      3861876.13     10121744.93      3861405.41     10120979.13
      3860174.76     10120372.37
#Sta/Elev= 30
  4101.1  200.54  4271.1  197.89  4393.5  195.89  4567.5  194.15  4770.8  191.25
  4857.4  189.97  4880.3  187.05  4903.7  185.23  4930.8  181.43  4946.2  179.99
  4980.7  179.13  4981.2  178.63  5010.7  178.63  5011.2  179.13  5055.4  180.11
  5072.3  182.15  5108.8  185.17  5139.6  186.15  5212.6  186.03  5386.6  187.79
  5577.4  188.45  5818.9  193.41  5959.2  195.52  6065.9  197.76  6217.3   199.6
  6324.1  199.99  6340.9  201.18  6357.5  201.75  6363.4  202.51  6372.1  202.26
#Mann= 6 ,-1 , 0
  4101.1     .15       0  4271.1     .17       0  4770.8     .15       0
  4903.7     .09       0  5108.8     .17       0  6217.3     .11       0
Bank Sta=4903.7,5108.8
XS Rating Curve= 0 ,0
Exp/Cntr=0.3,0.1

Type RM Length L Ch R = 1 ,68882   ,382,382,382
BEGIN DESCRIPTION:
CRYSTAL CREEK 137.0
END DESCRIPTION:
XS GIS Cut Line= 3
      3862169.54     10121679.67      3861803.61     10120885.19
      3861243.21     10119525.23
#Sta/Elev= 30
  4125.3  202.17  4612.9  191.85    4633  191.54  4685.2  190.24    4781  183.93
  4903.1  179.97  4960.5  175.46    4983     175  4984.6  174.21  5014.4  174.21
  5029.9  175.36  5047.7  175.17  5053.8  175.64  5059.2  177.26  5077.7  178.48
  5083.2  180.09  5101.7  181.08  5107.1   182.5  5136.4   185.2  5189.7  187.75
  5233.5  188.92  5290.9  189.85  5387.5  189.92  5534.3  189.48  5658.5  188.61
  5842.3  185.48  5895.6  185.72  6026.1  188.56  6233.8  194.61  6470.9  199.02
#Mann= 9 ,-1 , 0
  4125.3     .17       0  4612.9     .11       0    4633     .17       0
    4781     .15       0  4903.1     .09       0  5083.2     .15       0
  5233.5     .17       0  5387.5     .11       0  5534.3     .17       0
Bank Sta=4903.1,5083.2
XS Rating Curve= 0 ,0
Exp/Cntr=0.3,0.1

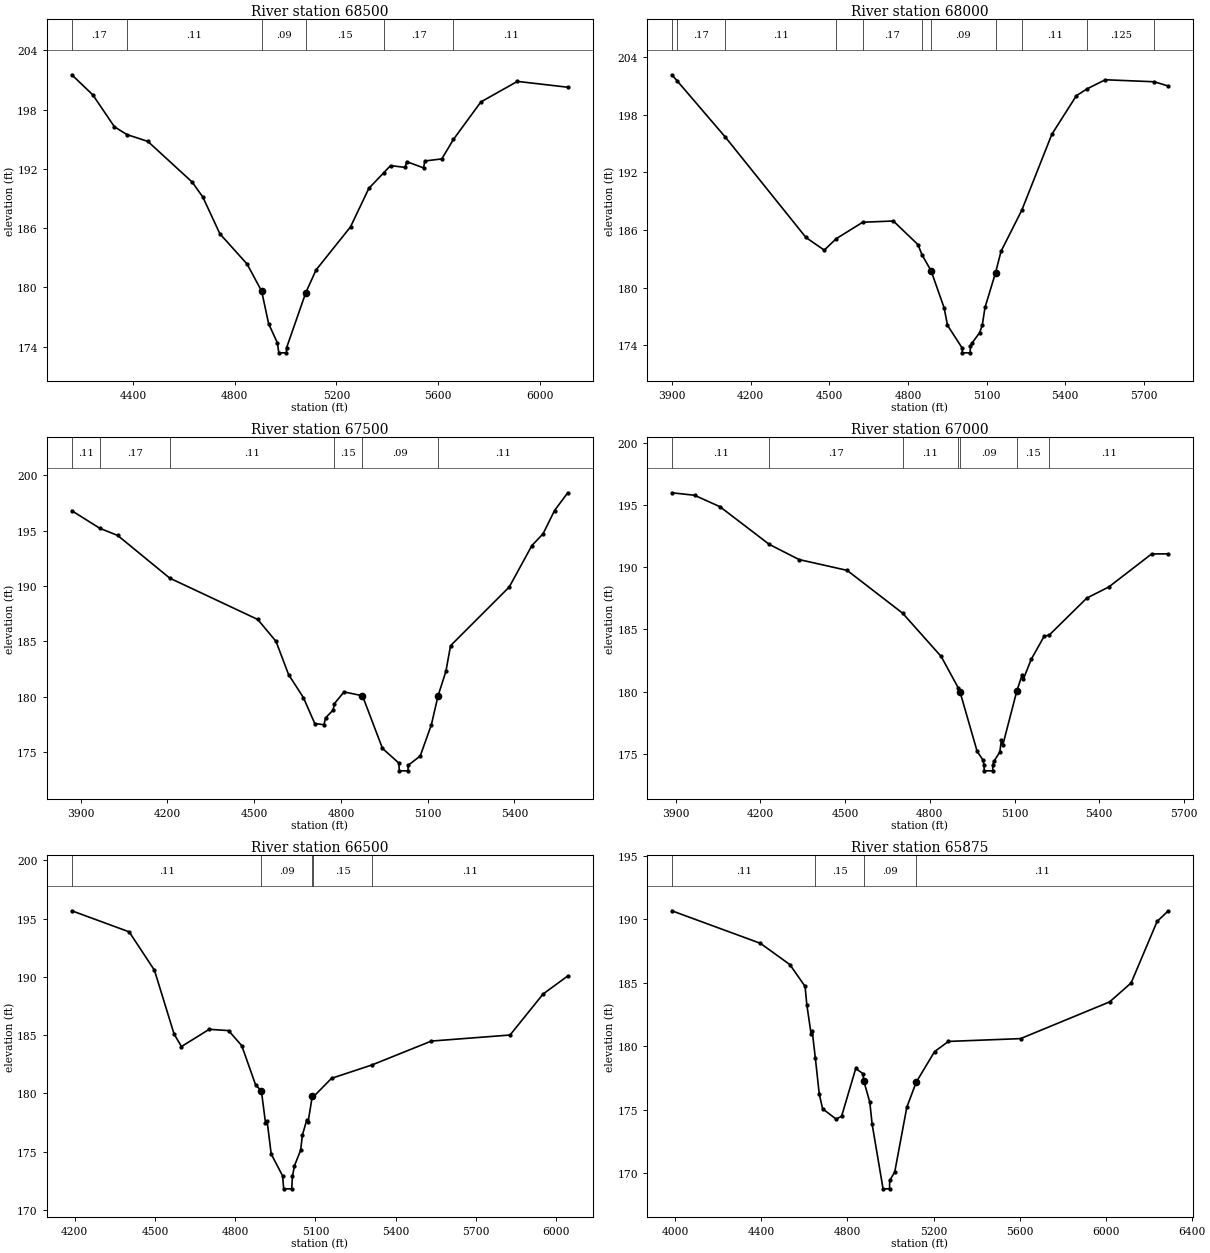
Type RM Length L Ch R = 1 ,68500   ,500,500,500
BEGIN DESCRIPTION:
CRYSTAL CREEK 136.0
END DESCRIPTION:
XS GIS Cut Line= 3
      3862351.82     10121627.55      3862157.84     10120810.05
      3862310.15     10119710.95
#Sta/Elev= 30
  4159.8  201.52  4242.8  199.48  4327.2  196.26  4376.1  195.47    4459  194.77
  4632.9  190.66  4675.2  189.13    4742  185.42  4849.1  182.35  4906.4   179.6
  4933.6  176.31  4968.1  174.37  4973.8  173.36  5003.6  173.36  5004.1  173.86
  5079.7  179.45  5120.1  181.75  5255.7  186.12  5327.5  190.01    5386  191.59
  5412.9  192.32    5471  192.14    5476  192.73  5542.8  192.09  5547.8  192.79
  5614.5     193  5660.2  194.97  5768.1  198.77  5911.7  200.85  6109.6  200.26
#Mann= 6 ,-1 , 0
  4159.8     .17       0  4376.1     .11       0  4906.4     .09       0
  5079.7     .15       0    5386     .17       0  5660.2     .11       0
Bank Sta=4906.4,5079.7
XS Rating Curve= 0 ,0
Exp/Cntr=0.3,0.1

Type RM Length L Ch R = 1 ,68000   ,500,500,500
BEGIN DESCRIPTION:
CRYSTAL CREEK 135.0
END DESCRIPTION:
XS GIS Cut Line= 3
      3862747.66     10121570.29      3862520.68     10120493.14
      3862362.55      10119717.6
#Sta/Elev= 30
  3899.2  202.19  3918.5  201.59  4103.7  195.68    4411  185.22  4480.9   183.9
  4526.2  185.09  4627.5  186.81  4744.3  186.94  4838.6  184.47  4853.3  183.44
  4888.5  181.74  4938.3  177.87    4951  176.06  5007.1  173.69  5007.6  173.19
  5037.4  173.19  5038.5  173.87  5043.6  174.17  5073.6  175.29  5083.8  176.09
  5094.2  177.93  5134.5  181.56  5155.2  183.77  5234.9  188.09  5349.1  195.98
  5442.8  200.01  5484.8  200.74  5553.2  201.67  5740.5  201.46  5791.5  201.03
#Mann= 11 ,-1 , 0
  3899.2     .11       0  3918.5     .17       0  4103.7     .11       0
  4526.2     .15       0  4627.5     .17       0  4853.3     .15       0
  4888.5     .09       0  5134.5     .15       0  5234.9     .11       0
  5484.8    .125       0  5740.5     .11       0
Bank Sta=4888.5,5134.5
XS Rating Curve= 0 ,0
Exp/Cntr=0.3,0.1

Type RM Length L Ch R = 1 ,67500   ,500,500,500
BEGIN DESCRIPTION:
CRYSTAL CREEK 134.0
END DESCRIPTION:
XS GIS Cut Line= 3
      3863283.33     10121342.65      3862933.86     10120267.31
      3862767.71     10119707.24
#Sta/Elev= 30
  3869.3  196.81  3966.1  195.22    4028  194.57  4208.1  190.71  4512.4  186.97
  4575.5  184.99  4618.9  181.99  4670.1  179.91  4709.5  177.56  4741.4  177.45
  4746.7  178.07  4773.4  178.79  4776.6  179.33  4810.6  180.42  4874.5  180.07
  4943.6  175.31    5000  173.99    5002  173.28  5031.9  173.28  5032.4  173.78
  5074.1  174.62  5112.5  177.43  5135.6180.0443    5163  182.29    5179   184.6
    5382  189.91  5460.4  193.66  5498.9  194.72  5538.5  196.82  5584.2  198.43
#Mann= 6 ,-1 , 0
  3869.3     .11       0  3966.1     .17       0  4208.1     .11       0
  4776.6     .15       0  4874.5     .09       0  5135.6     .11       0
Bank Sta=4874.5,5135.6
XS Rating Curve= 0 ,0
Exp/Cntr=0.3,0.1

Type RM Length L Ch R = 1 ,67000   ,500,500,500
BEGIN DESCRIPTION:
CRYSTAL CREEK 133.0
END DESCRIPTION:
XS GIS Cut Line= 3
      3863361.46     10121311.42      3863409.91     10120198.57
        3863325.     10119561.41
#Sta/Elev= 30
  3886.1  195.99  3966.5  195.79  4056.6  194.87  4231.3  191.84  4336.9  190.62
    4507  189.75  4703.5  186.31    4840  182.83    4900  180.33  4907.4  179.94
  4967.5   175.2  4987.5  174.52  4992.1  174.13  4992.6  173.63  5022.6  173.63
  5023.1  174.13  5027.7  174.42  5047.9  175.14  5053.2  176.07  5058.3  175.69
  5108.5  180.09  5126.4   181.3  5131.4  181.01  5158.9  182.59  5204.6  184.44
  5223.4  184.56  5355.9  187.52  5434.1  188.42  5585.5  191.07  5642.8  191.08
#Mann= 7 ,-1 , 0
  3886.1     .11       0  4231.3     .17       0  4703.5     .11       0
    4900     .17       0  4907.4     .09       0  5108.5     .15       0
  5223.4     .11       0
Bank Sta=4907.4,5108.5
XS Rating Curve= 0 ,0
Exp/Cntr=0.3,0.1

Type RM Length L Ch R = 1 ,66500   ,625,625,625
BEGIN DESCRIPTION:
CRYSTAL CREEK 132.0
END DESCRIPTION:
XS GIS Cut Line= 3
       3864314.6      10121030.2       3863888.8     10120339.62
      3863366.65     10119436.38
#Sta/Elev= 30
  4188.7  195.68  4403.3  193.87  4497.9  190.57  4571.3  185.09  4598.9  184.02
  4702.6   185.5  4775.1  185.39  4824.4  184.09  4876.4  180.71  4897.7  180.22
  4913.1  177.47    4919  177.65  4934.4  174.79  4976.9  172.92  4981.2   171.8
  5011.2   171.8  5013.8  172.87  5021.4  173.78  5044.5  175.12  5051.1  176.41
  5066.8  177.68  5072.6  177.57  5088.4   179.8  5091.5  179.69    5160  181.29
  5311.3  182.44  5533.4  184.49  5827.6  185.01  5951.1  188.53  6043.3  190.08
#Mann= 5 ,-1 , 0
  4188.7     .11       0  4897.7     .09       0  5088.4     .11       0
  5091.5     .15       0  5311.3     .11       0
Bank Sta=4897.7,5088.4
XS Rating Curve= 0 ,0
Exp/Cntr=0.3,0.1

Type RM Length L Ch R = 1 ,65875   ,633,633,633
BEGIN DESCRIPTION:
CRYSTAL CREEK 131.0
END DESCRIPTION:
XS GIS Cut Line= 3
       3865408.3     10120405.16      3864435.95     10120109.87
      3863408.32     10119332.24
#Sta/Elev= 30
  3983.8  190.66  4395.4   188.1  4532.1  186.43  4603.1  184.71  4611.3  183.25
  4630.8     181    4636  181.23  4650.6   179.1  4668.9  176.25  4684.5  175.08
  4747.2  174.27  4772.8  174.49  4838.5  178.25  4871.4  177.85  4876.6  177.23
    4904  175.59  4914.7  173.87  4965.5  168.78  4995.5  168.78  4996.4  169.44
  5019.7   170.1  5075.9   175.2  5119.5  177.17  5204.9  179.58  5269.3  180.38
  5604.4   180.6  6018.4  183.49  6118.3  184.98  6239.1  189.82  6288.7  190.62
#Mann= 4 ,-1 , 0
  3983.8     .11       0  4650.6     .15       0  4876.6     .09       0
  5119.5     .11       0
Bank Sta=4876.6,5119.5
XS Rating Curve= 0 ,0
Exp/Cntr=0.3,0.1