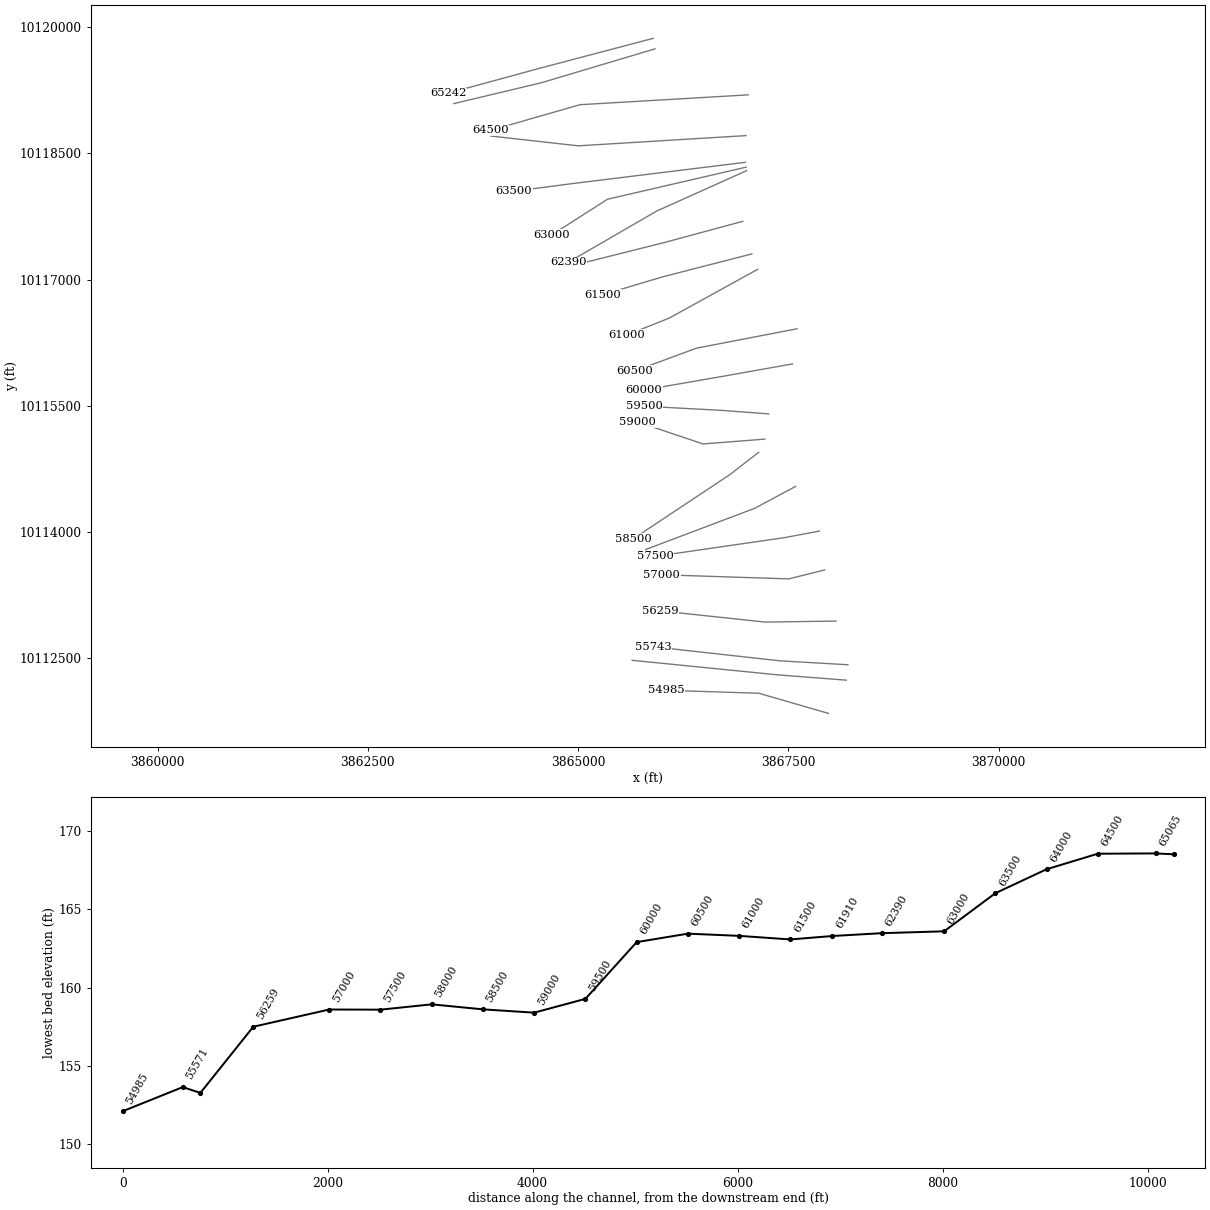
HEC-RAS study CRYSTAL CREEK.prj: CRYSTAL CREEK Base Level Engineering

--- CRYSTAL CREEK.g01 (geometry) --- (continued)

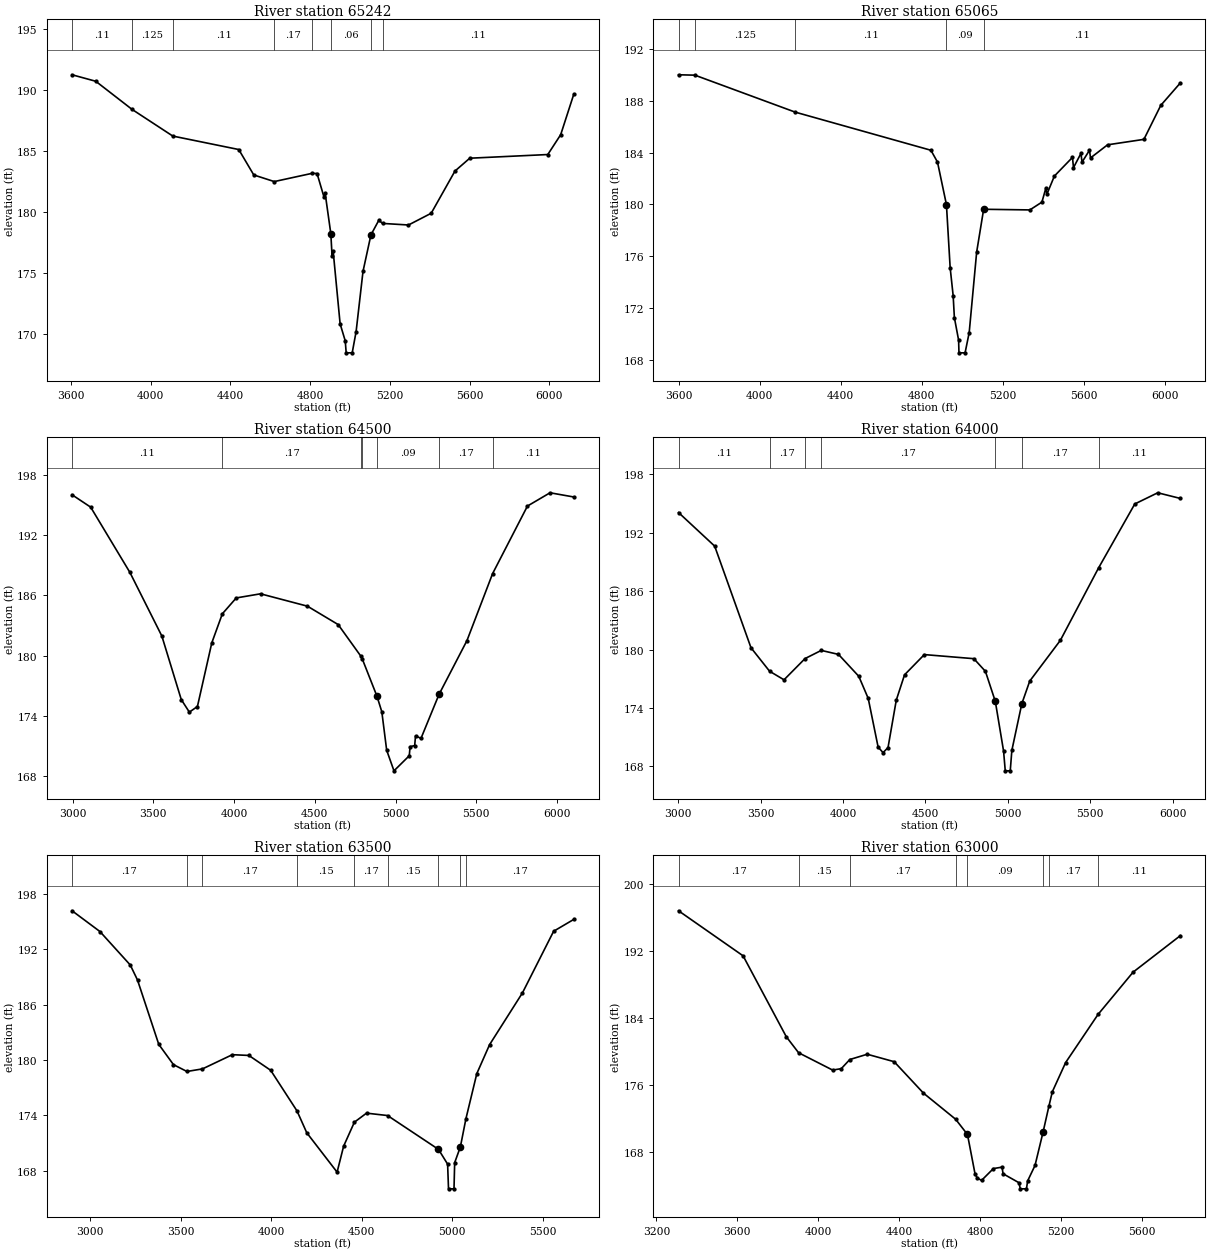
Type RM Length L Ch R = 1 ,65242   ,177,177,177
BEGIN DESCRIPTION:
CRYSTAL CREEK 130.0
END DESCRIPTION:
XS GIS Cut Line= 3
      3865892.72     10119868.71      3864544.64     10119513.47
      3863461.62       10119218.
#Sta/Elev= 30
  3605.9  191.23  3724.7   190.7  3906.8   188.4  4111.1  186.22  4441.9  185.12
  4517.3  183.04    4620   182.5  4808.6  183.17  4834.6  183.16  4869.7  181.22
  4874.9  181.58  4903.6  178.25    4910   176.4  4915.2  176.84  4950.3  170.87
    4976  169.48  4980.7   168.5  5010.9   168.5  5030.5  170.24  5065.1  175.16
  5104.8  178.14  5144.5  179.34    5163  179.08  5293.1  178.95  5407.1  179.91
  5526.3  183.36  5600.5  184.41  5991.8  184.71  6056.5  186.33  6122.6  189.66
#Mann= 8 ,-1 , 0
  3605.9     .11       0  3906.8    .125       0  4111.1     .11       0
    4620     .17       0  4808.6     .11       0  4903.6     .06       0
  5104.8     .15       0    5163     .11       0
Bank Sta=4903.6,5104.8
XS Rating Curve= 0 ,0
Exp/Cntr=0.3,0.1

Type RM Length L Ch R = 1 ,65065   ,565,565,565
BEGIN DESCRIPTION:
CRYSTAL CREEK 129.0
END DESCRIPTION:
XS GIS Cut Line= 3
       3865913.5      10119743.7      3864570.52     10119342.95
       3863522.9     10119092.67
#Sta/Elev= 30
  3598.5     190  3679.4  189.97  4174.8  187.12  4845.1  184.18  4877.6  183.27
  4921.8  179.99  4940.2  175.12    4955  172.97    4961  171.28  4981.9  169.54
  4983.7  168.56  5013.9  168.56  5034.2  170.12  5071.1  176.33  5105.6  179.63
  5333.9  179.58  5393.4  180.18  5412.9  181.26    5418  180.79    5455  182.19
  5544.3  183.63  5549.4  182.84  5586.3  183.94  5591.5  183.26  5628.4  184.18
  5633.6  183.59  5717.7   184.6  5897.2  185.02  5980.5  187.64  6077.1  189.37
#Mann= 5 ,-1 , 0
  3598.5     .11       0  3679.4    .125       0  4174.8     .11       0
  4921.8     .09       0  5105.6     .11       0
Bank Sta=4921.8,5105.6
XS Rating Curve= 0 ,0
Exp/Cntr=0.3,0.1

Type RM Length L Ch R = 1 ,64500   ,500,500,500
BEGIN DESCRIPTION:
CRYSTAL CREEK 128.0
END DESCRIPTION:
XS GIS Cut Line= 3
      3867022.87     10119196.84      3865022.89     10119079.81
      3863961.62     10118775.31
#Sta/Elev= 30
  2996.6     196  3111.8  194.77  3354.7  188.28  3552.6  181.95  3672.8  175.63
  3722.9  174.38  3772.9  174.94  3861.9  181.27  3927.2  184.16  4013.4  185.74
  4163.6  186.15  4454.1  184.92  4644.4  183.09  4786.2  179.92  4794.1  179.66
  4884.8  175.96  4914.9  174.41  4944.9  170.59  4990.1  168.54  5084.7  170.04
  5089.9  170.94  5118.4  171.06  5123.6  172.02  5157.4  171.77    5269  176.14
  5442.2   181.5  5600.9  188.16  5816.7  194.88  5956.7   196.2  6104.1  195.78
#Mann= 7 ,-1 , 0
  2996.6     .11       0  3927.2     .17       0  4786.2     .15       0
  4794.1     .17       0  4884.8     .09       0    5269     .17       0
  5600.9     .11       0
Bank Sta=4884.8,5269
XS Rating Curve= 0 ,0
Exp/Cntr=0.3,0.1

Type RM Length L Ch R = 1 ,64000   ,500,500,500
BEGIN DESCRIPTION:
CRYSTAL CREEK 127.0
END DESCRIPTION:
XS GIS Cut Line= 3
      3866996.88     10118712.46      3865002.28     10118590.97
      3863961.64     10118707.12
#Sta/Elev= 30
  3001.7  194.08  3221.1  190.63  3441.5  180.19  3554.3  177.78  3641.9   176.9
  3769.4  179.08    3868  179.92  3972.5  179.51  4095.7  177.26  4152.9  174.99
    4213  169.99    4243  169.42  4273.1  169.94  4323.2  174.81  4373.3  177.41
  4493.5  179.49    4794  179.07  4864.2  177.77  4924.3  174.68  4974.4  169.58
  4984.6  167.55  5014.9  167.55  5024.6  169.65    5085  174.44  5133.2  176.77
  5318.9  180.95  5550.5  188.38  5770.7  194.96    5910  196.11  6047.1  195.53
#Mann= 7 ,-1 , 0
  3001.7     .11       0  3554.3     .17       0  3769.4     .11       0
    3868     .17       0  4924.3     .09       0    5085     .17       0
  5550.5     .11       0
Bank Sta=4924.3,5085
XS Rating Curve= 0 ,0
Exp/Cntr=0.3,0.1

Type RM Length L Ch R = 1 ,63500   ,500,500,500
BEGIN DESCRIPTION:
CRYSTAL CREEK 126.0
END DESCRIPTION:
XS GIS Cut Line= 3
       3866986.5     10118394.76      3864902.32     10118138.29
      3864236.42       10118051.
#Sta/Elev= 30
  2900.1  196.18    3054  193.93  3221.5   190.3  3261.5  188.67    3379  181.69
  3460.2  179.49  3534.5  178.75  3620.3  179.03  3785.2  180.57  3876.5  180.49
    3997  178.88  4142.5  174.47  4196.4   172.1  4363.9  167.83    4400  170.65
  4459.4  173.25  4526.4  174.23  4642.7  173.97  4923.9   170.3  4974.3   168.7
  4979.3  166.02  5009.6  166.02  5013.3  168.86  5044.8  170.57  5075.5  173.63
  5135.6  178.52  5206.2  181.66  5387.8  187.28  5559.9  193.96  5671.6  195.25
#Mann= 9 ,-1 , 0
  2900.1     .17       0  3534.5     .15       0  3620.3     .17       0
  4142.5     .15       0  4459.4     .17       0  4642.7     .15       0
  4923.9     .06       0  5044.8     .11       0  5075.5     .17       0
Bank Sta=4923.9,5044.8
XS Rating Curve= 0 ,0
Exp/Cntr=0.3,0.1

Type RM Length L Ch R = 1 ,63000   ,610,610,610
BEGIN DESCRIPTION:
CRYSTAL CREEK 125.0
END DESCRIPTION:
XS GIS Cut Line= 3
      3866997.07      10118337.2      3865349.76     10117956.15
       3864684.8     10117531.12
#Sta/Elev= 30
  3309.2  196.79  3628.3  191.41  3841.8  181.75  3902.5  179.84  4070.8  177.77
  4113.5  177.94  4155.6  179.03  4241.7  179.66  4374.9  178.77  4519.6  175.02
  4678.7   171.9  4737.2  170.08  4774.8  165.35  4786.4  164.87  4806.9   164.6
  4865.3  166.01    4908  166.18  4913.2  165.39  4991.7  164.32  4998.3  163.59
  5028.7  163.59  5034.6  164.54    5071  166.38 5110.53 170.337  5139.4  173.43
  5156.6  175.18  5222.4  178.67  5382.4  184.41  5555.7  189.46  5789.2  193.82
#Mann= 8 ,-1 , 0
  3309.2     .17       0  3902.5     .15       0  4155.6     .17       0
  4678.7     .15       0  4737.2     .09       0 5110.53     .15       0
  5139.4     .17       0  5382.4     .11       0
Bank Sta=4737.2,5110.53
XS Rating Curve= 0 ,0
Exp/Cntr=0.3,0.1

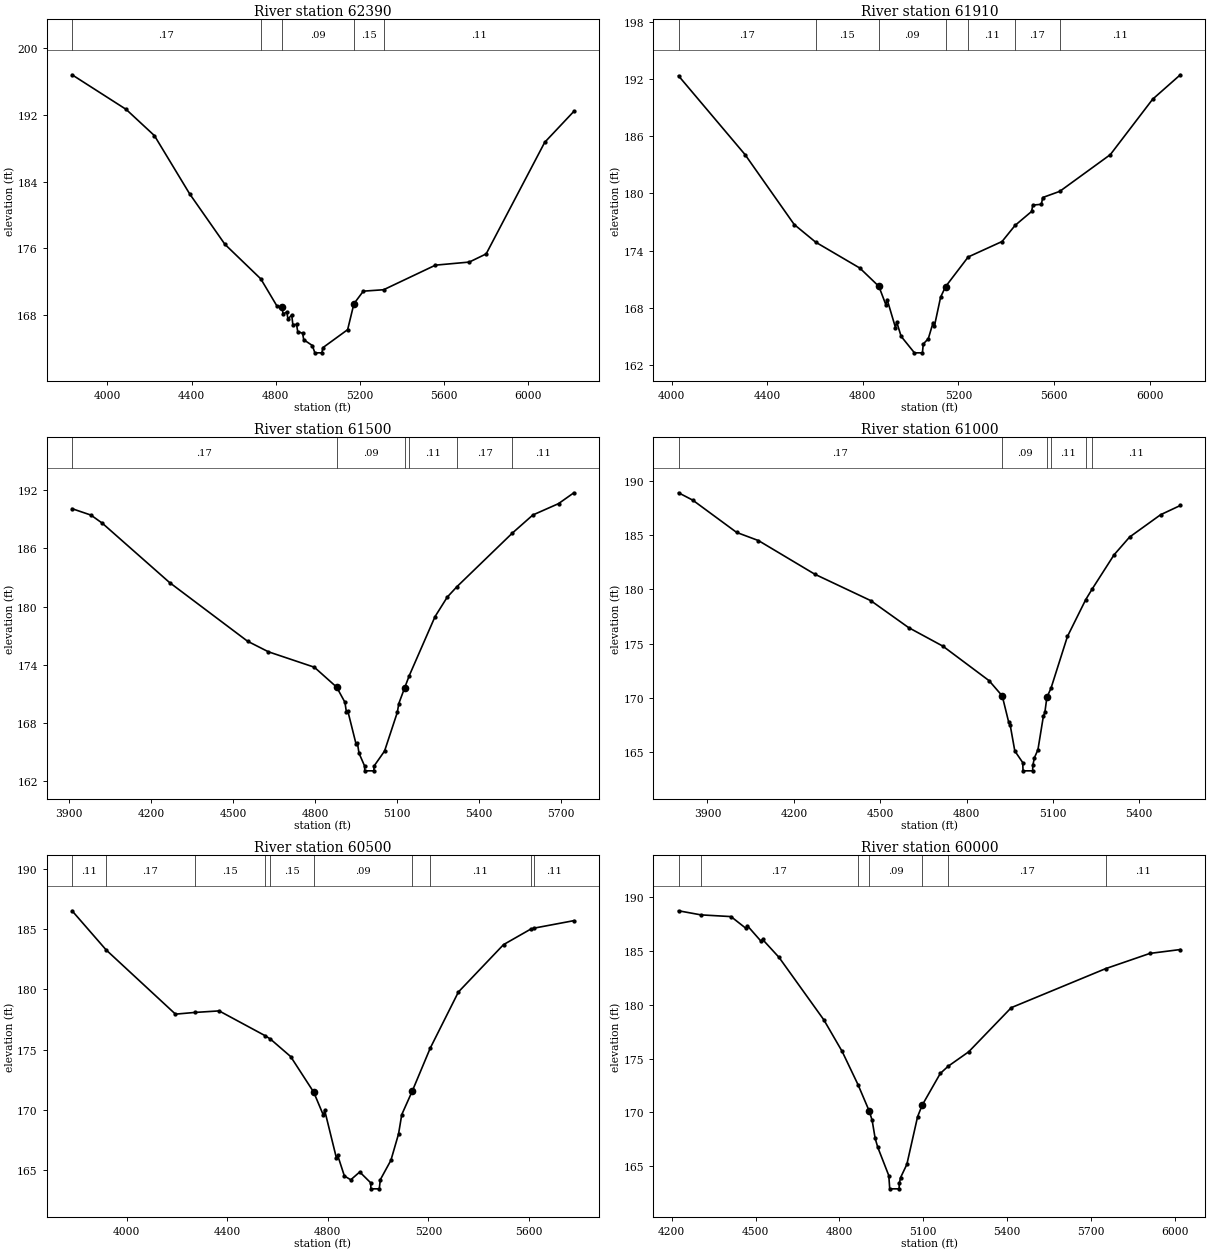
Type RM Length L Ch R = 1 ,62390   ,480,480,480
BEGIN DESCRIPTION:
CRYSTAL CREEK 124.0
END DESCRIPTION:
XS GIS Cut Line= 3
      3867002.31     10118295.54      3865936.67     10117816.65
      3864882.64     10117206.87
#Sta/Elev= 30
  3831.7  196.83  4088.7  192.68  4223.3  189.53  4390.9  182.54  4558.5  176.49
  4729.2  172.34  4806.5  169.06  4829.7  168.95  4835.2  168.14  4852.9  168.37
  4858.3  167.51    4876  168.02  4881.5  166.86  4899.2  166.87  4904.7  166.01
  4927.8  165.82  4933.3  165.04  4974.1  164.35  4986.2  163.47  5019.4  163.47
  5024.3  164.09    5142  166.25  5171.9  169.36  5216.6  170.87  5313.1  171.04
  5559.6  173.99  5720.4  174.36  5800.7  175.34  6079.2  188.73  6217.7  192.44
#Mann= 5 ,-1 , 0
  3831.7     .17       0  4729.2     .15       0  4829.7     .09       0
  5171.9     .15       0  5313.1     .11       0
Bank Sta=4829.7,5171.9
XS Rating Curve= 0 ,0
Exp/Cntr=0.3,0.1

Type RM Length L Ch R = 1 ,61910   ,410,410,410
BEGIN DESCRIPTION:
CRYSTAL CREEK 123.0
END DESCRIPTION:
XS GIS Cut Line= 3
      3866956.46     10117693.16      3866019.43      10117440.1
      3864925.63     10117165.69
#Sta/Elev= 30
  4029.4  192.33  4307.6  184.07  4513.2  176.74    4603  174.89  4787.3  172.18
  4867.1  170.26  4896.6  168.32  4901.8  168.87  4936.5  165.94  4941.7  166.52
  4960.2  165.02  5015.9  163.29  5049.2  163.29  5052.8  164.22  5073.8  164.77
    5094  166.47  5099.2  166.07  5125.3  169.13    5146  170.23  5240.6  173.34
  5382.2  174.96  5436.7  176.65  5505.7  178.11  5510.8  178.78  5546.8  178.86
    5552  179.57  5623.6  180.22    5835  184.07    6012  189.88  6127.7  192.44
#Mann= 7 ,-1 , 0
  4029.4     .17       0    4603     .15       0  4867.1     .09       0
    5146     .15       0  5240.6     .11       0  5436.7     .17       0
  5623.6     .11       0
Bank Sta=4867.1,5146
XS Rating Curve= 0 ,0
Exp/Cntr=0.3,0.1

Type RM Length L Ch R = 1 ,61500   ,500,500,500
BEGIN DESCRIPTION:
CRYSTAL CREEK 122.0
END DESCRIPTION:
XS GIS Cut Line= 3
       3867064.8     10117305.96       3866009.7     10117034.77
      3865293.97     10116821.58
#Sta/Elev= 30
  3910.6  190.09  3979.7  189.43    4021   188.6  4267.7  182.47  4552.8  176.43
  4629.1  175.34  4797.2  173.75  4878.7   171.7    4909  170.14  4914.3  169.17
  4919.5  169.25  4949.9  165.82    4955  165.89  4960.6  164.89    4981  163.57
  4981.7  163.07    5015  163.07  5015.8  163.57  5054.1  165.11  5100.8   169.1
  5106.3  170.01  5127.1  171.59  5144.6  172.89  5238.7  178.96  5283.6  180.98
  5318.9  182.05  5521.1  187.56  5596.7  189.44  5690.6  190.61  5746.8  191.73
#Mann= 6 ,-1 , 0
  3910.6     .17       0  4878.7     .09       0  5127.1     .15       0
  5144.6     .11       0  5318.9     .17       0  5521.1     .11       0
Bank Sta=4878.7,5127.1
XS Rating Curve= 0 ,0
Exp/Cntr=0.3,0.1

Type RM Length L Ch R = 1 ,61000   ,500,500,500
BEGIN DESCRIPTION:
CRYSTAL CREEK 121.0
END DESCRIPTION:
XS GIS Cut Line= 3
       3867132.6     10117121.95      3866081.25      10116542.2
      3865577.09     10116341.59
#Sta/Elev= 30
  3799.4   188.9  3848.9  188.22  4001.3  185.25    4077   184.5    4273   181.4
  4467.2  178.97  4598.5  176.49  4717.7  174.78  4878.3   171.6  4923.9   170.2
  4945.8  167.84  4951.5  167.52  4967.6  165.13  4995.1  164.06  4996.2   163.3
  5029.5   163.3  5030.2   163.8  5035.9  164.52  5047.9  165.24  5066.8  168.32
  5072.1   168.7    5079  170.06  5093.5  170.92  5150.4  175.67  5214.1  179.07
  5236.6  180.05  5312.2  183.18  5366.2  184.82  5474.1  186.88  5542.6  187.73
#Mann= 6 ,-1 , 0
  3799.4     .17       0  4923.9     .09       0    5079     .15       0
  5093.5     .11       0  5214.1     .17       0  5236.6     .11       0
Bank Sta=4923.9,5079
XS Rating Curve= 0 ,0
Exp/Cntr=0.3,0.1

Type RM Length L Ch R = 1 ,60500   ,500,500,500
BEGIN DESCRIPTION:
CRYSTAL CREEK 120.0
END DESCRIPTION:
XS GIS Cut Line= 3
      3867601.87     10116416.05      3866406.21     10116185.45
      3865675.28     10115915.73
#Sta/Elev= 30
  3782.3  186.52  3917.9  183.27  4193.8  177.94  4269.7  178.08  4367.5  178.21
  4550.7  176.15  4571.7  175.87  4652.1  174.42  4743.7  171.47  4782.4  169.55
  4787.5  169.96  4834.3  165.99  4839.4  166.21  4865.9  164.51  4891.3  164.19
    4927  164.84  4970.7  163.94  4971.5  163.44  5004.8  163.44  5008.9   164.2
  5051.1  165.81  5081.5     168  5094.2   169.6  5136.8  171.59  5207.6  175.12
  5319.7  179.78  5499.2  183.71  5606.8  184.99    5621  185.08  5779.1   185.7
#Mann= 10 ,-1 , 0
  3782.3     .11       0  3917.9     .17       0  4269.7     .15       0
  4550.7     .17       0  4571.7     .15       0  4743.7     .09       0
  5136.8     .15       0  5207.6     .11       0  5606.8     .17       0
    5621     .11       0
Bank Sta=4743.7,5136.8
XS Rating Curve= 0 ,0
Exp/Cntr=0.3,0.1

Type RM Length L Ch R = 1 ,60000   ,500,500,500
BEGIN DESCRIPTION:
CRYSTAL CREEK 119.0
END DESCRIPTION:
XS GIS Cut Line= 3
      3867549.23     10115998.67      3866786.06     10115862.61
      3865782.43     10115688.03
#Sta/Elev= 30
  4224.8  188.73  4304.7  188.35  4412.3  188.19  4466.2  187.09  4471.3  187.33
  4520.1  185.89  4525.2  186.07  4584.1   184.4  4744.2   178.6  4809.8  175.66
  4866.4  172.58  4906.8  170.11  4916.9  169.27  4927.7  167.59  4937.2  166.75
  4976.5  164.13  4979.8   162.9  5013.3   162.9  5014.1   163.4  5018.5  163.94
    5041  165.17  5079.4   169.6  5095.6  170.66  5160.6  173.62  5188.8  174.29
  5262.1  175.63  5414.3  179.73  5751.2  183.35    5910  184.77  6018.7  185.13
#Mann= 7 ,-1 , 0
  4224.8     .11       0  4304.7     .17       0  4866.4     .15       0
  4906.8     .09       0  5095.6     .15       0  5188.8     .17       0
  5751.2     .11       0
Bank Sta=4906.8,5095.6
XS Rating Curve= 0 ,0
Exp/Cntr=0.3,0.1

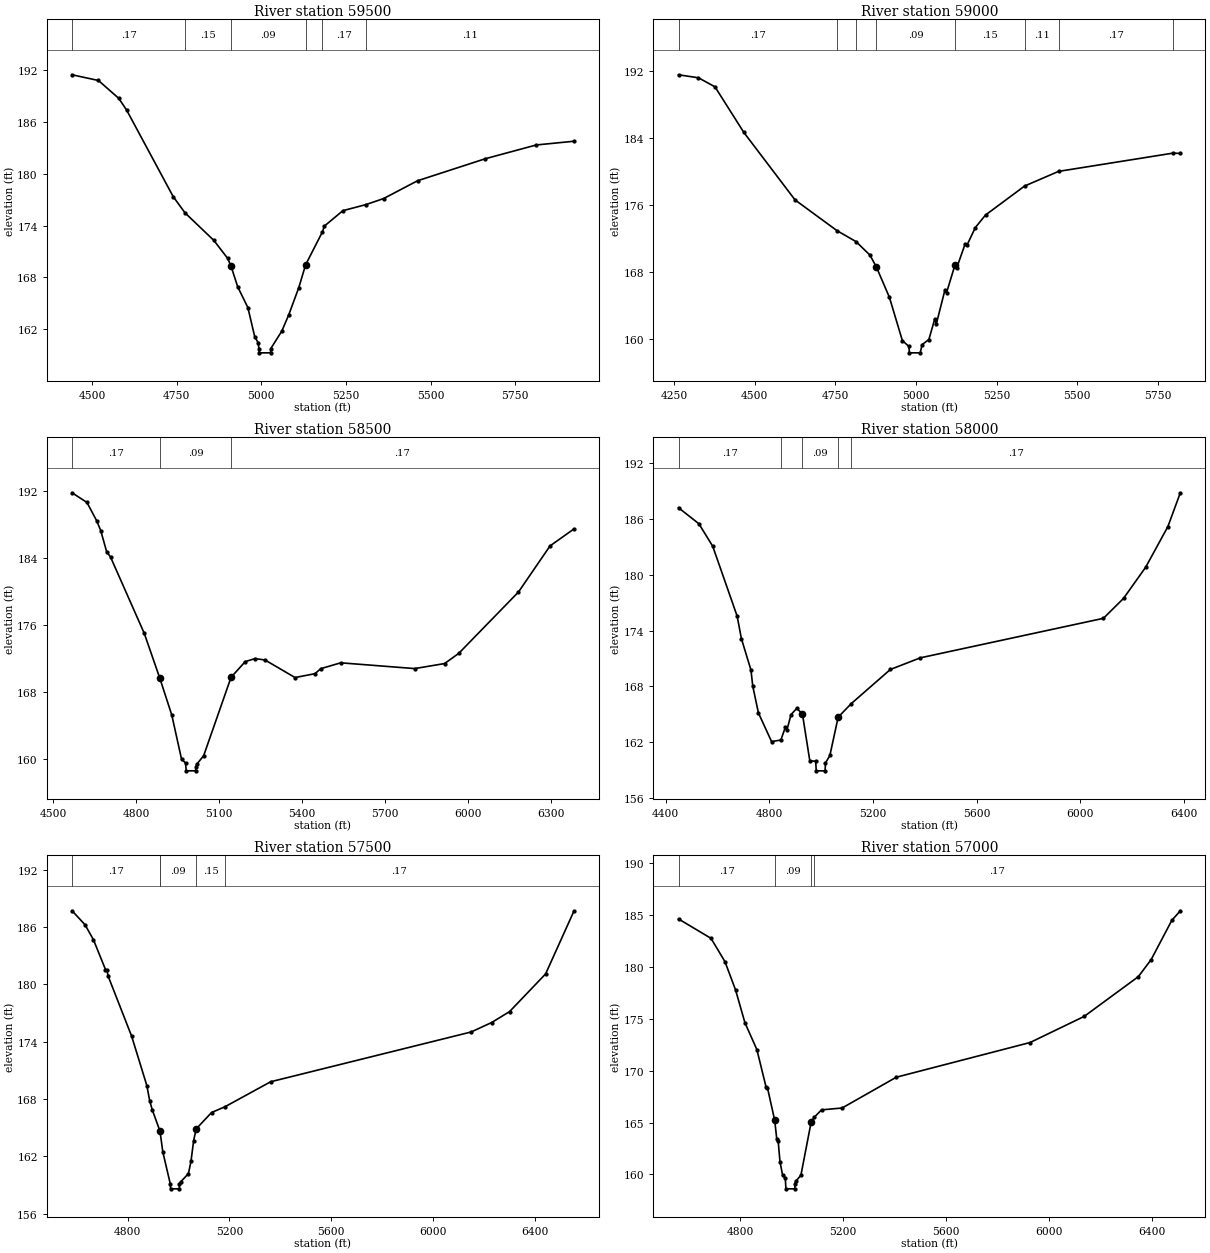
Type RM Length L Ch R = 1 ,59500   ,500,500,500
BEGIN DESCRIPTION:
CRYSTAL CREEK 118.0
END DESCRIPTION:
XS GIS Cut Line= 3
      3867265.41     10115404.09      3866708.49     10115446.16
       3865787.1     10115495.23
#Sta/Elev= 30
  4441.5  191.45  4519.3  190.79  4579.4  188.72  4602.5  187.37  4739.9  177.36
  4774.8  175.48  4860.2  172.28  4900.4  170.23  4910.4  169.35  4930.4  166.92
  4960.5  164.51  4980.6  161.16  4990.6  160.46  4993.2  159.78  4993.9  159.28
  5027.4  159.28  5028.2  159.78  5060.7   161.8  5080.8  163.65  5110.8  166.83
  5130.8  169.46  5180.7  173.29  5186.1  173.94    5241  175.73    5308  176.42
  5361.2  177.13  5461.3  179.19  5661.6  181.74  5811.8  183.33  5922.7  183.76
#Mann= 6 ,-1 , 0
  4441.5     .17       0  4774.8     .15       0  4910.4     .09       0
  5130.8     .15       0  5180.7     .17       0    5308     .11       0
Bank Sta=4910.4,5130.8
XS Rating Curve= 0 ,0
Exp/Cntr=0.3,0.1

Type RM Length L Ch R = 1 ,59000   ,500,500,500
BEGIN DESCRIPTION:
CRYSTAL CREEK 117.0
END DESCRIPTION:
XS GIS Cut Line= 3
      3867219.47     10115104.61      3866485.63     10115047.01
      3865709.02     10115307.73
#Sta/Elev= 30
  4263.9  191.59  4325.7  191.23  4376.9  190.15  4466.1  184.72  4625.1  176.65
  4755.6  172.97    4814  171.68  4857.3  170.06  4877.4  168.62  4917.5  165.03
  4957.6  159.87  4977.7  159.17  4979.6   158.4  5013.1   158.4  5018.8  159.38
  5039.8  159.99  5057.8  162.41  5063.1  161.87  5089.3  165.86  5094.6  165.57
  5120.8   168.9  5126.1  168.54  5152.4  171.42  5157.7  171.23  5183.9  173.36
  5215.4  174.85  5336.5  178.31  5441.9  180.06  5796.8  182.24  5819.2   182.2
#Mann= 8 ,-1 , 0
  4263.9     .17       0  4755.6     .15       0    4814     .17       0
  4877.4     .09       0  5120.8     .15       0  5336.5     .11       0
  5441.9     .17       0  5796.8     .11       0
Bank Sta=4877.4,5120.8
XS Rating Curve= 0 ,0
Exp/Cntr=0.3,0.1

Type RM Length L Ch R = 1 ,58500   ,500,500,500
BEGIN DESCRIPTION:
CRYSTAL CREEK 116.0
END DESCRIPTION:
XS GIS Cut Line= 3
      3867146.54     10114948.37      3866804.63     10114683.18
      3865652.32      10113917.5
#Sta/Elev= 30
  4567.3  191.84  4621.3  190.68  4656.6  188.48  4671.1  187.32  4692.2  184.82
  4706.4  184.17  4828.6  175.04  4884.7   169.7  4928.2  165.28  4963.5  160.01
  4977.9  159.55  4980.5  158.61  5014.7  158.61  5015.6  159.11  5020.1  159.46
  5043.6  160.42  5142.8  169.79  5193.9  171.66    5230  172.03    5266  171.85
  5374.3  169.76  5446.4  170.22  5467.5  170.82  5539.6  171.52  5807.2  170.83
  5915.5  171.43  5966.6  172.64    6183  179.98  6297.3  185.49  6383.5  187.51
#Mann= 3 , 0 , 0
  4567.3     .17       0  4884.7     .09       0  5142.8     .17       0
Bank Sta=4884.7,5142.8
XS Rating Curve= 0 ,0
Exp/Cntr=0.3,0.1

Type RM Length L Ch R = 1 ,58000   ,500,500,500
BEGIN DESCRIPTION:
CRYSTAL CREEK 115.0
END DESCRIPTION:
XS GIS Cut Line= 3
      3867584.04     10114542.12      3867099.07     10114281.63
      3865802.82     10113792.13
#Sta/Elev= 30
  4449.5  187.22    4528   185.5  4581.4  183.08  4675.7  175.56    4692  173.15
    4729  169.76  4735.8  168.06  4757.7  165.16  4808.4  162.08  4844.2  162.24
  4861.7  163.62  4867.3  163.28  4883.6  164.98  4905.5  165.64  4927.4  165.07
    4956  160.01  4978.7  159.96  4980.8  158.93    5015  158.93  5016.5  159.78
  5033.4  160.58  5065.4   164.7    5116  166.16  5266.8  169.83  5382.2  171.08
  6088.8  175.33  6166.4  177.47    6252  180.83  6337.5  185.19  6385.6  188.83
#Mann= 5 ,-1 , 0
  4449.5     .17       0  4844.2     .15       0  4927.4     .09       0
  5065.4     .15       0    5116     .17       0
Bank Sta=4927.4,5065.4
XS Rating Curve= 0 ,0
Exp/Cntr=0.3,0.1

Type RM Length L Ch R = 1 ,57500   ,500,500,500
BEGIN DESCRIPTION:
CRYSTAL CREEK 114.0
END DESCRIPTION:
XS GIS Cut Line= 3
      3867867.86     10114011.07      3867456.33      10113933.9
      3865917.89     10113711.08
#Sta/Elev= 30
  4581.3   187.7  4632.2  186.24  4665.2  184.68  4712.7  181.55  4717.8  181.52
  4723.7  180.82  4815.3  174.59  4875.5  169.39  4886.5  167.81  4896.7  166.86
  4926.2  164.69  4927.2   164.6  4938.2  162.45  4967.7  159.09  4968.6  158.59
  5002.9  158.59  5003.7  159.09  5008.6  159.33  5038.9  160.18    5049  161.49
  5059.4  163.64  5069.2  164.86  5129.8  166.58  5182.4  167.18  5362.2   169.8
  6150.4  175.01  6231.2     176  6301.9  177.15  6443.4  181.09  6554.5  187.65
#Mann= 5 ,-1 , 0
  4581.3     .17       0  4926.2     .15       0  4927.2     .09       0
  5069.2     .15       0  5182.4     .17       0
Bank Sta=4927.2,5069.2
XS Rating Curve= 0 ,0
Exp/Cntr=0.3,0.1

Type RM Length L Ch R = 1 ,57000   ,741,741,741
BEGIN DESCRIPTION:
CRYSTAL CREEK 113.0
END DESCRIPTION:
XS GIS Cut Line= 3
      3867930.36     10113549.05      3867504.85      10113443.1
      3865994.63     10113491.76
#Sta/Elev= 30
  4561.5  184.64  4687.7  182.77  4741.9  180.52  4783.2  177.78  4819.4  174.63
  4865.8  172.04    4902  168.38  4907.1  168.34  4935.1  165.21  4943.3  163.37
  4948.4  163.26  4955.7   161.2    4966   159.9  4976.3  159.64  4978.7   158.6
    5013   158.6  5013.9   159.1    5017  159.32    5037  159.92    5077  165.08
  5089.5  165.53  5117.1  166.22  5197.1   166.4  5407.5  169.37  5927.5  172.72
  6137.6  175.24  6347.7  179.07  6397.7  180.72  6477.8   184.5    6511  185.43
#Mann= 4 ,-1 , 0
  4561.5     .17       0  4935.1     .09       0    5077     .15       0
  5089.5     .17       0
Bank Sta=4935.1,5077
XS Rating Curve= 0 ,0
Exp/Cntr=0.3,0.1

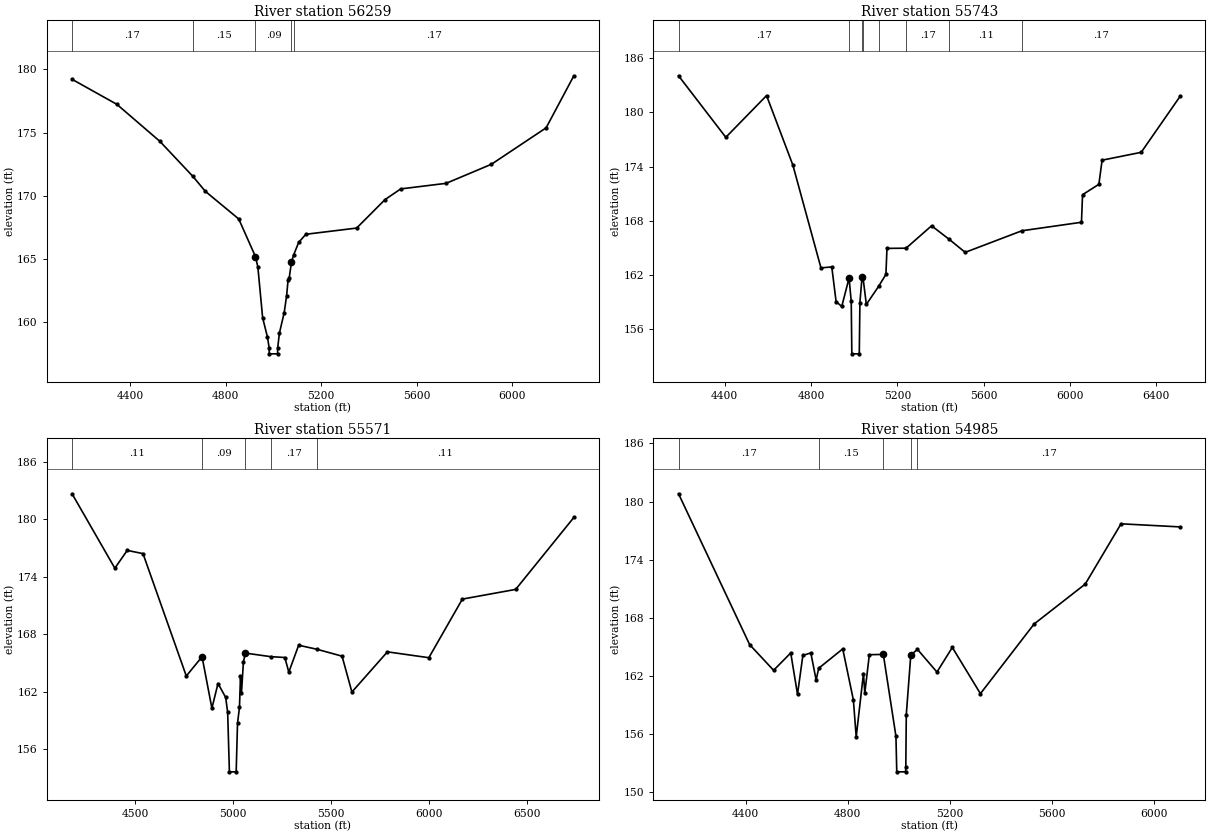
Type RM Length L Ch R = 1 ,56259   ,516,516,516
BEGIN DESCRIPTION:
CRYSTAL CREEK 112.0
END DESCRIPTION:
XS GIS Cut Line= 3
      3868065.47     10112941.48      3867222.66     10112929.49
      3865972.26     10113062.95
#Sta/Elev= 30
  4157.1  179.22  4344.7  177.24  4524.8  174.31  4662.8  171.54  4714.8  170.36
  4854.8  168.17  4924.8  165.19  4934.8  164.37  4954.8  160.35  4974.8  158.84
  4981.9     158  4982.7   157.5  5017.1   157.5    5018     158  5024.9  159.13
  5045.1  160.77  5055.1  162.09  5061.1  163.31  5066.1  163.51  5075.2  164.73
  5084.5  165.32  5105.4  166.31  5135.6  166.96  5348.2  167.45  5467.4  169.71
    5533  170.55  5722.7  170.99  5912.5   172.5  6141.3  175.38  6257.5   179.5
#Mann= 5 ,-1 , 0
  4157.1     .17       0  4662.8     .15       0  4924.8     .09       0
  5075.2     .15       0  5084.5     .17       0
Bank Sta=4924.8,5075.2
XS Rating Curve= 0 ,0
Exp/Cntr=0.3,0.1

Type RM Length L Ch R = 1 ,55743   ,172,172,172
BEGIN DESCRIPTION:
CRYSTAL CREEK 111.0
END DESCRIPTION:
XS GIS Cut Line= 3
      3868206.44     10112422.31       3867394.4     10112469.32
      3865892.83     10112636.07
#Sta/Elev= 30
  4186.6  184.05  4405.6  177.24  4594.3  181.86  4716.1  174.17  4846.3  162.79
  4896.4   162.9  4916.4  159.06  4942.6  158.52  4976.5  161.67  4986.5  159.08
  4989.3  153.28  5023.8  153.28  5026.7  158.96  5036.8  161.83    5041  161.72
  5056.5  158.75  5113.4  160.75  5147.1  162.07  5152.1  164.95  5240.4  164.97
  5358.7  167.45  5439.8  165.96  5514.4  164.51  5777.1   166.9  6052.9  167.84
  6057.9  170.89  6133.5  172.04  6148.5  174.71  6329.6  175.58  6510.8  181.81
#Mann= 8 ,-1 , 0
  4186.6     .17       0  4976.5     .09       0  5036.8     .17       0
    5041     .11       0  5113.4     .15       0  5240.4     .17       0
  5439.8     .11       0  5777.1     .17       0
Bank Sta=4976.5,5036.8
XS Rating Curve= 0 ,0
Exp/Cntr=0.3,0.1

Type RM Length L Ch R = 1 ,55571   ,586,586,586
BEGIN DESCRIPTION:
CRYSTAL CREEK 110.0
END DESCRIPTION:
XS GIS Cut Line= 3
      3868188.16     10112239.16       3867370.6     10112302.27
       3865642.7     10112474.96
#Sta/Elev= 30
    4180  182.64  4397.9  174.88  4461.1  176.74  4541.4   176.4    4762  163.64
  4842.3  165.65  4892.4  160.28  4923.5  162.86  4962.6  161.41  4972.7  159.85
  4981.6  153.65  5016.1  153.65  5022.9   158.7  5032.9  160.38  5038.1  163.61
  5043.1  161.87    5053  165.13  5063.1  166.03  5191.5  165.66  5264.1  165.57
  5284.2  164.04  5334.4  166.85  5427.4  166.43  5555.5  165.71  5605.7  161.97
  5786.6  166.16  5997.7  165.55  6168.5  171.66  6439.9  172.67  6736.5  180.17
#Mann= 5 ,-1 , 0
    4180     .11       0  4842.3     .09       0  5063.1     .11       0
  5191.5     .17       0  5427.4     .11       0
Bank Sta=4842.3,5063.1
XS Rating Curve= 0 ,0
Exp/Cntr=0.3,0.1

Type RM Length L Ch R = 1 ,54985   ,485,485,485
BEGIN DESCRIPTION:
CRYSTAL CREEK 109.0
END DESCRIPTION:
XS GIS Cut Line= 3
      3867975.18     10111844.25      3867146.61     10112083.77
      3866045.94     10112118.13
#Sta/Elev= 30
  4137.5  180.81  4415.8  165.24  4509.5  162.59  4576.6  164.38  4603.1  160.11
    4624  164.12  4655.2  164.39    4676  161.59    4686   162.8  4780.1   164.8
  4821.7  159.53  4832.8  155.72  4861.2  162.26  4866.4  160.24  4884.2   164.2
  4938.9  164.23  4988.3  155.78  4991.5  152.11    5026  152.11  5026.9  152.61
  5028.8  158.01 5046.41164.1648  5072.5  164.75  5148.8  162.41  5208.9  164.95
  5318.9  160.18    5529  167.37  5729.1  171.49  5869.2  177.71  6101.2  177.39
#Mann= 5 ,-1 , 0
  4137.5     .17       0    4686     .15       0  4938.9     .09       0
 5046.41     .15       0  5072.5     .17       0
Bank Sta=4938.9,5046.41
XS Rating Curve= 0 ,0
Exp/Cntr=0.3,0.1