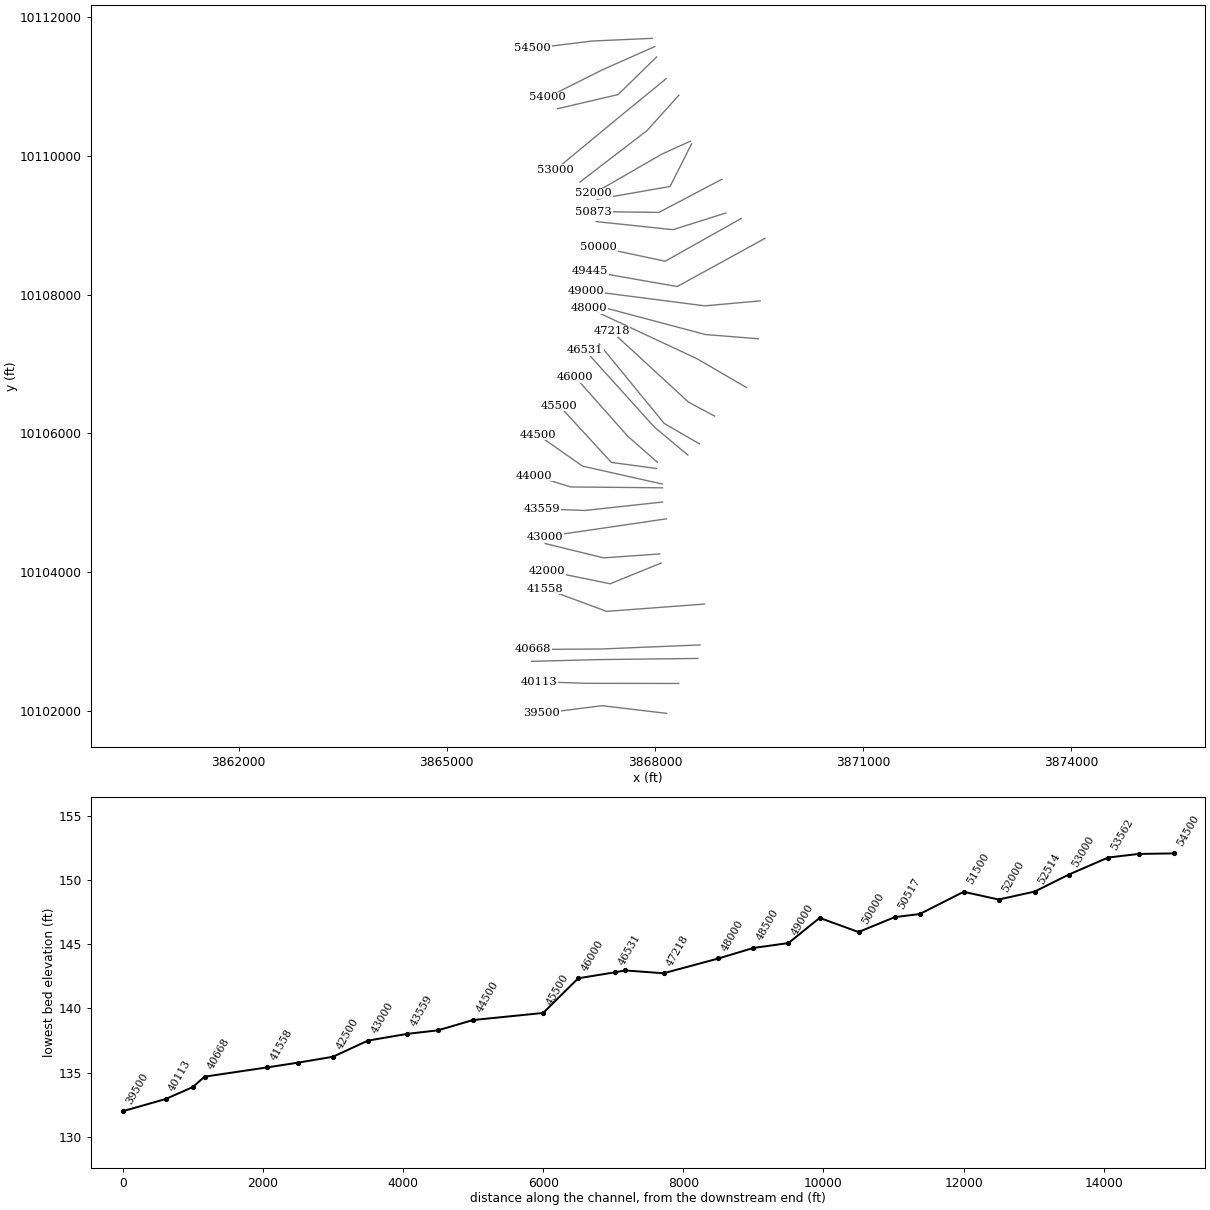
HEC-RAS study CRYSTAL CREEK.prj: CRYSTAL CREEK Base Level Engineering

--- CRYSTAL CREEK.g01 (geometry) --- (continued)

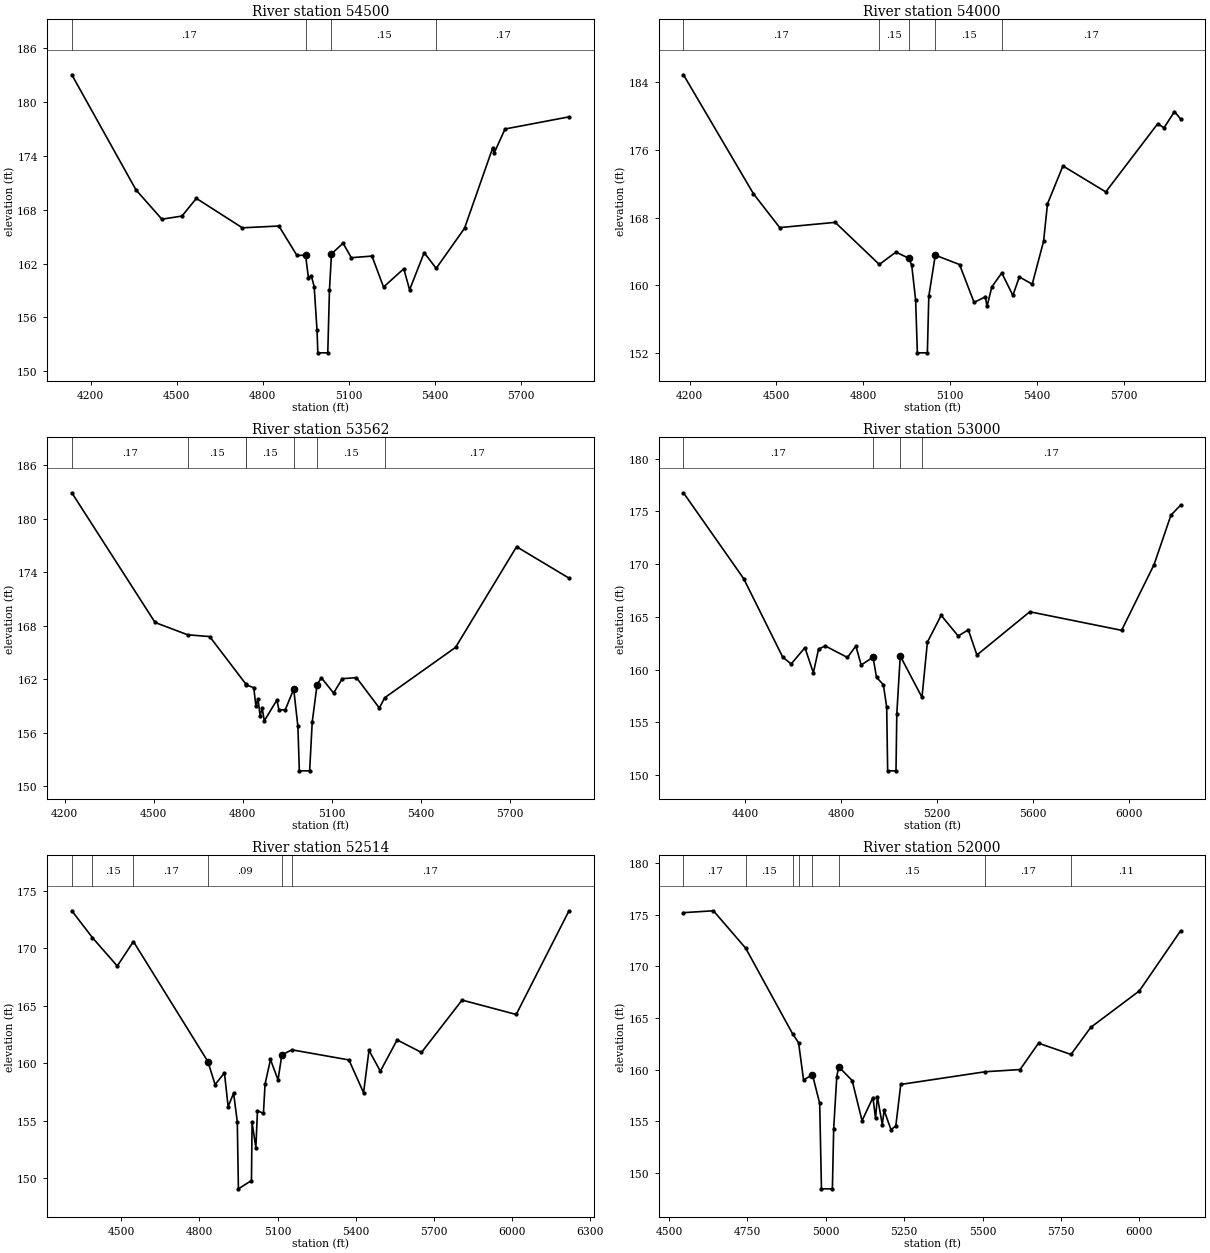
Type RM Length L Ch R = 1 ,54500   ,500,500,500
BEGIN DESCRIPTION:
CRYSTAL CREEK 108.0
END DESCRIPTION:
XS GIS Cut Line= 3
      3867961.24     10111698.43       3867096.6     10111659.73
      3866236.89      10111553.9
#Sta/Elev= 30
  4134.5  183.04  4358.1  170.21  4448.2  166.95  4518.3   167.3  4568.3  169.27
  4728.5  165.99  4855.8  166.19  4918.7  162.91  4948.7  162.94  4958.7  160.43
  4968.7  160.65  4978.7  159.44  4988.7  154.55  4991.5  152.06  5026.1  152.06
    5032  159.07    5039  163.08  5079.3  164.28  5108.1  162.66  5180.1  162.84
  5220.4  159.39  5290.9  161.43  5311.1  159.08  5361.9  163.22  5403.8  161.47
  5502.5  165.94  5600.6  174.89  5605.6  174.31  5643.6     177  5866.2  178.35
#Mann= 4 ,-1 , 0
  4134.5     .17       0  4948.7     .09       0    5039     .15       0
  5403.8     .17       0
Bank Sta=4948.7,5039
XS Rating Curve= 0 ,0
Exp/Cntr=0.3,0.1

Type RM Length L Ch R = 1 ,54000   ,438,438,438
BEGIN DESCRIPTION:
CRYSTAL CREEK 107.0
END DESCRIPTION:
XS GIS Cut Line= 3
      3867998.99     10111579.92      3867248.39     10111247.31
      3866446.87     10110845.27
#Sta/Elev= 30
    4179   184.9  4420.9  170.83  4511.6  166.83  4703.3  167.45  4855.8  162.47
  4913.1  163.93    4958   163.2  4967.8  162.36  4981.3  158.24  4987.2  152.02
  5021.8  152.02  5026.8  158.72  5049.2  163.57  5132.9  162.46  5183.2  157.99
  5222.3  158.64  5227.9   157.5  5244.6  159.82  5278.9  161.47  5317.2  158.81
  5339.6     161  5384.2  160.14  5423.3   165.2  5436.9  169.64  5490.3  174.12
  5638.3  171.05  5817.3  179.09  5839.7  178.64  5875.7  180.55  5896.7  179.68
#Mann= 5 ,-1 , 0
    4179     .17       0  4855.8     .15       0    4958     .09       0
  5049.2     .15       0  5278.9     .17       0
Bank Sta=4958,5049.2
XS Rating Curve= 0 ,0
Exp/Cntr=0.3,0.1

Type RM Length L Ch R = 1 ,53562   ,562,562,562
BEGIN DESCRIPTION:
CRYSTAL CREEK 106.0
END DESCRIPTION:
XS GIS Cut Line= 3
      3868025.04     10111430.35      3867470.58     10110887.72
      3866596.24     10110682.97
#Sta/Elev= 30
  4224.2  182.93  4504.5  168.38  4614.3     167  4688.4   166.8  4810.7  161.45
  4811.5  161.38  4836.8  161.07    4844  158.98    4851  159.81  4858.1  157.93
  4865.1  158.76  4872.3  157.35  4914.7  159.68  4921.7  158.57    4943  158.59
  4971.3  160.91  4985.4  156.72  4990.2  151.74  5024.9  151.74  5033.6   157.2
    5050  161.41  5064.4  162.18  5105.5  160.47    5135  162.08  5182.6  162.19
  5259.6  158.79  5277.7  159.94  5516.3  165.59  5721.7  176.88    5898  173.36
#Mann= 7 ,-1 , 0
  4224.2     .17       0  4614.3     .15       0  4810.7     .17       0
  4811.5     .15       0  4971.3     .09       0    5050     .15       0
  5277.7     .17       0
Bank Sta=4971.3,5050
XS Rating Curve= 0 ,0
Exp/Cntr=0.3,0.1

Type RM Length L Ch R = 1 ,53000   ,486,486,486
BEGIN DESCRIPTION:
CRYSTAL CREEK 105.0
END DESCRIPTION:
XS GIS Cut Line= 3
      3868163.92     10111117.84      3867499.38     10110574.01
      3866563.29     10109799.44
#Sta/Elev= 30
  4141.3  176.77  4392.5  168.63  4555.4  161.19  4590.6  160.54    4648  162.09
  4683.2   159.7  4704.8  161.95  4732.7  162.25  4825.3  161.16  4860.5  162.24
  4882.7  160.44  4932.2  161.18  4946.6  159.28  4975.3  158.57  4989.1  156.44
  4993.1  150.41  5027.9  150.41  5031.3  155.81  5045.6   161.3  5136.3  157.38
  5158.9  162.61  5216.3  165.15  5287.5  163.19  5329.6  163.78  5365.4  161.39
  5586.1  165.49  5969.1  163.73  6104.6  169.97  6174.9  174.65    6215  175.59
#Mann= 4 ,-1 , 0
  4141.3     .17       0  4932.2     .09       0  5045.6     .15       0
  5136.3     .17       0
Bank Sta=4932.2,5045.6
XS Rating Curve= 0 ,0
Exp/Cntr=0.3,0.1

Type RM Length L Ch R = 1 ,52514   ,514,514,514
BEGIN DESCRIPTION:
CRYSTAL CREEK 104.0
END DESCRIPTION:
XS GIS Cut Line= 3
      3868346.26     10110879.17      3867885.34     10110366.91
      3866919.55      10109625.1
#Sta/Elev= 30
  4310.9  173.25  4390.1  170.91  4485.2  168.45  4547.1  170.58  4832.8  160.15
  4860.4  158.15  4896.3  159.16  4910.5  156.23  4931.4   157.4  4945.6  154.93
  4949.9  149.09    5000  149.81  5002.3  154.86  5016.8  152.66  5023.1  155.89
  5045.8  155.64  5052.1  158.18  5072.9  160.33  5101.9  158.55  5116.4 160.722
  5154.7  161.17  5373.9  160.29    5430  157.44  5450.8  161.12  5494.4  159.31
  5558.7  162.03  5652.1  160.94    5808  165.49  6015.5  164.24  6217.8  173.24
#Mann= 6 ,-1 , 0
  4310.9     .17       0  4390.1     .15       0  4547.1     .17       0
  4832.8     .09       0  5116.4     .15       0  5154.7     .17       0
Bank Sta=4832.8,5116.4
XS Rating Curve= 0 ,0
Exp/Cntr=0.3,0.1

Type RM Length L Ch R = 1 ,52000   ,500,500,500
BEGIN DESCRIPTION:
CRYSTAL CREEK 103.0
END DESCRIPTION:
XS GIS Cut Line= 3
       3868511.2     10110215.11      3868098.13     10110026.72
      3867117.83     10109461.06
#Sta/Elev= 30
    4546  175.19  4641.6  175.37  4744.7  171.74  4894.3  163.46  4913.2  162.61
  4929.1  159.01  4957.6   159.5  4980.6  156.73  4986.2  148.47  5021.1  148.47
  5025.2  154.27    5035   159.3    5041  160.29  5084.1  158.95  5115.7  155.06
  5150.4   157.3  5158.8  155.29  5164.6  157.39  5180.3  154.68  5186.1  156.06
  5208.1   154.2  5223.4  154.55  5239.2  158.57  5509.1   159.8  5619.8  160.01
  5678.7  162.56  5782.3  161.47  5845.3  164.09  6000.4  167.62  6131.8  173.43
#Mann= 8 ,-1 , 0
    4546     .17       0  4744.7     .15       0  4894.3     .17       0
  4913.2     .15       0  4957.6     .09       0    5041     .15       0
  5509.1     .17       0  5782.3     .11       0
Bank Sta=4957.6,5041
XS Rating Curve= 0 ,0
Exp/Cntr=0.3,0.1

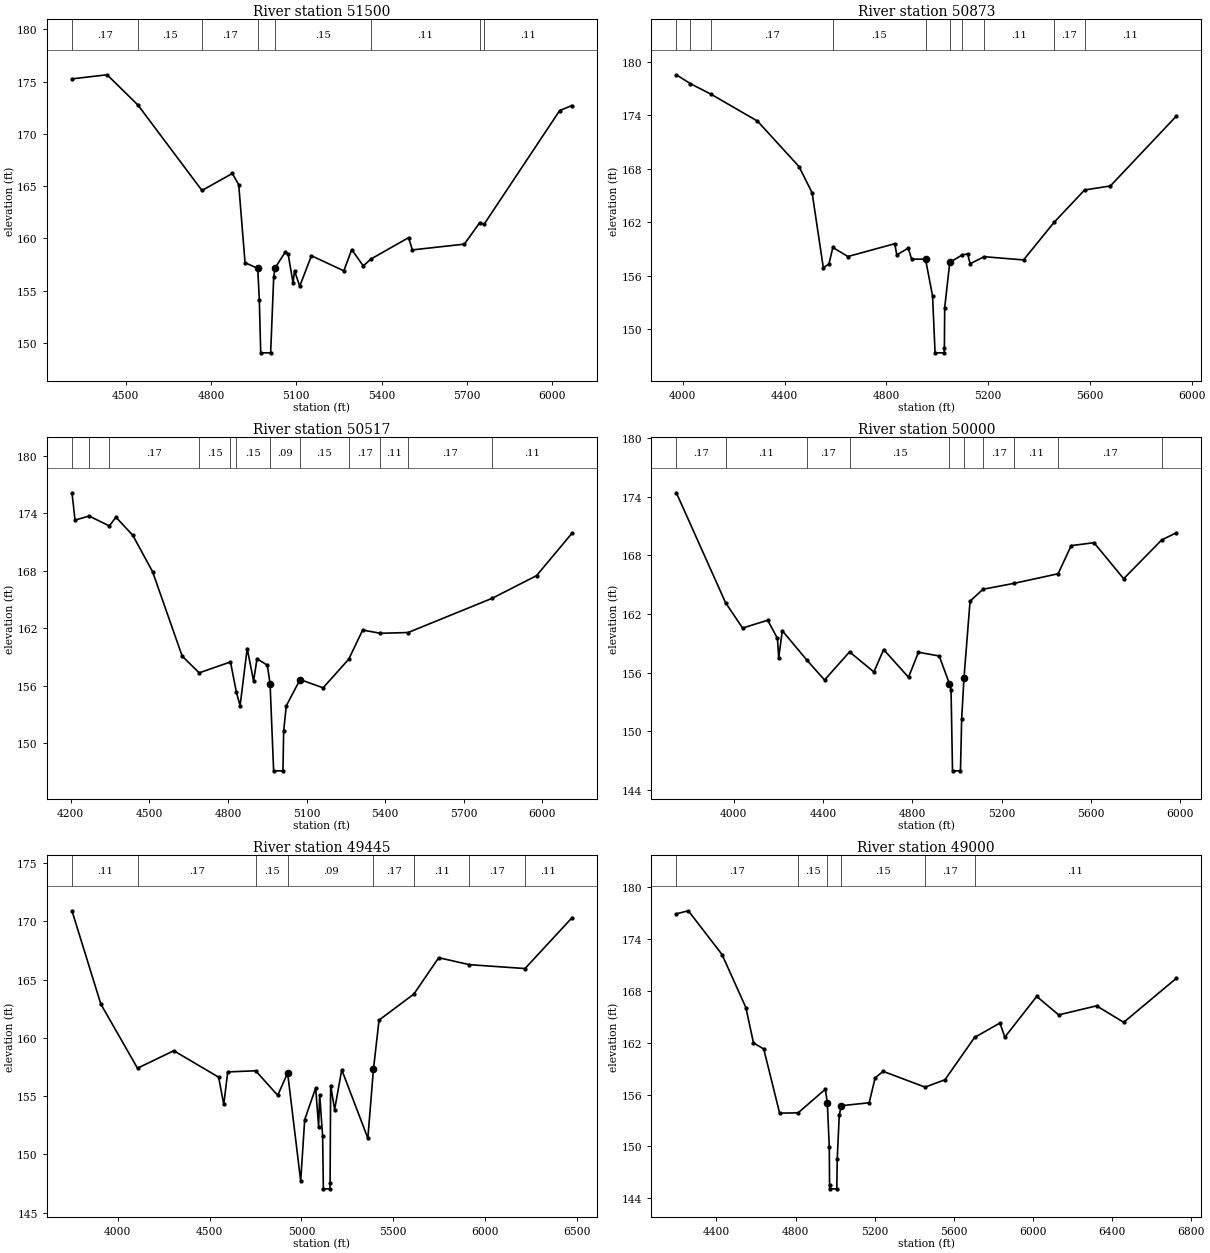
Type RM Length L Ch R = 1 ,51500   ,627,627,627
BEGIN DESCRIPTION:
CRYSTAL CREEK 102.0
END DESCRIPTION:
XS GIS Cut Line= 3
      3868528.55     10110176.05       3868218.3     10109561.75
      3867165.71     10109377.43
#Sta/Elev= 30
  4311.8  175.26  4435.2  175.65  4543.9  172.75  4768.6  164.59  4875.5  166.22
  4897.8  165.14    4920  157.69  4964.6  157.14  4970.2  154.14  4975.1  149.07
    5010  149.07  5020.8  156.31 5024.99157.1481  5061.4  158.71  5071.5  158.51
  5088.8  155.74  5093.9  156.92  5112.1  155.44  5153.4  158.35  5267.2  156.91
  5294.9  158.94  5335.5  157.38  5362.6  158.04  5494.8  160.08  5508.1  158.91
  5690.8  159.46  5744.1  161.49  5760.6  161.38  6025.8  172.23  6068.6  172.71
#Mann= 8 ,-1 , 0
  4311.8     .17       0  4543.9     .15       0  4768.6     .17       0
  4964.6     .09       0 5024.99     .15       0  5362.6     .11       0
  5744.1     .17       0  5760.6     .11       0
Bank Sta=4964.6,5024.99
XS Rating Curve= 0 ,0
Exp/Cntr=0.3,0.1

Type RM Length L Ch R = 1 ,50873   ,356,356,356
BEGIN DESCRIPTION:
CRYSTAL CREEK 101.0
END DESCRIPTION:
XS GIS Cut Line= 3
      3868964.27     10109664.98      3868057.37     10109187.32
      3867117.94     10109199.47
#Sta/Elev= 30
    3975  178.55  4029.9  177.56    4113  176.34  4293.8  173.35  4456.9  168.25
  4508.5  165.31  4552.5  156.89  4574.6  157.31    4590  159.17  4649.1  158.15
  4833.3  159.59  4841.2  158.33  4886.4   159.1  4899.4  157.86  4954.2  157.85
  4981.9  153.71  4991.7  147.34  5027.3  147.34  5028.3  147.84  5029.5   152.4
  5049.5  157.49  5098.3  158.33  5119.5  158.45  5129.5  157.34  5184.5  158.13
  5339.5  157.77  5458.9  161.97  5579.3  165.62  5680.6  166.07  5939.5   173.9
#Mann= 10 ,-1 , 0
    3975     .17       0  4029.9     .11       0    4113     .17       0
    4590     .15       0  4954.2     .09       0  5049.5     .15       0
  5098.3     .17       0  5184.5     .11       0  5458.9     .17       0
  5579.3     .11       0
Bank Sta=4954.2,5049.5
XS Rating Curve= 0 ,0
Exp/Cntr=0.3,0.1

Type RM Length L Ch R = 1 ,50517   ,517,517,517
BEGIN DESCRIPTION:
CRYSTAL CREEK 100.0
END DESCRIPTION:
XS GIS Cut Line= 3
      3869018.99     10109177.77      3868260.33     10108938.49
      3867153.74       10109055.
#Sta/Elev= 30
  4204.5  176.13  4216.2  173.28    4270   173.7  4347.1  172.67  4372.3  173.58
  4436.4   171.7  4512.2  167.89  4625.1  159.08    4690  157.33  4809.6  158.47
  4831.8  155.34  4846.2  153.89  4873.3  159.87  4897.7  156.49  4910.9   158.8
  4950.2  158.13  4960.7  156.17  4974.3   147.1  5009.9   147.1  5012.5  151.27
  5022.6  153.89  5075.2  156.63  5163.1  155.77    5261  158.76  5314.2   161.8
  5381.5  161.46  5487.6  161.54  5809.1  165.12  5977.9  167.48  6112.7  171.89
#Mann= 12 ,-1 , 0
  4204.5     .17       0    4270     .11       0  4347.1     .17       0
    4690     .15       0  4809.6     .11       0  4831.8     .15       0
  4960.7     .09       0  5075.2     .15       0    5261     .17       0
  5381.5     .11       0  5487.6     .17       0  5809.1     .11       0
Bank Sta=4960.7,5075.2
XS Rating Curve= 0 ,0
Exp/Cntr=0.3,0.1

Type RM Length L Ch R = 1 ,50000   ,555,555,555
BEGIN DESCRIPTION:
CRYSTAL CREEK 99.0
END DESCRIPTION:
XS GIS Cut Line= 3
      3869244.69     10109099.65      3868148.19     10108483.61
      3867187.35     10108687.33
#Sta/Elev= 30
  3742.3  174.41  3962.7  163.16    4039  160.56  4151.6  161.36  4195.2   159.5
    4201  157.51  4216.9  160.29    4327  157.28  4406.3  155.24  4518.5  158.12
  4627.5  156.06  4670.9  158.36  4782.5  155.52  4827.1  158.08  4920.1   157.7
    4966  154.85  4973.1  154.24  4979.7  145.94  5015.3  145.94  5020.8  151.29
    5031  155.44  5058.3  163.31  5116.1  164.53  5256.1  165.14  5452.9  166.12
  5511.5     169  5613.7   169.3  5746.6  165.61  5916.9  169.58  5982.2  170.31
#Mann= 10 ,-1 , 0
  3742.3     .17       0  3962.7     .11       0    4327     .17       0
  4518.5     .15       0    4966     .09       0    5031     .15       0
  5116.1     .17       0  5256.1     .11       0  5452.9     .17       0
  5916.9     .11       0
Bank Sta=4966,5031
XS Rating Curve= 0 ,0
Exp/Cntr=0.3,0.1

Type RM Length L Ch R = 1 ,49445   ,445,445,445
BEGIN DESCRIPTION:
CRYSTAL CREEK 98.0
END DESCRIPTION:
XS GIS Cut Line= 3
       3869587.6     10108813.21      3868321.65     10108118.38
      3867063.85     10108337.83
#Sta/Elev= 30
  3750.8  170.92  3907.8  162.91  4107.5   157.4  4304.9   158.9    4549  156.63
  4576.9  154.29  4598.7  157.08  4750.5  157.18  4870.6  155.07  4924.6  156.99
  4995.7  147.71  5017.5  152.98  5077.2   155.7  5093.3  152.38    5099  155.13
  5115.1  151.55  5119.1  147.04  5154.7  147.04  5155.7  147.54  5158.7  155.91
  5180.5  153.85  5219.1  157.27  5361.2  151.39  5391.6  157.29  5422.1  161.53
  5611.9  163.77  5746.9  166.89  5914.3  166.29  6216.8  165.96  6471.7  170.31
#Mann= 8 ,-1 , 0
  3750.8     .11       0  4107.5     .17       0  4750.5     .15       0
  4924.6     .09       0  5391.6     .17       0  5611.9     .11       0
  5914.3     .17       0  6216.8     .11       0
Bank Sta=4924.6,5391.6
XS Rating Curve= 0 ,0
Exp/Cntr=0.3,0.1

Type RM Length L Ch R = 1 ,49000   ,500,500,500
BEGIN DESCRIPTION:
CRYSTAL CREEK 97.0
END DESCRIPTION:
XS GIS Cut Line= 3
      3869517.82     10107911.07      3868718.51      10107839.6
      3867008.44     10108059.86
#Sta/Elev= 30
  4197.5  176.94  4258.2  177.29  4428.4  172.22  4548.9  166.08  4587.2  161.99
  4639.2  161.28  4719.5  153.85  4812.8  153.88  4950.5  156.62  4960.5  155.07
  4970.5  149.91  4971.8  145.58  4972.8  145.08  5008.4  145.08  5010.7  148.54
  5020.8  153.59  5030.9  154.71  5172.1  155.05  5202.3  157.94  5242.6  158.69
  5454.9  156.86  5555.2  157.72  5704.9  162.62    5833  164.29  5857.7  162.65
    6019  167.37  6129.9  165.23  6321.5  166.28  6458.6  164.37  6724.2  169.46
#Mann= 6 ,-1 , 0
  4197.5     .17       0  4812.8     .15       0  4960.5     .09       0
  5030.9     .15       0  5454.9     .17       0  5704.9     .11       0
Bank Sta=4960.5,5030.9
XS Rating Curve= 0 ,0
Exp/Cntr=0.3,0.1

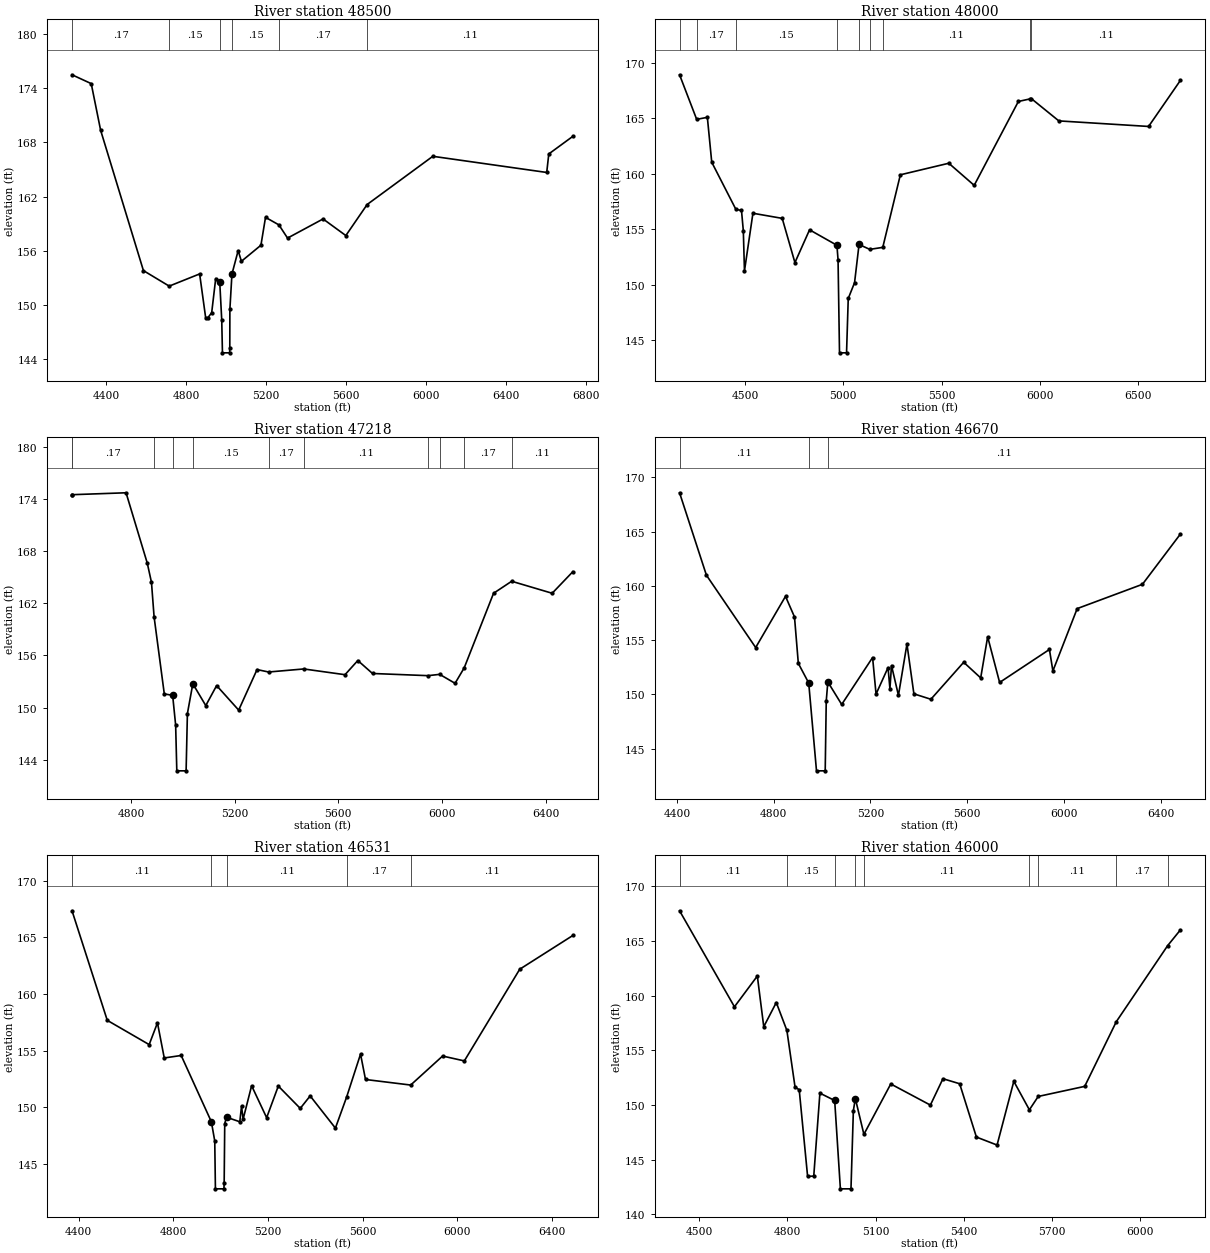
Type RM Length L Ch R = 1 ,48500   ,500,500,500
BEGIN DESCRIPTION:
CRYSTAL CREEK 96.0
END DESCRIPTION:
XS GIS Cut Line= 3
      3869493.52     10107364.47      3868726.39     10107426.07
       3867051.7     10107871.84
#Sta/Elev= 30
  4230.4   175.5  4326.4  174.52  4373.4  169.35  4587.2  153.81    4716  152.09
  4868.1  153.44  4898.2  148.59  4908.2  148.56  4928.3  149.14  4948.4  152.93
  4968.4   152.6  4978.5  148.36  4982.1   144.7  5017.8   144.7  5018.8   145.2
  5019.2  149.51  5029.5  153.42  5060.6  156.02  5076.9  154.84  5174.4  156.62
  5197.3  159.71  5264.4  158.87  5307.4  157.41  5484.9  159.53  5598.7  157.69
  5705.2  161.13  6033.3  166.47  6602.5  164.68  6612.8  166.73    6733  168.68
#Mann= 6 ,-1 , 0
  4230.4     .17       0    4716     .15       0  4968.4     .09       0
  5029.5     .15       0  5264.4     .17       0  5705.2     .11       0
Bank Sta=4968.4,5029.5
XS Rating Curve= 0 ,0
Exp/Cntr=0.3,0.1

Type RM Length L Ch R = 1 ,48000   ,782,782,782
BEGIN DESCRIPTION:
CRYSTAL CREEK 95.0
END DESCRIPTION:
XS GIS Cut Line= 3
      3869319.94     10106661.33      3868600.76     10107079.85
      3867048.49     10107805.48
#Sta/Elev= 30
  4167.9   168.9  4254.9  164.89  4309.2  165.07  4331.5  161.03  4454.2  156.79
  4482.7  156.69    4492  154.87  4497.8  151.25  4540.8  156.44  4689.7  155.98
  4754.3     152  4828.7  154.95  4967.7  153.56  4973.5  152.26  4980.9  143.88
  5016.7  143.88  5025.3  148.77  5057.4  150.19  5080.2  153.63  5134.8  153.19
  5200.8  153.37  5290.2   159.9  5536.4  160.94  5665.5  158.95  5890.1   166.5
  5949.7  166.73  5955.6  166.76  6095.7  164.75  6551.9  164.25  6713.5  168.39
#Mann= 9 ,-1 , 0
  4167.9     .11       0  4254.9     .17       0  4454.2     .15       0
  4967.7     .09       0  5080.2     .15       0  5134.8     .17       0
  5200.8     .11       0  5949.7     .17       0  5955.6     .11       0
Bank Sta=4967.7,5080.2
XS Rating Curve= 0 ,0
Exp/Cntr=0.3,0.1

Type RM Length L Ch R = 1 ,47218   ,548,548,548
BEGIN DESCRIPTION:
CRYSTAL CREEK 94.0
END DESCRIPTION:
XS GIS Cut Line= 3
      3868859.86     10106249.01      3868482.92     10106451.96
      3867375.95     10107471.73
#Sta/Elev= 30
  4571.9  174.47    4572  174.47  4780.5  174.69  4862.4   166.6  4878.6  164.39
  4888.7  160.43  4928.1  151.57  4960.3  151.41  4971.9  147.99  4976.4  142.73
  5012.3  142.73  5017.3  149.31  5038.2  152.74  5088.2  150.23  5130.1  152.53
  5215.2  149.71  5286.1  154.37  5330.7  154.09  5466.4  154.44  5625.7  153.78
  5675.1  155.41  5731.8  153.92  5946.4  153.67    5991  153.82  6050.5  152.79
  6085.8  154.57  6199.1  163.14    6269  164.52  6425.3  163.14  6505.1  165.62
#Mann= 11 ,-1 , 0
  4571.9     .11       0    4572     .17       0  4888.7     .15       0
  4960.3     .09       0  5038.2     .15       0  5330.7     .17       0
  5466.4     .11       0  5946.4     .17       0    5991     .11       0
  6085.8     .17       0    6269     .11       0
Bank Sta=4960.3,5038.2
XS Rating Curve= 0 ,0
Exp/Cntr=0.3,0.1

Type RM Length L Ch R = 1 ,46670   ,139,139,139
BEGIN DESCRIPTION:
CRYSTAL CREEK 93.0
END DESCRIPTION:
XS GIS Cut Line= 3
      3868644.16     10105847.53      3868134.51     10106143.19
      3867195.65     10107290.13
#Sta/Elev= 30
  4410.8  168.59  4521.9  160.99  4725.6  154.32    4849  159.04  4886.2  157.14
    4902  152.86    4945  151.05  4977.2  142.95  5013.2  142.95  5017.5  149.38
    5024  151.15  5081.4  149.07  5209.2   153.4  5223.5  150.03  5273.1  152.47
  5280.9  150.52  5287.4  152.66  5316.1  149.91  5351.3  154.64    5380  150.05
  5450.3  149.55    5586  152.96  5656.3  151.52  5685.1  155.31  5734.6   151.1
  5940.6  154.14  5954.9  152.16  6055.4  157.91  6325.3  160.15  6482.2  164.78
#Mann= 3 , 0 , 0
  4410.8     .11       0    4945     .09       0    5024     .11       0
Bank Sta=4945,5024
XS Rating Curve= 0 ,0
Exp/Cntr=0.3,0.1

Type RM Length L Ch R = 1 ,46531   ,531,531,531
BEGIN DESCRIPTION:
CRYSTAL CREEK 92.0
END DESCRIPTION:
XS GIS Cut Line= 3
       3868474.3     10105688.15      3867992.67     10106090.52
      3866995.46     10107196.15
#Sta/Elev= 30
  4372.4  167.35  4521.4  157.68  4698.4  155.54  4733.5  157.46  4762.2  154.36
  4833.7  154.58  4961.3  148.73  4975.6  147.03  4978.4  142.81  5014.4  142.81
  5015.4  143.31  5017.8  148.57  5025.3  149.13  5081.5  148.73  5088.8  150.11
  5095.5  148.96  5131.4  151.91  5194.9  149.09  5244.2  151.88  5336.9  149.91
  5378.8  151.01  5485.5  148.17  5532.9  150.91  5591.7   154.7  5612.7  152.46
  5803.6  151.97  5938.5  154.53  6030.4   154.1  6264.4  162.19  6488.9  165.17
#Mann= 5 ,-1 , 0
  4372.4     .11       0  4961.3     .09       0  5025.3     .11       0
  5532.9     .17       0  5803.6     .11       0
Bank Sta=4961.3,5025.3
XS Rating Curve= 0 ,0
Exp/Cntr=0.3,0.1

Type RM Length L Ch R = 1 ,46000   ,500,500,500
BEGIN DESCRIPTION:
CRYSTAL CREEK 91.0
END DESCRIPTION:
XS GIS Cut Line= 3
      3868034.75     10105584.53      3867609.49     10105958.34
      3866855.26     10106807.29
#Sta/Elev= 30
  4433.8  167.74  4620.3  158.97  4698.1  161.78  4719.9  157.15  4762.5  159.36
  4798.5  156.81  4826.2  151.64  4840.4  151.39  4868.9  143.48  4889.8   143.5
  4910.7  151.08  4960.9  150.41  4980.3  142.34  5016.3  142.34  5024.4  149.48
  5031.1  150.59  5060.2  147.32  5151.5  151.92  5286.1  149.99  5328.8   152.4
  5385.6  151.94  5442.5  147.07  5512.7  146.34  5569.6  152.16  5622.5  149.56
  5652.6  150.78  5810.5   151.7  5917.9  157.61  6092.2  164.55  6135.6  165.99
#Mann= 9 ,-1 , 0
  4433.8     .11       0  4798.5     .15       0  4960.9     .09       0
  5031.1     .15       0  5060.2     .11       0  5622.5     .17       0
  5652.6     .11       0  5917.9     .17       0  6092.2     .11       0
Bank Sta=4960.9,5031.1
XS Rating Curve= 0 ,0
Exp/Cntr=0.3,0.1

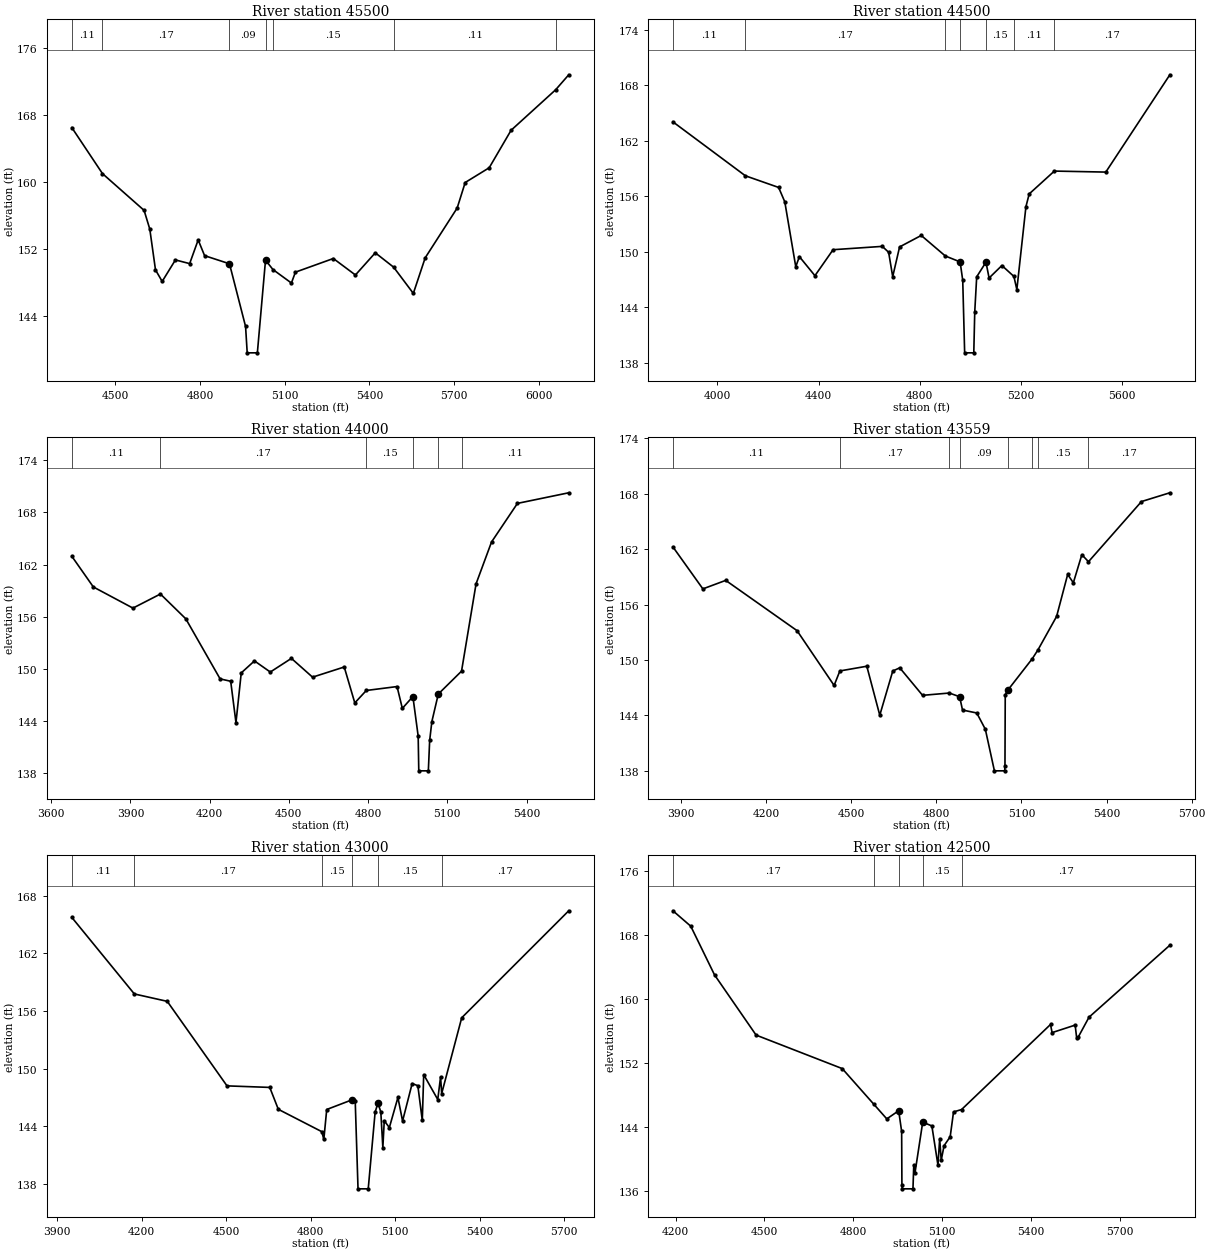
Type RM Length L Ch R = 1 ,45500   ,1000,1000,1000
BEGIN DESCRIPTION:
CRYSTAL CREEK 90.0
END DESCRIPTION:
XS GIS Cut Line= 3
      3868021.76     10105493.38      3867372.86     10105581.08
       3866624.2     10106396.12
#Sta/Elev= 30
  4345.2  166.55  4453.9  161.05  4601.4  156.66  4621.6  154.42  4641.8  149.55
  4665.5  148.17  4712.4  150.74  4762.9   150.3  4793.1  153.13  4815.8  151.25
  4904.1  150.28  4961.1  142.79  4966.9  139.64  5002.9  139.64  5031.8  150.71
  5058.2  149.59  5123.6  147.98  5137.8  149.28  5272.2  150.91  5350.5  148.94
  5420.9  151.59  5486.1  149.87  5555.8  146.74  5597.8  150.99  5711.2  156.94
  5739.6  159.99  5824.7  161.75  5902.3  166.23  6060.3  171.07  6106.7  172.86
#Mann= 7 ,-1 , 0
  4345.2     .11       0  4453.9     .17       0  4904.1     .09       0
  5031.8     .17       0  5058.2     .15       0  5486.1     .11       0
  6060.3    .125       0
Bank Sta=4904.1,5031.8
XS Rating Curve= 0 ,0
Exp/Cntr=0.3,0.1

Type RM Length L Ch R = 1 ,44500   ,500,500,500
BEGIN DESCRIPTION:
CRYSTAL CREEK 89.0
END DESCRIPTION:
XS GIS Cut Line= 3
      3868105.48     10105269.44      3866958.35     10105527.05
      3866312.27     10105979.06
#Sta/Elev= 30
  3824.3  164.06  4110.7  158.23  4242.1  156.97  4266.5  155.41  4309.8   148.4
  4324.1  149.49  4385.6  147.43  4457.3  150.24    4652   150.6  4676.9  149.96
    4693  147.33  4720.2  150.54  4805.8  151.78    4901  149.56  4959.5  148.92
  4969.8  146.93  4977.4  139.09  5013.5  139.09  5017.3  143.52    5025  147.31
  5061.6  148.89    5074  147.18  5124.6  148.53  5172.1  147.35  5183.7  145.93
  5219.6  154.89  5232.5  156.27    5332  158.74  5535.3  158.63  5788.5  169.15
#Mann= 7 ,-1 , 0
  3824.3     .11       0  4110.7     .17       0    4901     .15       0
  4959.5     .09       0  5061.6     .15       0  5172.1     .11       0
    5332     .17       0
Bank Sta=4959.5,5061.6
XS Rating Curve= 0 ,0
Exp/Cntr=0.3,0.1

Type RM Length L Ch R = 1 ,44000   ,441,441,441
BEGIN DESCRIPTION:
CRYSTAL CREEK 88.0
END DESCRIPTION:
XS GIS Cut Line= 3
      3868109.38     10105214.73      3866787.54     10105227.23
      3866252.33     10105391.65
#Sta/Elev= 30
  3678.1  162.96  3759.6  159.43  3909.6     157  4013.6  158.62  4109.7  155.77
  4239.7  148.86  4279.7  148.59  4299.7  143.84  4319.7  149.55  4369.7  150.93
  4429.7  149.65  4509.7  151.22  4589.7  149.06  4709.7  150.23  4749.7   146.1
  4793.3  147.53  4909.7  147.98  4929.7  145.47  4969.7  146.83  4989.7  142.28
    4992  138.29  5028.2  138.29  5033.2  141.78  5041.5  143.95  5065.9  147.12
  5153.9  149.75  5208.9  159.79  5267.5   164.6  5365.6  169.04  5559.9  170.26
#Mann= 6 ,-1 , 0
  3678.1     .11       0  4013.6     .17       0  4793.3     .15       0
  4969.7     .09       0  5065.9     .15       0  5153.9     .11       0
Bank Sta=4969.7,5065.9
XS Rating Curve= 0 ,0
Exp/Cntr=0.3,0.1

Type RM Length L Ch R = 1 ,43559   ,559,559,559
BEGIN DESCRIPTION:
CRYSTAL CREEK 87.0
END DESCRIPTION:
XS GIS Cut Line= 3
      3868112.87     10105009.87      3866990.48      10104887.9
      3866367.81     10104911.07
#Sta/Elev= 30
    3871  162.24  3976.6   157.7  4057.1  158.62  4308.6  153.18  4439.3  147.25
  4459.6  148.82  4554.6  149.33  4600.3  144.03  4646.1  148.81  4670.7  149.16
  4751.2  146.18  4845.5  146.43  4881.9  146.03    4892  144.59  4942.3  144.27
  4972.5  142.51  5004.5  138.01  5040.7  138.01  5041.7  138.51  5042.7  146.24
  5052.7  146.78  5138.4  150.16  5157.7  151.08  5223.8  154.72  5262.8  159.26
  5282.8  158.36  5312.8   161.4  5336.2  160.64    5523  167.15  5623.1   168.1
#Mann= 8 ,-1 , 0
    3871     .11       0  4459.6     .17       0  4845.5     .15       0
  4881.9     .09       0  5052.7     .15       0  5138.4     .17       0
  5157.7     .15       0  5336.2     .17       0
Bank Sta=4881.9,5052.7
XS Rating Curve= 0 ,0
Exp/Cntr=0.3,0.1

Type RM Length L Ch R = 1 ,43000   ,500,500,500
BEGIN DESCRIPTION:
CRYSTAL CREEK 86.0
END DESCRIPTION:
XS GIS Cut Line= 3
      3868162.91      10104766.9      3867126.26     10104614.48
      3866417.86     10104511.07
#Sta/Elev= 30
  3952.2  165.75  4174.1  157.78  4290.9  157.01    4503  148.21  4654.7  148.05
  4685.1  145.77  4839.6  143.44  4846.6  142.63  4856.9  145.75  4947.8  146.77
    4958  146.67    4968  137.49  5004.2  137.49  5028.7  145.48  5038.8  146.42
  5048.9  145.49  5056.1  141.78  5061.1  144.58  5079.2  143.87  5109.6     147
  5126.1  144.55  5160.1  148.45  5180.3  148.23  5196.1  144.61  5201.1  149.38
    5251  146.79    5261  149.15  5264.9  147.41    5336   155.3  5715.9  166.44
#Mann= 6 ,-1 , 0
  3952.2     .11       0  4174.1     .17       0  4839.6     .15       0
  4947.8     .09       0  5038.8     .15       0  5264.9     .17       0
Bank Sta=4947.8,5038.8
XS Rating Curve= 0 ,0
Exp/Cntr=0.3,0.1

Type RM Length L Ch R = 1 ,42500   ,500,500,500
BEGIN DESCRIPTION:
CRYSTAL CREEK 85.0
END DESCRIPTION:
XS GIS Cut Line= 3
      3868067.87     10104261.07      3867261.18      10104204.1
      3866417.81     10104411.08
#Sta/Elev= 30
  4191.3  171.01  4251.5  169.08  4331.7  162.99    4472  155.46  4762.7  151.27
  4868.6  146.84  4913.1  144.98  4953.2     146  4963.2  143.41  4964.1  136.73
  4965.1  136.23  5001.4  136.23  5004.1  139.21  5008.4  138.27  5034.3  144.57
  5065.2   144.1  5085.8  139.18  5091.6  142.51  5096.7  139.79  5106.4  141.63
    5127  142.74  5138.3  145.85  5165.5  146.15  5465.7  156.79  5470.9  155.77
  5548.8  156.71    5554  155.07  5559.5  155.23  5595.6   157.7  5868.4   166.7
#Mann= 5 ,-1 , 0
  4191.3     .17       0  4868.6     .15       0  4953.2     .09       0
  5034.3     .15       0  5165.5     .17       0
Bank Sta=4953.2,5034.3
XS Rating Curve= 0 ,0
Exp/Cntr=0.3,0.1

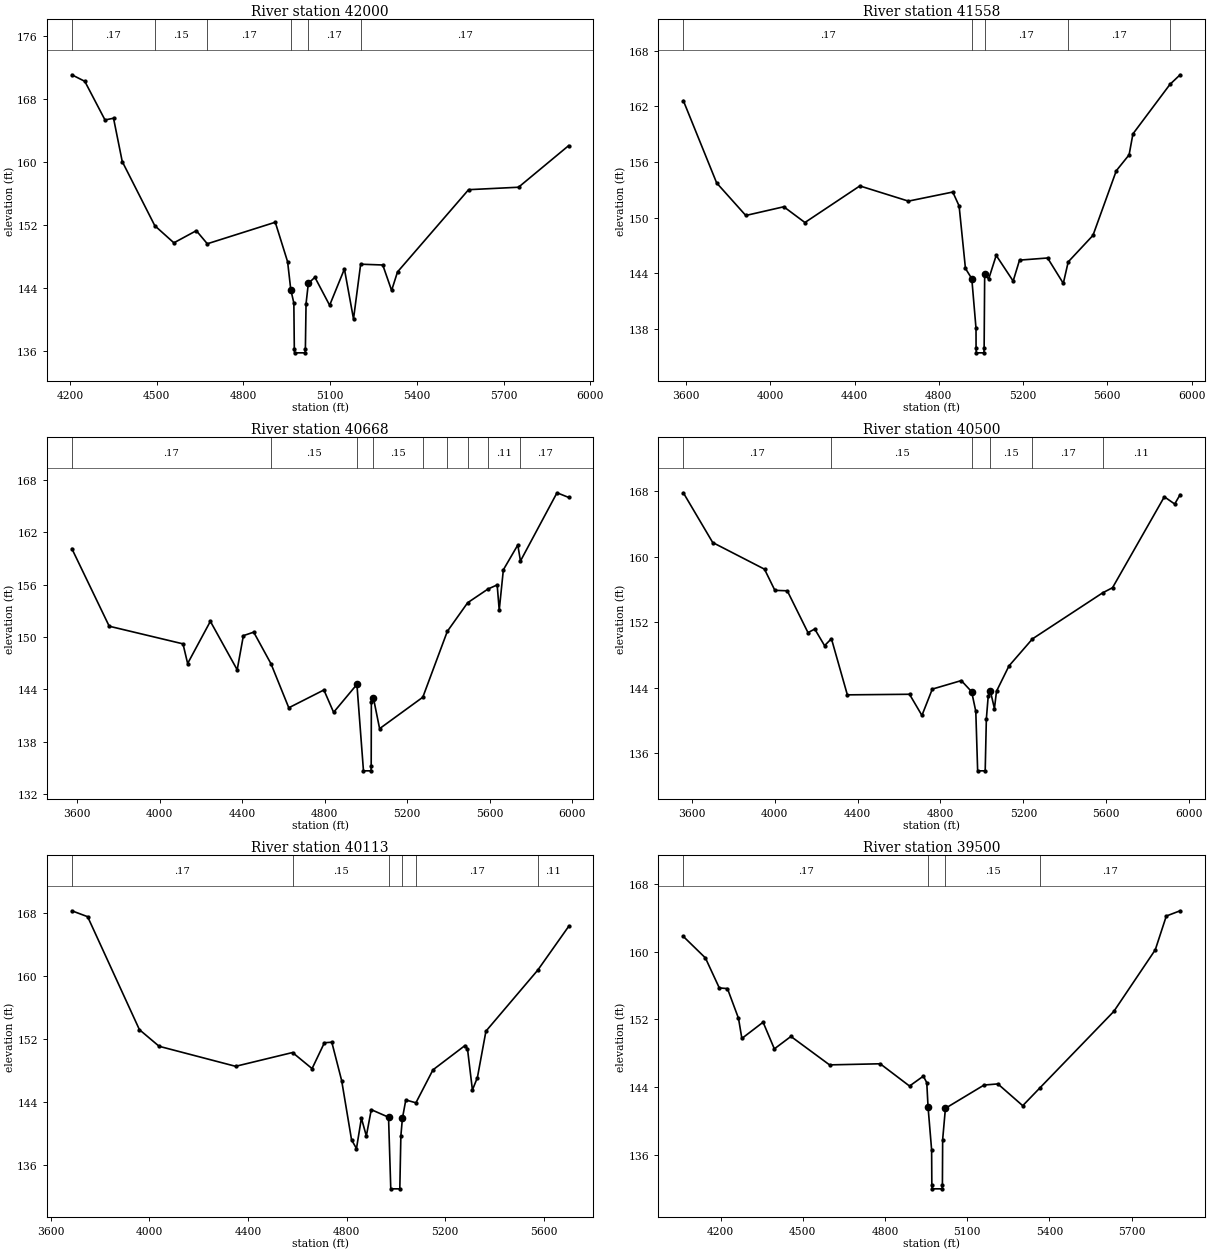
Type RM Length L Ch R = 1 ,42000   ,442,442,442
BEGIN DESCRIPTION:
CRYSTAL CREEK 84.0
END DESCRIPTION:
XS GIS Cut Line= 3
      3868089.42      10104129.2      3867354.39     10103830.53
      3866448.06     10104016.44
#Sta/Elev= 30
  4206.6  171.03  4251.5   170.2  4321.4   165.3  4350.9  165.52    4381  160.03
  4493.7  151.89  4559.7  149.72  4637.3  151.26  4675.3   149.6  4910.4  152.33
  4953.1  147.32    4964   143.8  4974.7  142.08  4976.3  136.27  4977.3  135.77
  5013.6  135.77  5014.6  136.27  5016.9     142  5024.8  144.58  5047.5  145.35
  5098.5   141.8  5149.6   146.4  5181.1  140.07  5205.8  147.01  5282.3  146.91
  5312.9  143.68  5333.3  146.03  5579.2  156.46  5751.9  156.77  5925.2  162.04
#Mann= 6 ,-1 , 0
  4206.6     .17       0  4493.7     .15       0  4675.3     .17       0
    4964     .09       0  5024.8     .17       0  5205.8     .17       0
Bank Sta=4964,5024.8
XS Rating Curve= 0 ,0
Exp/Cntr=0.3,0.1

Type RM Length L Ch R = 1 ,41558   ,890,890,890
BEGIN DESCRIPTION:
CRYSTAL CREEK 83.0
END DESCRIPTION:
XS GIS Cut Line= 3
      3868713.56     10103537.65      3867304.29     10103432.36
      3866417.87     10103761.06
#Sta/Elev= 30
  3586.8  162.63  3745.1  153.74  3883.3  150.23  4063.8  151.17  4164.1  149.47
  4424.8  153.42  4655.5  151.78  4866.1  152.76  4896.1  151.26  4926.2  144.51
  4956.3  143.41  4976.4  138.03  4976.6   135.9  4977.6   135.4  5013.9   135.4
  5014.9   135.9  5017.5  143.89  5036.5  143.37  5072.2  145.92  5152.7  143.15
    5183  145.41  5316.2  145.64  5390.8   142.9  5414.1  145.22  5531.6  148.08
  5642.4  155.06  5703.2  156.78  5721.4  159.04  5897.4  164.39  5945.4  165.42
#Mann= 5 ,-1 , 0
  3586.8     .17       0  4956.3     .09       0  5017.5     .17       0
  5414.1     .17       0  5897.4     .11       0
Bank Sta=4956.3,5017.5
XS Rating Curve= 0 ,0
Exp/Cntr=0.3,0.1

Type RM Length L Ch R = 1 ,40668   ,168,168,168
BEGIN DESCRIPTION:
CRYSTAL CREEK 82.0
END DESCRIPTION:
XS GIS Cut Line= 3
      3868648.98     10102948.32      3867223.98     10102889.71
       3866241.5     10102883.22
#Sta/Elev= 30
  3573.8  160.13  3755.1  151.24  4112.8  149.22  4135.4  146.97  4245.5   151.8
  4375.6  146.25  4405.6  150.16  4455.7  150.56  4539.7  146.93  4625.8   141.9
    4796  143.94  4843.1  141.38  4956.1  144.58  4987.9  134.68  5024.3  134.68
  5025.3  135.18  5026.1  142.56  5036.1  143.03  5066.1  139.51  5275.6  143.11
  5394.4  150.65    5493  153.93  5591.6   155.5  5636.1  155.97  5646.1  153.08
  5666.1   157.7  5736.1  160.54  5749.1  158.71  5926.2  166.52  5982.5  165.99
#Mann= 9 ,-1 , 0
  3573.8     .17       0  4539.7     .15       0  4956.1     .09       0
  5036.1     .15       0  5275.6     .17       0  5394.4     .11       0
    5493     .17       0  5591.6     .11       0  5749.1     .17       0
Bank Sta=4956.1,5036.1
XS Rating Curve= 0 ,0
Exp/Cntr=0.3,0.1

Type RM Length L Ch R = 1 ,40500   ,387,387,387
BEGIN DESCRIPTION:
CRYSTAL CREEK 81.0
END DESCRIPTION:
XS GIS Cut Line= 3
      3868619.73     10102753.53      3867178.33     10102736.52
      3866221.65     10102711.89
#Sta/Elev= 30
  3558.5  167.79  3700.4  161.72  3950.4  158.47  4000.4  155.89  4060.4  155.83
  4160.4  150.73    4193  151.17  4240.4  149.14  4273.5  149.99  4350.4  143.14
  4650.5  143.21  4710.5  140.63  4760.5  143.84  4900.5  144.88  4950.5  143.52
  4970.5  141.13  4979.5  133.87  5015.9  133.87  5021.5  140.21  5030.5  142.99
  5040.5  143.65  5060.5  141.47  5070.5  143.58  5130.5  146.66  5244.2  149.97
  5583.3  155.59  5630.7  156.21  5880.8   167.3  5930.8  166.42    5957  167.56
#Mann= 6 ,-1 , 0
  3558.5     .17       0  4273.5     .15       0  4950.5     .09       0
  5040.5     .15       0  5244.2     .17       0  5583.3     .11       0
Bank Sta=4950.5,5040.5
XS Rating Curve= 0 ,0
Exp/Cntr=0.3,0.1

Type RM Length L Ch R = 1 ,40113   ,613,613,613
BEGIN DESCRIPTION:
CRYSTAL CREEK 80.0
END DESCRIPTION:
XS GIS Cut Line= 3
      3868341.94     10102392.42      3867028.04     10102394.49
      3866328.09     10102416.72
#Sta/Elev= 30
  3686.1  168.23  3750.2  167.48  3960.2  153.14  4040.2  151.03  4350.2  148.49
    4581  150.24  4660.2   148.2  4710.2  151.48  4740.2  151.55  4780.2  146.67
  4820.2  139.17  4840.2  138.05  4860.2  141.91  4880.2  139.65  4900.2  142.99
  4970.2  142.03  4979.3  132.94  5015.9  132.94  5020.2  139.66 5026.41 141.877
  5040.2  144.22  5081.2  143.86  5150.3  148.04  5280.3  151.13  5290.3  150.71
  5310.3  145.49  5330.4  147.05  5365.1  152.95  5575.3   160.7  5700.3  166.24
#Mann= 6 ,-1 , 0
  3686.1     .17       0    4581     .15       0  4970.2     .09       0
 5026.41     .15       0  5081.2     .17       0  5575.3     .11       0
Bank Sta=4970.2,5026.41
XS Rating Curve= 0 ,0
Exp/Cntr=0.3,0.1

Type RM Length L Ch R = 1 ,39500   ,500,500,500
BEGIN DESCRIPTION:
CRYSTAL CREEK 79.0
END DESCRIPTION:
XS GIS Cut Line= 3
      3868167.84     10101961.07      3867238.34       10102072.
      3866367.88     10101961.07
#Sta/Elev= 30
  4063.9   161.8  4144.5  159.26  4195.2  155.72    4225  155.64  4265.3  152.13
  4277.6  149.75  4355.1  151.67  4396.2  148.52  4456.7  149.99  4597.7  146.63
  4782.6  146.76  4889.7  144.13  4940.1   145.3  4952.6  144.53  4957.3141.6546
  4970.3   136.6  4971.1  132.49  4972.1  131.99  5008.7  131.99  5009.7  132.49
  5010.6  137.81  5020.7   141.5  5161.8  144.25  5212.2  144.38  5302.9  141.81
  5366.4  143.94  5635.6  152.95  5786.8  160.22  5827.1  164.21  5877.5  164.83
#Mann= 4 ,-1 , 0
  4063.9     .17       0  4957.3     .09       0  5020.7     .15       0
  5366.4     .17       0
Bank Sta=4957.3,5020.7
XS Rating Curve= 0 ,0
Exp/Cntr=0.3,0.1