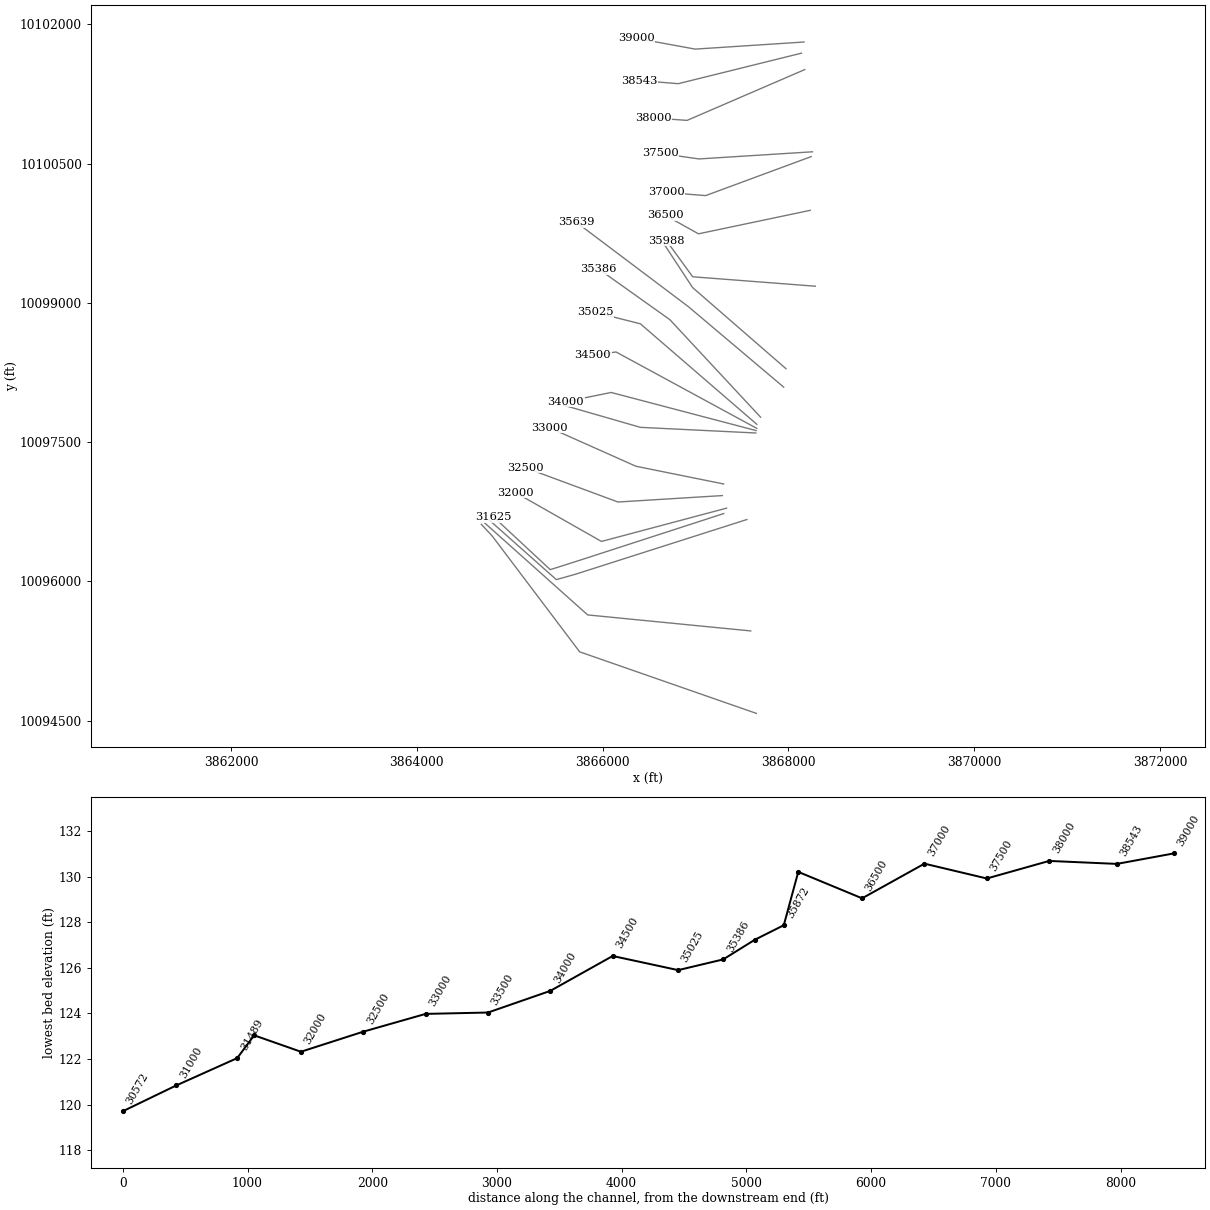
HEC-RAS study CRYSTAL CREEK.prj: CRYSTAL CREEK Base Level Engineering

--- CRYSTAL CREEK.g01 (geometry) --- (continued)

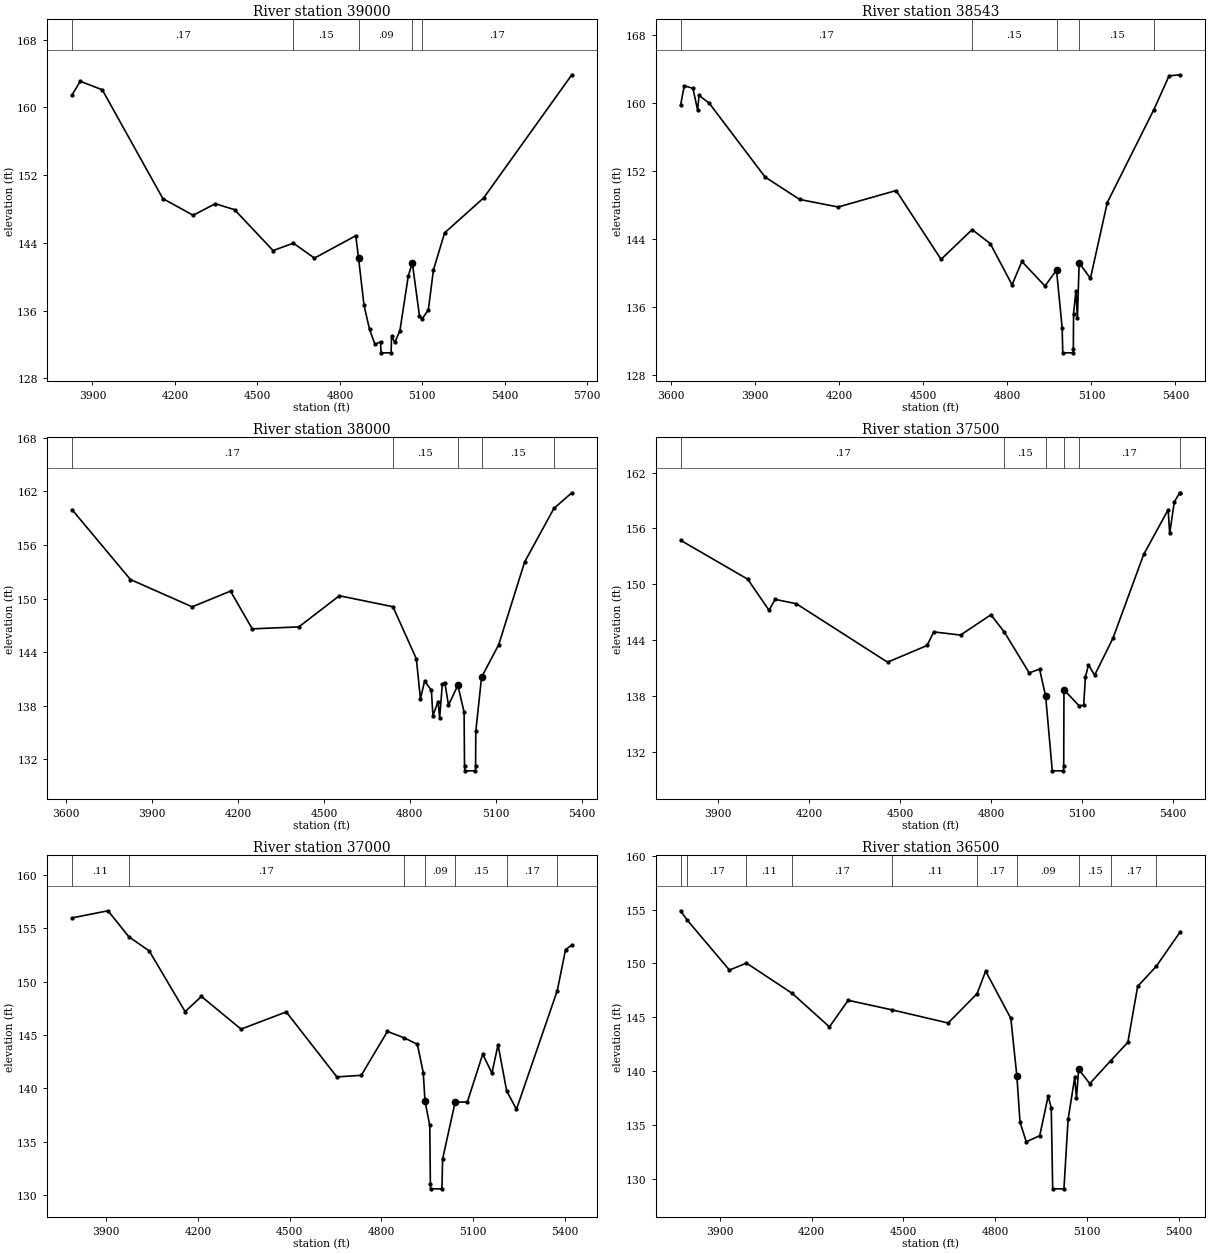
Type RM Length L Ch R = 1 ,39000   ,457,457,457
BEGIN DESCRIPTION:
CRYSTAL CREEK 78.0
END DESCRIPTION:
XS GIS Cut Line= 3
      3868167.85     10101811.07      3866995.84     10101734.73
      3866362.78     10101850.75
#Sta/Elev= 30
  3825.5  161.47  3855.6  163.09  3935.7  162.09  4156.2  149.23  4266.4  147.27
  4346.6  148.63  4416.8  147.93    4557   143.1  4630.9  143.97  4707.4  142.21
  4857.7  144.85  4867.7  142.26  4887.7  136.65  4907.8  133.79  4927.8  132.01
  4947.9  132.33  4949.6  131.02  4986.3  131.02    4988  132.99    5000  132.27
  5018.3  133.63  5048.8  140.11  5063.5  141.63  5089.4  135.39  5098.7     135
  5121.7  136.09  5140.3  140.81  5180.9  145.19  5323.3  149.33  5643.6  163.86
#Mann= 5 ,-1 , 0
  3825.5     .17       0  4630.9     .15       0  4867.7     .09       0
  5063.5     .15       0  5098.7     .17       0
Bank Sta=4867.7,5063.5
XS Rating Curve= 0 ,0
Exp/Cntr=0.3,0.1

Type RM Length L Ch R = 1 ,38543   ,543,543,543
BEGIN DESCRIPTION:
CRYSTAL CREEK 77.0
END DESCRIPTION:
XS GIS Cut Line= 3
      3868140.55     10101691.02       3866813.9     10101362.16
      3866397.56     10101395.89
#Sta/Elev= 30
  3633.2  159.69  3646.3  161.98  3677.2  161.69    3694  159.13  3699.1  160.85
  3735.4  159.94  3934.8  151.25  4058.4  148.61  4195.8  147.72  4402.7  149.66
  4563.1  141.56  4674.1  145.06  4738.9  143.41  4816.6  138.57  4851.7  141.31
  4934.1  138.42  4975.3   140.3  4995.4  133.52  4997.7  130.56  5034.4  130.56
  5035.4  131.06  5036.2  135.17  5044.8  137.87  5049.8  134.61  5056.2  141.15
  5096.4  139.32  5156.6  148.24    5323  159.19  5377.3  163.16  5417.7  163.28
#Mann= 5 ,-1 , 0
  3633.2     .17       0  4674.1     .15       0  4975.3     .09       0
  5056.2     .15       0    5323     .11       0
Bank Sta=4975.3,5056.2
XS Rating Curve= 0 ,0
Exp/Cntr=0.3,0.1

Type RM Length L Ch R = 1 ,38000   ,500,500,500
BEGIN DESCRIPTION:
CRYSTAL CREEK 76.0
END DESCRIPTION:
XS GIS Cut Line= 3
      3868175.27     10101513.93      3866908.31     10100966.68
      3866543.36     10100993.11
#Sta/Elev= 30
  3619.9  159.97  3824.1  152.13  4039.8  149.07  4173.7  150.83  4249.6   146.6
  4412.3  146.82  4553.9  150.31    4741  149.08  4822.9  143.24  4837.1  138.76
  4851.8  140.76  4875.3  139.71  4880.8  136.87  4898.8  138.46  4904.3  136.64
  4913.4  140.38  4922.3  140.58  4935.1  138.06  4967.8  140.27  4989.6  137.27
  4991.1  131.19  4992.1  130.69  5028.8  130.69  5029.8  131.19  5030.5  135.11
  5050.6  141.18  5110.7  144.84    5201  154.09  5303.4   160.1  5365.9  161.85
#Mann= 5 ,-1 , 0
  3619.9     .17       0    4741     .15       0  4967.8     .09       0
  5050.6     .15       0  5303.4     .11       0
Bank Sta=4967.8,5050.6
XS Rating Curve= 0 ,0
Exp/Cntr=0.3,0.1

Type RM Length L Ch R = 1 ,37500   ,500,500,500
BEGIN DESCRIPTION:
CRYSTAL CREEK 75.0
END DESCRIPTION:
XS GIS Cut Line= 3
      3868258.71     10100628.29      3867037.23     10100551.42
      3866617.85     10100611.07
#Sta/Elev= 30
  3776.1  154.73  3997.4  150.54  4067.5   147.2  4087.6  148.37  4157.7   147.9
  4458.3  141.61  4588.6  143.41  4610.6  144.87  4698.8  144.53    4799  146.71
  4843.5  144.84  4925.1  140.46  4959.3  140.86  4979.3  137.97  5001.2  129.92
  5037.9  129.92  5038.9  130.42  5039.8  138.64  5089.2  136.93  5104.7  136.97
  5110.5  140.02  5120.6  141.32  5140.8  140.21  5201.4   144.2  5302.4   153.2
  5383.1  158.01  5388.2  155.48  5403.4  158.85  5421.3  159.84  5423.6  159.84
#Mann= 6 ,-1 , 0
  3776.1     .17       0  4843.5     .15       0  4979.3     .09       0
  5039.8     .15       0  5089.2     .17       0  5421.3     .11       0
Bank Sta=4979.3,5039.8
XS Rating Curve= 0 ,0
Exp/Cntr=0.3,0.1

Type RM Length L Ch R = 1 ,37000   ,500,500,500
BEGIN DESCRIPTION:
CRYSTAL CREEK 74.0
END DESCRIPTION:
XS GIS Cut Line= 3
      3868244.72     10100576.43      3867108.51      10100156.3
      3866687.55     10100189.93
#Sta/Elev= 30
  3788.6  155.96  3906.4  156.63  3974.6  154.19  4041.1  152.87  4158.4  147.18
  4211.7   148.6  4341.2  145.54  4488.9  147.15  4654.4  141.06  4734.2  141.21
  4819.5  145.32  4873.7  144.73  4917.4  144.12  4936.7  141.47  4942.5  138.76
  4958.1  136.51    4960  131.07    4961  130.57  4997.8  130.57    5000  133.37
  5040.8  138.68  5080.9  138.72  5131.1  143.19  5161.2  141.42  5181.2  144.07
  5209.5  139.73  5241.4  138.03  5374.8  149.15  5401.9     153  5422.3  153.41
#Mann= 7 ,-1 , 0
  3788.6     .11       0  3974.6     .17       0  4873.7     .15       0
  4942.5     .09       0  5040.8     .15       0  5209.5     .17       0
  5374.8     .11       0
Bank Sta=4942.5,5040.8
XS Rating Curve= 0 ,0
Exp/Cntr=0.3,0.1

Type RM Length L Ch R = 1 ,36500   ,512,512,512
BEGIN DESCRIPTION:
CRYSTAL CREEK 73.0
END DESCRIPTION:
XS GIS Cut Line= 3
      3868234.28     10099997.67      3867031.94     10099744.54
      3866677.01     10099942.08
#Sta/Elev= 30
  3771.3  154.89  3793.1  154.02  3931.2  149.38  3986.7  150.03  4136.7  147.21
  4258.2   144.1  4319.5  146.57  4463.5  145.68  4646.5  144.46  4741.2  147.19
  4769.1  149.28  4851.5  144.89  4871.3  139.51  4881.5  135.25    4902  133.42
    4946  133.99  4973.5  137.65  4983.7   136.6  4988.4  129.05  5025.2  129.05
  5038.8  135.51  5060.5   139.4  5066.2  137.48  5073.3  140.16  5109.7  138.83
    5178  140.95  5234.3  142.67  5266.3  147.86  5327.7  149.75  5406.2  152.96
#Mann= 10 ,-1 , 0
  3771.3     .11       0  3793.1     .17       0  3986.7     .11       0
  4136.7     .17       0  4463.5     .11       0  4741.2     .17       0
  4871.3     .09       0  5073.3     .15       0    5178     .17       0
  5327.7     .11       0
Bank Sta=4871.3,5073.3
XS Rating Curve= 0 ,0
Exp/Cntr=0.3,0.1

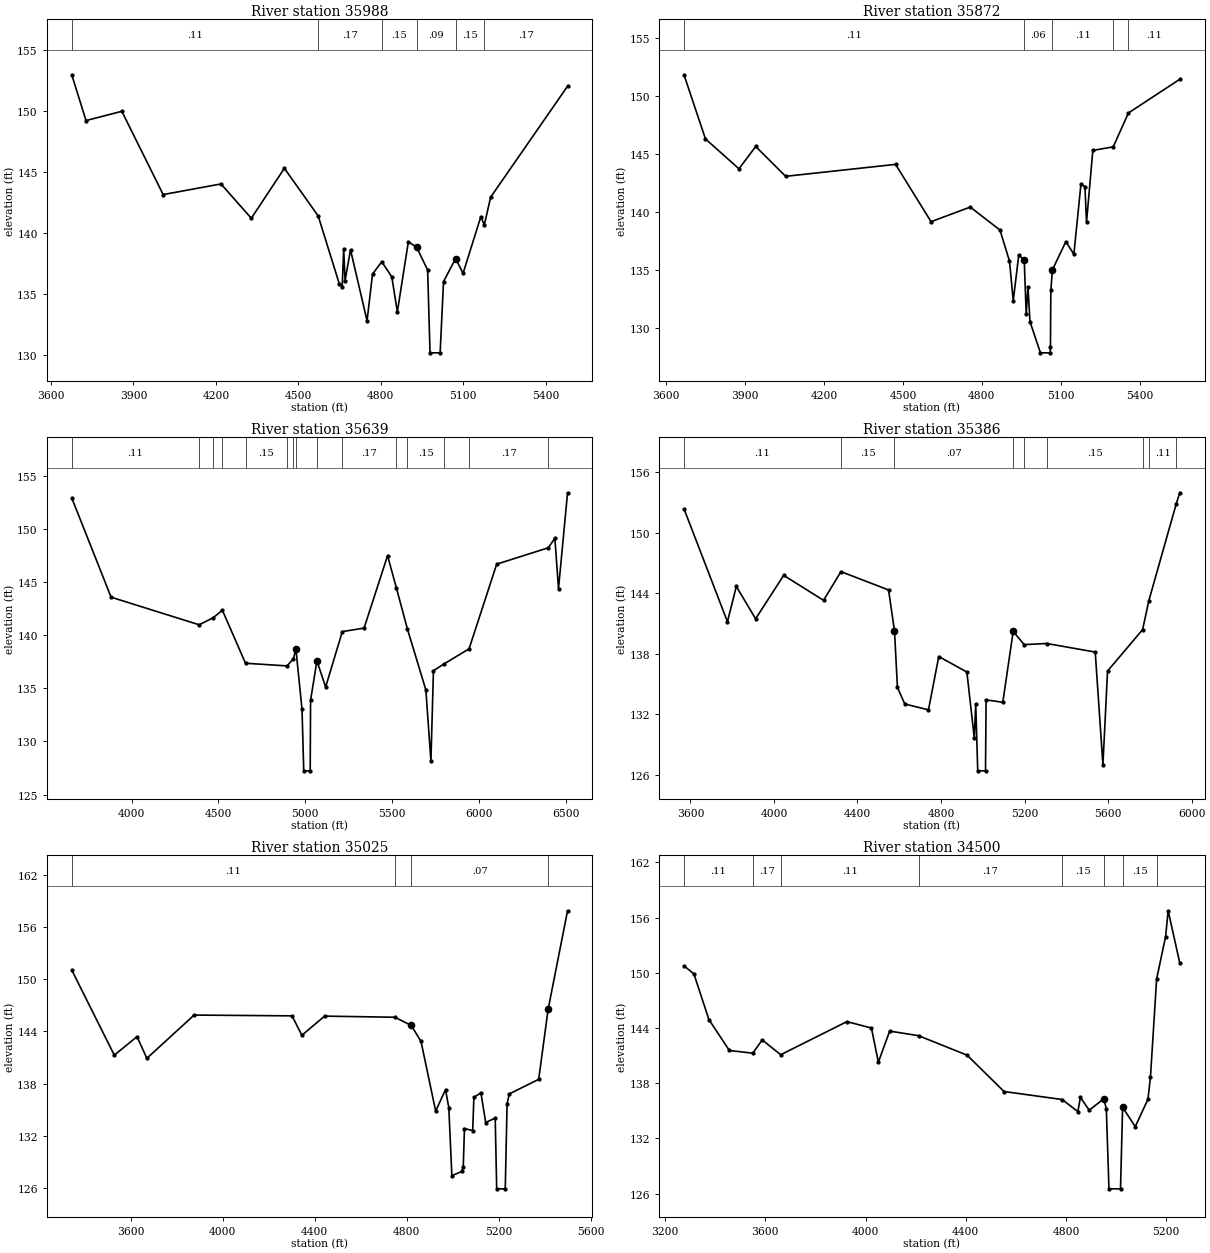
Type RM Length L Ch R = 1 ,35988   ,116,116,116
BEGIN DESCRIPTION:
CRYSTAL CREEK 72.0
END DESCRIPTION:
XS GIS Cut Line= 3
      3868289.56     10099180.03      3866968.87     10099281.75
      3866686.86     10099670.42
#Sta/Elev= 30
  3675.4  152.98  3727.3  149.23  3857.6  149.99  4008.1  143.17  4218.7  144.04
    4329  141.23  4449.4  145.32  4572.5  141.42    4650  135.81    4660  135.62
  4665.3  138.74  4670.3  136.12  4690.1  138.65  4750.3  132.83  4770.3  136.66
  4803.9  137.67  4840.5  136.43  4860.6  133.56  4900.7  139.31  4930.9  138.85
  4970.9  136.99  4979.6  130.21  5016.4  130.21  5028.7  136.04  5072.7  137.93
  5099.8  136.72  5164.7  141.37  5177.1  140.68  5200.3  142.96  5480.2  152.04
#Mann= 6 ,-1 , 0
  3675.4     .11       0  4572.5     .17       0  4803.9     .15       0
  4930.9     .09       0  5072.7     .15       0  5177.1     .17       0
Bank Sta=4930.9,5072.7
XS Rating Curve= 0 ,0
Exp/Cntr=0.3,0.1

Type RM Length L Ch R = 1 ,35872   ,233,233,233
BEGIN DESCRIPTION:
Mapping XS 6da51c09
END DESCRIPTION:
XS GIS Cut Line= 3
      3867973.38     10098291.43      3866968.01     10099165.64
      3866665.13     10099627.48
#Sta/Elev= 30
  3667.7  151.83  3749.4   146.3  3876.7  143.73  3940.3  145.65  4054.2  143.08
    4472  144.11  4606.9  139.17  4755.9  140.43  4868.9  138.45    4905  135.78
  4919.3  132.36  4940.1  136.27    4961   135.9  4968.6   131.2  4975.3  133.57
  4982.9  130.56  5022.6  127.87  5059.7  127.87  5060.7  128.37  5062.2  133.27
  5068.2  135.03  5119.5  137.46  5149.7  136.36  5176.7  142.42  5191.8   142.2
  5197.8  139.11  5221.8  145.31  5299.3  145.62  5357.2  148.54  5552.3  151.44
#Mann= 5 ,-1 , 0
  3667.7     .11       0    4961     .06       0  5068.2     .11       0
  5299.3     .17       0  5357.2     .11       0
Bank Sta=4961,5068.2
XS Rating Curve= 0 ,0
Exp/Cntr=0.3,0.1

Type RM Length L Ch R = 1 ,35639   ,253,253,253
BEGIN DESCRIPTION:
CRYSTAL CREEK 71.0
END DESCRIPTION:
XS GIS Cut Line= 3
      3867949.08     10098092.64       3866921.6     10098960.73
      3865714.81     10099870.17
#Sta/Elev= 30
  3654.9  152.92  3881.4  143.58  4389.1  140.98  4471.1  141.66  4522.5  142.35
  4655.9  137.36  4894.8  137.11  4932.1  137.79  4946.1  138.72  4981.3  133.03
  4991.4  127.23  5028.5  127.23  5030.7  133.88  5067.3  137.58  5117.4  135.12
  5213.5  140.34  5338.9  140.67  5474.2  147.49  5524.6  144.48  5588.8  140.57
  5694.9  134.85    5724  128.15  5738.6  136.66  5800.2   137.3  5943.8  138.72
  6102.9  146.69  6400.1  148.23  6438.1  149.13    6459  144.39  6511.1  153.41
#Mann= 15 ,-1 , 0
  3654.9     .11       0  4389.1     .17       0  4471.1     .11       0
  4522.5     .17       0  4655.9     .15       0  4894.8     .11       0
  4932.1     .15       0  4946.1     .09       0  5067.3     .15       0
  5213.5     .17       0  5524.6     .11       0  5588.8     .15       0
  5800.2     .11       0  5943.8     .17       0  6400.1     .11       0
Bank Sta=4946.1,5067.3
XS Rating Curve= 0 ,0
Exp/Cntr=0.3,0.1

Type RM Length L Ch R = 1 ,35386   ,361,361,361
BEGIN DESCRIPTION:
Mapping XS 0432b14f
END DESCRIPTION:
XS GIS Cut Line= 3
      3867700.05     10097768.82      3866723.74     10098819.29
      3865958.09     10099364.42
#Sta/Elev= 30
  3569.2  152.36  3777.3  141.16  3819.8  144.66  3912.2  141.45  4046.5  145.76
  4237.6  143.28  4320.6  146.13  4548.8  144.31  4577.2  140.25  4591.3  134.64
  4626.5     133  4739.9  132.42  4789.2  137.71  4923.8  136.17  4959.3  129.62
  4966.1  133.03  4975.8  126.37    5013  126.37  5015.8  133.41  5095.8  133.17
  5145.6   140.2  5198.2  138.89  5306.4     139  5538.4  138.15  5575.2  126.96
  5597.4  136.27  5765.3  140.38  5795.1  143.25  5926.3  152.85  5943.2  153.95
#Mann= 9 ,-1 , 0
  3569.2     .11       0  4320.6     .15       0  4577.2     .07       0
  5145.6     .15       0  5198.2     .17       0  5306.4     .15       0
  5765.3     .17       0  5795.1     .11       0  5926.3     .17       0
Bank Sta=4577.2,5145.6
XS Rating Curve= 0 ,0
Exp/Cntr=0.3,0.1

Type RM Length L Ch R = 1 ,35025   ,525,525,525
BEGIN DESCRIPTION:
CRYSTAL CREEK 70.0
END DESCRIPTION:
XS GIS Cut Line= 3
      3867659.47     10097692.45      3866406.18     10098774.86
      3865923.17     10098897.35
#Sta/Elev= 30
    3344  151.03  3528.8  141.26  3627.6  143.38  3670.3  140.89  3875.5  145.86
  4301.1  145.77  4343.9  143.54  4442.8  145.74  4747.3  145.61  4818.8  144.68
  4861.6  142.83  4925.2  134.83    4968  137.29  4982.3  135.24  4995.6  127.42
  5039.5   127.9  5045.2  128.44  5050.3  132.83  5086.1  132.59  5091.3   136.4
  5121.9  136.93  5142.7  133.52    5184  134.03  5190.4   125.9  5227.6   125.9
  5235.6  135.65  5244.9   136.8  5372.9  138.48  5413.9  146.52  5498.3  157.84
#Mann= 4 ,-1 , 0
    3344     .11       0  4747.3     .17       0  4818.8     .07       0
  5413.9     .11       0
Bank Sta=4818.8,5413.9
XS Rating Curve= 0 ,0
Exp/Cntr=0.3,0.1

Type RM Length L Ch R = 1 ,34500   ,500,500,500
BEGIN DESCRIPTION:
CRYSTAL CREEK 69.0
END DESCRIPTION:
XS GIS Cut Line= 3
      3867659.46     10097648.19      3866143.84      10098471.7
      3865891.92     10098435.57
#Sta/Elev= 30
  3275.1  150.76  3314.7  149.89  3374.5  144.93  3456.3  141.56  3549.7  141.27
  3587.4  142.71  3661.3   141.1  3925.7   144.7  4023.5     144  4051.1  140.29
  4096.3  143.67  4211.4  143.17  4405.5  141.05  4552.8   137.1    4785  136.23
  4847.5  134.92  4857.9  136.46    4893  135.07    4951   136.3  4961.3  135.24
  4971.8  126.52  5017.9  126.52  5026.3  135.39  5076.8  133.28  5127.3  136.25
  5137.4  138.63  5162.1  149.33    5198  153.95  5208.1  156.75  5254.5  151.09
#Mann= 8 ,-1 , 0
  3275.1     .11       0  3549.7     .17       0  3661.3     .11       0
  4211.4     .17       0    4785     .15       0    4951     .07       0
  5026.3     .15       0  5162.1     .11       0
Bank Sta=4951,5026.3
XS Rating Curve= 0 ,0
Exp/Cntr=0.3,0.1

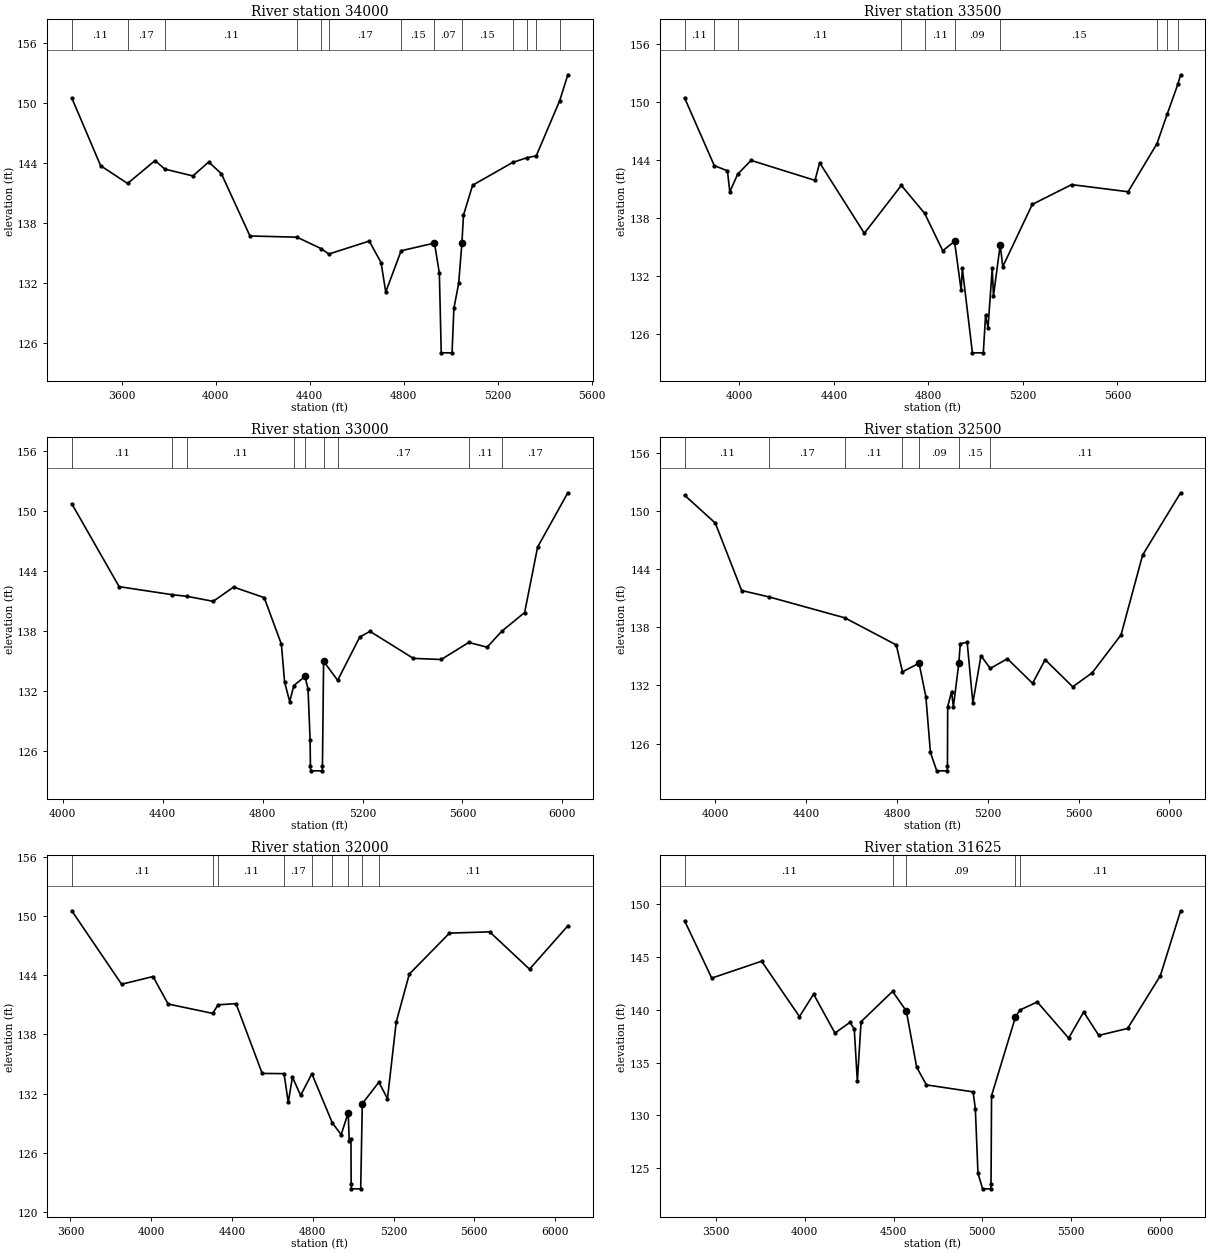
Type RM Length L Ch R = 1 ,34000   ,500,500,500
BEGIN DESCRIPTION:
CRYSTAL CREEK 68.0
END DESCRIPTION:
XS GIS Cut Line= 3
      3867651.64     10097624.75      3866091.44     10098035.28
      3865602.28     10097936.17
#Sta/Elev= 30
  3386.7  150.51  3509.7  143.72  3624.4  141.95  3741.3  144.24  3782.6  143.39
  3902.6   142.7  3969.7   144.1  4023.6  142.93  4145.5  136.69  4345.7  136.57
  4448.8  135.42  4481.2  134.88  4653.4  136.18  4703.8  134.03  4723.7  131.08
  4789.2  135.21  4931.3  135.98    4952  132.96    4960  124.99  5006.1  124.99
  5013.9  129.45  5034.3  131.95    5048  135.96  5054.7  138.77  5093.6  141.77
  5264.7  144.06  5327.1  144.54  5364.6  144.71  5464.5  150.24  5499.1  152.83
#Mann= 13 ,-1 , 0
  3386.7     .11       0  3624.4     .17       0  3782.6     .11       0
  4345.7     .17       0  4448.8     .11       0  4481.2     .17       0
  4789.2     .15       0  4931.3     .07       0    5048     .15       0
  5264.7     .17       0  5327.1     .11       0  5364.6     .17       0
  5464.5     .11       0
Bank Sta=4931.3,5048
XS Rating Curve= 0 ,0
Exp/Cntr=0.3,0.1

Type RM Length L Ch R = 1 ,33500   ,500,500,500
BEGIN DESCRIPTION:
CRYSTAL CREEK 67.0
END DESCRIPTION:
XS GIS Cut Line= 3
      3867649.01     10097598.71      3866405.88     10097659.56
      3865584.75     10097896.32
#Sta/Elev= 30
  3768.2  150.46  3893.9  143.44  3949.6   142.9  3959.6  140.72  3992.9  142.55
  4049.7  143.98    4320  141.91    4340  143.73  4528.9  136.43  4685.6  141.39
  4784.5  138.48  4860.7  134.62  4910.7  135.59  4938.6  130.52  4943.7  132.78
  4986.3  124.04  5032.4  124.04    5042  127.92  5052.4  126.66  5070.2  132.79
  5075.4  129.94  5103.9  135.22  5114.8  132.97  5239.7  139.42  5406.2  141.47
  5645.2  140.73  5767.3  145.71  5811.4  148.83  5855.7  151.87  5867.4  152.85
#Mann= 10 ,-1 , 0
  3768.2     .11       0  3893.9     .17       0  3992.9     .11       0
  4685.6     .17       0  4784.5     .11       0  4910.7     .09       0
  5103.9     .15       0  5767.3     .17       0  5811.4     .11       0
  5855.7     .17       0
Bank Sta=4910.7,5103.9
XS Rating Curve= 0 ,0
Exp/Cntr=0.3,0.1

Type RM Length L Ch R = 1 ,33000   ,500,500,500
BEGIN DESCRIPTION:
CRYSTAL CREEK 66.0
END DESCRIPTION:
XS GIS Cut Line= 3
      3867302.65     10097049.35      3866358.15     10097240.29
      3865425.19     10097656.52
#Sta/Elev= 30
  4036.4  150.75  4225.9  142.44  4436.7  141.64  4497.7  141.47  4602.4  140.97
    4684   142.4  4806.5  141.34  4875.3  136.67  4888.1  132.88  4908.5  130.92
  4925.2  132.53  4969.7  133.44  4981.9  132.18  4990.1  127.12  4991.4  124.48
  4992.4  123.98  5038.6  123.98  5039.6  124.48  5044.2  134.96  5100.4  133.05
    5189   137.4  5229.9  137.96  5403.5  135.25    5515  135.14  5625.2  136.85
  5698.5  136.37  5756.7  137.96  5848.8  139.85  5900.7  146.41  6021.6  151.85
#Mann= 9 ,-1 , 0
  4036.4     .11       0  4436.7     .17       0  4497.7     .11       0
  4925.2     .15       0  4969.7     .09       0  5044.2     .15       0
  5100.4     .17       0  5625.2     .11       0  5756.7     .17       0
Bank Sta=4969.7,5044.2
XS Rating Curve= 0 ,0
Exp/Cntr=0.3,0.1

Type RM Length L Ch R = 1 ,32500   ,500,500,500
BEGIN DESCRIPTION:
CRYSTAL CREEK 65.0
END DESCRIPTION:
XS GIS Cut Line= 3
      3867288.76     10096924.35      3866164.91     10096855.04
      3865171.72     10097222.58
#Sta/Elev= 30
  3864.2   151.6  3999.6  148.73  4115.6  141.78  4238.1  141.11  4570.7  138.96
  4796.9  136.17  4823.9   133.4  4897.1  134.29  4927.1  130.83  4947.2  125.09
    4975   123.2  5021.2   123.2  5022.2   123.7  5023.2  129.82  5040.4  131.36
  5048.2  129.78  5072.4  134.31  5078.6   136.3    5109  136.45  5134.1   130.2
  5169.8  135.06  5210.9  133.75  5286.1  134.75  5397.1  132.22  5452.5  134.65
  5574.1  131.86    5660  133.31  5786.8  137.21  5881.9  145.44  6049.2  151.85
#Mann= 7 ,-1 , 0
  3864.2     .11       0  4238.1     .17       0  4570.7     .11       0
  4823.9     .15       0  4897.1     .09       0  5072.4     .15       0
  5210.9     .11       0
Bank Sta=4897.1,5072.4
XS Rating Curve= 0 ,0
Exp/Cntr=0.3,0.1

Type RM Length L Ch R = 1 ,32000   ,375,375,375
BEGIN DESCRIPTION:
CRYSTAL CREEK 64.0
END DESCRIPTION:
XS GIS Cut Line= 3
      3867333.83     10096788.92      3865987.19     10096430.21
        3865063.     10096955.62
#Sta/Elev= 30
  3606.4  150.56  3853.2   143.1  4008.5  143.88  4083.6  141.09    4304  140.14
  4331.2  141.01  4419.8  141.13  4549.5  134.04  4657.6  134.02  4678.5  131.11
  4699.2  133.67  4739.8  131.81  4795.4  134.01  4896.5  129.03  4940.4  127.82
  4975.3  130.04  4980.5  127.15    4989   127.4    4990  122.82    4991  122.32
  5037.3  122.32  5045.2  130.97  5127.3  133.15  5169.9  131.47  5213.1  139.25
    5278  144.13  5476.9  148.29  5675.9  148.42  5873.5  144.63  6063.1  149.03
#Mann= 9 ,-1 , 0
  3606.4     .11       0    4304     .17       0  4331.2     .11       0
  4657.6     .17       0  4795.4     .11       0  4896.5     .15       0
  4975.3     .09       0  5045.2     .15       0  5127.3     .11       0
Bank Sta=4975.3,5045.2
XS Rating Curve= 0 ,0
Exp/Cntr=0.3,0.1

Type RM Length L Ch R = 1 ,31625   ,136,136,136
BEGIN DESCRIPTION:
Mapping XS 75a4ff48
END DESCRIPTION:
XS GIS Cut Line= 4
      3867303.44     10096730.55      3865730.52     10096220.13
      3865435.38     10096126.38      3864827.76     10096692.34
#Sta/Elev= 30
  3322.8  148.45  3475.9  143.01  3756.5  144.61    3970  139.36  4049.5  141.49
  4169.7   137.8  4253.8  138.81  4278.5  138.19  4295.9  133.22  4316.9  138.88
  4494.2  141.75  4571.5   139.9  4630.2  134.56  4684.9  132.89  4947.7  132.23
  4960.4  130.65  4975.2  124.51  5001.5  123.04  5047.8  123.04  5048.8  123.54
  5051.7  131.87    5186   139.3    5211  139.98  5309.1  140.75    5486  137.32
  5570.5   139.8  5655.5  137.58  5818.2  138.24  6002.4  143.24  6116.5  149.39
#Mann= 5 ,-1 , 0
  3322.8     .11       0  4494.2     .17       0  4571.5     .09       0
    5186     .15       0    5211     .11       0
Bank Sta=4571.5,5186
XS Rating Curve= 0 ,0
Exp/Cntr=0.3,0.1

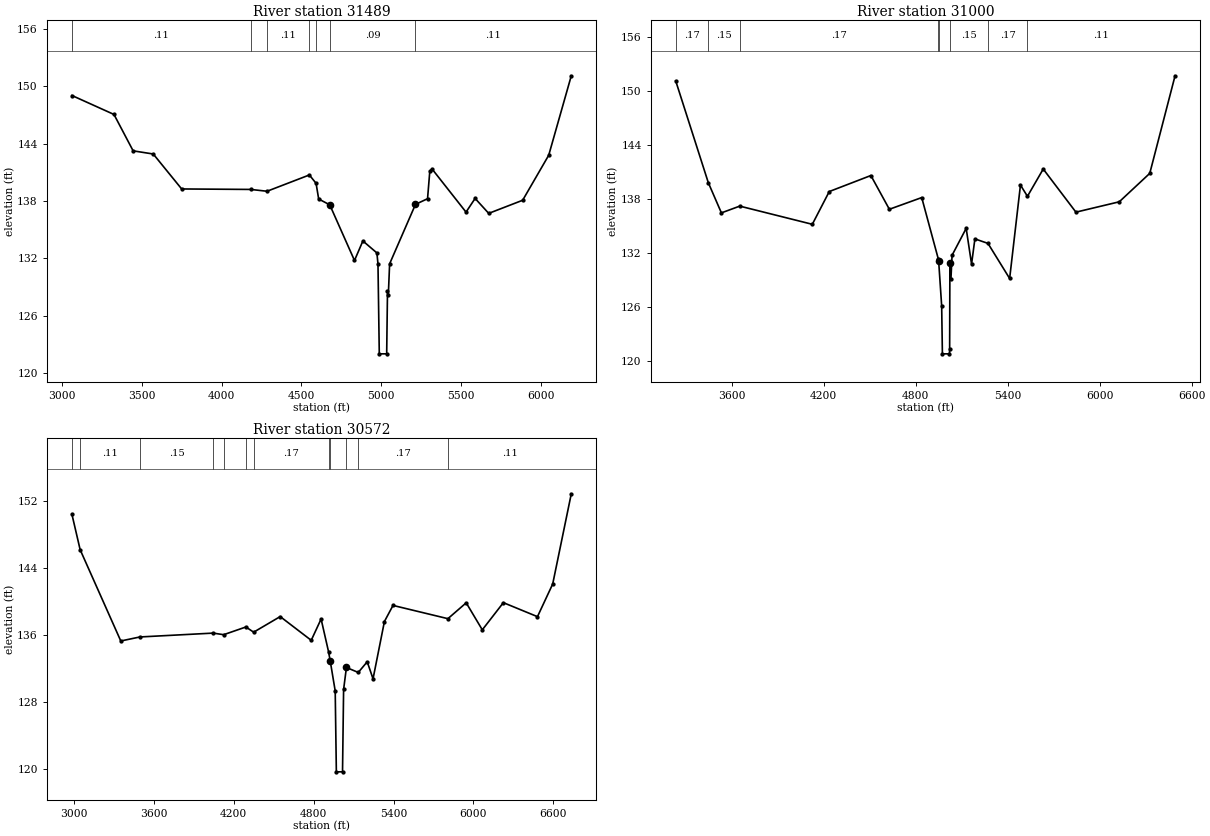
Type RM Length L Ch R = 1 ,31489   ,489,489,489
BEGIN DESCRIPTION:
CRYSTAL CREEK 63.0
END DESCRIPTION:
XS GIS Cut Line= 4
       3867552.7     10096666.42      3865709.69     10096077.77
      3865501.36     10096018.74      3864772.88     10096666.07
#Sta/Elev= 30
  3063.8  149.02    3327  147.04  3446.8  143.24  3572.8  142.91  3750.6  139.26
    4183  139.21  4285.1  139.02  4549.9  140.72    4592  139.85  4608.3  138.21
  4677.7137.6023  4832.5  131.79    4885  133.83  4972.7  132.58  4979.5  131.44
  4987.7  122.04    5034  122.04  5039.1  128.59  5044.3  128.18  5052.4  131.44
  5214.3  137.65  5289.8  138.24    5304  141.13  5318.3  141.34  5530.7  136.84
  5587.5  138.27  5672.8  136.71  5885.2  138.08  6048.3  142.78  6189.6  151.08
#Mann= 7 ,-1 , 0
  3063.8     .11       0    4183     .17       0  4285.1     .11       0
  4549.9     .17       0    4592     .11       0  4677.7     .09       0
  5214.3     .11       0
Bank Sta=4677.7,5214.3
XS Rating Curve= 0 ,0
Exp/Cntr=0.3,0.1

Type RM Length L Ch R = 1 ,31000   ,428,428,428
BEGIN DESCRIPTION:
CRYSTAL CREEK 62.0
END DESCRIPTION:
XS GIS Cut Line= 3
      3867594.24     10095466.02       3865838.5     10095638.57
      3864726.22      10096632.7
#Sta/Elev= 30
  3235.8  151.16  3448.4  139.85  3533.6   136.5  3653.4  137.25  4126.5  135.23
    4237  138.87  4508.3  140.65  4628.9   136.9  4839.9   138.2  4948.5  131.35
  4950.4  131.13    4970  126.15  4974.7  120.84    5021  120.84    5022  121.34
  5023.6  130.96  5030.3  129.11  5037.8  131.79  5129.8  134.78  5164.9  130.81
  5186.6  133.61  5271.9  133.11  5413.2  129.21  5483.7  139.59  5529.3  138.34
  5632.2  141.37  5845.4  136.58    6128  137.73  6326.9  140.89  6491.8  151.73
#Mann= 8 ,-1 , 0
  3235.8     .17       0  3448.4     .15       0  3653.4     .17       0
  4948.5     .15       0  4950.4     .09       0  5023.6     .15       0
  5271.9     .17       0  5529.3     .11       0
Bank Sta=4950.4,5023.6
XS Rating Curve= 0 ,0
Exp/Cntr=0.3,0.1

Type RM Length L Ch R = 1 ,30572   ,72,72,72
BEGIN DESCRIPTION:
Mapping XS d79a1941
END DESCRIPTION:
XS GIS Cut Line= 4
      3867654.09     10094577.79      3865752.27     10095240.88
      3864810.38     10096489.23      3864694.05     10096614.25
#Sta/Elev= 30
  2985.9   150.4  3047.5  146.19  3352.6  135.31  3496.2  135.79  4046.2  136.25
  4124.8  136.06  4291.8  136.98  4350.1  136.36  4549.3  138.22  4782.3  135.39
  4856.4  137.93    4912  134.05    4925  132.92  4962.3  129.35  4970.9  119.71
  5017.2  119.71  5025.3  129.53  5046.5  132.15  5135.4  131.56  5202.6  132.83
  5246.3   130.8  5331.7  137.63  5396.2  139.55  5808.3  137.97  5945.7  139.86
  6066.5  136.64  6224.7  139.88  6480.7  138.21    6595   142.1  6734.6  152.86
#Mann= 12 ,-1 , 0
  2985.9     .17       0  3047.5     .11       0  3496.2     .15       0
  4046.2     .11       0  4124.8     .17       0  4291.8     .11       0
  4350.1     .17       0    4912     .15       0    4925     .09       0
  5046.5     .15       0  5135.4     .17       0  5808.3     .11       0
Bank Sta=4925,5046.5
XS Rating Curve= 0 ,0
Exp/Cntr=0.3,0.1