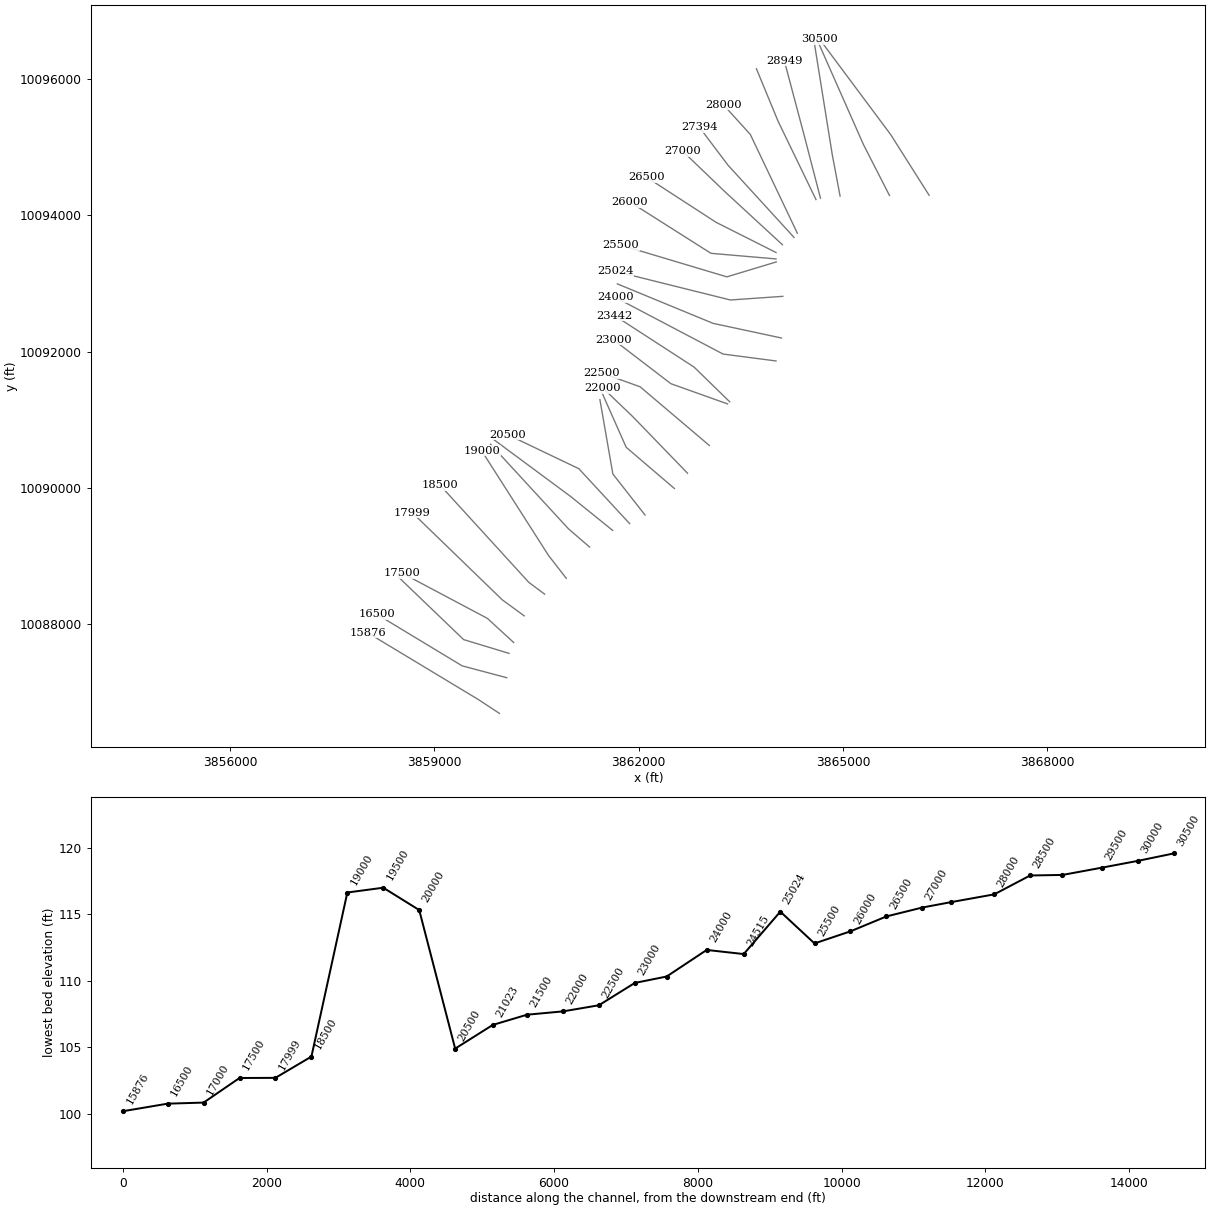
HEC-RAS study CRYSTAL CREEK.prj: CRYSTAL CREEK Base Level Engineering

--- CRYSTAL CREEK.g01 (geometry) --- (continued)

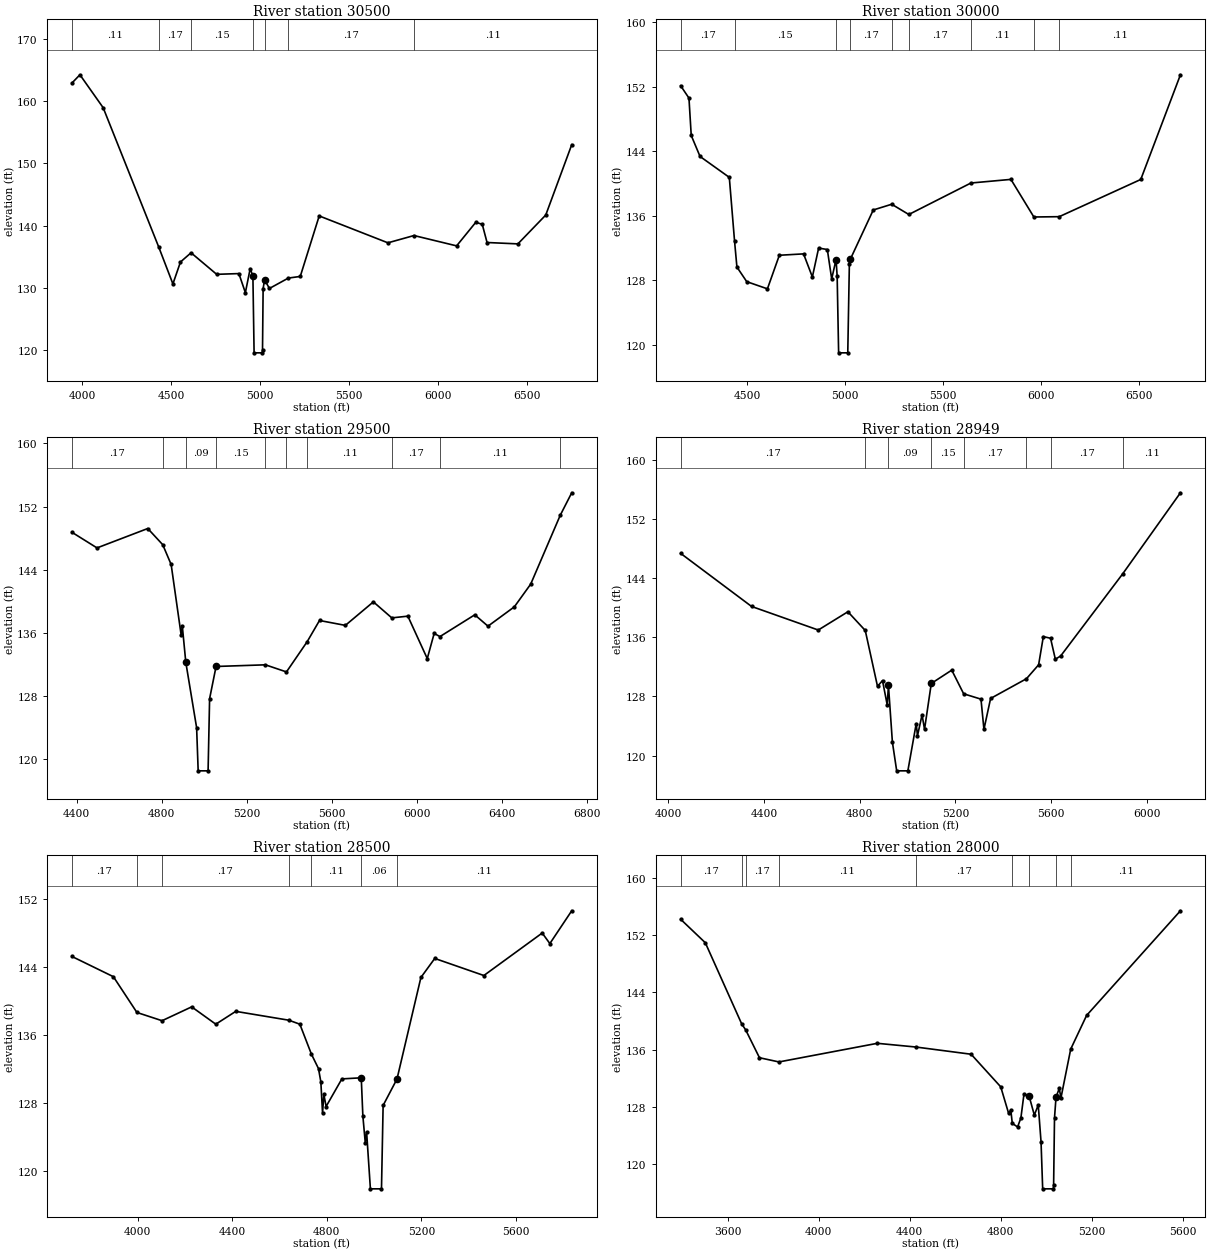
Type RM Length L Ch R = 1 ,30500   ,500,500,500
BEGIN DESCRIPTION:
CRYSTAL CREEK 61.0
END DESCRIPTION:
XS GIS Cut Line= 3
      3866266.14     10094297.35      3865701.28      10095189.7
      3864655.88     10096593.39
#Sta/Elev= 30
  3943.9  162.91  3988.6  164.23  4119.1  158.94  4431.3  136.55  4510.7  130.64
  4553.1  134.16  4612.6  135.64  4756.5  132.18  4881.1   132.3  4917.6  129.24
  4944.7   133.1  4959.9  131.89  4966.6  119.57  5012.9  119.57  5013.9  120.07
  5017.3   129.9  5025.6  131.29  5052.7  129.91  5159.1  131.58  5225.8  131.84
  5332.2  141.56    5718  137.24  5864.5  138.41  6103.8  136.75  6211.2  140.53
  6247.7  140.22  6274.7  137.29  6447.9  137.07  6604.3   141.7  6750.2     153
#Mann= 7 ,-1 , 0
  3943.9     .11       0  4431.3     .17       0  4612.6     .15       0
  4959.9     .09       0  5025.6     .15       0  5159.1     .17       0
  5864.5     .11       0
Bank Sta=4959.9,5025.6
XS Rating Curve= 0 ,0
Exp/Cntr=0.3,0.1

Type RM Length L Ch R = 1 ,30000   ,500,500,500
BEGIN DESCRIPTION:
CRYSTAL CREEK 60.0
END DESCRIPTION:
XS GIS Cut Line= 3
      3865684.51     10094293.06      3865302.71      10095040.6
      3864612.24     10096603.58
#Sta/Elev= 30
  4160.6   152.1  4202.9  150.57  4214.5  145.94  4259.4  143.34  4408.6  140.75
  4435.5  132.81  4447.4  129.64  4497.4  127.83  4602.9  126.94  4663.7   131.1
  4787.2  131.27  4832.1  128.41    4864  131.99  4908.4  131.81  4930.6  128.17
  4952.9  130.57  4958.5  128.49    4966  119.01  5012.6  119.01  5020.7  129.96
  5026.1  130.63  5142.6  136.71  5236.7  137.42  5323.9  136.15  5640.5  140.05
  5844.4   140.5  5961.4  135.84  6090.8  135.88  6506.5  140.49  6708.7  153.46
#Mann= 9 ,-1 , 0
  4160.6     .17       0  4435.5     .15       0  4952.9     .09       0
  5026.1     .17       0  5236.7     .11       0  5323.9     .17       0
  5640.5     .11       0  5961.4     .17       0  6090.8     .11       0
Bank Sta=4952.9,5026.1
XS Rating Curve= 0 ,0
Exp/Cntr=0.3,0.1

Type RM Length L Ch R = 1 ,29500   ,551,551,551
BEGIN DESCRIPTION:
CRYSTAL CREEK 59.0
END DESCRIPTION:
XS GIS Cut Line= 3
      3864958.88     10094285.43      3864843.35     10094896.91
      3864569.99     10096601.43
#Sta/Elev= 30
  4377.7  148.74  4495.4  146.76  4733.9  149.22  4804.2  147.17  4843.8  144.66
  4891.1  135.67  4896.2  136.87  4912.6  132.27  4963.5  123.97  4970.8   118.5
  5017.4   118.5  5024.5  127.65  5054.9  131.73  5286.7  131.94  5385.7  131.04
  5483.2  134.88    5541  137.56  5662.5  136.94  5794.2  139.92  5880.7  137.89
  5956.2  138.11  6047.4  132.73  6079.8  135.92    6107  135.52  6270.7  138.28
  6332.7  136.84  6456.6  139.29  6533.5  142.17  6672.5  150.91  6726.3  153.75
#Mann= 10 ,-1 , 0
  4377.7     .17       0  4804.2     .15       0  4912.6     .09       0
  5054.9     .15       0  5286.7     .11       0  5385.7     .17       0
  5483.2     .11       0  5880.7     .17       0    6107     .11       0
  6672.5     .17       0
Bank Sta=4912.6,5054.9
XS Rating Curve= 0 ,0
Exp/Cntr=0.3,0.1

Type RM Length L Ch R = 1 ,28949   ,449,449,449
BEGIN DESCRIPTION:
CRYSTAL CREEK 58.0
END DESCRIPTION:
XS GIS Cut Line= 3
      3864670.68     10094254.21      3864432.46     10095172.83
      3864139.43     10096275.04
#Sta/Elev= 30
    4051  147.34  4347.3  140.17  4626.3  136.98  4750.2  139.45  4822.8  136.92
    4874  129.37  4894.9  130.15  4914.6  126.86  4919.7   129.5  4936.2  121.84
  4954.2  117.95  5000.9  117.95  5035.9  124.34  5041.1  122.69  5060.3  125.52
  5070.6  123.56 5098.87129.7624  5184.4  131.56  5234.2  128.36  5306.6  127.64
    5319  123.56  5346.8  127.73  5496.8   130.4  5547.6  132.28  5567.3  136.09
  5597.5  135.87  5617.5  133.04  5639.7  133.47  5899.7   144.6  6140.5  155.53
#Mann= 8 ,-1 , 0
    4051     .17       0  4822.8     .15       0  4919.7     .09       0
 5098.87     .15       0  5234.2     .17       0  5496.8     .11       0
  5597.5     .17       0  5899.7     .11       0
Bank Sta=4919.7,5098.87
XS Rating Curve= 0 ,0
Exp/Cntr=0.3,0.1

Type RM Length L Ch R = 1 ,28500   ,500,500,500
BEGIN DESCRIPTION:
CRYSTAL CREEK 57.0
END DESCRIPTION:
XS GIS Cut Line= 3
      3864604.72     10094233.35      3864048.67     10095383.82
      3863729.89     10096156.55
#Sta/Elev= 30
  3722.2  145.26  3897.4  142.88  3996.9  138.67  4103.2   137.7  4228.5  139.33
  4330.5  137.29  4414.9   138.8  4639.4  137.76    4686  137.29    4735  133.76
  4764.9  132.06  4774.8   130.5    4782  126.83  4787.5  129.03    4797   127.6
  4863.7  130.85  4945.7  130.98  4952.5   126.5  4962.7  123.33  4968.3  124.63
  4984.4  117.91  5031.3  117.91  5038.2  127.73  5096.9  130.84    5198  142.79
  5256.6  145.03  5464.3  143.02    5711  148.02  5743.4  146.78  5835.9  150.64
#Mann= 7 ,-1 , 0
  3722.2     .17       0  3996.9     .15       0  4103.2     .17       0
  4639.4     .15       0    4735     .11       0  4945.7     .06       0
  5096.9     .11       0
Bank Sta=4945.7,5096.9
XS Rating Curve= 0 ,0
Exp/Cntr=0.3,0.1

Type RM Length L Ch R = 1 ,28000   ,606,606,606
BEGIN DESCRIPTION:
CRYSTAL CREEK 56.0
END DESCRIPTION:
XS GIS Cut Line= 3
      3864330.42     10093740.29      3863639.84     10095191.23
      3863243.61     10095629.19
#Sta/Elev= 30
  3393.1  154.26  3501.5  150.97  3661.4   139.6    3679  138.76  3739.6  134.86
  3825.3  134.27  4257.8  136.88  4427.4  136.36  4670.2  135.35  4800.5  130.78
  4834.7  127.11  4844.8  127.52  4851.3  125.66  4874.6  125.16  4889.1  126.42
  4902.8   129.8  4925.5  129.46  4948.2  126.82  4965.4  128.24  4977.7  123.08
  4984.9  116.49    5032  116.49    5033  116.99  5036.9  126.41  5043.6  129.34
  5057.8  130.55  5065.3  129.24  5108.2  136.07  5178.1  140.79  5590.6  155.45
#Mann= 9 ,-1 , 0
  3393.1     .17       0  3661.4     .15       0    3679     .17       0
  3825.3     .11       0  4427.4     .17       0  4851.3     .15       0
  4925.5     .09       0  5043.6     .15       0  5108.2     .11       0
Bank Sta=4925.5,5043.6
XS Rating Curve= 0 ,0
Exp/Cntr=0.3,0.1

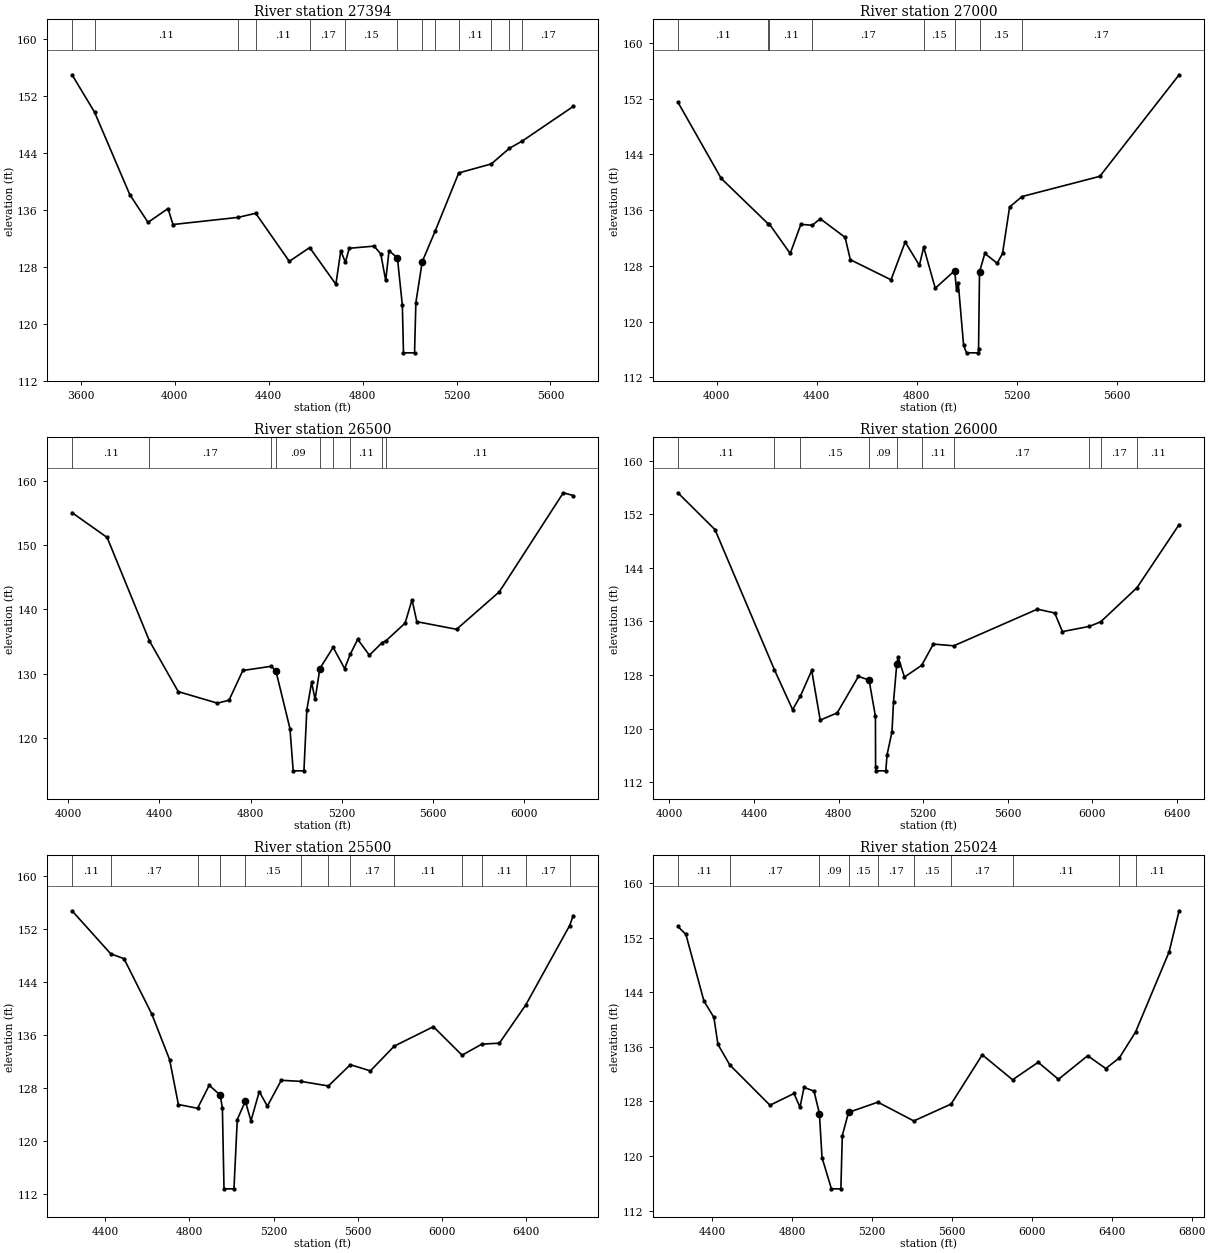
Type RM Length L Ch R = 1 ,27394   ,394,394,394
BEGIN DESCRIPTION:
CRYSTAL CREEK 55.0
END DESCRIPTION:
XS GIS Cut Line= 3
      3864281.77     10093677.84      3863312.53      10094739.3
      3862892.93     10095295.84
#Sta/Elev= 30
  3562.6  154.99  3658.6  149.73  3808.5  138.14  3886.2  134.24  3971.3  136.19
  3992.3  133.94  4269.2  134.94  4344.7  135.52  4487.8  128.76  4574.5   130.7
  4686.1  125.54  4707.1  130.25  4726.7  128.62  4742.9   130.6  4848.9   130.9
  4877.3   129.8  4898.3  126.08  4912.5  130.26  4948.2  129.24  4969.2  122.56
    4974   115.9  5021.1   115.9  5026.8  122.97  5053.9  128.72  5108.7     133
  5209.3  141.19  5348.1  142.46  5425.3  144.66  5480.1  145.68    5697  150.54
#Mann= 13 ,-1 , 0
  3562.6     .17       0  3658.6     .11       0  4269.2     .17       0
  4344.7     .11       0  4574.5     .17       0  4726.7     .15       0
  4948.2     .09       0  5053.9     .15       0  5108.7     .17       0
  5209.3     .11       0  5348.1     .17       0  5425.3     .11       0
  5480.1     .17       0
Bank Sta=4948.2,5053.9
XS Rating Curve= 0 ,0
Exp/Cntr=0.3,0.1

Type RM Length L Ch R = 1 ,27000   ,500,500,500
BEGIN DESCRIPTION:
CRYSTAL CREEK 54.0
END DESCRIPTION:
XS GIS Cut Line= 3
      3864111.64     10093570.19      3863262.98     10094353.05
      3862649.83     10094941.73
#Sta/Elev= 30
  3845.4  151.51  4018.5  140.56  4207.3     134  4210.8  134.01  4294.6  129.77
  4337.2  133.96  4382.7  133.82  4414.8  134.76  4514.1  132.09  4535.1  128.88
  4697.8  125.99  4754.5  131.42  4811.2  128.07  4828.5  130.67  4874.7  124.78
  4952.6  127.31  4959.8  124.49  4966.6  125.55  4988.1  116.57  4999.8   115.5
  5046.9   115.5  5047.9     116  5051.7  127.11    5073  129.78  5122.4  128.36
  5143.8  129.78  5172.1  136.45  5221.7  137.95  5532.8  140.85    5850  155.44
#Mann= 8 ,-1 , 0
  3845.4     .11       0  4207.3     .17       0  4210.8     .11       0
  4382.7     .17       0  4828.5     .15       0  4952.6     .09       0
  5051.7     .15       0  5221.7     .17       0
Bank Sta=4952.6,5051.7
XS Rating Curve= 0 ,0
Exp/Cntr=0.3,0.1

Type RM Length L Ch R = 1 ,26500   ,500,500,500
BEGIN DESCRIPTION:
CRYSTAL CREEK 53.0
END DESCRIPTION:
XS GIS Cut Line= 3
      3864017.93     10093455.59      3863138.99     10093898.21
      3862117.86     10094561.06
#Sta/Elev= 30
  4015.9  155.07  4169.9  151.21  4355.3  135.12  4482.3  127.18  4654.2  125.38
  4705.4  125.84  4766.1  130.47  4891.2  131.13  4911.8  130.33  4973.1   121.4
  4987.3  114.83  5034.4  114.83  5047.1  124.32  5068.2  128.64  5083.4  125.96
  5104.5  130.78  5162.7  134.08  5213.2  130.76  5237.8     133  5270.6  135.32
    5322  132.85  5377.4   134.8  5395.6  135.13  5478.9  137.85  5509.2   141.5
  5530.3  138.08  5704.8  136.89  5892.8  142.74  6173.6  158.17  6217.4  157.74
#Mann= 9 ,-1 , 0
  4015.9     .11       0  4355.3     .17       0  4891.2     .15       0
  4911.8     .09       0  5104.5     .15       0  5162.7     .17       0
  5237.8     .11       0  5377.4     .17       0  5395.6     .11       0
Bank Sta=4911.8,5104.5
XS Rating Curve= 0 ,0
Exp/Cntr=0.3,0.1

Type RM Length L Ch R = 1 ,26000   ,500,500,500
BEGIN DESCRIPTION:
CRYSTAL CREEK 52.0
END DESCRIPTION:
XS GIS Cut Line= 3
      3864017.84     10093361.07      3863062.37     10093443.31
      3861872.44     10094198.42
#Sta/Elev= 30
    4041  155.21  4216.3  149.71  4496.9  128.81    4583  122.84  4620.3   124.9
  4673.3  128.69  4713.5  121.28  4793.8  122.36  4894.1   127.8  4944.3  127.26
  4974.4  121.85  4975.2  114.21  4976.2  113.71  5023.4  113.71  5029.4  116.11
  5052.7  119.54  5059.9  124.04  5075.1  129.59  5081.1  130.68  5111.6  127.71
  5193.1  129.46    5248  132.63  5344.6  132.37  5739.6  137.84  5821.5  137.27
  5857.9  134.49  5985.4  135.27  6038.8  135.95  6210.4  141.05  6409.3  150.46
#Mann= 10 ,-1 , 0
    4041     .11       0  4496.9     .17       0  4620.3     .15       0
  4944.3     .09       0  5075.1     .15       0  5193.1     .11       0
  5344.6     .17       0  5985.4     .11       0  6038.8     .17       0
  6210.4     .11       0
Bank Sta=4944.3,5075.1
XS Rating Curve= 0 ,0
Exp/Cntr=0.3,0.1

Type RM Length L Ch R = 1 ,25500   ,476,476,476
BEGIN DESCRIPTION:
CRYSTAL CREEK 51.0
END DESCRIPTION:
XS GIS Cut Line= 3
      3864021.38     10093316.72      3863295.96     10093097.58
      3861741.49     10093562.83
#Sta/Elev= 30
  4242.2  154.78  4425.7  148.29  4488.9  147.55  4620.8   139.2  4705.5  132.31
  4747.3  125.53  4838.3  124.96  4893.6  128.43  4945.8  126.97  4956.2  124.99
  4963.9   112.8  5011.2   112.8  5026.9  123.26  5065.2  126.04    5092  123.07
  5131.4  127.48  5169.7  125.28  5235.9  129.19  5330.2  129.02  5459.6  128.33
  5563.8  131.54  5659.1  130.61  5772.1  134.34  5958.3  137.28  6094.4  132.98
  6188.7  134.65  6271.5  134.79  6397.1  140.57  6605.4  152.55  6622.6  154.06
#Mann= 13 ,-1 , 0
  4242.2     .11       0  4425.7     .17       0  4838.3     .15       0
  4945.8     .09       0  5065.2     .15       0  5330.2     .17       0
  5459.6     .11       0  5563.8     .17       0  5772.1     .11       0
  6094.4     .17       0  6188.7     .11       0  6397.1     .17       0
  6605.4     .11       0
Bank Sta=4945.8,5065.2
XS Rating Curve= 0 ,0
Exp/Cntr=0.3,0.1

Type RM Length L Ch R = 1 ,25024   ,509,509,509
BEGIN DESCRIPTION:
CRYSTAL CREEK 50.0
END DESCRIPTION:
XS GIS Cut Line= 3
      3864117.82     10092811.07      3863347.29     10092757.45
      3861661.53     10093177.51
#Sta/Elev= 30
  4227.6  153.63  4267.7  152.47  4357.9  142.72    4408   140.3  4428.1  136.36
  4487.3  133.35  4688.7  127.44    4809  129.16    4839  127.15  4859.1  130.05
  4909.2  129.51 4936.16126.2266  4949.3  119.77  4996.4  115.19  5043.7  115.19
  5050.9     123    5082  126.39  5228.9  127.89  5408.8  125.14  5595.5  127.61
  5751.7  134.83  5903.4  131.17  6031.7  133.73  6133.1  131.24  6279.5  134.69
  6370.1  132.82    6438  134.37  6519.3  138.17  6687.2   149.9  6737.3  155.93
#Mann= 10 ,-1 , 0
  4227.6     .11       0  4487.3     .17       0 4936.16     .09       0
    5082     .15       0  5228.9     .17       0  5408.8     .15       0
  5595.5     .17       0  5903.4     .11       0    6438     .17       0
  6519.3     .11       0
Bank Sta=4936.16,5082
XS Rating Curve= 0 ,0
Exp/Cntr=0.3,0.1

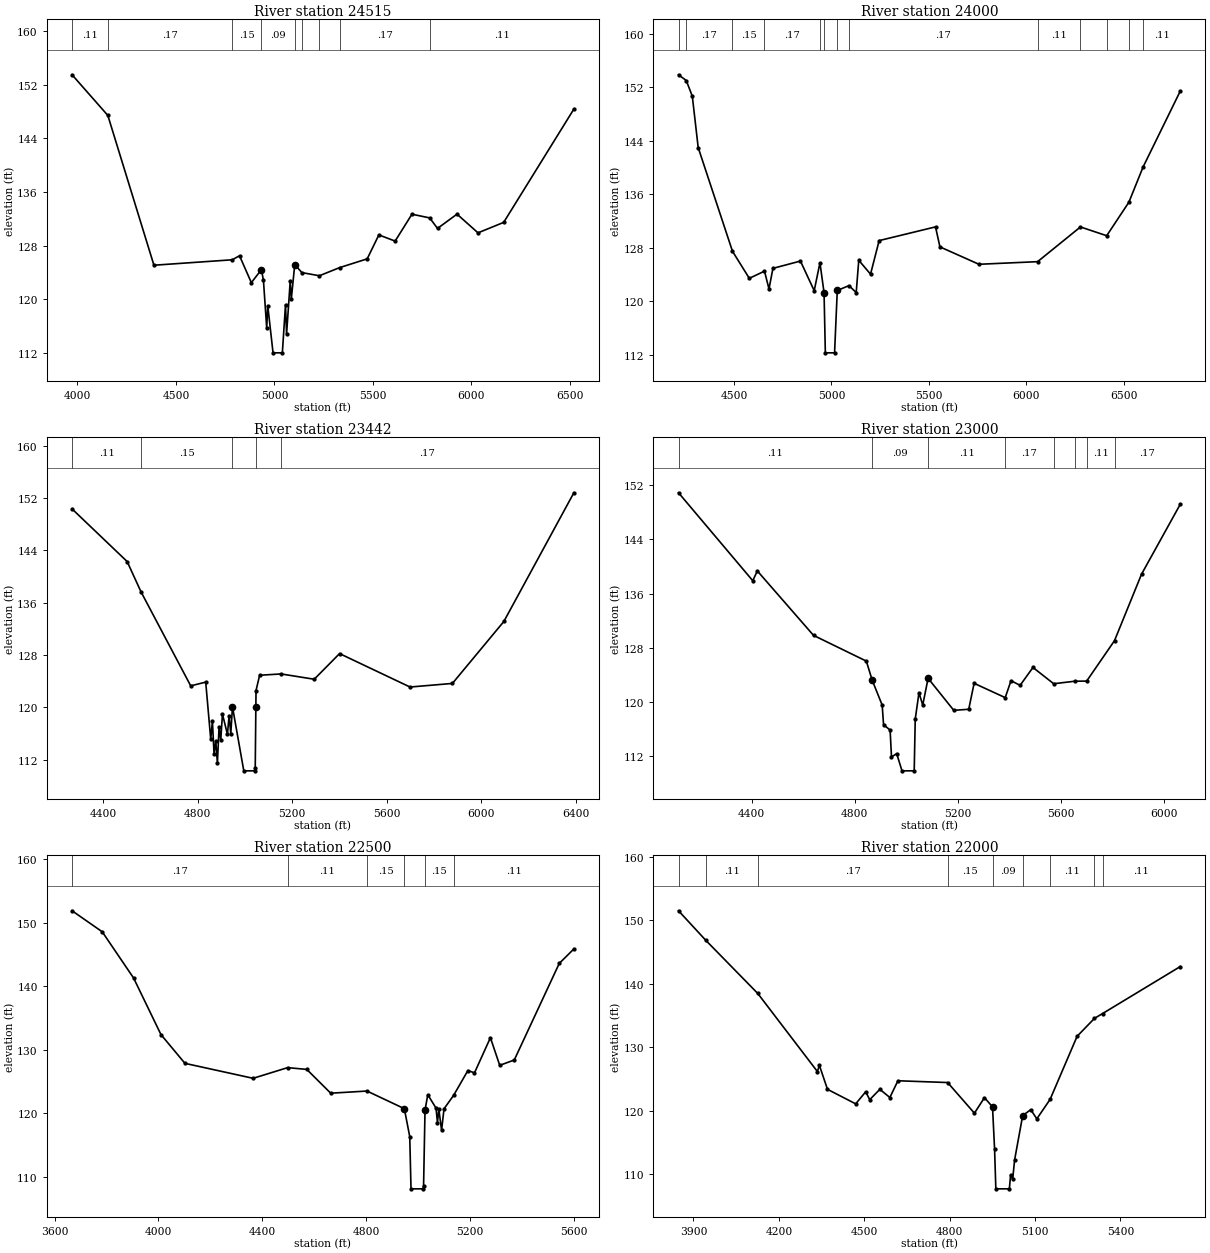
Type RM Length L Ch R = 1 ,24515   ,515,515,515
BEGIN DESCRIPTION:
CRYSTAL CREEK 49.0
END DESCRIPTION:
XS GIS Cut Line= 3
      3864097.76     10092198.66      3863093.08       10092414.
      3861688.01     10092993.81
#Sta/Elev= 30
  3972.5  153.48    4154  147.42  4388.1  125.07  4785.3  125.88  4822.7  126.48
  4882.6  122.47  4933.8  124.41    4944  122.83  4960.7   115.7  4965.9  119.05
  4992.8     112  5040.1     112  5056.1   119.2  5061.5  114.78    5080  122.68
  5085.4  119.99    5103  125.17  5139.3  123.97    5228   123.5  5331.4  124.72
  5470.8  126.02    5530  129.59  5612.6  128.67    5698  132.68    5788  132.13
  5827.8  130.56  5926.8  132.69  6033.4   129.9  6163.7  131.46    6520  148.36
#Mann= 9 ,-1 , 0
  3972.5     .11       0    4154     .17       0  4785.3     .15       0
  4933.8     .09       0    5103     .15       0  5139.3     .17       0
    5228     .15       0  5331.4     .17       0    5788     .11       0
Bank Sta=4933.8,5103
XS Rating Curve= 0 ,0
Exp/Cntr=0.3,0.1

Type RM Length L Ch R = 1 ,24000   ,558,558,558
BEGIN DESCRIPTION:
CRYSTAL CREEK 48.0
END DESCRIPTION:
XS GIS Cut Line= 3
      3864017.83     10091861.07      3863240.43     10091962.57
      3861656.79     10092795.88
#Sta/Elev= 30
    4216  153.88  4255.7  153.02  4286.6  150.68  4316.8     143  4492.7  127.49
    4579  123.45  4656.8  124.52  4679.9  121.86  4700.1  124.94  4841.2  126.03
  4911.8   121.6  4941.3  125.78  4962.3   121.3  4968.9  112.31  5016.2  112.31
  5030.1  121.63  5090.1  122.36  5127.2  121.32  5140.3  126.15  5200.7  124.07
  5244.8  129.09    5534  131.14  5556.6  128.15  5756.7  125.55  6057.5  125.94
  6277.3  131.13  6411.9  129.82  6525.7  134.83  6598.6   140.1  6789.5  151.46
#Mann= 13 ,-1 , 0
    4216     .11       0  4255.7     .17       0  4492.7     .15       0
  4656.8     .17       0  4941.3     .15       0  4962.3     .09       0
  5030.1     .15       0  5090.1     .17       0  6057.5     .11       0
  6277.3     .17       0  6411.9     .11       0  6525.7     .17       0
  6598.6     .11       0
Bank Sta=4962.3,5030.1
XS Rating Curve= 0 ,0
Exp/Cntr=0.3,0.1

Type RM Length L Ch R = 1 ,23442   ,442,442,442
BEGIN DESCRIPTION:
CRYSTAL CREEK 47.0
END DESCRIPTION:
XS GIS Cut Line= 3
      3863337.35     10091261.15      3862813.82     10091771.47
      3861646.39     10092528.51
#Sta/Elev= 30
  4268.9  150.34  4501.9   142.3  4560.5  137.67  4770.7   123.3  4834.2  123.87
  4855.4  115.16  4862.5  117.87  4869.5  112.91  4876.7  114.88  4883.6  111.51
  4890.8  117.07  4897.8     115    4905  118.98  4926.1  115.89  4933.2  118.76
  4940.2  115.97  4947.4  120.09  4995.3  110.31  5042.7  110.31  5043.7  110.81
  5046.3120.0825    5047  122.58  5062.2  124.92  5152.9  125.12  5293.2  124.31
  5400.4  128.23  5698.4  123.12  5877.7  123.67  6095.3  133.14  6391.4  152.81
#Mann= 5 ,-1 , 0
  4268.9     .11       0  4560.5     .15       0  4947.4     .09       0
  5046.3     .15       0  5152.9     .17       0
Bank Sta=4947.4,5046.3
XS Rating Curve= 0 ,0
Exp/Cntr=0.3,0.1

Type RM Length L Ch R = 1 ,23000   ,500,500,500
BEGIN DESCRIPTION:
CRYSTAL CREEK 46.0
END DESCRIPTION:
XS GIS Cut Line= 3
      3863306.06     10091229.92      3862473.93     10091526.79
      3861629.04     10092174.33
#Sta/Elev= 30
  4116.5  150.88  4404.6   137.9  4422.5  139.34  4640.5  129.83  4845.5  126.03
  4868.4   123.2  4907.1  119.53  4912.4  116.64  4937.9  115.85  4943.2  111.88
  4963.4  112.37    4984  109.83  5031.4  109.83  5035.4  117.46  5049.9  121.36
  5064.5  119.54  5085.3  123.49    5185  118.76  5243.1  118.92  5263.9  122.75
  5384.7  120.64  5407.2  123.14  5442.5  122.45  5492.4  125.09  5572.9  122.69
    5655  123.06  5700.9  123.08    5809  129.05    5914  138.87  6064.5   149.2
#Mann= 8 ,-1 , 0
  4116.5     .11       0  4868.4     .09       0  5085.3     .11       0
  5384.7     .17       0  5572.9     .11       0    5655     .17       0
  5700.9     .11       0    5809     .17       0
Bank Sta=4868.4,5085.3
XS Rating Curve= 0 ,0
Exp/Cntr=0.3,0.1

Type RM Length L Ch R = 1 ,22500   ,500,500,500
BEGIN DESCRIPTION:
CRYSTAL CREEK 45.0
END DESCRIPTION:
XS GIS Cut Line= 3
      3863038.76     10090618.78      3862022.54     10091480.82
       3861458.9     10091684.76
#Sta/Elev= 30
  3667.4  151.85  3783.5  148.55  3904.3  141.28  4009.7  132.39    4102  127.87
  4364.5  125.52  4497.4   127.2  4571.1  126.92  4663.3  123.18  4802.9  123.52
  4946.7  120.75  4967.5  116.36  4972.4  108.15  5019.8  108.15  5020.8  108.65
  5026.3  120.48  5036.9  122.95  5068.8  120.83  5074.2  118.55  5079.5  120.67
  5090.1  117.36  5099.5  120.73  5136.1  122.82  5191.4  126.74  5216.8  126.38
  5278.1   131.9    5314  127.56    5370   128.4  5543.2  143.58  5599.4  145.85
#Mann= 6 ,-1 , 0
  3667.4     .17       0  4497.4     .11       0  4802.9     .15       0
  4946.7     .09       0  5026.3     .15       0  5136.1     .11       0
Bank Sta=4946.7,5026.3
XS Rating Curve= 0 ,0
Exp/Cntr=0.3,0.1

Type RM Length L Ch R = 1 ,22000   ,500,500,500
BEGIN DESCRIPTION:
CRYSTAL CREEK 44.0
END DESCRIPTION:
XS GIS Cut Line= 3
      3862717.82      10090211.1      3861916.81     10091039.73
      3861476.26     10091462.52
#Sta/Elev= 30
  3847.5  151.53  3943.3  146.87    4126  138.49  4335.3  126.19  4342.5  127.15
  4370.8  123.38  4469.9  121.09  4505.1  122.99  4519.3  121.75  4554.8  123.38
    4590  122.09  4618.3  124.73    4793  124.45  4887.1  119.62  4922.4  122.07
  4950.7  120.61  4957.9  114.02  4962.4  107.69  5009.9  107.69  5014.3   109.9
  5021.5   109.2  5028.4  112.27  5056.7  119.24    5085  120.17  5106.4  118.73
    5153  121.79  5247.9  131.74    5309  134.57  5337.2  135.32  5610.6  142.74
#Mann= 9 ,-1 , 0
  3847.5     .17       0  3943.3     .11       0    4126     .17       0
    4793     .15       0  4950.7     .09       0  5056.7     .15       0
    5153     .11       0    5309     .15       0  5337.2     .11       0
Bank Sta=4950.7,5056.7
XS Rating Curve= 0 ,0
Exp/Cntr=0.3,0.1

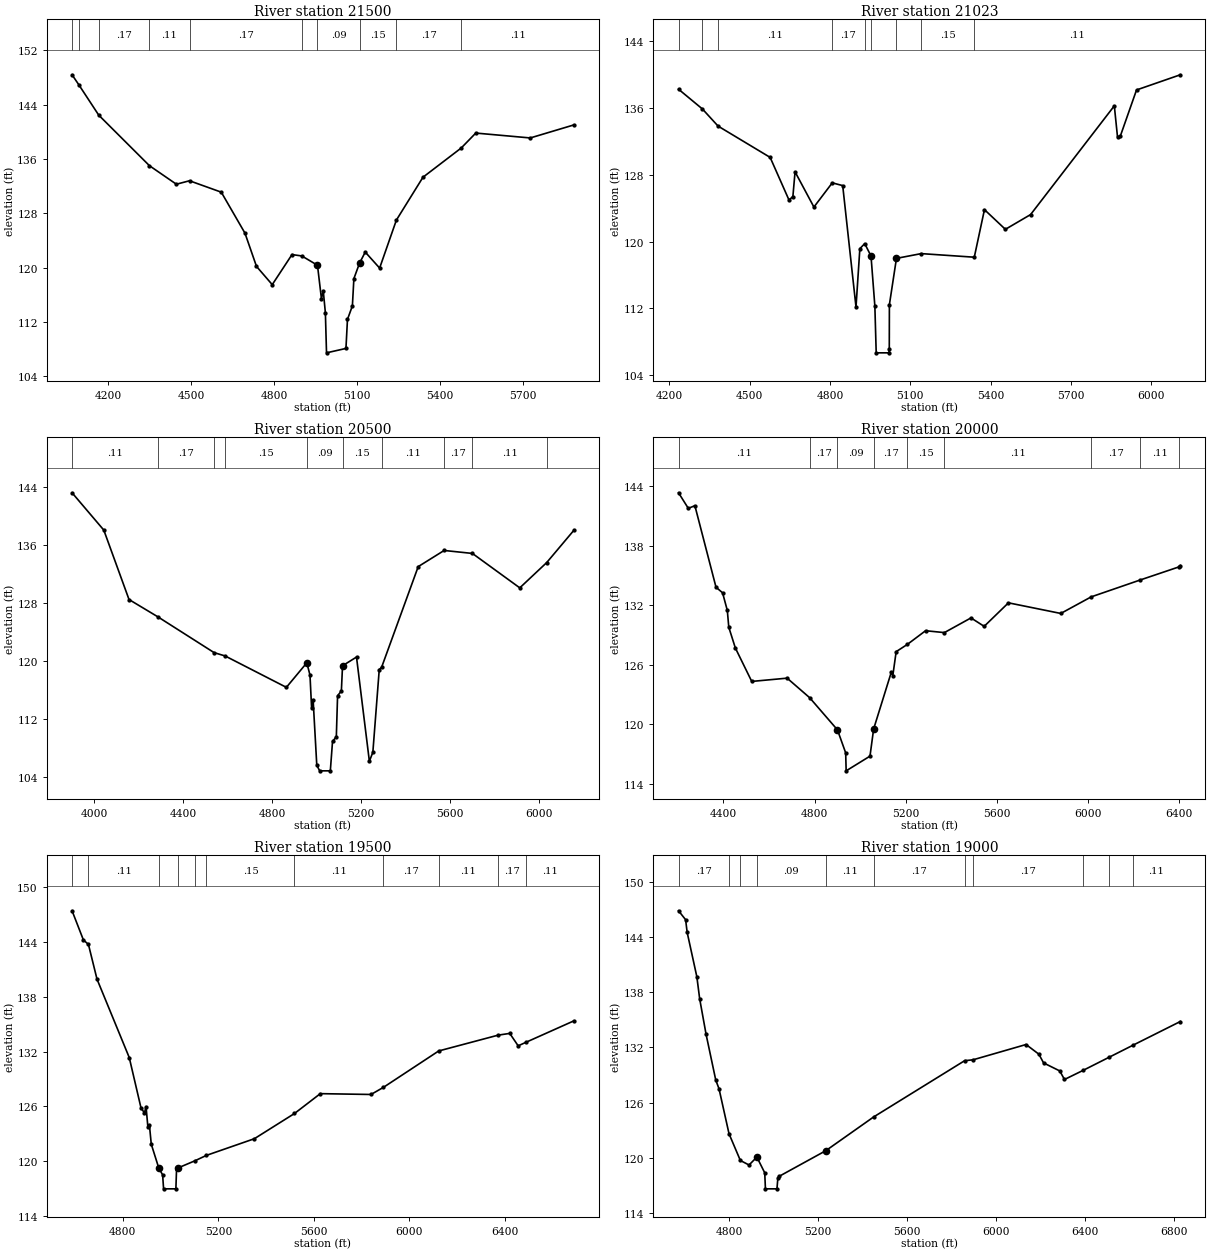
Type RM Length L Ch R = 1 ,21500   ,477,477,477
BEGIN DESCRIPTION:
CRYSTAL CREEK 43.0
END DESCRIPTION:
XS GIS Cut Line= 3
      3862524.85     10089986.85      3861817.11     10090592.03
      3861458.86     10091400.07
#Sta/Elev= 30
  4068.8  148.42  4093.5  146.93  4165.3  142.47  4348.7  135.02  4446.1  132.29
  4493.6   132.8  4608.5  131.12  4694.2  125.08  4735.9  120.18  4792.9  117.49
  4864.3  121.92  4899.8  121.72  4956.5  120.35  4970.8  115.42  4977.4  116.57
  4985.1  113.35  4989.2  107.44  5059.5  108.09    5065  112.37  5082.8  114.36
  5088.2  118.38  5108.8 120.675  5129.3  122.29  5181.3  119.93    5242  127.01
  5338.1  133.32  5476.5  137.63  5529.1  139.83  5726.2  139.11  5883.9  141.03
#Mann= 10 ,-1 , 0
  4068.8     .17       0  4093.5     .11       0  4165.3     .17       0
  4348.7     .11       0  4493.6     .17       0  4899.8     .15       0
  4956.5     .09       0  5108.8     .15       0    5242     .17       0
  5476.5     .11       0
Bank Sta=4956.5,5108.8
XS Rating Curve= 0 ,0
Exp/Cntr=0.3,0.1

Type RM Length L Ch R = 1 ,21023   ,523,523,523
BEGIN DESCRIPTION:
CRYSTAL CREEK 42.0
END DESCRIPTION:
XS GIS Cut Line= 3
      3862093.89     10089596.41      3861621.31     10090199.39
       3861431.1     10091292.36
#Sta/Elev= 30
  4233.9  138.26  4323.2  135.89  4381.7  133.84  4576.3  130.09  4646.8  124.98
  4661.3   125.4  4669.4  128.36  4739.9  124.14  4808.5  127.04  4847.5  126.71
  4897.2  112.16  4911.6  119.15  4929.8  119.76  4953.3  118.27  4967.7  112.27
  4972.7  106.67  5020.6  106.67  5021.6  107.17    5022  112.44  5048.4  117.99
    5141  118.56  5339.3  118.13  5377.3  123.83  5455.5  121.47  5549.8  123.24
  5862.7  136.27  5874.6  132.54  5884.8  132.61  5945.7  138.17  6109.4  139.99
#Mann= 9 ,-1 , 0
  4233.9     .11       0  4323.2     .17       0  4381.7     .11       0
  4808.5     .17       0  4929.8     .15       0  4953.3     .09       0
  5048.4     .11       0    5141     .15       0  5339.3     .11       0
Bank Sta=4953.3,5048.4
XS Rating Curve= 0 ,0
Exp/Cntr=0.3,0.1

Type RM Length L Ch R = 1 ,20500   ,500,500,500
BEGIN DESCRIPTION:
CRYSTAL CREEK 41.0
END DESCRIPTION:
XS GIS Cut Line= 3
      3861868.21     10089469.65      3861121.19     10090277.63
      3860078.52      10090776.8
#Sta/Elev= 30
  3899.6  143.26  4042.3  138.11  4155.7  128.53    4285  126.15  4538.4   121.2
    4588  120.74  4863.3  116.41  4955.2   119.8  4969.4  118.11  4976.7  113.58
  4983.5  114.72    5000  105.67    5013  104.89  5060.9  104.89  5070.8  108.94
  5087.9   109.6  5093.5  115.25  5110.6  115.92  5115.8119.3896  5178.6  120.59
  5236.5  106.21  5252.1  107.45  5280.9  118.87  5291.4  119.17  5456.1  133.07
  5572.7   135.3  5699.8  134.89  5912.8  130.14  6033.9  133.63    6156  138.08
#Mann= 10 ,-1 , 0
  3899.6     .11       0    4285     .17       0  4538.4     .11       0
    4588     .15       0  4955.2     .09       0  5115.8     .15       0
  5291.4     .11       0  5572.7     .17       0  5699.8     .11       0
  6033.9     .17       0
Bank Sta=4955.2,5115.8
XS Rating Curve= 0 ,0
Exp/Cntr=0.3,0.1

Type RM Length L Ch R = 1 ,20000   ,500,500,500
BEGIN DESCRIPTION:
CRYSTAL CREEK 40.0
END DESCRIPTION:
XS GIS Cut Line= 3
       3861618.2      10089370.7      3860998.23     10089871.38
      3859870.03     10090707.07
#Sta/Elev= 30
  4203.1  143.33    4246  141.76  4274.8  142.03  4367.5  133.81  4396.3  133.25
  4417.1  131.47  4423.5  129.78  4452.3  127.69  4524.2  124.32  4679.4  124.65
  4778.2  122.68  4900.1  119.44  4936.2  117.12  4938.3  115.31  5042.8  116.79
  5058.9 119.535  5136.7  125.28  5142.9   124.9  5157.6  127.32  5206.7  128.05
  5286.7  129.43  5369.1  129.24  5485.8  130.72  5543.7  129.87  5650.1  132.24
  5879.7  131.17    6013  132.84    6229  134.55  6396.5  135.85    6404     136
#Mann= 9 ,-1 , 0
  4203.1     .11       0  4778.2     .17       0  4900.1     .09       0
  5058.9     .17       0  5206.7     .15       0  5369.1     .11       0
    6013     .17       0    6229     .11       0  6396.5     .17       0
Bank Sta=4900.1,5058.9
XS Rating Curve= 0 ,0
Exp/Cntr=0.3,0.1

Type RM Length L Ch R = 1 ,19500   ,500,500,500
BEGIN DESCRIPTION:
CRYSTAL CREEK 39.0
END DESCRIPTION:
XS GIS Cut Line= 3
      3861279.67      10089125.9      3860967.83     10089395.31
      3859824.72     10090637.34
#Sta/Elev= 30
  4587.9   147.4  4635.3  144.21  4656.4  143.72  4692.3  139.92  4827.2  131.35
  4876.6  125.82  4890.9   125.3  4897.5  125.99  4905.1  123.78  4911.7  123.94
  4919.4  121.87 4950.87119.2588  4966.9  118.52  4970.9  116.99  5022.4  116.99
  5025.2  119.15  5032.7119.2903  5101.4  120.05  5150.3  120.65  5350.7  122.47
  5518.8  125.23  5626.9   127.4    5839  127.31  5891.1  128.09  6122.4  132.07
  6371.4   133.8  6419.7  133.99  6454.9  132.63  6488.6  133.03    6688  135.36
#Mann= 11 ,-1 , 0
  4587.9     .17       0  4656.4     .11       0 4950.87     .07       0
  5032.7     .11       0  5101.4     .17       0  5150.3     .15       0
  5518.8     .11       0  5891.1     .17       0  6122.4     .11       0
  6371.4     .17       0  6488.6     .11       0
Bank Sta=4950.87,5032.7
XS Rating Curve= 0 ,0
Exp/Cntr=0.3,0.1

Type RM Length L Ch R = 1 ,19000   ,500,500,500
BEGIN DESCRIPTION:
CRYSTAL CREEK 38.0
END DESCRIPTION:
XS GIS Cut Line= 3
      3860937.04     10088665.96      3860675.18     10089003.88
      3859692.21     10090543.91
#Sta/Elev= 30
  4572.5  146.84  4604.3  145.87  4611.3  144.49  4654.8  139.67  4667.5  137.27
  4696.4   133.4  4739.8  128.44  4754.3  127.51  4799.4  122.61  4850.3  119.71
  4889.2  119.22  4924.5  120.08  4959.8  118.37  4962.9  116.63  5014.7  116.63
  5018.7  117.77  5024.6  117.99  5233.9  120.77  5449.1  124.44  5857.8  130.55
  5895.8  130.65  6133.9  132.31  6191.4  131.26  6212.6  130.31  6285.3  129.44
  6306.5  128.51    6391  129.51  6504.9   130.9  6612.3  132.21    6827  134.81
#Mann= 11 ,-1 , 0
  4572.5     .17       0  4799.4     .15       0  4850.3     .17       0
  4924.5     .09       0  5233.9     .11       0  5449.1     .17       0
  5857.8     .11       0  5895.8     .17       0    6391     .11       0
  6504.9     .17       0  6612.3     .11       0
Bank Sta=4924.5,5233.9
XS Rating Curve= 0 ,0
Exp/Cntr=0.3,0.1

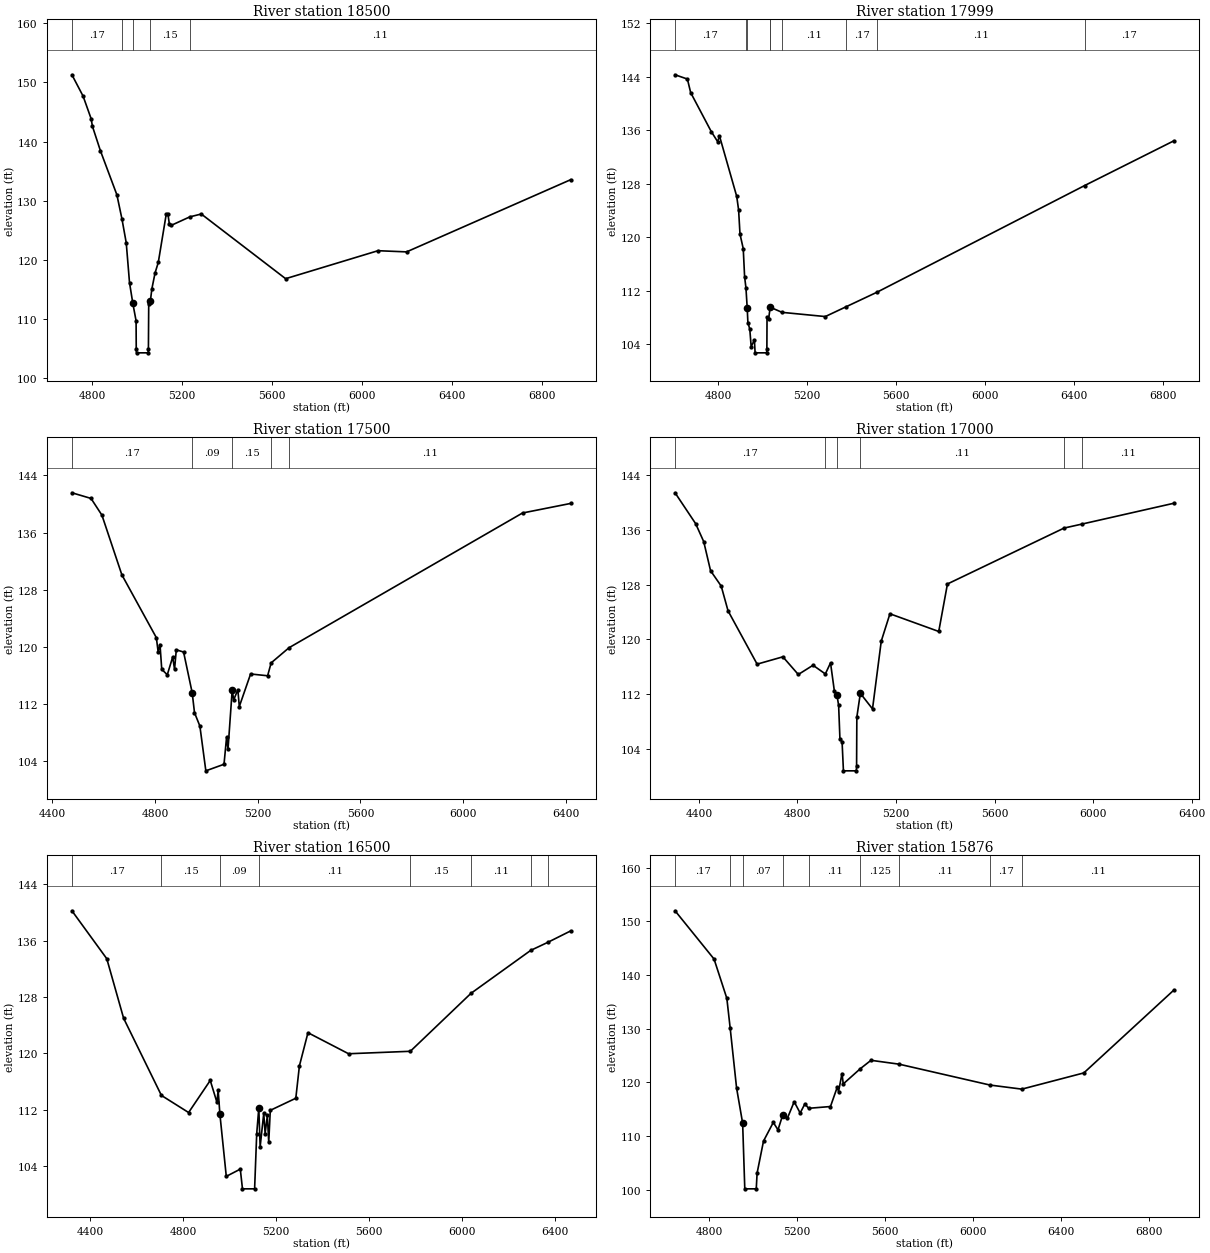
Type RM Length L Ch R = 1 ,18500   ,501,501,501
BEGIN DESCRIPTION:
CRYSTAL CREEK 37.0
END DESCRIPTION:
XS GIS Cut Line= 3
      3860618.89     10088433.45      3860386.03      10088607.3
      3859087.41       10090031.
#Sta/Elev= 30
  4709.4  151.28  4759.2  147.66  4794.6  143.88  4800.8  142.55  4836.3  138.42
  4909.3     131  4931.9  126.91  4950.9  122.89  4965.5  116.15  4980.1  112.67
  4994.7   109.7  4995.4  104.89  4996.6  104.29  5048.4  104.29  5049.5  104.89
  5050.9  112.58  5058.3  113.08    5065  115.13  5079.2  117.81  5093.4  119.56
  5128.6  127.69    5136  127.83  5142.7  126.03  5150.2  125.82  5233.8  127.27
  5284.6  127.75  5659.6  116.82  6070.4  121.55  6197.4  121.35    6927  133.55
#Mann= 5 ,-1 , 0
  4709.4     .17       0  4931.9     .15       0  4980.1     .09       0
  5058.3     .15       0  5233.8     .11       0
Bank Sta=4980.1,5058.3
XS Rating Curve= 0 ,0
Exp/Cntr=0.3,0.1

Type RM Length L Ch R = 1 ,17999   ,499,499,499
BEGIN DESCRIPTION:
CRYSTAL CREEK 36.0
END DESCRIPTION:
XS GIS Cut Line= 3
      3860319.04     10088114.31      3859996.93     10088349.94
      3858674.19     10089631.72
#Sta/Elev= 30
  4606.1  144.31  4661.6  143.67  4676.3  141.64  4768.6  135.82  4797.5   134.3
  4805.8  135.15  4883.2  126.11  4891.7  124.07  4897.9  120.47  4912.5  118.29
  4918.7  114.05  4924.6  112.43 4930.47109.3465  4933.4  107.22  4941.9  106.24
  4948.1  103.63  4962.7  104.61  4965.8  102.69  5017.6  102.69  5018.7  103.29
  5019.4  108.01  5026.6  107.77  5033.5 109.495  5033.6  109.52  5086.8  108.75
  5281.2  108.12  5374.2  109.58  5513.8  111.77  6446.5  127.73  6847.1  134.42
#Mann= 9 ,-1 , 0
  4606.1     .17       0  4924.6     .15       0 4930.47     .09       0
  5033.5     .12       0  5033.6     .15       0  5086.8     .11       0
  5374.2     .17       0  5513.8     .11       0  6446.5     .17       0
Bank Sta=4930.47,5033.5
XS Rating Curve= 0 ,0
Exp/Cntr=0.3,0.1

Type RM Length L Ch R = 1 ,17500   ,500,500,500
BEGIN DESCRIPTION:
CRYSTAL CREEK 35.0
END DESCRIPTION:
XS GIS Cut Line= 3
      3860164.27     10087722.64      3859778.45     10088077.21
      3858524.98     10088742.96
#Sta/Elev= 30
    4476  141.58  4550.4  140.79  4592.9  138.45  4670.6   130.1    4805  121.31
  4811.8  119.37  4819.2  120.35    4826  116.88  4847.6  116.12  4868.6   118.6
  4875.9  116.89  4882.7  119.61  4911.1   119.3 4944.68113.5919  4953.6  110.82
  4974.6  108.94  4997.8  102.68  5068.6   103.6  5078.6  107.39  5084.2  105.71
  5100.5     114  5106.2  112.59  5122.5  114.04  5128.2  111.68  5172.2  116.23
  5238.5  115.98  5252.2  117.78  5321.8   119.9  6231.6  138.75  6419.3  140.09
#Mann= 5 ,-1 , 0
    4476     .17       0 4944.68     .09       0  5100.5     .15       0
  5252.2     .17       0  5321.8     .11       0
Bank Sta=4944.68,5100.5
XS Rating Curve= 0 ,0
Exp/Cntr=0.3,0.1

Type RM Length L Ch R = 1 ,17000   ,500,500,500
BEGIN DESCRIPTION:
CRYSTAL CREEK 34.0
END DESCRIPTION:
XS GIS Cut Line= 3
       3860096.6     10087563.04      3859429.65     10087765.12
      3858472.28     10088684.45
#Sta/Elev= 30
  4303.1  141.41  4386.6  136.91  4419.5  134.28  4447.2  130.04  4490.5  127.79
  4518.2  124.18  4636.2   116.4  4740.7  117.47  4803.3  114.89  4863.1  116.24
  4913.1  114.97  4934.1  116.59  4949.6   112.5  4960.1  111.91    4967  110.38
  4972.3  105.49    4981  105.07  4986.5  100.83  5038.7  100.83  5039.9  101.53
  5040.9  108.67  5055.1  112.14  5104.5  109.87    5140  119.76  5175.2  123.75
  5373.3  121.17  5408.6   128.1  5881.9  136.26    5953  136.83  6327.3  139.88
#Mann= 6 ,-1 , 0
  4303.1     .17       0  4913.1     .11       0  4960.1     .09       0
  5055.1     .11       0  5881.9     .17       0    5953     .11       0
Bank Sta=4960.1,5055.1
XS Rating Curve= 0 ,0
Exp/Cntr=0.3,0.1

Type RM Length L Ch R = 1 ,16500   ,624,624,624
BEGIN DESCRIPTION:
CRYSTAL CREEK 33.0
END DESCRIPTION:
XS GIS Cut Line= 3
       3860062.7     10087205.21      3859408.01     10087379.16
      3858152.77      10088138.4
#Sta/Elev= 30
  4322.6  140.25  4472.5  133.44  4544.9  124.98  4707.4  114.02  4824.3  111.59
  4917.4  116.15  4946.1  113.04  4951.3  114.78  4958.8  111.36  4986.3  102.52
  5046.5  103.55  5055.9  100.75  5108.1  100.75  5117.1  108.58  5126.1  112.23
  5131.9  106.74  5147.4  111.47  5153.3  108.59  5162.9  111.18  5168.8  107.36
  5175.5   111.9  5285.2  113.62  5300.7  118.22  5337.5  122.93  5512.1  119.94
  5777.6  120.29  6038.3  128.52    6295  134.62  6368.3  135.76    6467  137.39
#Mann= 8 ,-1 , 0
  4322.6     .17       0  4707.4     .15       0  4958.8     .09       0
  5126.1     .11       0  5777.6     .15       0  6038.3     .11       0
    6295     .17       0  6368.3     .11       0
Bank Sta=4958.8,5126.1
XS Rating Curve= 0 ,0
Exp/Cntr=0.3,0.1

Type RM Length L Ch R = 1 ,15876   ,656,656,656
BEGIN DESCRIPTION:
CRYSTAL CREEK 32.0
END DESCRIPTION:
XS GIS Cut Line= 3
       3859954.8     10086680.88      3859642.85     10086886.07
      3858019.08     10087865.74
#Sta/Elev= 30
  4644.6  151.97  4822.1  142.98  4880.3  135.66  4895.6  130.08  4924.6  118.97
  4952.2  112.41    4962  100.18  5014.2  100.18    5018  103.11  5047.2  109.08
  5091.7  112.55  5113.1  111.17  5134.6  113.93  5155.8  113.33  5186.8   116.4
    5214   114.3  5235.4     116  5252.5  115.18  5351.9  115.51  5382.9  119.13
  5388.7   118.3  5404.3  121.64  5410.1  119.72  5488.4  122.58  5536.3  124.12
  5664.2   123.4    6078  119.51  6222.8  118.75  6504.9  121.77  6914.4  137.19
#Mann= 9 ,-1 , 0
  4644.6     .17       0  4895.6     .11       0  4952.2     .07       0
  5134.6     .17       0  5252.5     .11       0  5488.4    .125       0
  5664.2     .11       0    6078     .17       0  6222.8     .11       0
Bank Sta=4952.2,5134.6
XS Rating Curve= 0 ,0
Exp/Cntr=0.3,0.1