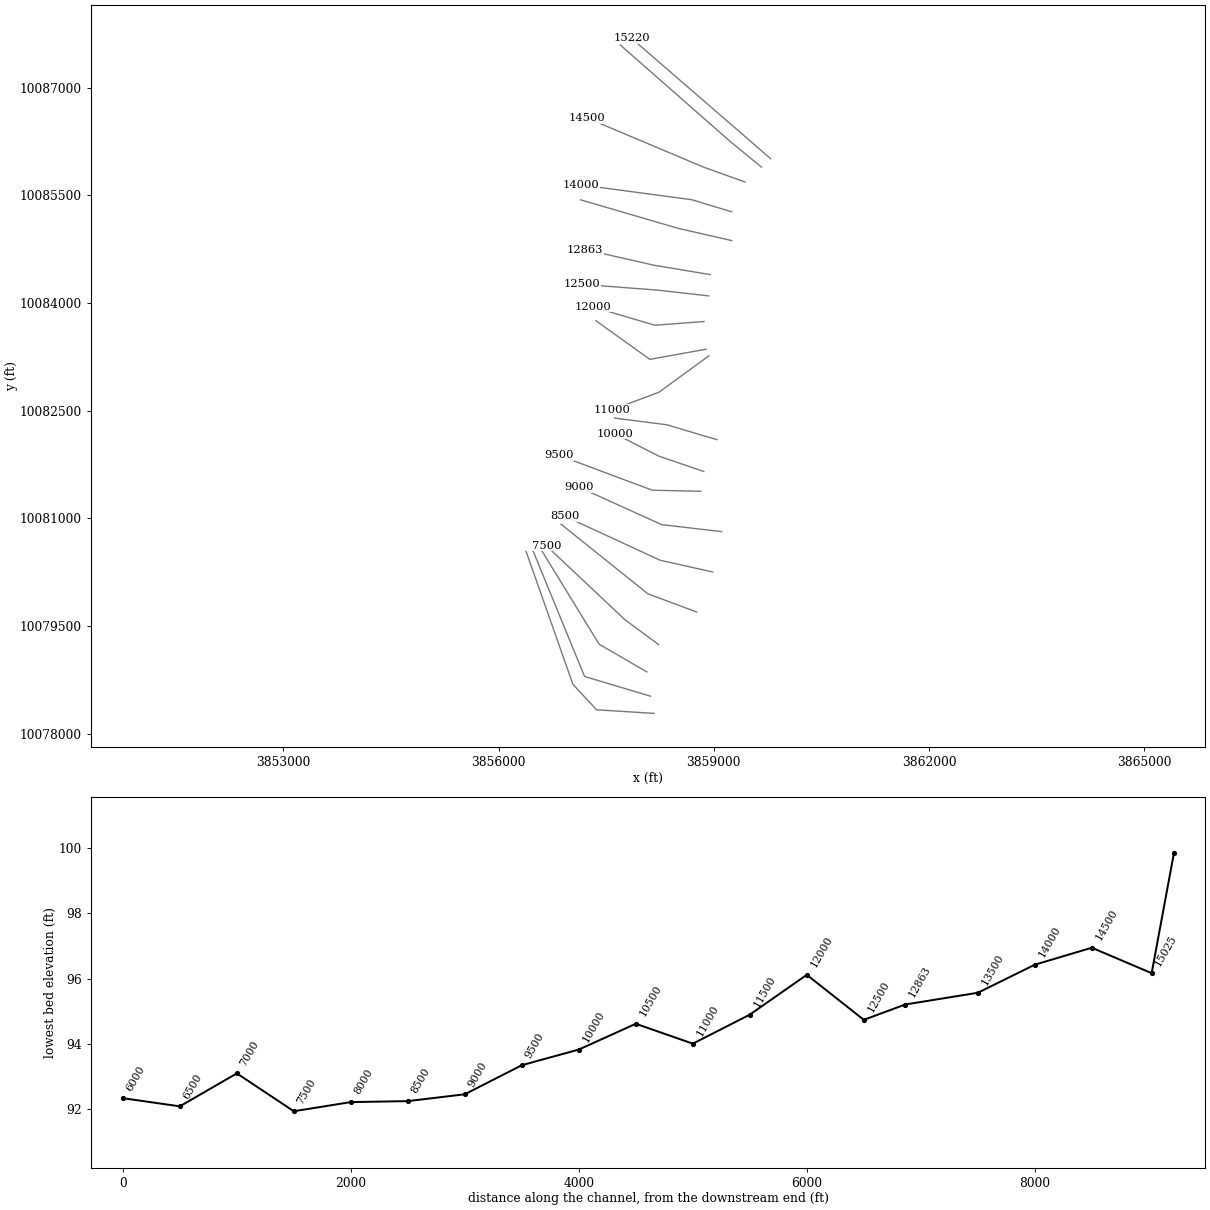
HEC-RAS study CRYSTAL CREEK.prj: CRYSTAL CREEK Base Level Engineering

--- CRYSTAL CREEK.g01 (geometry) --- (continued)

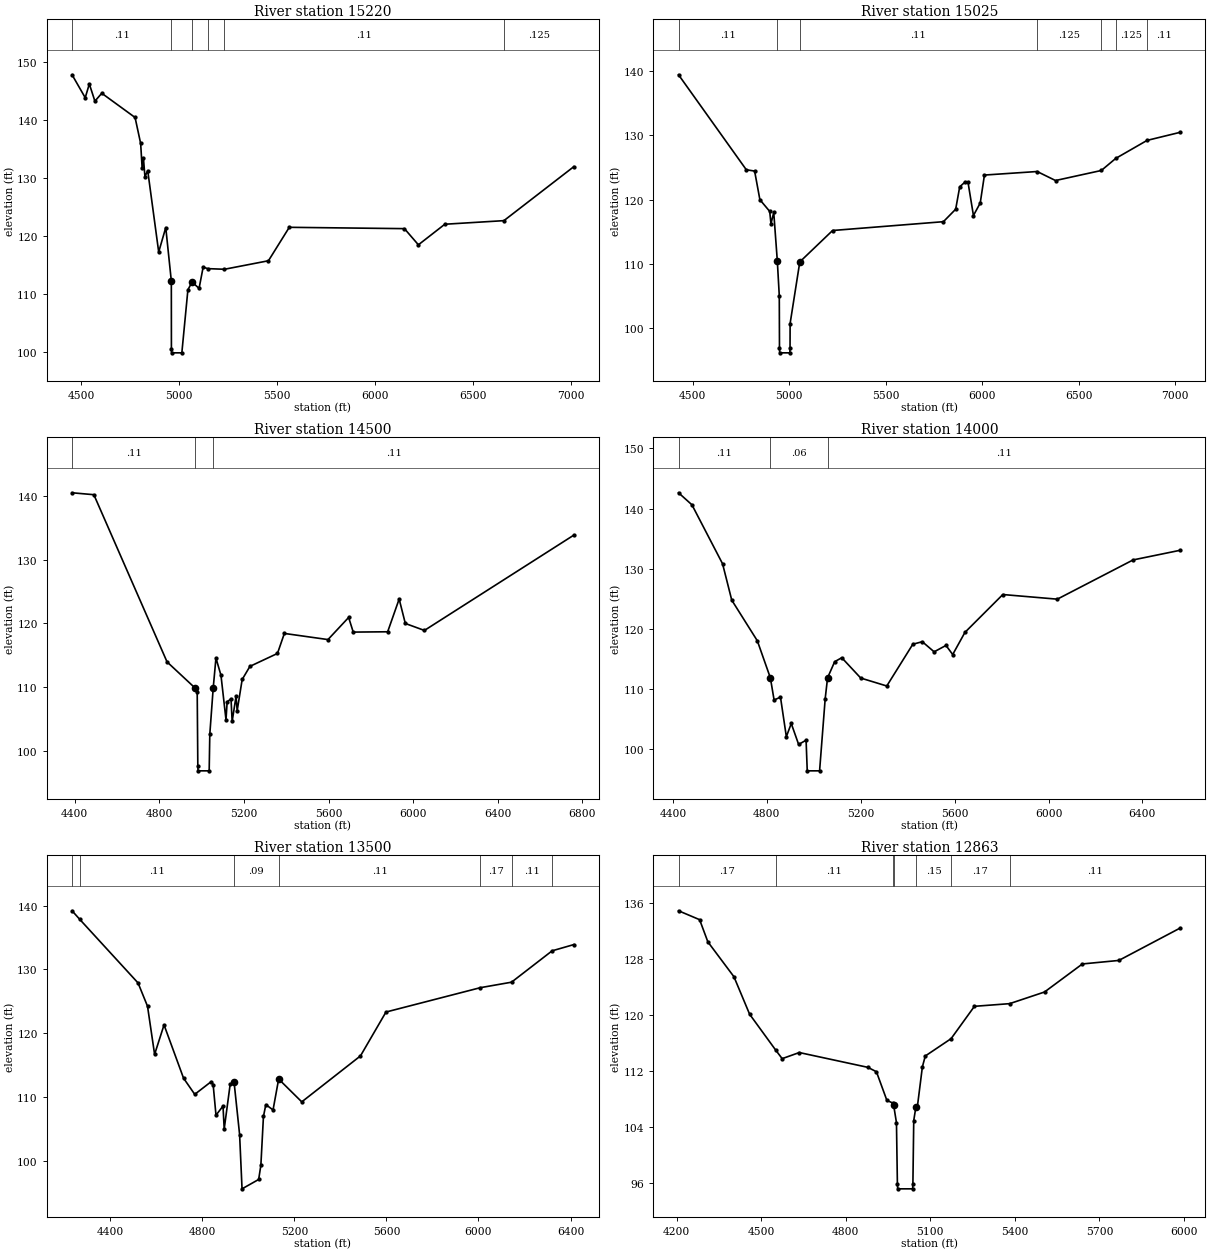
Type RM Length L Ch R = 1 ,15220   ,195,195,195
BEGIN DESCRIPTION:
CRYSTAL CREEK 31.0
END DESCRIPTION:
XS GIS Cut Line= 3
      3859790.76     10086009.55      3859378.43       10086367.
      3857853.58     10087686.36
#Sta/Elev= 30
  4454.3  147.82  4521.5  143.86  4542.4  146.23  4570.9  143.27    4606  144.63
    4776  140.45  4804.5  135.97  4812.1  131.73  4818.7  133.41  4826.4  130.24
  4840.6  131.28  4896.6  117.24  4932.7  121.46  4961.1  112.23  4961.5  100.54
  4962.6   99.84  5014.8   99.84  5045.7  110.71  5066.9  112.06  5102.8  110.96
  5123.6  114.63  5147.3  114.37  5232.4  114.26    5457  115.73  5563.4   121.5
  6151.3  121.27  6222.6  118.48  6357.5  122.03  6659.3  122.65  7016.4  131.97
#Mann= 6 ,-1 , 0
  4454.3     .11       0  4961.1     .06       0  5066.9     .11       0
  5147.3     .15       0  5232.4     .11       0  6659.3    .125       0
Bank Sta=4961.1,5066.9
XS Rating Curve= 0 ,0
Exp/Cntr=0.3,0.1

Type RM Length L Ch R = 1 ,15025   ,525,525,525
BEGIN DESCRIPTION:
CRYSTAL CREEK 30.0
END DESCRIPTION:
XS GIS Cut Line= 3
      3859662.93     10085892.02      3859220.69     10086255.74
      3857697.01     10087592.88
#Sta/Elev= 30
  4427.4   139.4  4778.6  124.63  4821.6  124.43  4848.9  119.98  4899.8  118.16
  4906.3  116.24  4920.7  117.99 4939.13110.4917  4949.4  105.03  4950.4   96.87
  4951.6   96.17    5004   96.17  5005.1   96.87  5005.5  100.73  5055.7  110.31
  5225.6  115.19  5799.7  116.56  5863.3   118.5  5884.2  121.98  5912.6  122.75
  5926.9  122.74  5955.3  117.52  5990.5  119.46  6012.3  123.81  6285.4  124.36
  6380.5  122.96  6617.8  124.52  6692.7   126.4    6855   129.2  7027.2  130.46
#Mann= 7 ,-1 , 0
  4427.4     .11       0 4939.13     .09       0  5055.7     .11       0
  6285.4    .125       0  6617.8     .11       0  6692.7    .125       0
    6855     .11       0
Bank Sta=4939.13,5055.7
XS Rating Curve= 0 ,0
Exp/Cntr=0.3,0.1

Type RM Length L Ch R = 1 ,14500   ,500,500,500
BEGIN DESCRIPTION:
CRYSTAL CREEK 29.0
END DESCRIPTION:
XS GIS Cut Line= 3
      3859434.79     10085684.36      3858858.02     10085891.07
      3857236.88     10086574.99
#Sta/Elev= 30
  4387.3  140.44  4490.3  140.14  4836.3  113.99  4968.3  109.92  4978.9  109.24
  4981.8   97.65    4983   96.95  5035.5   96.95  5038.4  102.66  5054.4  109.85
  5067.5  114.59  5091.2   111.9    5115  104.94  5120.4  107.73  5138.7  108.23
  5144.1  104.68  5162.4  108.59  5167.8  106.35  5191.5  111.24  5228.1  113.29
  5358.3  115.31  5390.9  118.44  5597.1  117.48  5694.8  120.94  5716.5  118.65
  5879.3   118.7  5933.6  123.82  5962.7     120    6053  118.91  6759.5  133.82
#Mann= 3 , 0 , 0
  4387.3     .11       0  4968.3     .09       0  5054.4     .11       0
Bank Sta=4968.3,5054.4
XS Rating Curve= 0 ,0
Exp/Cntr=0.3,0.1

Type RM Length L Ch R = 1 ,14000   ,500,500,500
BEGIN DESCRIPTION:
CRYSTAL CREEK 28.0
END DESCRIPTION:
XS GIS Cut Line= 3
      3859247.33     10085269.42      3858696.04     10085437.02
      3857148.38     10085644.42
#Sta/Elev= 30
  4423.8  142.64  4480.9  140.64  4611.4  130.84  4650.5   124.8  4759.5  118.04
 4815.04 111.879  4830.9   108.2  4858.1  108.68  4883.1   102.1    4904   104.3
  4935.4  100.82  4967.2  101.52  4972.1   96.43  5024.7   96.43  5048.6  108.43
  5058.7  111.89    5089  114.57  5119.2  115.23    5200  111.85  5310.9  110.53
  5421.9  117.47  5462.3  117.89  5512.7  116.21  5563.2  117.27  5591.8  115.76
  5643.9  119.44  5805.3  125.73  6037.4  124.96  6360.2  131.48  6561.5  133.09
#Mann= 3 , 0 , 0
  4423.8     .11       0 4815.04     .06       0  5058.7     .11       0
Bank Sta=4815.04,5058.7
XS Rating Curve= 0 ,0
Exp/Cntr=0.3,0.1

Type RM Length L Ch R = 1 ,13500   ,637,637,637
BEGIN DESCRIPTION:
CRYSTAL CREEK 27.0
END DESCRIPTION:
XS GIS Cut Line= 3
      3859247.34     10084868.37      3858500.92     10085039.56
      3857143.23     10085436.06
#Sta/Elev= 30
  4234.2  139.18  4267.4  137.84  4520.9  127.86    4562  124.21  4592.8  116.66
  4633.8  121.28  4718.5  112.93  4767.2  110.39    4839  112.39  4847.2  111.91
  4859.5  107.12    4890  108.55  4895.2  104.96  4921.1  111.95  4938.1   112.3
  4962.1  104.09  4972.7   95.57  5044.9   97.04  5054.5   99.26  5065.7  106.92
  5076.1  108.78  5107.4  107.94  5131.8  112.79  5232.2  109.21  5487.3  116.42
  5598.1   123.3  6008.2  127.12  6143.6  127.98    6320   132.9  6414.4  133.88
#Mann= 7 ,-1 , 0
  4234.2     .17       0  4267.4     .11       0  4938.1     .09       0
  5131.8     .11       0  6008.2     .17       0  6143.6     .11       0
    6320     .17       0
Bank Sta=4938.1,5131.8
XS Rating Curve= 0 ,0
Exp/Cntr=0.3,0.1

Type RM Length L Ch R = 1 ,12863   ,363,363,363
BEGIN DESCRIPTION:
CRYSTAL CREEK 26.0
END DESCRIPTION:
XS GIS Cut Line= 3
      3858950.43     10084394.42      3858168.21     10084524.73
      3857205.63     10084743.38
#Sta/Elev= 30
    4207  134.85  4281.8  133.58    4311  130.42  4403.5  125.45  4459.2   120.1
  4551.1  115.02  4574.6  113.77  4635.4  114.64  4878.7  112.53  4909.1   111.9
    4946  107.83  4966.9  107.44  4969.9  107.19  4980.1  104.64  4983.4   95.91
  4984.6   95.21  5037.3   95.21  5038.4   95.91  5041.4  104.95  5048.9  106.85
    5054  106.83  5072.1  112.61  5082.4  114.15  5173.9  116.62  5256.7  121.23
  5381.6  121.61  5505.3  123.27  5639.7  127.27  5768.9  127.77  5987.1   132.4
#Mann= 7 ,-1 , 0
    4207     .17       0  4551.1     .11       0  4966.9     .15       0
  4969.9     .09       0  5048.9     .15       0  5173.9     .17       0
  5381.6     .11       0
Bank Sta=4969.9,5048.9
XS Rating Curve= 0 ,0
Exp/Cntr=0.3,0.1

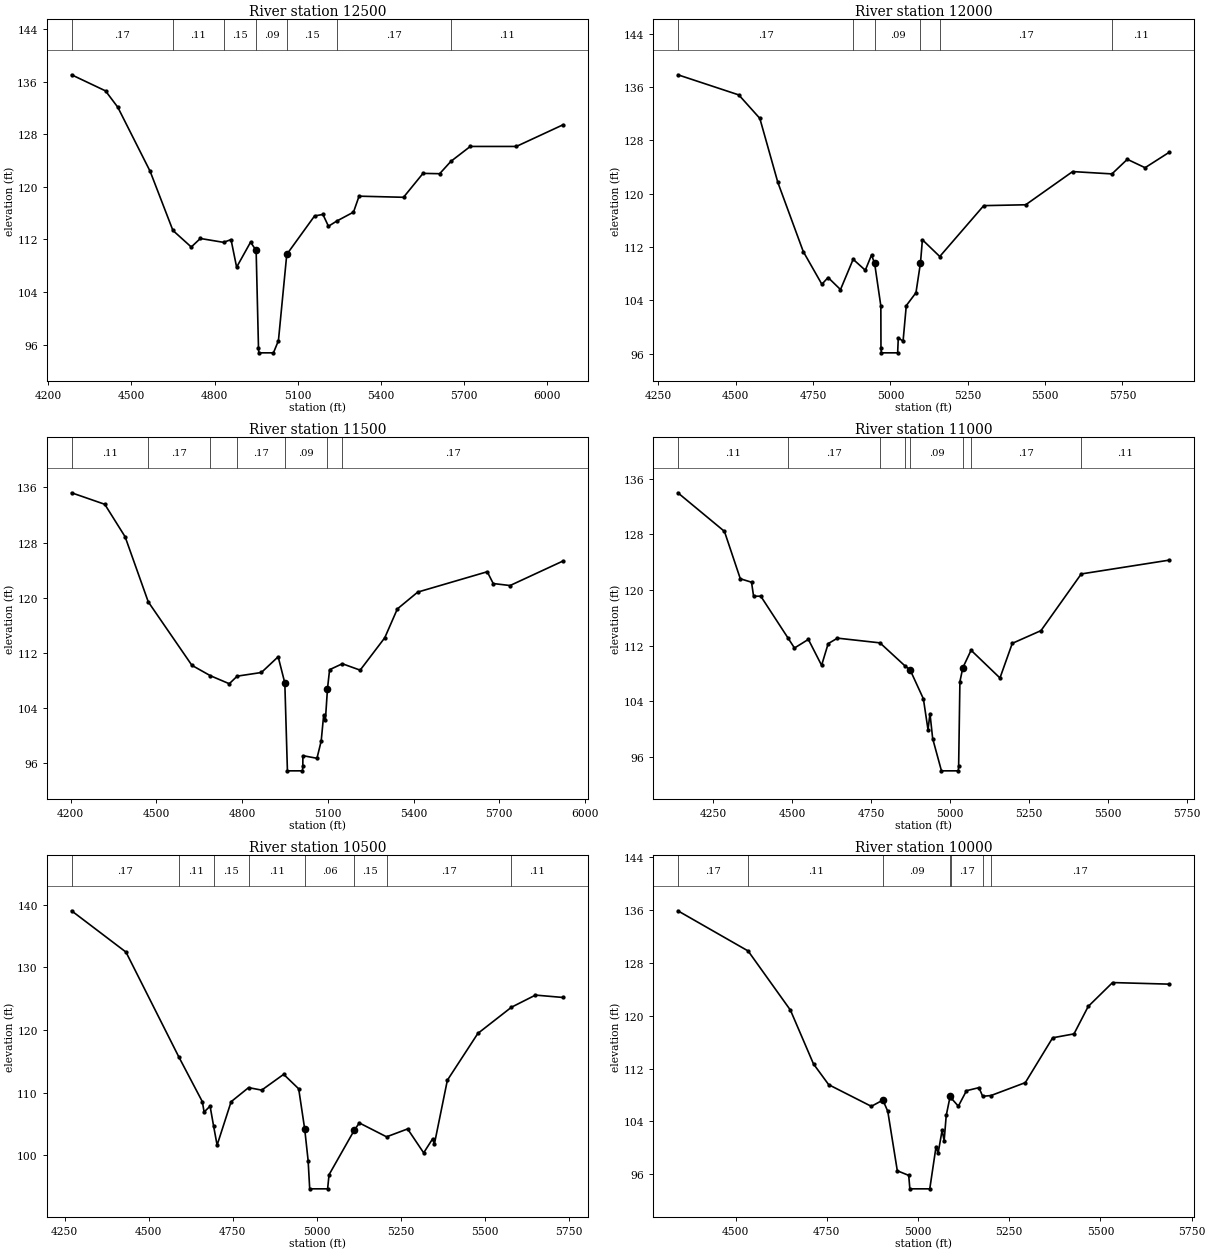
Type RM Length L Ch R = 1 ,12500   ,500,500,500
BEGIN DESCRIPTION:
CRYSTAL CREEK 25.0
END DESCRIPTION:
XS GIS Cut Line= 3
      3858929.59     10084097.55      3858218.27     10084177.53
      3857164.01       10084259.
#Sta/Elev= 30
  4284.2  137.07  4406.7  134.62    4451  132.13  4567.7  122.37  4649.9  113.37
  4716.1  110.85  4748.8  112.15  4832.5  111.56  4859.5  111.98  4879.7  107.78
    4930  111.59  4950.1  110.33  4958.6   95.44  4959.8   94.74  5012.5   94.74
  5030.5   96.59  5060.6  109.72  5160.9  115.58    5191  115.81    5211  114.01
  5240.9   114.8  5301.3  116.16  5321.4  118.59  5481.8  118.42  5552.1  122.06
  5612.2  122.01  5652.7  123.89  5722.6  126.16  5888.8  126.16  6057.4  129.46
#Mann= 7 ,-1 , 0
  4284.2     .17       0  4649.9     .11       0  4832.5     .15       0
  4950.1     .09       0  5060.6     .15       0  5240.9     .17       0
  5652.7     .11       0
Bank Sta=4950.1,5060.6
XS Rating Curve= 0 ,0
Exp/Cntr=0.3,0.1

Type RM Length L Ch R = 1 ,12000   ,500,500,500
BEGIN DESCRIPTION:
CRYSTAL CREEK 24.0
END DESCRIPTION:
XS GIS Cut Line= 3
      3858861.96     10083740.77      3858177.03     10083688.75
      3857312.63     10083944.71
#Sta/Elev= 30
  4313.1  137.83    4510  134.81    4578  131.29  4636.2  121.69  4718.4  111.31
  4778.5  106.41  4798.6  107.42  4838.7  105.61  4879.6  110.15  4918.9  108.51
    4939   110.8    4949  109.54  4969.1  103.15  4969.5   96.82  4970.7   96.12
  5023.4   96.12  5025.5   98.38  5040.9   97.86  5051.3   103.2  5082.6  105.14
  5097.2  109.62  5103.4  113.08  5159.5  110.57  5301.6   118.2  5437.2  118.33
  5588.9  123.31  5715.9  122.96  5765.6  125.15    5823  123.89  5901.5  126.22
#Mann= 6 ,-1 , 0
  4313.1     .17       0  4879.6     .15       0    4949     .09       0
  5097.2     .15       0  5159.5     .17       0  5715.9     .11       0
Bank Sta=4949,5097.2
XS Rating Curve= 0 ,0
Exp/Cntr=0.3,0.1

Type RM Length L Ch R = 1 ,11500   ,500,500,500
BEGIN DESCRIPTION:
CRYSTAL CREEK 23.0
END DESCRIPTION:
XS GIS Cut Line= 3
      3858892.26     10083354.48      3858108.25     10083213.41
      3857357.66     10083750.92
#Sta/Elev= 30
  4203.4  135.22  4319.6  133.55  4390.8  128.84  4471.8   119.4  4624.5   110.2
  4689.3  108.69  4755.3  107.53  4782.9  108.63  4867.6  109.16  4926.3  111.44
  4949.6  107.64  4958.7    94.9  5011.4    94.9  5012.6    95.6  5012.8    97.1
  5062.1   96.72  5076.9   99.23  5085.4  102.95  5091.6  102.27  5098.9  106.82
  5106.3  109.57  5150.9  110.43  5213.2   109.5  5299.2  114.19  5343.4  118.38
  5414.7  120.82  5657.9  123.77  5678.8  122.06  5737.7  121.77  5923.2  125.33
#Mann= 7 ,-1 , 0
  4203.4     .11       0  4471.8     .17       0  4689.3     .15       0
  4782.9     .17       0  4949.6     .09       0  5098.9     .17       0
  5150.9     .17       0
Bank Sta=4949.6,5098.9
XS Rating Curve= 0 ,0
Exp/Cntr=0.3,0.1

Type RM Length L Ch R = 1 ,11000   ,500,500,500
BEGIN DESCRIPTION:
CRYSTAL CREEK 22.0
END DESCRIPTION:
XS GIS Cut Line= 3
      3858931.36     10083263.33      3858236.11     10082755.79
      3857585.84     10082512.46
#Sta/Elev= 30
  4139.2  133.99  4286.6  128.44  4336.8  121.63  4372.3  121.13  4378.8  119.12
  4401.6  119.12  4487.4  113.13  4508.2  111.67  4552.1  112.91    4594  109.18
  4614.8   112.3  4644.2  113.09  4778.7  112.41  4858.3  109.08    4874  108.53
    4916  104.37  4930.7   99.93  4936.9  102.24  4945.4   98.65  4973.2   94.01
  5026.4   94.01  5027.6   94.71  5031.6  106.83  5040.8  108.83  5066.9  111.35
  5158.3  107.36  5197.3  112.34  5288.1  114.17  5415.5  122.32  5694.3  124.31
#Mann= 8 ,-1 , 0
  4139.2     .11       0  4487.4     .17       0  4778.7     .15       0
  4858.3     .11       0    4874     .09       0  5040.8     .15       0
  5066.9     .17       0  5415.5     .11       0
Bank Sta=4874,5040.8
XS Rating Curve= 0 ,0
Exp/Cntr=0.3,0.1

Type RM Length L Ch R = 1 ,10500   ,500,500,500
BEGIN DESCRIPTION:
CRYSTAL CREEK 21.0
END DESCRIPTION:
XS GIS Cut Line= 3
      3859043.15      10082094.6      3858343.53     10082301.95
      3857616.29     10082395.28
#Sta/Elev= 30
  4270.3  139.04  4432.3  132.44  4589.1  115.74  4659.6  108.54  4664.8  106.89
  4682.6  107.83  4693.2  104.61  4703.5   101.6  4745.2  108.54  4797.2  110.79
  4836.2  110.39  4901.6  112.91  4946.3   110.6  4964.2  104.17  4974.4   99.14
  4979.1   94.62  5032.4   94.62  5036.7   96.88  5111.3  103.94  5126.7  105.15
  5207.9  102.93  5270.5  104.19  5318.3  100.37    5345  102.62  5350.1  101.75
  5388.8  111.97  5479.6  119.45  5579.5  123.63    5651  125.57  5733.2  125.19
#Mann= 8 ,-1 , 0
  4270.3     .17       0  4589.1     .11       0  4693.2     .15       0
  4797.2     .11       0  4964.2     .06       0  5111.3     .15       0
  5207.9     .17       0  5579.5     .11       0
Bank Sta=4964.2,5111.3
XS Rating Curve= 0 ,0
Exp/Cntr=0.3,0.1

Type RM Length L Ch R = 1 ,10000   ,500,500,500
BEGIN DESCRIPTION:
CRYSTAL CREEK 20.0
END DESCRIPTION:
XS GIS Cut Line= 3
      3858859.83     10081651.28      3858236.71     10081863.58
      3857622.75     10082176.06
#Sta/Elev= 30
  4341.7  135.82  4534.3  129.75  4650.2  120.82  4713.5  112.69  4755.1  109.56
    4872  106.29  4903.7  107.23  4917.1  105.53  4943.2   96.56  4974.5   95.86
  4977.6   93.83  5032.2   93.83  5049.4  100.21    5055    99.2    5066  102.66
  5071.6  101.11  5077.3  104.92  5088.3  107.86  5090.3  107.57  5110.5  106.31
  5132.8  108.65    5167  109.11  5177.2   107.8    5200  107.92  5294.1  109.87
    5369  116.64  5427.5  117.23  5466.4  121.37  5533.2  124.98  5688.9  124.74
#Mann= 7 ,-1 , 0
  4341.7     .17       0  4534.3     .11       0  4903.7     .09       0
  5088.3     .11       0  5090.3     .17       0  5177.2     .15       0
    5200     .17       0
Bank Sta=4903.7,5088.3
XS Rating Curve= 0 ,0
Exp/Cntr=0.3,0.1

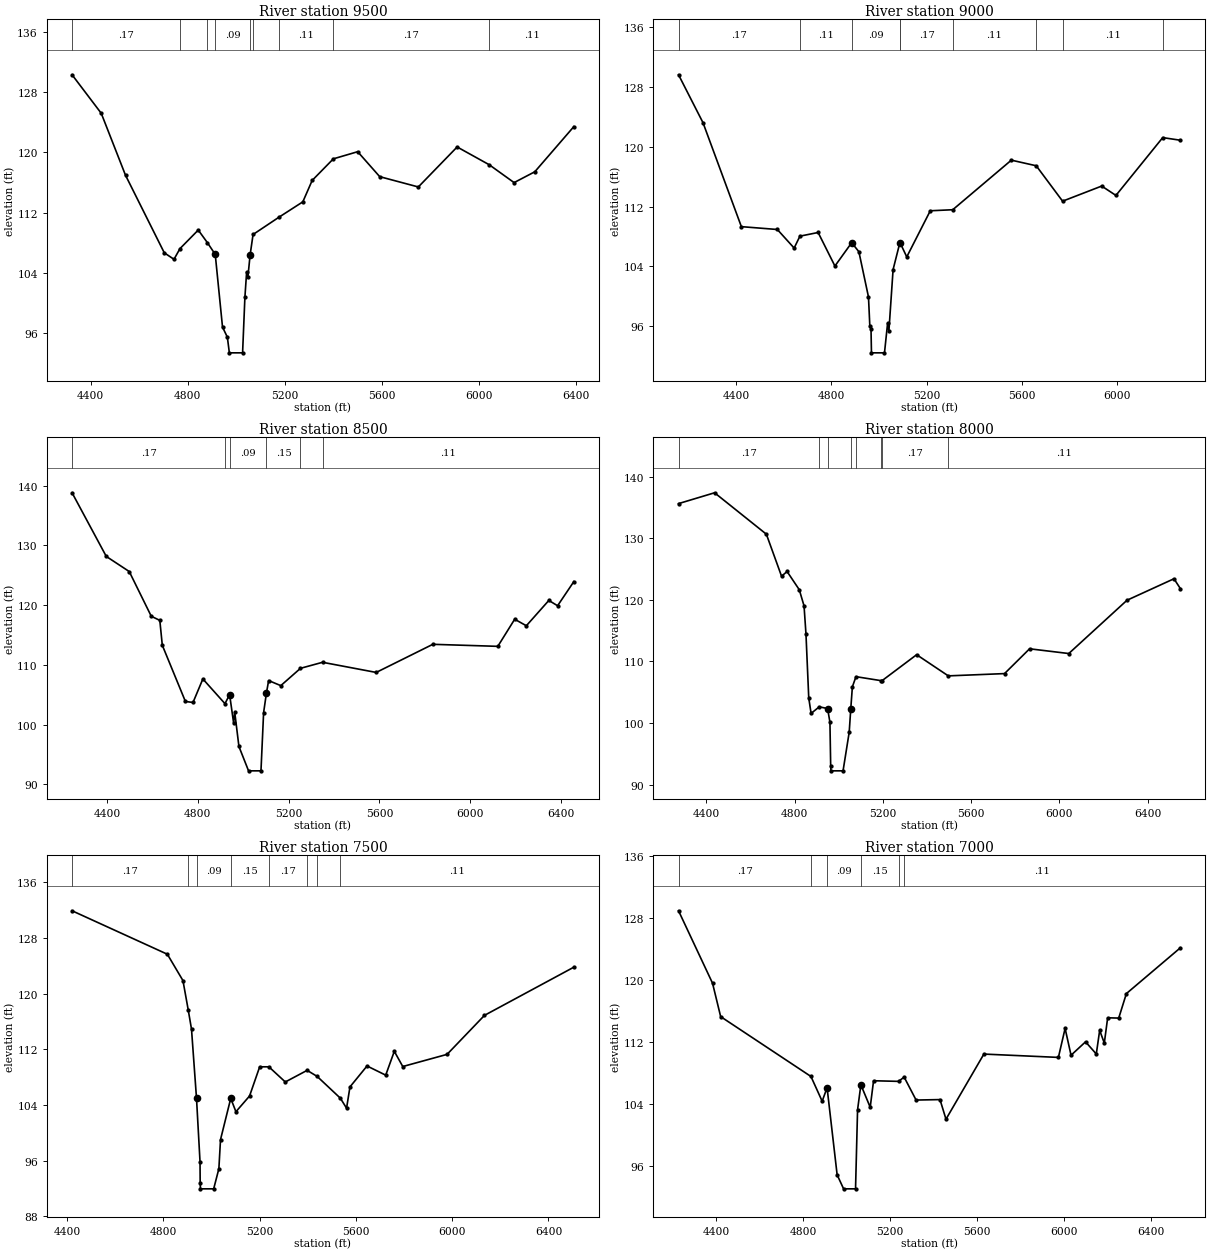
Type RM Length L Ch R = 1 ,9500    ,500,500,500
BEGIN DESCRIPTION:
CRYSTAL CREEK 19.0
END DESCRIPTION:
XS GIS Cut Line= 3
      3858818.17     10081375.23      3858141.73     10081390.18
      3856836.94     10081878.01
#Sta/Elev= 30
  4323.4  130.33  4443.7  125.21  4543.8  116.97  4703.8  106.65  4743.8  105.79
  4768.4  107.21  4843.8  109.68  4881.6     108  4913.9  106.44  4943.9   96.78
  4963.9   95.43  4972.1   93.35  5026.7   93.35  5036.2  100.71  5043.4  104.11
  5048.8   103.5  5057.6106.3348  5069.9  109.09  5176.8  111.39  5275.1  113.43
  5313.7  116.28    5401  119.15  5501.4   120.1  5592.3  116.78  5751.5  115.41
  5911.6  120.73  6044.2  118.36  6146.5  115.99  6231.9  117.43    6393  123.44
#Mann= 9 ,-1 , 0
  4323.4     .17       0  4768.4     .15       0  4881.6     .11       0
  4913.9     .09       0  5057.6     .15       0  5069.9     .17       0
  5176.8     .11       0    5401     .17       0  6044.2     .11       0
Bank Sta=4913.9,5057.6
XS Rating Curve= 0 ,0
Exp/Cntr=0.3,0.1

Type RM Length L Ch R = 1 ,9000    ,500,500,500
BEGIN DESCRIPTION:
CRYSTAL CREEK 18.0
END DESCRIPTION:
XS GIS Cut Line= 3
      3859109.87     10080812.73      3858273.76     10080910.52
      3857121.56     10081431.95
#Sta/Elev= 30
  4158.2  129.59  4260.9  123.19    4422  109.31    4573  108.93  4643.5  106.45
  4667.7  108.04  4744.2  108.53  4814.7  104.05  4885.1  107.17  4915.3  105.96
  4955.6   99.92  4961.2   96.06  4966.2   95.68  4968.1   92.46  5022.8   92.46
  5035.8    96.4  5041.3   95.38  5058.9  103.58  5087.5  107.19    5089  107.11
  5116.3  105.27    5215  111.43  5309.4  111.57  5555.3  118.19  5659.8  117.44
  5770.5  112.71  5934.6  114.73  5994.4  113.48  6190.8   121.2  6264.7  120.85
#Mann= 9 ,-1 , 0
  4158.2     .17       0  4667.7     .11       0  4885.1     .09       0
  5087.5     .11       0    5089     .17       0  5309.4     .11       0
  5659.8     .17       0  5770.5     .11       0  6190.8     .17       0
Bank Sta=4885.1,5087.5
XS Rating Curve= 0 ,0
Exp/Cntr=0.3,0.1

Type RM Length L Ch R = 1 ,8500    ,500,500,500
BEGIN DESCRIPTION:
CRYSTAL CREEK 17.0
END DESCRIPTION:
XS GIS Cut Line= 3
      3858984.88     10080250.23      3858249.58     10080414.83
      3856927.81     10081026.17
#Sta/Elev= 30
  4246.5  138.82  4397.2  128.16  4498.3  125.63  4595.3  118.14  4632.9  117.45
  4643.9  113.28  4745.6  103.87  4779.1   103.7  4822.5  107.64  4919.9   103.5
  4940.3  105.02  4957.8  100.31  4962.9  102.05  4981.3   96.33  5023.7   92.25
  5078.4   92.25    5090     102  5102.4  105.27  5112.1  107.37  5165.7  106.52
  5252.4  109.42  5349.6  110.43  5585.8  108.73  5835.2  113.44  6121.4   113.1
  6195.7  117.64  6247.1  116.55  6346.1  120.79  6384.6   119.9  6456.3  123.95
#Mann= 6 ,-1 , 0
  4246.5     .17       0  4919.9     .15       0  4940.3     .09       0
  5102.4     .15       0  5252.4     .17       0  5349.6     .11       0
Bank Sta=4940.3,5102.4
XS Rating Curve= 0 ,0
Exp/Cntr=0.3,0.1

Type RM Length L Ch R = 1 ,8000    ,500,500,500
BEGIN DESCRIPTION:
CRYSTAL CREEK 16.0
END DESCRIPTION:
XS GIS Cut Line= 3
      3858760.96     10079692.92      3858080.32     10079946.95
      3856872.08     10080915.46
#Sta/Elev= 30
  4273.5  135.64  4436.9   137.4  4671.7  130.67  4740.6  123.84  4765.6  124.61
  4820.9  121.65  4842.5  119.03  4851.2   114.5  4863.9  104.05  4874.5  101.55
  4911.5  102.62  4949.3  102.34  4959.9  100.12  4963.3   93.02  4964.6   92.22
  5019.4   92.22  5047.3    98.5  5054.4  102.32  5061.7  105.88    5078  107.52
  5192.4  106.87  5196.2  106.87    5353  111.09  5496.5  107.65  5751.5  108.02
  5865.1  112.05  6042.8  111.28  6306.8  119.94  6519.7  123.43  6548.5  121.84
#Mann= 8 ,-1 , 0
  4273.5     .17       0  4911.5     .15       0  4949.3     .09       0
  5054.4     .15       0    5078     .17       0  5192.4     .15       0
  5196.2     .17       0  5496.5     .11       0
Bank Sta=4949.3,5054.4
XS Rating Curve= 0 ,0
Exp/Cntr=0.3,0.1

Type RM Length L Ch R = 1 ,7500    ,500,500,500
BEGIN DESCRIPTION:
CRYSTAL CREEK 15.0
END DESCRIPTION:
XS GIS Cut Line= 3
      3858229.64     10079239.83      3857763.83     10079583.38
      3856667.16     10080614.82
#Sta/Elev= 30
  4421.2  131.93    4817  125.68  4881.8  121.89  4903.4  117.73  4917.3  114.91
  4938.1  104.95  4952.7   95.83  4953.3   92.74  4954.6   91.94  5009.4   91.94
    5031   94.84  5037.8   99.02  5080.3  104.95  5101.8  103.03  5158.4  105.29
  5200.5  109.49  5238.7  109.49  5306.9  107.31  5397.6  108.98  5439.2  108.11
  5535.5  104.98  5561.4  103.54  5575.5   106.6  5646.4  109.61    5724  108.29
  5759.7  111.72  5794.8  109.53  5978.9  111.28  6134.3  116.89  6505.5  123.82
#Mann= 8 ,-1 , 0
  4421.2     .17       0  4903.4     .15       0  4938.1     .09       0
  5080.3     .15       0  5238.7     .17       0  5397.6     .11       0
  5439.2     .17       0  5535.5     .11       0
Bank Sta=4938.1,5080.3
XS Rating Curve= 0 ,0
Exp/Cntr=0.3,0.1

Type RM Length L Ch R = 1 ,7000    ,500,500,500
BEGIN DESCRIPTION:
CRYSTAL CREEK 14.0
END DESCRIPTION:
XS GIS Cut Line= 3
      3858068.24     10078857.85      3857400.76     10079244.74
      3856599.44     10080552.34
#Sta/Elev= 30
  4228.5  128.96  4384.7  119.62    4422  115.31  4836.8  107.59  4888.3   104.4
  4910.9  106.14  4957.1    94.9  4986.8    93.1  5041.6    93.1  5050.9  103.28
  5066.1  106.52    5109  103.62  5124.4  107.04  5239.1  106.96  5264.9  107.51
  5319.8  104.55  5429.6  104.61  5457.1  102.08  5631.2  110.48  5973.5  110.05
  6004.3  113.79  6031.6  110.33  6098.2  112.06  6147.6  110.49  6163.1  113.54
  6184.4   111.9  6199.8  115.16  6250.6  115.12  6285.8  118.28  6533.6  124.18
#Mann= 6 ,-1 , 0
  4228.5     .17       0  4836.8     .15       0  4910.9     .09       0
  5066.1     .15       0  5239.1     .17       0  5264.9     .11       0
Bank Sta=4910.9,5066.1
XS Rating Curve= 0 ,0
Exp/Cntr=0.3,0.1

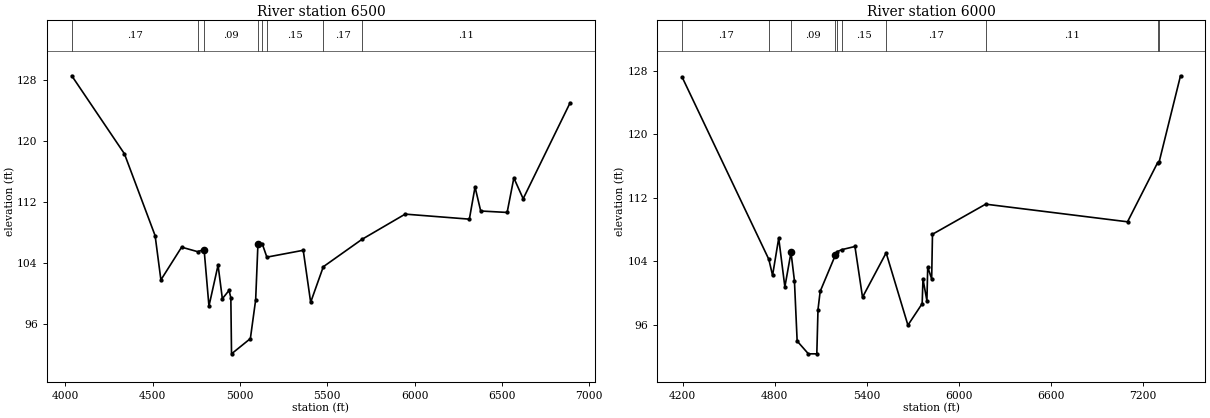
Type RM Length L Ch R = 1 ,6500    ,500,500,500
BEGIN DESCRIPTION:
CRYSTAL CREEK 13.0
END DESCRIPTION:
XS GIS Cut Line= 3
      3858120.28     10078519.33       3857198.5     10078795.26
      3856480.96     10080544.41
#Sta/Elev= 30
  4037.8  128.61  4339.1  118.37    4515  107.61  4548.1   101.8  4666.6   106.1
  4758.4  105.51  4795.4  105.79  4823.2   98.36  4875.4  103.74  4899.9   99.33
  4938.2  100.42  4948.5   99.46  4952.4   92.09  5060.3   94.09  5090.6   99.18
  5103.6  106.48    5128  106.56  5154.8  104.79    5363  105.69  5405.5   98.86
  5477.9  103.53  5698.8  107.12  5946.6  110.44  6314.1  109.78  6346.6     114
    6379  110.85  6530.3  110.66  6568.8  115.19  6622.2  112.46  6890.6  125.05
#Mann= 8 ,-1 , 0
  4037.8     .17       0  4758.4     .15       0  4795.4     .09       0
  5103.6     .15       0    5128     .17       0  5154.8     .15       0
  5477.9     .17       0  5698.8     .11       0
Bank Sta=4795.4,5103.6
XS Rating Curve= 0 ,0
Exp/Cntr=0.3,0.1

Type RM Length L Ch R = 1 ,6000    ,500,500,500
BEGIN DESCRIPTION:
CRYSTAL CREEK 12.0
END DESCRIPTION:
XS GIS Cut Line= 4
      3858165.84     10078280.61       3857365.4     10078330.62
      3857035.66     10078686.64      3856383.99     10080536.76
#Sta/Elev= 30
    4198  127.17  4762.8  104.24  4787.1  102.22  4827.2  106.91  4867.3  100.77
  4907.4  105.12  4929.7  101.54  4947.4   93.95  5020.7   92.34  5075.6   92.34
  5083.3   97.91  5097.4   100.2  5196.7  104.78  5207.9   105.2  5238.1  105.46
  5324.2  105.86  5373.6   99.47  5527.6  105.06  5669.6   95.95  5762.5   98.66
  5767.8  101.76  5793.4   99.03  5798.7  103.27  5824.4  101.78  5829.7   107.4
  6176.5  111.19  7101.5  108.97  7296.9  116.39  7308.2  116.56  7446.8  127.36
#Mann= 10 ,-1 , 0
    4198     .17       0  4762.8     .11       0  4907.4     .09       0
  5196.7     .15       0  5207.9     .17       0  5238.1     .15       0
  5527.6     .17       0  6176.5     .11       0  7296.9     .17       0
  7308.2     .11       0
Bank Sta=4907.4,5196.7
XS Rating Curve= 0 ,0
Exp/Cntr=0.3,0.1