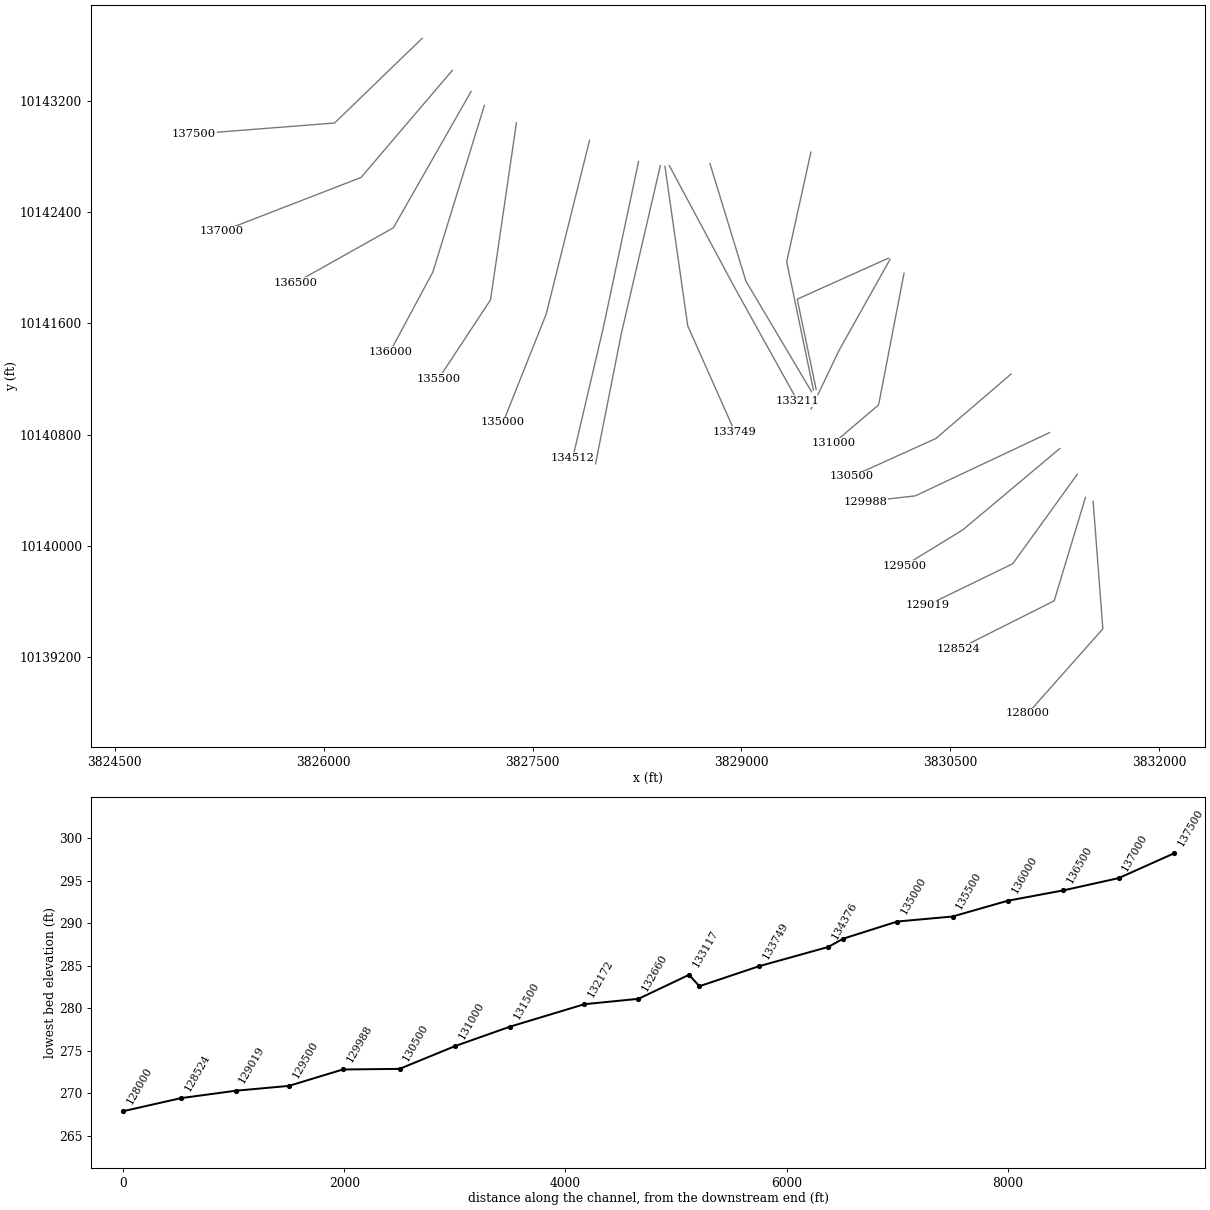
HEC-RAS study CRYSTAL CREEK.prj: CRYSTAL CREEK Base Level Engineering

--- CRYSTAL CREEK.g10 (geometry) --- (continued)

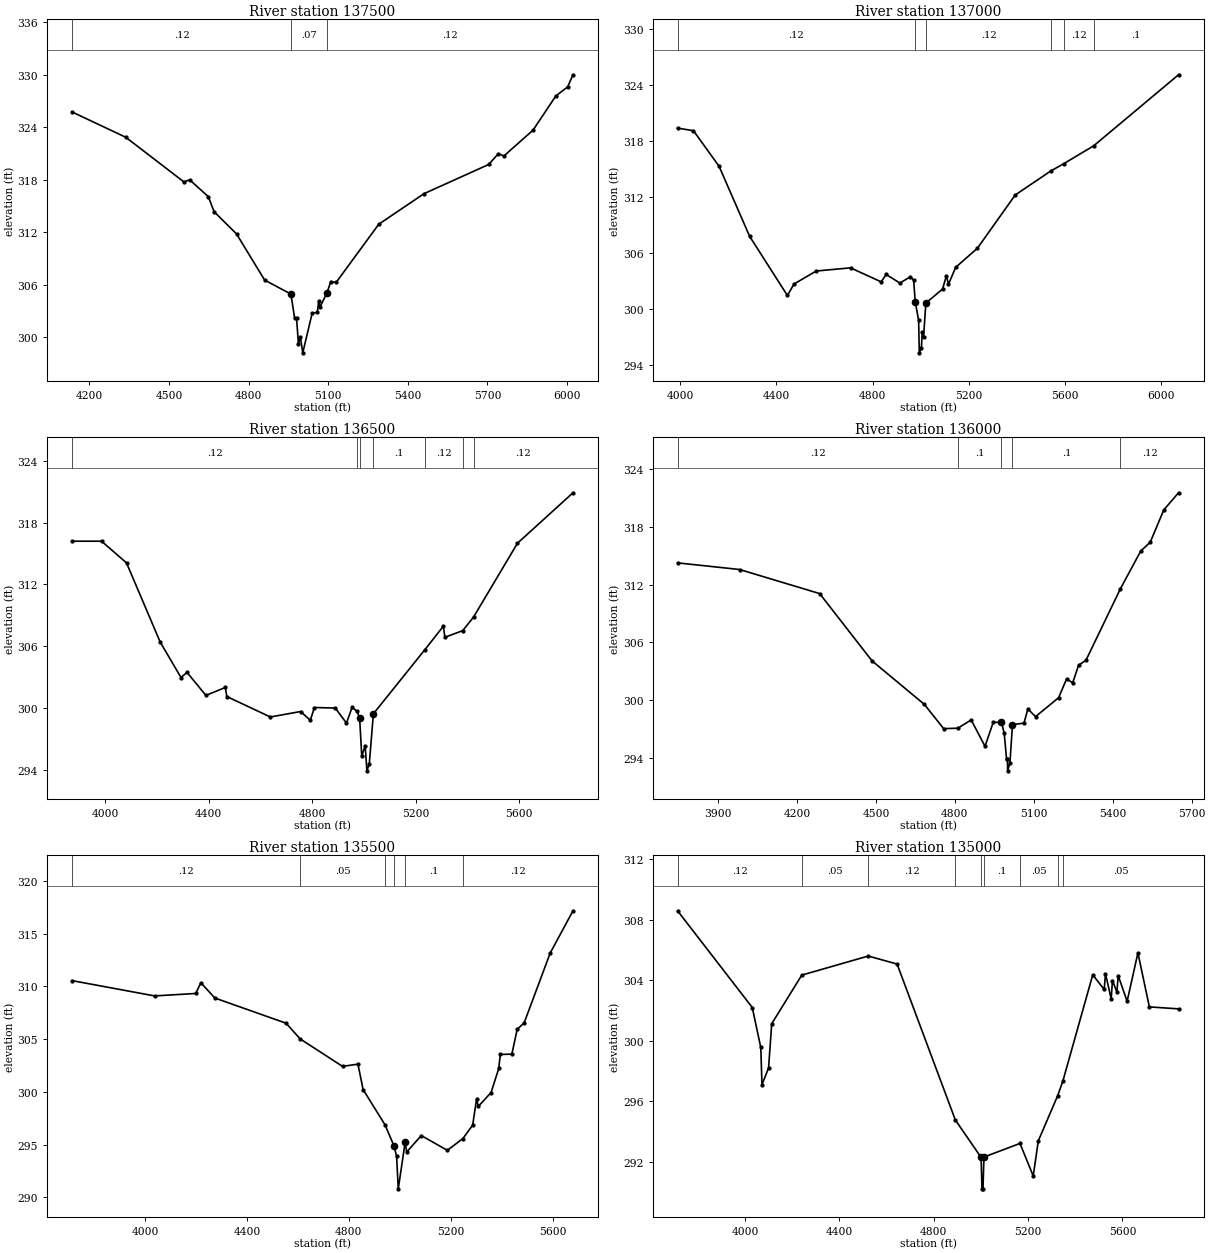
Type RM Length L Ch R = 1 ,137500  ,500,500,500
BEGIN DESCRIPTION:
CRYSTAL CREEK 269.0
END DESCRIPTION:
XS GIS Cut Line= 3
      3826706.62     10143649.01      3826077.58     10143040.28
      3825067.84     10142961.07
#Sta/Elev= 30
  4134.3  325.77  4337.1  322.87  4556.3  317.76  4577.6  318.01  4648.1  316.08
  4669.5  314.37  4754.4  311.82  4860.3  306.54  4959.4  304.94  4973.5  302.15
  4980.7  302.19  4987.7   299.2  4994.9  300.07    5004  298.22  5039.5  302.76
    5059  302.84    5064  304.13  5069.6  303.49    5095 305.068  5109.7  306.37
  5129.8  306.27  5290.2  312.92  5460.8  316.42  5704.7  319.76  5741.6  321.01
  5761.7  320.72    5872  323.69  5957.9   327.6  6002.4  328.63  6022.5  330.02
#Mann= 3 , 0 , 0
  4134.3     .12       0  4959.4     .07       0    5095     .12       0
Bank Sta=4959.4,5095
XS Rating Curve= 0 ,0
Exp/Cntr=0.3,0.1

Type RM Length L Ch R = 1 ,137000  ,500,500,500
BEGIN DESCRIPTION:
CRYSTAL CREEK 268.0
END DESCRIPTION:
XS GIS Cut Line= 3
      3826923.66     10143419.01       3826267.9     10142648.87
      3825267.86     10142261.07
#Sta/Elev= 30
  3988.5  319.37  4054.7  319.09  4161.3  315.28  4288.6  307.77  4445.5  301.45
  4473.1  302.68  4565.4  304.07  4708.2  304.41  4835.5  302.91  4856.4   303.7
  4913.5  302.78  4956.3  303.44  4970.6   303.1  4977.2   300.8  4991.5  298.78
  4994.2  295.31  5002.7  295.81  5006.6  297.56  5011.9  296.99  5021.5  300.63
    5091  302.14  5107.3  303.58  5115.5  302.64  5145.4  304.46    5236  306.51
  5393.3  312.21    5543  314.81  5595.3  315.56  5720.1  317.48  6072.6  325.08
#Mann= 6 ,-1 , 0
  3988.5     .12       0  4977.2     .07       0  5021.5     .12       0
    5543      .1       0  5595.3     .12       0  5720.1      .1       0
Bank Sta=4977.2,5021.5
XS Rating Curve= 0 ,0
Exp/Cntr=0.3,0.1

Type RM Length L Ch R = 1 ,136500  ,500,500,500
BEGIN DESCRIPTION:
CRYSTAL CREEK 267.0
END DESCRIPTION:
XS GIS Cut Line= 3
      3827058.22      10143267.1      3826500.02     10142287.01
      3825795.23     10141891.25
#Sta/Elev= 30
  3872.1  316.21  3986.2  316.21  4082.7   314.1  4212.8   306.4  4293.3  302.95
  4316.4  303.45  4389.6  301.21  4464.6  301.98  4470.3   301.1  4638.6  299.11
  4755.6  299.64  4793.1  298.79  4808.9  300.03  4889.6  299.98  4932.8  298.51
  4954.5  300.04    4974  299.66  4983.8  298.99  4991.9   295.3  5005.1  296.31
  5011.9  293.87    5021  294.54  5036.9  299.42  5235.7  305.65  5307.3  307.94
  5313.1  306.86  5382.2  307.51  5424.1  308.83  5593.7  316.01  5808.3  320.92
#Mann= 7 ,-1 , 0
  3872.1     .12       0    4974      .1       0  4983.8     .07       0
  5036.9      .1       0  5235.7     .12       0  5382.2      .1       0
  5424.1     .12       0
Bank Sta=4983.8,5036.9
XS Rating Curve= 0 ,0
Exp/Cntr=0.3,0.1

Type RM Length L Ch R = 1 ,136000  ,500,500,500
BEGIN DESCRIPTION:
CRYSTAL CREEK 266.0
END DESCRIPTION:
XS GIS Cut Line= 3
       3827153.7     10143167.29       3826783.7     10141969.43
      3826476.61     10141396.43
#Sta/Elev= 30
  3746.3  314.26  3982.1  313.57  4286.3  311.07  4485.4  304.08  4684.3  299.56
  4757.6  297.04  4811.5  297.09  4862.2  297.95  4914.6  295.21  4945.9  297.69
  4977.3  297.72  4987.8  296.54  4996.5  293.92    5000  293.92  5000.7  292.66
  5009.5  293.48  5019.1  297.45  5062.9  297.62  5077.6  299.09  5106.8  298.29
  5194.5  300.26    5225  302.22  5247.7  301.79  5270.4  303.63  5298.5  304.15
  5429.3  311.57  5506.4  315.48  5542.7  316.41  5594.2  319.76  5650.1  321.54
#Mann= 5 ,-1 , 0
  3746.3     .12       0  4811.5      .1       0  4977.3     .07       0
  5019.1      .1       0  5429.3     .12       0
Bank Sta=4977.3,5019.1
XS Rating Curve= 0 ,0
Exp/Cntr=0.3,0.1

Type RM Length L Ch R = 1 ,135500  ,500,500,500
BEGIN DESCRIPTION:
CRYSTAL CREEK 265.0
END DESCRIPTION:
XS GIS Cut Line= 3
      3827383.74     10143041.41      3827197.82     10141768.72
      3826823.85     10141201.15
#Sta/Elev= 30
  3713.8  310.54  4037.5  309.09  4199.2  309.32  4219.5  310.34  4274.2  308.89
    4554   306.5  4609.3  305.01  4775.3  302.41  4835.9  302.62  4856.1  300.21
  4942.6  296.85  4977.4  294.86  4987.5   293.9  4994.1   290.8  5021.1  295.22
  5027.2  294.29  5084.4  295.85  5186.8  294.45  5247.8  295.57  5286.1  296.84
  5301.2  299.29  5308.5  298.62  5358.4  299.93  5388.5  302.22  5394.5  303.54
  5439.8  303.57  5460.8  305.92  5488.2  306.54  5590.3  313.15  5679.7  317.16
#Mann= 6 ,-1 , 0
  3713.8     .12       0  4609.3     .05       0  4942.6      .1       0
  4977.4     .07       0  5021.1      .1       0  5247.8     .12       0
Bank Sta=4977.4,5021.1
XS Rating Curve= 0 ,0
Exp/Cntr=0.3,0.1

Type RM Length L Ch R = 1 ,135000  ,488,488,488
BEGIN DESCRIPTION:
CRYSTAL CREEK 264.0
END DESCRIPTION:
XS GIS Cut Line= 3
      3827908.91     10142915.53      3827597.85      10141667.1
      3827288.24     10140888.61
#Sta/Elev= 30
  3713.4  308.58  4030.2  302.19  4066.3  299.55  4071.4  297.09  4099.3  298.19
  4112.7  301.12  4240.2  304.33  4522.1  305.59  4644.4  305.06  4891.1  294.77
 5000.72 292.284  5004.3  290.21  5008.6  290.21  5012.7  292.31  5165.6  293.21
  5221.7  291.06  5243.2  293.38  5325.3  296.36  5347.6  297.34  5474.1  304.35
  5522.7  303.38  5528.1  304.43  5552.3  302.76  5557.7  303.97  5576.6  303.21
    5582   304.3  5619.9   302.6  5665.7   305.8  5714.2  302.23  5837.8   302.1
#Mann= 9 ,-1 , 0
  3713.4     .12       0  4240.2     .05       0  4522.1     .12       0
  4891.1      .1       0 5000.72     .07       0  5012.7      .1       0
  5165.6     .05       0  5325.3     .12       0  5347.6     .05       0
Bank Sta=5000.72,5012.7
XS Rating Curve= 0 ,0
Exp/Cntr=0.3,0.1

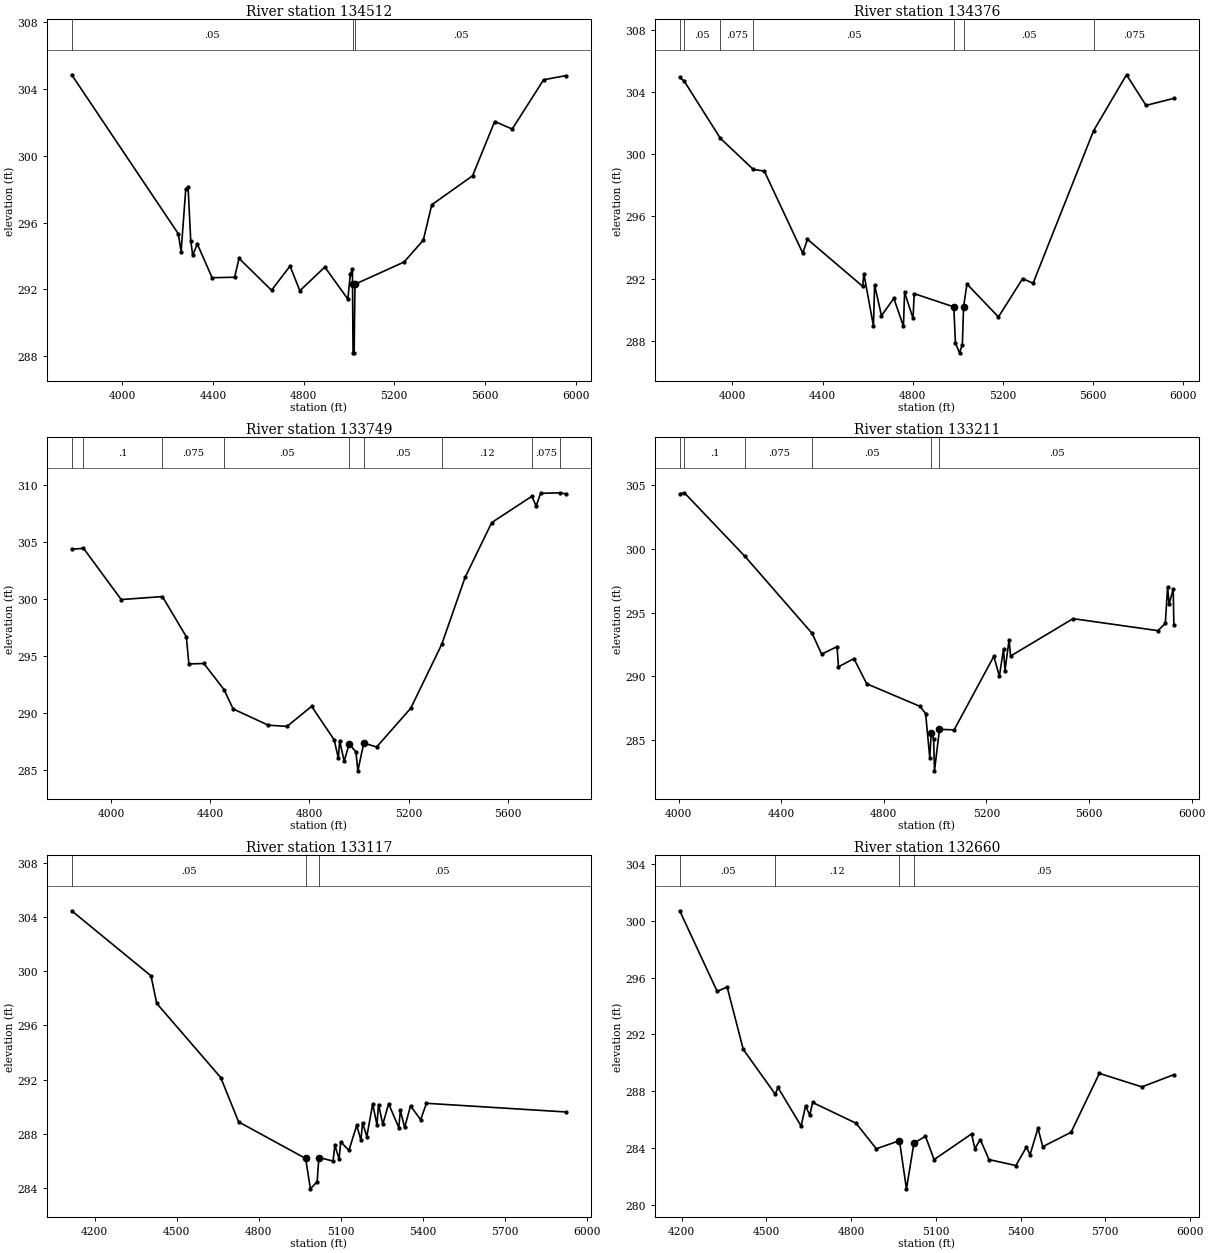
Type RM Length L Ch R = 1 ,134512  ,136,136,136
BEGIN DESCRIPTION:
CRYSTAL CREEK 263.0
END DESCRIPTION:
XS GIS Cut Line= 3
      3828261.06     10142763.29      3828007.38      10141567.2
      3827788.98     10140635.45
#Sta/Elev= 30
  3777.3  304.86  4247.7  295.33    4260  294.26  4280.5  298.02  4290.7  298.13
  4302.4  294.93  4311.1  294.05  4331.6  294.72  4396.6   292.7  4495.9  292.73
  4515.6  293.86  4658.7  291.95  4740.5   293.4  4783.7  291.92  4893.8  293.34
  4995.5  291.42  5006.3  292.91  5015.6  293.21 5016.06 292.308  5018.4   288.2
  5023.2   288.2  5026.8  292.31  5243.3  293.64  5328.2  294.95  5365.5  297.07
  5545.6  298.81  5643.1  302.06  5720.5  301.61  5858.8  304.56    5957  304.81
#Mann= 3 , 0 , 0
  3777.3     .05       0 5016.06     .03       0  5026.8     .05       0
Bank Sta=5016.06,5026.8
XS Rating Curve= 0 ,0
Exp/Cntr=0.3,0.1

Type RM Length L Ch R = 1 ,134376  ,627,627,627
BEGIN DESCRIPTION:
CRYSTAL CREEK 262.0
END DESCRIPTION:
XS GIS Cut Line= 3
       3828417.3     10142733.77      3828138.49     10141531.58
      3827952.02     10140589.66
#Sta/Elev= 30
  3765.9  304.95  3785.4  304.72  3945.9  301.04  4092.4  299.03  4141.5  298.92
  4312.2  293.64  4333.3  294.53  4578.4   291.5  4583.5  292.32  4626.2  288.95
  4631.3  291.59  4661.8  289.61  4716.7  290.73  4759.3  288.93  4764.5  291.11
    4802  289.44  4807.1  291.03  4982.9  290.18  4990.3  287.85  5008.3  287.22
  5020.9  287.74 5026.37 290.177  5041.3  291.65  5181.2  289.53  5288.8     292
  5334.9   291.7  5603.7  301.52  5749.9  305.12  5836.4  303.15  5960.2   303.6
#Mann= 7 ,-1 , 0
  3765.9    .075       0  3785.4     .05       0  3945.9    .075       0
  4092.4     .05       0  4982.9     .05       0 5026.37     .05       0
  5603.7    .075       0
Bank Sta=4982.9,5026.37
XS Rating Curve= 0 ,0
Exp/Cntr=0.3,0.1

Type RM Length L Ch R = 1 ,133749  ,538,538,538
BEGIN DESCRIPTION:
CRYSTAL CREEK 261.0
END DESCRIPTION:
XS GIS Cut Line= 3
      3828450.61     10142728.69      3828614.32     10141582.12
      3828952.79     10140819.78
#Sta/Elev= 30
  3841.8  304.35  3889.4  304.44  4041.4  299.95  4207.6  300.21  4304.1  296.69
  4314.2  294.31  4374.8  294.35  4456.1  292.06  4492.7  290.37  4634.1  288.95
  4709.9  288.84  4809.1   290.6    4900  287.67    4917  286.04  4922.1  287.59
  4940.4   285.8  4960.7  287.31  4987.8   286.6  4995.6  284.95  5019.3  287.38
  5071.3  287.04    5209  290.44  5333.8  296.03  5427.9  301.89  5535.2  306.69
  5696.8  308.99  5714.4  308.14  5732.2  309.25  5811.5   309.3  5834.1   309.2
#Mann= 9 ,-1 , 0
  3841.8    .075       0  3889.4      .1       0  4207.6    .075       0
  4456.1     .05       0  4960.7     .03       0  5019.3     .05       0
  5333.8     .12       0  5696.8    .075       0  5811.5     .05       0
Bank Sta=4960.7,5019.3
XS Rating Curve= 0 ,0
Exp/Cntr=0.3,0.1

Type RM Length L Ch R = 1 ,133211  ,94,94,94
BEGIN DESCRIPTION:
Mapping XS acd5d741
END DESCRIPTION:
XS GIS Cut Line= 3
      3828481.87     10142733.84      3828951.77     10141855.88
      3829403.09     10141041.94
#Sta/Elev= 30
  4004.2   304.3  4022.3  304.38    4259  299.39  4520.6  293.36  4557.4  291.74
  4617.5  292.33  4623.2  290.75  4683.3  291.39  4733.2  289.42  4940.9  287.65
  4962.8  287.09  4979.1  283.63  4984.8  285.58  4994.1  285.13  4997.4   282.6
  5016.9  285.85  5074.1  285.81  5228.8  291.57  5250.5  290.01  5266.5  292.14
  5272.3  290.44  5288.3  292.88    5294  291.59  5537.8  294.52  5868.6  293.58
  5897.4  294.15  5906.3     297  5912.1  295.65  5928.1  296.85  5930.7     294
#Mann= 6 ,-1 , 0
  4004.2    .075       0  4022.3      .1       0    4259    .075       0
  4520.6     .05       0  4984.8     .07       0  5016.9     .05       0
Bank Sta=4984.8,5016.9
XS Rating Curve= 0 ,0
Exp/Cntr=0.3,0.1

Type RM Length L Ch R = 1 ,133117  ,457,457,457
BEGIN DESCRIPTION:
CRYSTAL CREEK 260.0
END DESCRIPTION:
XS GIS Cut Line= 3
      3828773.64     10142748.53       3829032.5     10141902.86
      3829503.44     10141108.46
#Sta/Elev= 30
  4115.6  304.45  4405.8  299.65  4426.7  297.62  4660.8  292.15  4726.3  288.88
  4971.4  286.18    4989  283.94  5013.7  284.47  5019.9  286.25  5071.8  285.99
  5078.4  287.15    5094  286.14  5099.8   287.4    5130  286.78  5158.3  288.62
  5173.9  287.54  5179.7  288.82  5195.3   287.8  5216.8  290.19  5232.4  288.67
  5238.2  290.16  5253.8   288.7  5275.2  290.22  5312.3  288.45  5318.1  289.72
  5333.7  288.47  5355.2  290.06  5392.2  289.04  5413.6  290.25  5923.5  289.61
#Mann= 3 , 0 , 0
  4115.6     .05       0  4971.4     .07       0  5019.9     .05       0
Bank Sta=4971.4,5019.9
XS Rating Curve= 0 ,0
Exp/Cntr=0.3,0.1

Type RM Length L Ch R = 1 ,132660  ,488,488,488
BEGIN DESCRIPTION:
CRYSTAL CREEK 259.0
END DESCRIPTION:
XS GIS Cut Line= 3
      3829498.82     10142830.65      3829325.18     10142042.86
      3829517.05      10141120.1
#Sta/Elev= 30
  4193.3   300.7    4326  295.02  4361.1  295.34  4418.2  290.94  4531.7  287.78
    4541  288.26    4623  285.54  4638.7  286.96  4653.7  286.31  4663.9   287.2
  4817.5  285.74  4889.2  283.94  4971.1  284.51  4995.9  281.12  5022.3  284.34
  5063.1  284.82  5093.8  283.18  5226.5  284.99    5238  283.95  5257.2  284.59
  5288.1  283.18  5383.2  282.76  5420.6  284.06  5433.3  283.52  5461.5  285.39
  5478.3  284.09  5578.5   285.1  5678.7  289.25  5829.2   288.3  5942.5  289.16
#Mann= 4 ,-1 , 0
  4193.3     .05       0  4531.7     .12       0  4971.1     .07       0
  5022.3     .05       0
Bank Sta=4971.1,5022.3
XS Rating Curve= 0 ,0
Exp/Cntr=0.3,0.1

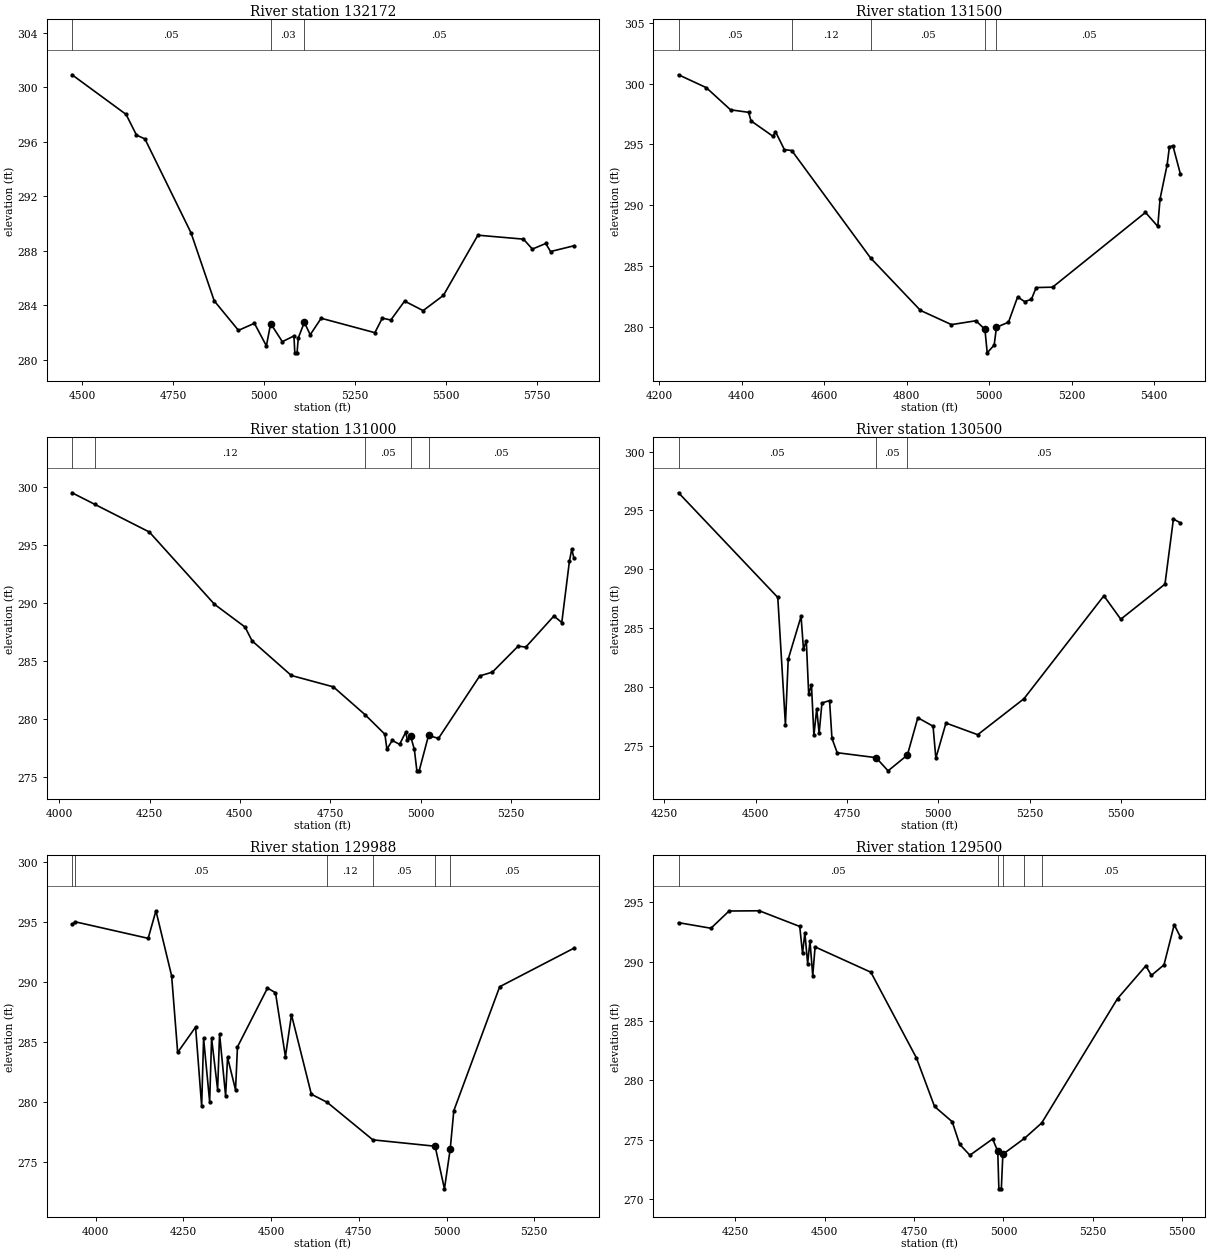
Type RM Length L Ch R = 1 ,132172  ,672,672,672
BEGIN DESCRIPTION:
Mapping XS 53fef309
END DESCRIPTION:
XS GIS Cut Line= 3
      3830055.23     10142068.48      3829400.73     10141773.78
       3829536.4     10141125.31
#Sta/Elev= 30
  4472.1  300.91  4620.7     298  4649.3  296.48  4672.5   296.2  4799.2  289.31
  4863.1  284.31  4929.8  282.14  4973.7  282.66  5006.6     281  5018.4  282.64
  5050.5  281.31  5082.4  281.73  5084.8  280.49    5091  280.49  5094.3  281.58
    5111  282.73  5127.2  281.82  5157.3  283.03    5305  281.97  5325.5  283.04
  5348.9   282.9  5386.8  284.29  5437.8  283.59  5493.6  284.71  5588.4  289.13
  5713.7  288.84  5738.3  288.11    5775  288.52  5788.3  287.93  5852.4  288.35
#Mann= 3 , 0 , 0
  4472.1     .05       0  5018.4     .03       0    5111     .05       0
Bank Sta=5018.4,5111
XS Rating Curve= 0 ,0
Exp/Cntr=0.3,0.1

Type RM Length L Ch R = 1 ,131500  ,500,500,500
BEGIN DESCRIPTION:
CRYSTAL CREEK 257.0
END DESCRIPTION:
XS GIS Cut Line= 3
      3830067.85     10142061.07      3829699.89     10141403.52
       3829500.2     10140984.81
#Sta/Elev= 30
  4246.5  300.72  4313.9  299.66  4372.6  297.84  4416.6  297.63  4422.3  296.93
  4475.7  295.66  4481.7  296.04  4503.4  294.56  4521.2  294.49  4712.5  285.65
  4833.4  281.34  4908.7  280.17  4968.1  280.49  4989.8  279.78  4995.4  277.85
  5012.3  278.49  5017.8  279.95    5047  280.37  5069.2  282.45  5085.9  282.07
  5102.4  282.24  5114.2  283.22    5154  283.25  5379.4   289.4  5409.2  288.25
  5414.7  290.51  5431.9  293.32  5437.4  294.79  5445.9  294.88  5463.9  292.58
#Mann= 5 ,-1 , 0
  4246.5     .05       0  4521.2     .12       0  4712.5     .05       0
  4989.8     .03       0  5017.8     .05       0
Bank Sta=4989.8,5017.8
XS Rating Curve= 0 ,0
Exp/Cntr=0.3,0.1

Type RM Length L Ch R = 1 ,131000  ,500,500,500
BEGIN DESCRIPTION:
CRYSTAL CREEK 256.0
END DESCRIPTION:
XS GIS Cut Line= 3
      3830167.86     10141961.11      3829985.29     10141014.25
      3829662.41     10140738.96
#Sta/Elev= 30
  4035.7  299.49  4098.2   298.5  4249.6  296.11  4429.8  289.89  4514.4  287.93
  4533.6  286.75  4642.4  283.76  4758.8  282.78    4847  280.37  4901.4   278.7
  4906.9  277.41  4921.8  278.17  4942.1  277.83  4958.7  278.86  4963.8  278.22
  4972.7  278.52  4982.9  277.39  4989.9  275.55  4996.2  275.55  5022.2   278.6
  5049.6  278.34  5163.8  283.72  5198.9  284.05  5270.3  286.29  5291.2   286.2
  5369.1  288.88  5390.9  288.32    5412  293.59  5418.5  294.64  5424.3  293.89
#Mann= 5 ,-1 , 0
  4035.7     .05       0  4098.2     .12       0    4847     .05       0
  4972.7     .05       0  5022.2     .05       0
Bank Sta=4972.7,5022.2
XS Rating Curve= 0 ,0
Exp/Cntr=0.3,0.1

Type RM Length L Ch R = 1 ,130500  ,512,512,512
BEGIN DESCRIPTION:
CRYSTAL CREEK 255.0
END DESCRIPTION:
XS GIS Cut Line= 3
       3830936.3     10141235.13      3830396.97     10140772.45
      3829793.96     10140499.04
#Sta/Elev= 30
  4289.4   296.5  4560.9  287.61  4581.8  276.81  4589.5  282.37  4624.6     286
  4631.2  283.21  4638.9  283.95  4645.4  279.42  4653.1  280.16  4659.7  275.89
  4667.4  278.15    4674  276.07  4681.7  278.64  4702.5  278.85  4709.1  275.64
  4723.4  274.42  4829.8     274  4862.6  272.88  4915.4  274.22    4944  277.39
  4985.7  276.67  4993.3  273.95    5021  276.94  5107.8  275.95  5234.2     279
    5453  287.75  5499.2  285.76  5620.1  288.74  5643.2  294.27  5662.1  293.95
#Mann= 3 , 0 , 0
  4289.4     .05       0  4829.8     .05       0  4915.4     .05       0
Bank Sta=4829.8,4915.4
XS Rating Curve= 0 ,0
Exp/Cntr=0.3,0.1

Type RM Length L Ch R = 1 ,129988  ,488,488,488
BEGIN DESCRIPTION:
CRYSTAL CREEK 254.0
END DESCRIPTION:
XS GIS Cut Line= 3
      3831214.13     10140815.03       3830248.5     10140359.69
      3829887.74     10140318.49
#Sta/Elev= 30
  3932.4  294.79    3942  294.99  4149.4  293.62  4171.5  295.91  4216.3   290.5
  4233.5  284.14  4284.6  286.25  4301.9  279.67  4307.4  285.31  4324.7  280.04
  4330.2  285.32  4347.4  281.05    4353  285.67  4370.2  280.53  4375.7  283.73
  4398.5  281.03    4404   284.6  4489.6  289.49  4512.4   289.1  4540.7  283.79
    4558  287.27  4614.6  280.67  4659.6     280    4790  276.88  4967.5  276.35
  4994.1  272.81  5010.7  276.14  5020.8   279.3  5151.6   289.6  5363.1   292.8
#Mann= 6 ,-1 , 0
  3932.4     .12       0    3942     .05       0  4659.6     .12       0
    4790     .05       0  4967.5     .05       0  5010.7     .05       0
Bank Sta=4967.5,5010.7
XS Rating Curve= 0 ,0
Exp/Cntr=0.3,0.1

Type RM Length L Ch R = 1 ,129500  ,481,481,481
BEGIN DESCRIPTION:
CRYSTAL CREEK 253.0
END DESCRIPTION:
XS GIS Cut Line= 3
      3831287.04     10140700.45       3830590.7       10140116.
      3830168.95     10139856.68
#Sta/Elev= 30
  4090.9  293.28  4181.6  292.81  4232.3  294.26  4316.9  294.28  4430.1  292.96
  4437.9  290.69  4444.4  292.42  4452.2  289.84  4458.7  291.72  4466.5  288.82
    4473  291.24  4629.1  289.11  4756.6   281.9  4807.3  277.81  4856.7  276.53
  4877.6  274.63  4906.2  273.71  4969.9  275.08  4984.2  274.04  4987.3  270.88
  4994.2  270.88  4998.5  273.79    5059  275.13  5107.1  276.42  5319.4  286.89
  5398.7  289.65  5414.1  288.84  5449.4  289.73    5478  293.11  5495.1  292.08
#Mann= 5 ,-1 , 0
  4090.9     .05       0  4984.2     .05       0  4998.5     .05       0
    5059    .075       0  5107.1     .05       0
Bank Sta=4984.2,4998.5
XS Rating Curve= 0 ,0
Exp/Cntr=0.3,0.1

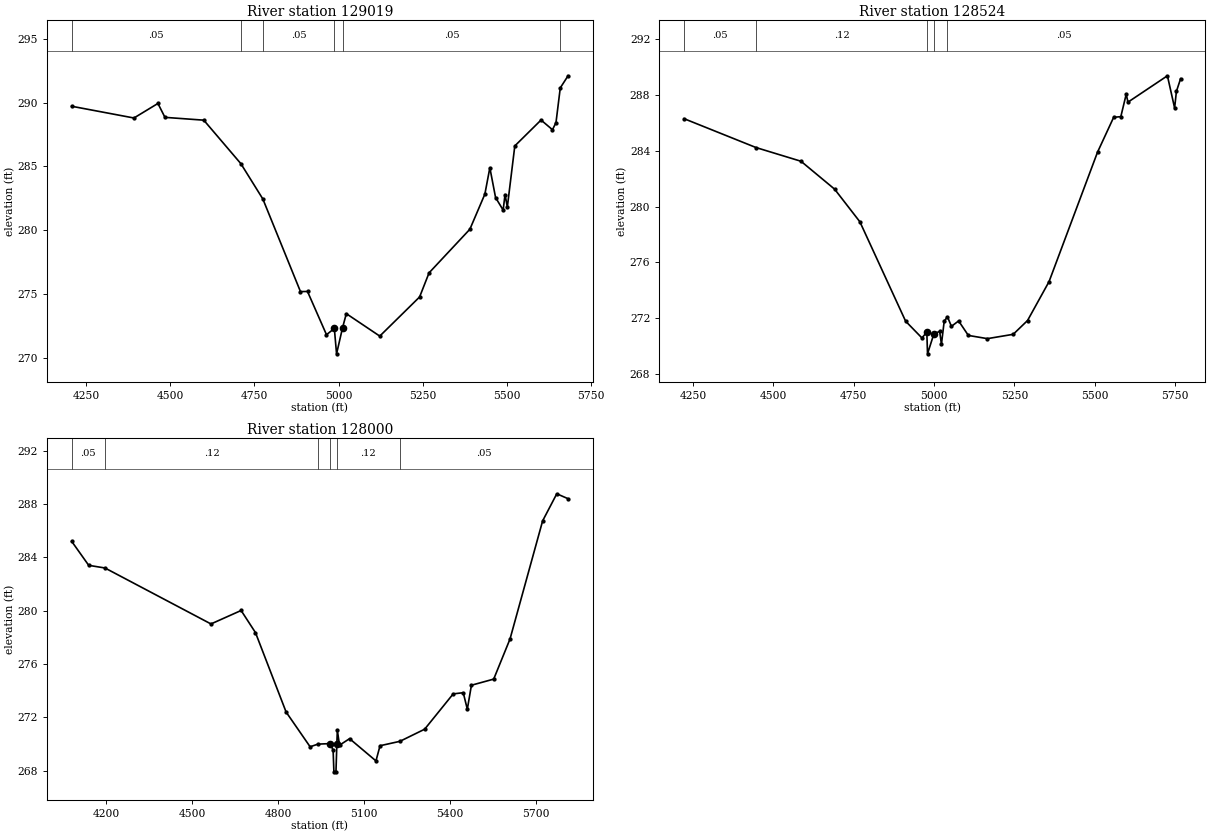
Type RM Length L Ch R = 1 ,129019  ,495,495,495
BEGIN DESCRIPTION:
CRYSTAL CREEK 252.0
END DESCRIPTION:
XS GIS Cut Line= 3
        3831412.     10140514.64      3830948.26      10139871.5
      3830335.61     10139573.68
#Sta/Elev= 30
  4207.1  289.72    4392   288.8  4463.2  289.94  4484.1  288.85  4599.4  288.63
  4709.5  285.22  4774.8  282.45  4886.5  275.19  4907.4   275.2  4963.8  271.81
  4987.1   272.3  4993.7  270.31 5011.66 272.374  5022.7  273.46    5122   271.7
  5240.3  274.77  5268.4  276.66  5389.6  280.08  5434.1  282.83  5448.9   284.9
  5465.9  282.56  5488.4  281.58    5494   282.8  5500.8  281.82    5523  286.61
  5600.9  288.64  5634.9  287.88  5645.3  288.44    5658  291.16  5681.2  292.11
#Mann= 6 ,-1 , 0
  4207.1     .05       0  4709.5     .12       0  4774.8     .05       0
  4987.1     .07       0 5011.66     .05       0    5658      .1       0
Bank Sta=4987.1,5011.66
XS Rating Curve= 0 ,0
Exp/Cntr=0.3,0.1

Type RM Length L Ch R = 1 ,128524  ,524,524,524
BEGIN DESCRIPTION:
CRYSTAL CREEK 251.0
END DESCRIPTION:
XS GIS Cut Line= 3
      3831471.04     10140348.87       3831246.2     10139605.11
       3830561.2     10139260.27
#Sta/Elev= 30
    4223   286.3  4446.8  284.23  4586.3  283.25  4690.8  281.25  4769.4  278.91
  4911.7  271.78  4962.4  270.58  4977.6     271  4979.8  269.44  4999.5  270.87
  5017.5  271.05  5023.1  270.13  5031.7  271.78  5041.8   272.1  5054.1  271.41
  5076.5   271.8  5106.8  270.76  5166.1  270.53  5246.3  270.84  5290.9  271.83
  5357.8  274.62  5508.5   283.9  5558.7   286.4    5581  286.45  5597.7  288.05
  5603.3  287.49  5725.9  289.38  5748.3  287.07  5753.9  288.26  5766.9  289.17
#Mann= 5 ,-1 , 0
    4223     .05       0  4446.8     .12       0  4977.6     .07       0
  4999.5     .12       0  5041.8     .05       0
Bank Sta=4977.6,4999.5
XS Rating Curve= 0 ,0
Exp/Cntr=0.3,0.1

Type RM Length L Ch R = 1 ,128000  ,500,500,500
BEGIN DESCRIPTION:
CRYSTAL CREEK 250.0
END DESCRIPTION:
XS GIS Cut Line= 3
      3831525.94     10140320.27      3831595.76     10139403.62
      3831057.27       10138796.
#Sta/Elev= 30
  4080.7   285.2  4140.1   283.4  4196.8   283.2  4566.5     279  4671.6  280.01
  4721.7  278.35  4828.5  272.39  4912.3  269.78  4939.5  269.98  4982.5  270.02
  4992.5  269.52  4995.2   267.9  5002.4   267.9 5005.46  269.96  5007.2  271.02
  5014.8   269.9  5049.9  270.39  5141.9  268.72  5156.1  269.86  5225.4  270.19
  5311.7   271.1  5411.2  273.75  5446.3  273.84  5460.5   272.6  5474.8   274.4
  5552.5  274.86  5609.4  277.87  5723.2  286.74  5772.5  288.77  5811.9   288.4
#Mann= 6 ,-1 , 0
  4080.7     .05       0  4196.8     .12       0  4939.5     .05       0
  4982.5     .07       0 5005.46     .12       0  5225.4     .05       0
Bank Sta=4982.5,5005.46
XS Rating Curve= 0 ,0
Exp/Cntr=0.3,0.1