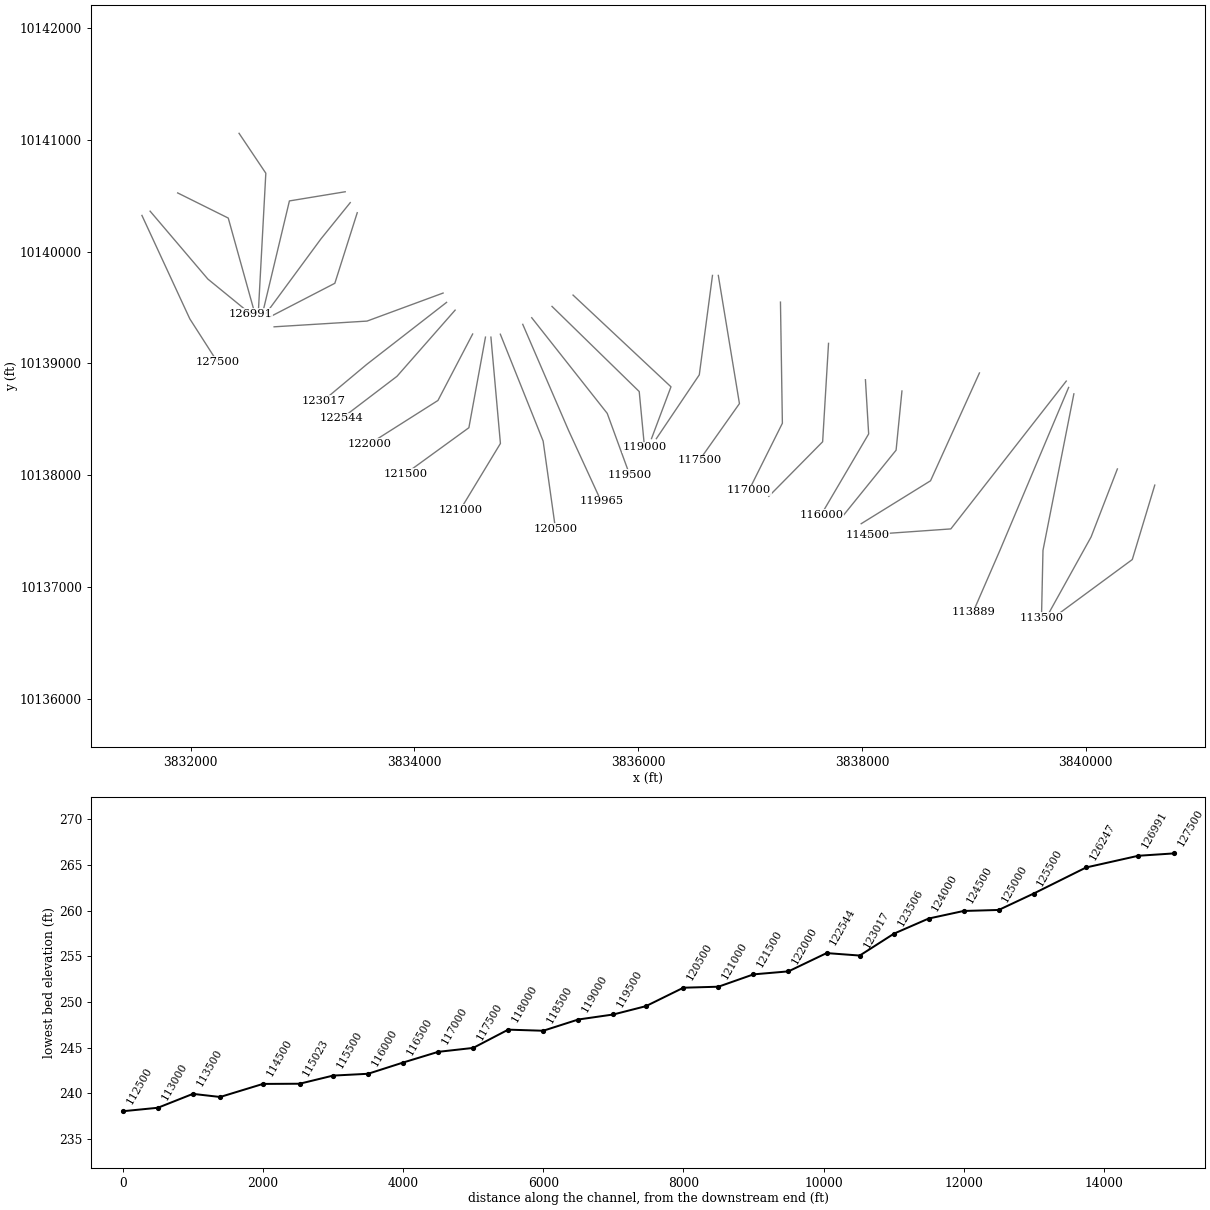
HEC-RAS study CRYSTAL CREEK.prj: CRYSTAL CREEK Base Level Engineering

--- CRYSTAL CREEK.g10 (geometry) --- (continued)

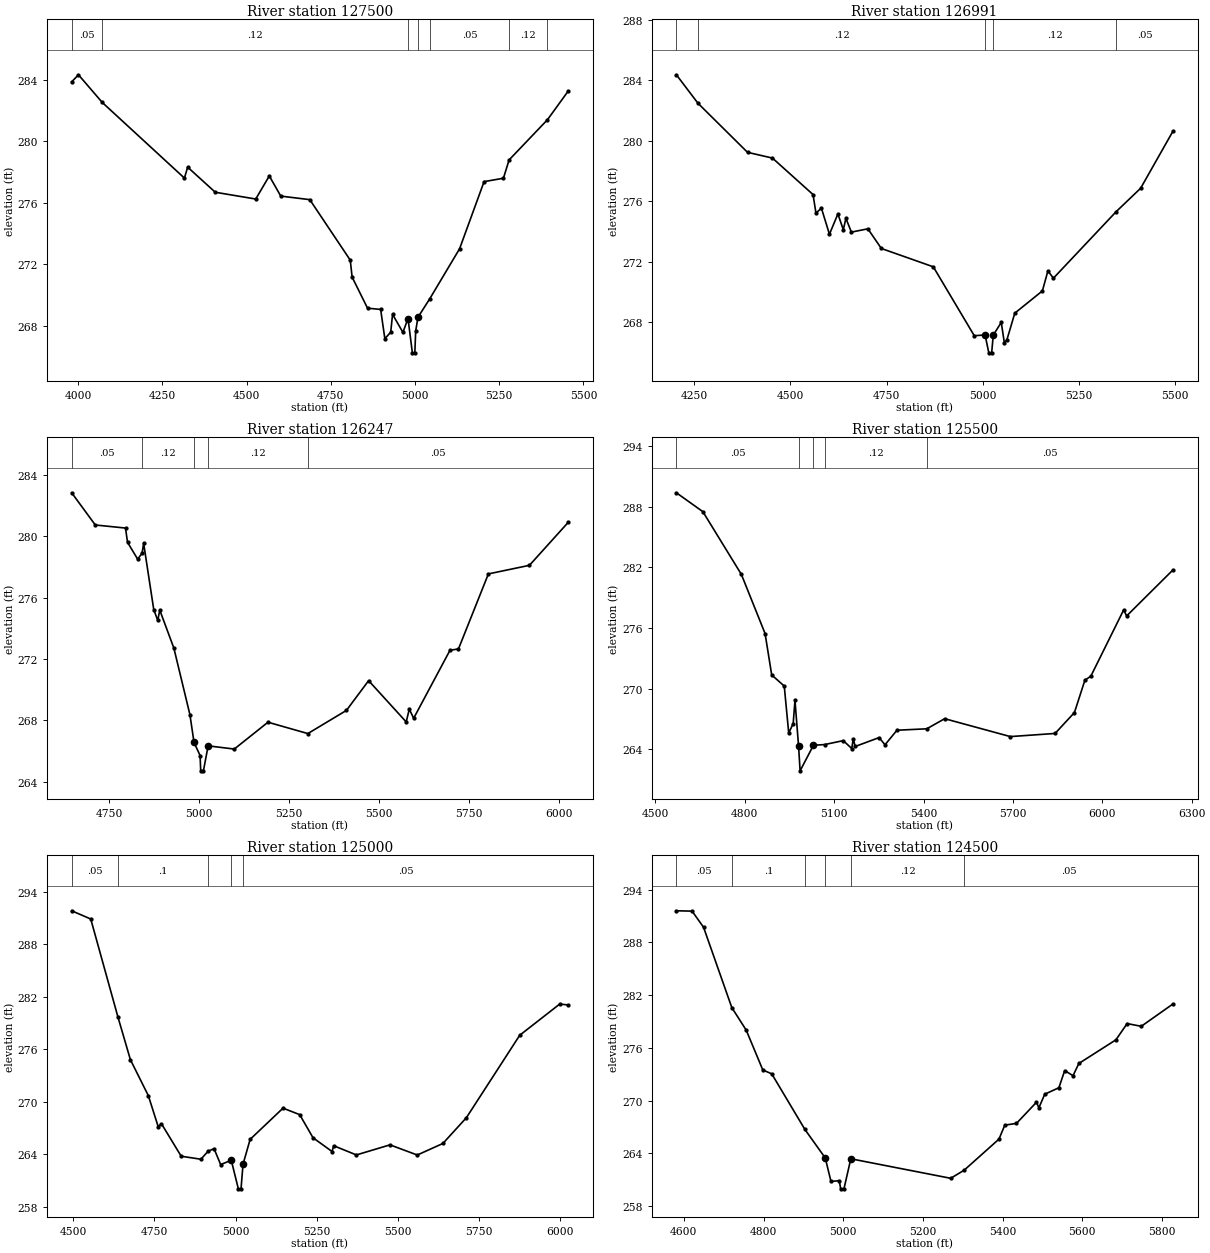
Type RM Length L Ch R = 1 ,127500  ,509,509,509
BEGIN DESCRIPTION:
CRYSTAL CREEK 249.0
END DESCRIPTION:
XS GIS Cut Line= 3
      3831564.14     10140323.69      3831992.15     10139398.39
      3832237.32     10139015.33
#Sta/Elev= 30
  3980.5  283.85  4000.6  284.31  4071.4  282.51  4315.2   277.6  4324.9  278.31
  4406.9  276.68    4527  276.24  4567.3  277.74  4601.3  276.43  4687.5   276.2
  4807.7  272.27  4813.2  271.17    4859  269.15  4897.9  269.07  4910.4  267.17
  4927.8  267.59  4933.3  268.75    4964  267.58  4979.2  268.48  4992.1  266.25
  4999.4  266.25    5002  267.67  5008.7  268.56  5043.7  269.76  5132.3  273.01
    5205  277.37  5262.5  277.59  5279.3  278.78  5393.2  281.39  5454.8  283.25
#Mann= 7 ,-1 , 0
  3980.5     .05       0  4071.4     .12       0  4979.2     .07       0
  5008.7     .12       0  5043.7     .05       0  5279.3     .12       0
  5393.2     .05       0
Bank Sta=4979.2,5008.7
XS Rating Curve= 0 ,0
Exp/Cntr=0.3,0.1

Type RM Length L Ch R = 1 ,126991  ,744,744,744
BEGIN DESCRIPTION:
CRYSTAL CREEK 248.0
END DESCRIPTION:
XS GIS Cut Line= 3
      3831637.18     10140361.94      3832153.08     10139754.84
      3832536.36     10139441.75
#Sta/Elev= 30
  4203.3  284.35  4259.4  282.47  4388.3  279.23  4453.2  278.85  4558.8  276.44
  4566.3  275.22  4580.6  275.54  4601.4  273.82  4623.4  275.16  4637.5  274.12
  4644.3  274.87  4658.5  273.96  4701.4  274.18  4736.5  272.88  4871.6  271.67
  4978.2  267.12  5006.3  267.17    5016  265.99  5023.4  265.99  5027.6  267.16
  5048.4     268  5056.3  266.67  5062.8  266.83  5083.6  268.61  5155.4  270.08
  5169.7   271.4  5184.1  270.92  5347.2  275.31    5411  276.86  5494.9  280.62
#Mann= 5 ,-1 , 0
  4203.3     .05       0  4259.4     .12       0  5006.3     .07       0
  5027.6     .12       0  5347.2     .05       0
Bank Sta=5006.3,5027.6
XS Rating Curve= 0 ,0
Exp/Cntr=0.3,0.1

Type RM Length L Ch R = 1 ,126247  ,747,747,747
BEGIN DESCRIPTION:
Mapping XS d28f06a1
END DESCRIPTION:
XS GIS Cut Line= 3
      3831883.61     10140525.07      3832335.72     10140300.17
      3832570.36     10139457.38
#Sta/Elev= 30
  4645.5  282.84  4711.1  280.74  4795.1  280.54  4800.7  279.61  4828.9  278.51
  4841.1   278.9  4845.5  279.54  4873.6  275.22  4884.7  274.52  4890.3  275.19
  4929.5  272.71  4974.1  268.37  4985.5  266.56  5002.3  265.71  5004.1  264.71
  5011.6  264.71  5024.7  266.34  5097.4  266.13    5191  267.88  5301.8  267.14
    5409  268.65  5470.7  270.59  5575.1   267.9  5583.7  268.73  5595.9  268.14
  5696.8  272.57  5720.4  272.66  5803.5  277.55  5917.6  278.11  6025.3  280.91
#Mann= 5 ,-1 , 0
  4645.5     .05       0  4841.1     .12       0  4985.5     .07       0
  5024.7     .12       0  5301.8     .05       0
Bank Sta=4985.5,5024.7
XS Rating Curve= 0 ,0
Exp/Cntr=0.3,0.1

Type RM Length L Ch R = 1 ,125500  ,500,500,500
BEGIN DESCRIPTION:
CRYSTAL CREEK 247.0
END DESCRIPTION:
XS GIS Cut Line= 3
      3832432.33     10141058.38      3832671.58     10140701.33
      3832605.08     10139466.01
#Sta/Elev= 30
  4570.2  289.38  4659.1  287.51  4788.2  281.31  4867.9  275.45  4890.2  271.35
  4932.3  270.25  4947.3   265.6  4962.3  266.54  4968.3  268.83  4980.3 264.334
  4985.5  261.86  5030.3  264.39  5067.7  264.46  5130.4  264.85  5158.9  264.07
  5163.9  265.02  5170.5  264.27  5250.6  265.15  5270.6  264.44  5310.7  265.88
  5410.7  266.02  5470.9  267.02  5691.3  265.25  5841.5  265.56  5906.5  267.63
  5941.6  270.83  5961.6  271.23  6071.8  277.79  6081.8  277.19  6237.1  281.74
#Mann= 5 ,-1 , 0
  4570.2     .05       0  4980.3     .05       0  5030.3     .05       0
  5067.7     .12       0  5410.7     .05       0
Bank Sta=4980.3,5030.3
XS Rating Curve= 0 ,0
Exp/Cntr=0.3,0.1

Type RM Length L Ch R = 1 ,125000  ,500,500,500
BEGIN DESCRIPTION:
CRYSTAL CREEK 246.0
END DESCRIPTION:
XS GIS Cut Line= 3
      3833381.12     10140535.57      3832882.43     10140453.49
      3832644.25     10139455.62
#Sta/Elev= 30
  4494.6   291.8  4553.4  290.86  4636.9  279.72  4675.7   274.8    4731   270.7
  4761.4  267.16  4771.5  267.49  4832.4  263.78  4893.2  263.44    4915  264.34
  4933.7  264.65    4954  262.83  4986.8  263.32  5008.6  260.06  5016.9  260.06
    5023  262.86    5045  265.71  5146.4  269.27  5197.8  268.53  5238.9  265.89
  5297.6  264.32  5302.7  264.98  5372.6  263.93  5476.3  265.08  5560.5  263.92
  5639.5  265.24  5711.9  268.18  5876.4  277.59  5999.7  281.15  6025.9  281.05
#Mann= 5 ,-1 , 0
  4494.6     .05       0  4636.9      .1       0    4915     .05       0
  4986.8     .07       0    5023     .05       0
Bank Sta=4986.8,5023
XS Rating Curve= 0 ,0
Exp/Cntr=0.3,0.1

Type RM Length L Ch R = 1 ,124500  ,500,500,500
BEGIN DESCRIPTION:
CRYSTAL CREEK 245.0
END DESCRIPTION:
XS GIS Cut Line= 3
      3833426.29     10140438.38      3833163.32     10140112.56
      3832673.13     10139445.75
#Sta/Elev= 30
  4581.3   291.6  4620.7  291.56  4649.5  289.72  4720.4  280.58  4756.6  278.01
  4798.2  273.48  4820.6  273.04  4903.7  266.72    4955  263.46  4969.3  260.79
  4990.2  260.88  4993.6  259.95  5001.9  259.95  5019.1  263.37  5269.8  261.15
  5303.6  262.07    5391  265.61  5405.6   267.2  5434.9   267.4    5485   269.8
  5491.2  269.18  5505.9  270.72  5541.4  271.46    5556  273.41  5576.9  272.83
  5591.5  274.22  5684.5  276.91  5712.7  278.76  5748.2  278.45  5827.6  280.99
#Mann= 6 ,-1 , 0
  4581.3     .05       0  4720.4      .1       0  4903.7     .12       0
    4955     .07       0  5019.1     .12       0  5303.6     .05       0
Bank Sta=4955,5019.1
XS Rating Curve= 0 ,0
Exp/Cntr=0.3,0.1

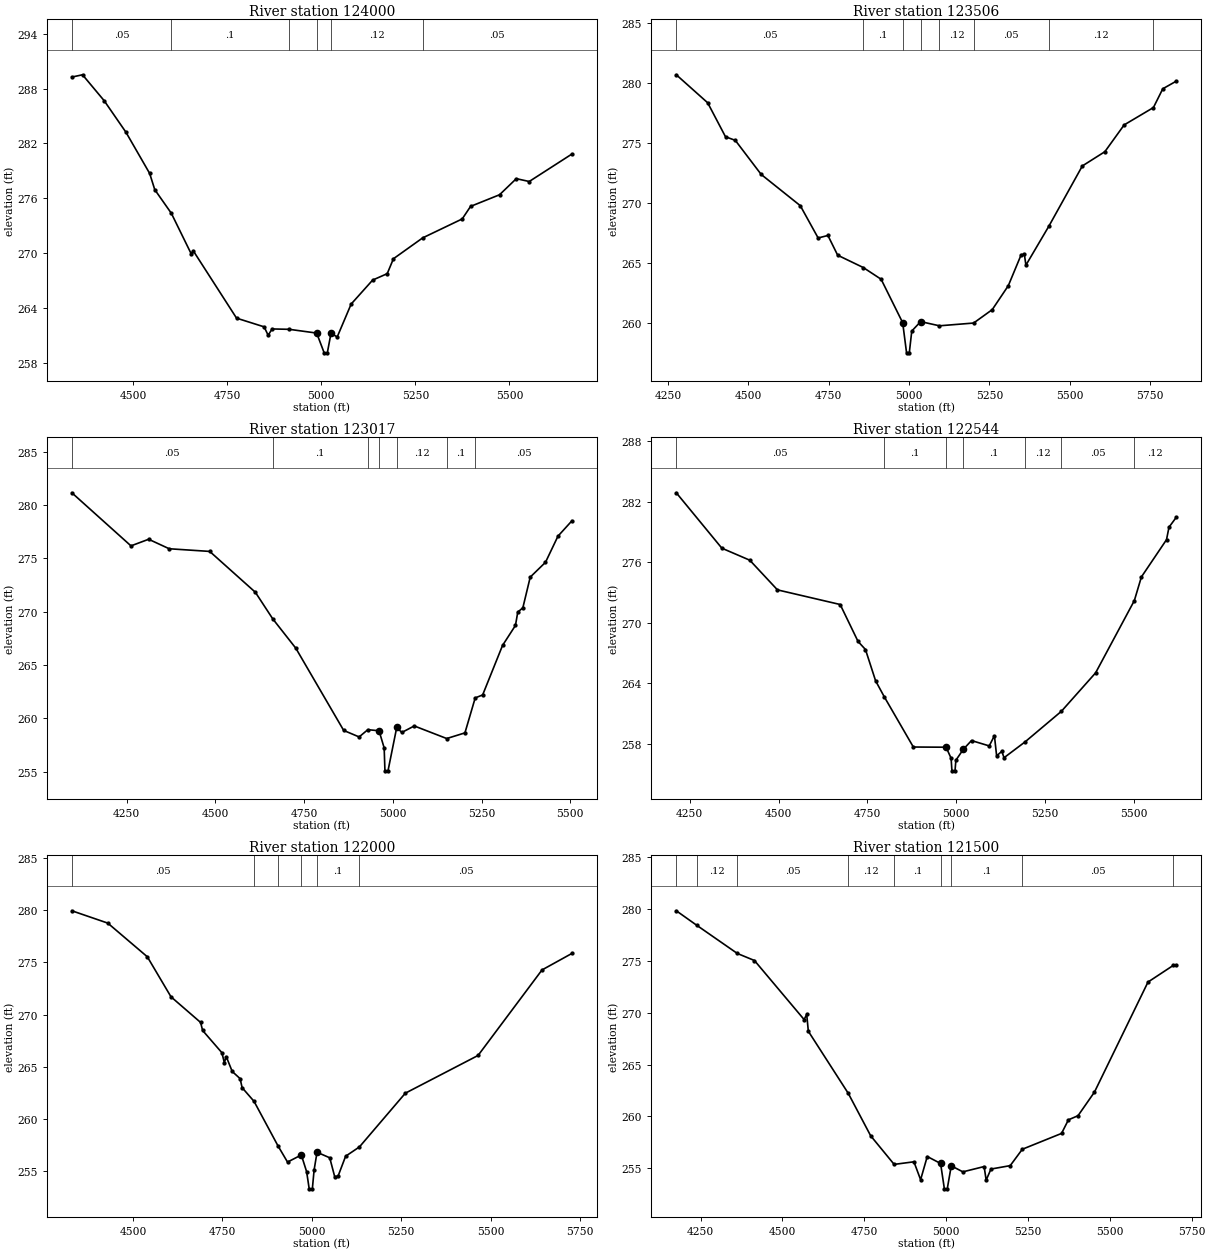
Type RM Length L Ch R = 1 ,124000  ,494,494,494
BEGIN DESCRIPTION:
CRYSTAL CREEK 244.0
END DESCRIPTION:
XS GIS Cut Line= 3
      3833488.76     10140348.05       3833288.5     10139716.65
      3832697.11     10139410.58
#Sta/Elev= 30
  4337.6  289.25  4365.9   289.5  4423.4  286.67  4481.3  283.22  4544.3  278.72
  4557.8  276.95  4601.8  274.37  4654.6  269.94  4659.9  270.28  4775.1  262.91
  4848.3  261.96    4859  261.04  4869.5  261.73  4914.9  261.69  4987.9  261.28
  5007.8  259.12  5016.2  259.12  5025.9  261.25  5042.5  260.86  5079.5  264.45
  5136.6  267.07  5175.3  267.77  5191.8   269.4  5269.5  271.68  5374.5  273.75
  5396.7  275.12  5473.6  276.39  5518.2  278.15  5552.5  277.84  5665.9  280.84
#Mann= 6 ,-1 , 0
  4337.6     .05       0  4601.8      .1       0  4914.9     .12       0
  4987.9     .07       0  5025.9     .12       0  5269.5     .05       0
Bank Sta=4987.9,5025.9
XS Rating Curve= 0 ,0
Exp/Cntr=0.3,0.1

Type RM Length L Ch R = 1 ,123506  ,489,489,489
BEGIN DESCRIPTION:
CRYSTAL CREEK 243.0
END DESCRIPTION:
XS GIS Cut Line= 3
      3834256.11     10139629.31      3833576.32     10139378.45
      3832745.69     10139327.24
#Sta/Elev= 30
  4275.4  280.71  4373.1  278.37  4428.6  275.53  4459.1  275.23  4539.7  272.38
  4661.4  269.77    4717  267.07  4747.4  267.28  4777.8  265.63  4857.5   264.6
  4913.1  263.62  4980.2  259.99  4992.3  257.47  5000.8  257.47  5008.5  259.29
  5036.1  260.08  5094.6  259.73    5201  259.96    5259  261.08    5309  263.08
  5349.1  265.67  5358.9  265.71  5363.9   264.8  5435.2  268.05  5539.5  273.09
  5609.6  274.28  5669.7  276.52  5760.8  277.97    5790  279.54  5832.2  280.18
#Mann= 8 ,-1 , 0
  4275.4     .05       0  4857.5      .1       0  4980.2     .07       0
  5036.1      .1       0  5094.6     .12       0    5201     .05       0
  5435.2     .12       0  5760.8     .05       0
Bank Sta=4980.2,5036.1
XS Rating Curve= 0 ,0
Exp/Cntr=0.3,0.1

Type RM Length L Ch R = 1 ,123017  ,473,473,473
BEGIN DESCRIPTION:
CRYSTAL CREEK 242.0
END DESCRIPTION:
XS GIS Cut Line= 3
      3834287.34     10139545.96      3833573.68     10138991.06
      3833186.71     10138667.54
#Sta/Elev= 30
    4096  281.15  4262.5  276.17  4312.3  276.79  4370.2   275.9  4484.3  275.65
  4612.8  271.82  4661.7  269.33  4726.8  266.57  4861.6  258.86  4905.1  258.25
  4929.6  258.93  4961.2  258.83  4975.6  257.22  4977.8  255.07  4986.4  255.07
    5011  259.14  5025.3  258.67  5060.4  259.28  5151.8   258.1  5203.1  258.63
    5232  261.91    5253  262.19    5309  266.83  5345.4  268.71  5351.9  269.96
  5366.2  270.36    5387  273.24    5430  274.63  5465.1  277.08  5504.4  278.52
#Mann= 7 ,-1 , 0
    4096     .05       0  4661.7      .1       0  4929.6     .12       0
  4961.2     .07       0    5011     .12       0  5151.8      .1       0
    5232     .05       0
Bank Sta=4961.2,5011
XS Rating Curve= 0 ,0
Exp/Cntr=0.3,0.1

Type RM Length L Ch R = 1 ,122544  ,544,544,544
BEGIN DESCRIPTION:
CRYSTAL CREEK 241.0
END DESCRIPTION:
XS GIS Cut Line= 3
      3834363.75     10139476.53      3833843.93      10138884.3
      3833351.36     10138508.93
#Sta/Elev= 30
    4212  282.89  4340.2   277.4  4418.8  276.21  4496.7  273.27  4673.2  271.82
  4723.5  268.16  4744.4  267.36  4772.9  264.26  4797.4  262.67  4879.1   257.7
  4971.2  257.68  4985.4  256.59  4987.7  255.34  4996.4  255.34  4998.8  256.39
  5020.2  257.49  5042.8  258.34  5092.7  257.81  5107.3  258.82  5113.5  256.83
  5128.1  257.27  5134.4  256.64  5193.6  258.21  5295.8  261.24  5392.1  265.05
  5501.1  272.21  5520.9  274.55  5591.6  278.24  5598.6  279.48  5619.3  280.47
#Mann= 7 ,-1 , 0
    4212     .05       0  4797.4      .1       0  4971.2     .07       0
  5020.2      .1       0  5193.6     .12       0  5295.8     .05       0
  5501.1     .12       0
Bank Sta=4971.2,5020.2
XS Rating Curve= 0 ,0
Exp/Cntr=0.3,0.1

Type RM Length L Ch R = 1 ,122000  ,500,500,500
BEGIN DESCRIPTION:
CRYSTAL CREEK 240.0
END DESCRIPTION:
XS GIS Cut Line= 3
      3834520.46     10139262.87      3834210.27     10138668.33
      3833596.42     10138278.63
#Sta/Elev= 30
  4329.4  279.94  4429.8  278.76  4540.3  275.54  4606.5  271.71  4689.2  269.26
  4694.9  268.49  4748.8  266.36  4755.5  265.42  4761.1  265.98  4777.6  264.57
  4799.7  263.88  4805.3  263.02  4838.6  261.71  4905.4  257.46  4932.2   255.9
  4970.8  256.58  4985.6  254.98  4992.8  253.34  5001.6  253.34  5006.5  255.14
  5014.7  256.84  5050.2  256.31  5064.1   254.5  5073.4  254.55  5094.6  256.46
  5133.2  257.35  5261.5  262.49  5464.8   266.1  5643.5  274.28  5727.1  275.86
#Mann= 6 ,-1 , 0
  4329.4     .05       0  4838.6     .12       0  4905.4      .1       0
  4970.8     .07       0  5014.7      .1       0  5133.2     .05       0
Bank Sta=4970.8,5014.7
XS Rating Curve= 0 ,0
Exp/Cntr=0.3,0.1

Type RM Length L Ch R = 1 ,121500  ,500,500,500
BEGIN DESCRIPTION:
CRYSTAL CREEK 239.0
END DESCRIPTION:
XS GIS Cut Line= 3
      3834635.03     10139235.07      3834486.73     10138424.52
      3833917.81     10138011.04
#Sta/Elev= 30
    4176  279.85    4238  278.46  4362.4  275.73  4414.7  275.05  4566.4  269.35
  4574.3  269.85  4579.3  268.22  4701.2  262.23  4769.7  258.13  4841.4  255.37
  4901.8  255.62  4922.2  253.89  4942.5  256.13  4983.2  255.46  4994.8  253.01
  5003.6  253.01  5015.8  255.23  5051.3  254.65  5116.2  255.16  5122.4  253.85
  5137.1  254.92  5195.9  255.25  5232.8  256.83  5352.7  258.36  5373.6  259.67
    5403  260.07  5453.2  262.35  5616.7  272.97  5694.5  274.59  5703.3  274.59
#Mann= 9 ,-1 , 0
    4176     .05       0    4238     .12       0  4362.4     .05       0
  4701.2     .12       0  4841.4      .1       0  4983.2     .07       0
  5015.8      .1       0  5232.8     .05       0  5694.5     .12       0
Bank Sta=4983.2,5015.8
XS Rating Curve= 0 ,0
Exp/Cntr=0.3,0.1

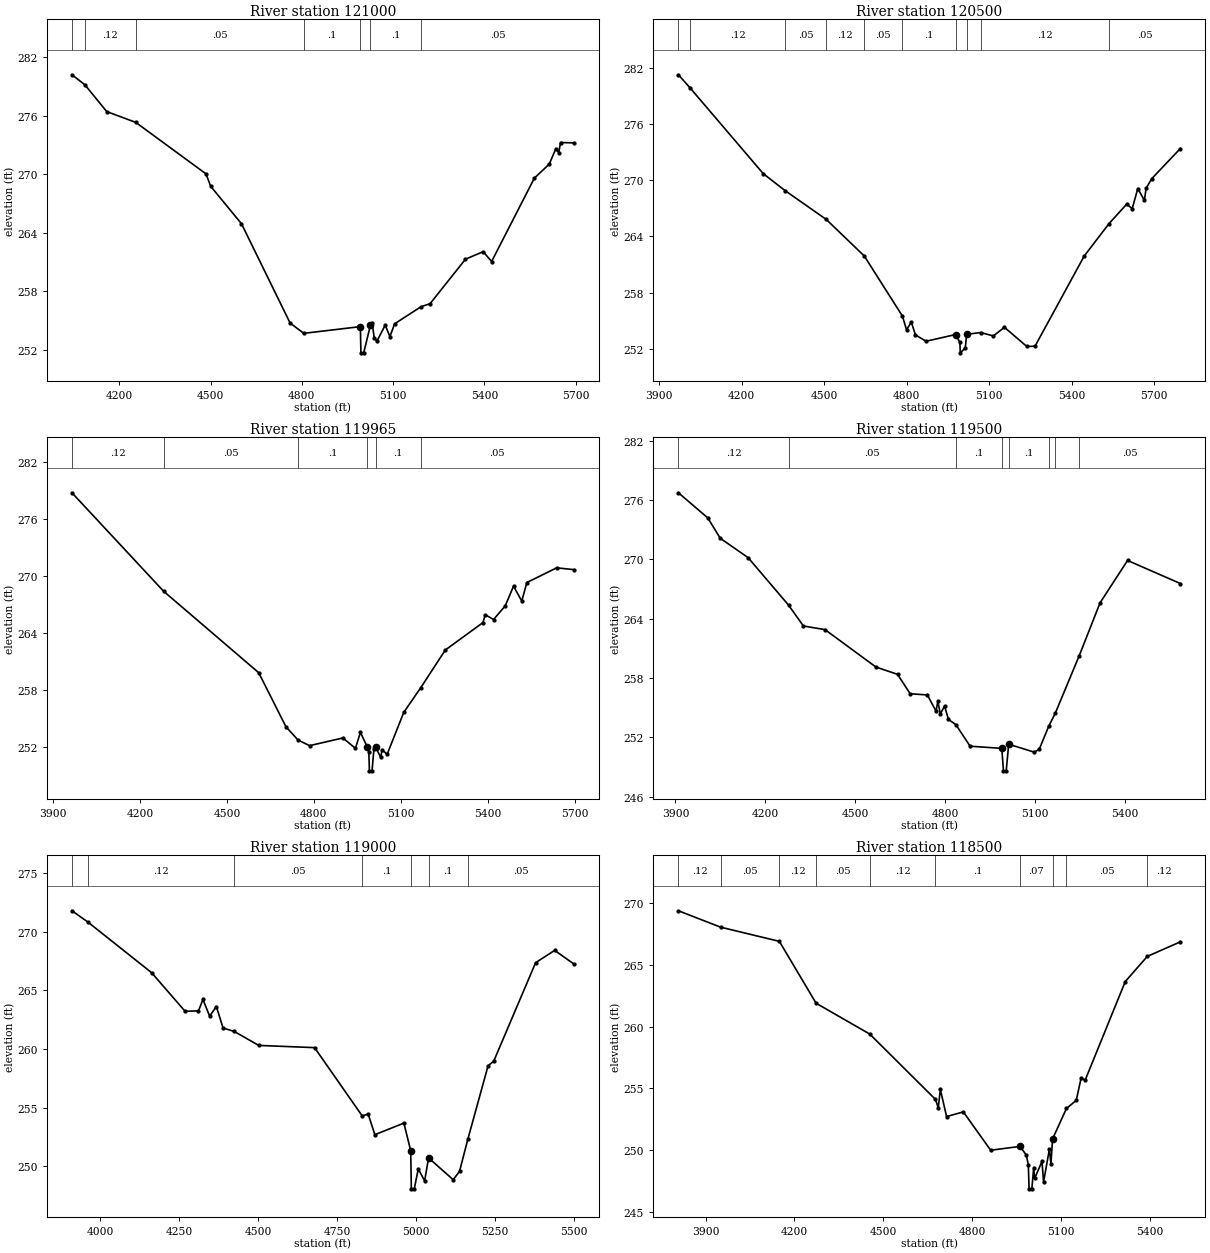
Type RM Length L Ch R = 1 ,121000  ,500,500,500
BEGIN DESCRIPTION:
CRYSTAL CREEK 238.0
END DESCRIPTION:
XS GIS Cut Line= 3
      3834683.65     10139235.03      3834768.67     10138283.52
      3834409.32     10137689.92
#Sta/Elev= 30
  4044.7  280.19    4087  279.17  4159.1  276.41  4254.2  275.31  4485.3  270.02
  4500.5  268.75  4601.7  264.91  4761.5  254.72  4806.5  253.66  4992.4  254.35
  4994.2  251.66  5003.3  251.66  5025.5  254.49  5031.3  254.69  5037.9  253.21
  5046.8  252.86    5074   254.5  5089.5  253.33    5105  254.64  5192.1   256.4
  5221.4   256.7  5337.8  261.27    5396  262.04  5423.7  261.03    5564  269.58
  5613.2  271.03  5634.6  272.61  5644.2  272.19  5650.1  273.24  5693.9   273.2
#Mann= 7 ,-1 , 0
  4044.7     .05       0    4087     .12       0  4254.2     .05       0
  4806.5      .1       0  4992.4     .07       0  5025.5      .1       0
  5192.1     .05       0
Bank Sta=4992.4,5025.5
XS Rating Curve= 0 ,0
Exp/Cntr=0.3,0.1

Type RM Length L Ch R = 1 ,120500  ,535,535,535
BEGIN DESCRIPTION:
CRYSTAL CREEK 237.0
END DESCRIPTION:
XS GIS Cut Line= 3
      3834767.87     10139261.03      3835150.47     10138305.06
      3835261.24     10137518.01
#Sta/Elev= 30
  3970.3  281.29  4012.9  279.88  4278.5  270.72  4357.6  268.91  4507.6  265.82
  4645.6  261.92  4784.5  255.49  4799.6  254.01  4816.9  254.84    4832  253.46
  4870.7  252.79  4978.4  253.51  4993.5  252.66  4994.9  251.55  5013.1  252.06
  5018.1  253.53    5069  253.72  5115.1  253.36  5155.5  254.28  5236.8  252.23
  5266.6  252.26  5445.4   261.9  5535.3  265.36  5599.8  267.45    5620  266.98
  5640.2  269.12  5664.2  267.86  5670.5  269.15  5690.7  270.17  5794.8   273.4
#Mann= 10 ,-1 , 0
  3970.3     .05       0  4012.9     .12       0  4357.6     .05       0
  4507.6     .12       0  4645.6     .05       0  4784.5      .1       0
  4978.4     .07       0  5018.1      .1       0    5069     .12       0
  5535.3     .05       0
Bank Sta=4978.4,5018.1
XS Rating Curve= 0 ,0
Exp/Cntr=0.3,0.1

Type RM Length L Ch R = 1 ,119965  ,465,465,465
BEGIN DESCRIPTION:
CRYSTAL CREEK 236.0
END DESCRIPTION:
XS GIS Cut Line= 3
      3834968.24     10139349.27      3835378.13     10138399.33
      3835669.27     10137765.83
#Sta/Elev= 30
  3965.4   278.8  4281.8  268.43  4609.8  259.86  4703.8  254.17  4745.7  252.77
  4785.2  252.18  4900.1  252.99  4943.6   251.9  4960.7  253.58  4984.2  252.06
  4989.7  251.56  4991.8  249.53  5000.9  249.53  5007.5  251.88    5013  252.03
  5030.4  250.97  5035.9  251.72  5053.1  251.28  5110.4  255.69  5169.3   258.3
  5253.7  262.25  5383.3  265.13  5391.6  265.96  5420.1  265.46  5460.3  266.89
    5489  268.97  5517.5   267.4    5535  269.35  5637.9   270.9  5697.2  270.71
#Mann= 6 ,-1 , 0
  3965.4     .12       0  4281.8     .05       0  4745.7      .1       0
  4984.2     .07       0    5013      .1       0  5169.3     .05       0
Bank Sta=4984.2,5013
XS Rating Curve= 0 ,0
Exp/Cntr=0.3,0.1

Type RM Length L Ch R = 1 ,119500  ,500,500,500
BEGIN DESCRIPTION:
CRYSTAL CREEK 235.0
END DESCRIPTION:
XS GIS Cut Line= 3
      3835048.49     10139408.54      3835723.41     10138552.75
      3835923.97     10138002.89
#Sta/Elev= 30
  3910.1  276.72  4008.2  274.18  4049.8  272.12  4142.9  270.16  4277.9  265.36
  4327.2  263.26  4399.4  262.89  4569.3  259.11  4641.5  258.37  4683.7  256.41
  4740.9  256.29  4769.8  254.66  4776.1  255.65  4784.2  254.36  4798.4  255.17
  4811.4  253.81  4835.9   253.3  4883.6  251.11  4989.4  250.89    4995  248.62
  5004.2  248.62  5012.4  251.31  5097.6  250.51  5114.3  250.79  5146.3  253.14
  5167.8  254.43  5247.8  260.25  5317.6  265.61  5409.3  269.88  5585.3  267.55
#Mann= 8 ,-1 , 0
  3910.1     .12       0  4277.9     .05       0  4835.9      .1       0
  4989.4     .07       0  5012.4      .1       0  5146.3     .05       0
  5167.8      .1       0  5247.8     .05       0
Bank Sta=4989.4,5012.4
XS Rating Curve= 0 ,0
Exp/Cntr=0.3,0.1

Type RM Length L Ch R = 1 ,119000  ,500,500,500
BEGIN DESCRIPTION:
CRYSTAL CREEK 234.0
END DESCRIPTION:
XS GIS Cut Line= 3
      3835229.83     10139509.73      3836009.36     10138748.01
      3836056.52     10138250.54
#Sta/Elev= 30
  3910.1   271.8  3960.4  270.84  4162.3  266.52  4268.5  263.22  4310.9  263.26
    4325  264.23  4346.2  262.81  4367.5  263.63  4388.6   261.8  4424.2   261.5
  4501.8  260.31  4678.5  260.12  4829.2   254.3  4848.2  254.45  4869.5  252.69
  4961.4  253.68    4983  251.32    4985  248.07  4994.3  248.07    5007  249.77
  5027.1  248.75  5039.6  250.71  5117.5  248.85  5137.6  249.56    5164  252.31
    5228  258.57    5246  258.97  5378.6  267.37  5438.9  268.42  5499.7  267.26
#Mann= 7 ,-1 , 0
  3910.1     .05       0  3960.4     .12       0  4424.2     .05       0
  4829.2      .1       0    4983     .07       0  5039.6      .1       0
    5164     .05       0
Bank Sta=4983,5039.6
XS Rating Curve= 0 ,0
Exp/Cntr=0.3,0.1

Type RM Length L Ch R = 1 ,118500  ,500,500,500
BEGIN DESCRIPTION:
CRYSTAL CREEK 233.0
END DESCRIPTION:
XS GIS Cut Line= 3
      3835417.84     10139611.09      3836293.16     10138790.46
      3836119.31     10138327.25
#Sta/Elev= 30
  3808.1  269.39  3950.7  268.06  4148.9  266.91  4273.1  261.89  4454.2  259.39
  4676.1  254.09  4685.4  253.41  4692.5   254.9  4713.5   252.7  4770.1  253.08
  4862.4  249.97  4961.1  250.28  4982.6  249.59  4989.5  248.79  4992.1  246.84
  5001.4  246.84  5007.7  248.57  5010.7  247.68  5035.6  249.06    5041   247.4
  5060.5  250.04  5065.9  248.86  5071.4  250.89  5118.3  253.36  5151.3  254.01
  5167.5   255.8  5181.5  255.66  5316.8  263.65  5391.2  265.69  5502.7  266.87
#Mann= 10 ,-1 , 0
  3808.1     .12       0  3950.7     .05       0  4148.9     .12       0
  4273.1     .05       0  4454.2     .12       0  4676.1      .1       0
  4961.1     .07       0  5071.4      .1       0  5118.3     .05       0
  5391.2     .12       0
Bank Sta=4961.1,5071.4
XS Rating Curve= 0 ,0
Exp/Cntr=0.3,0.1

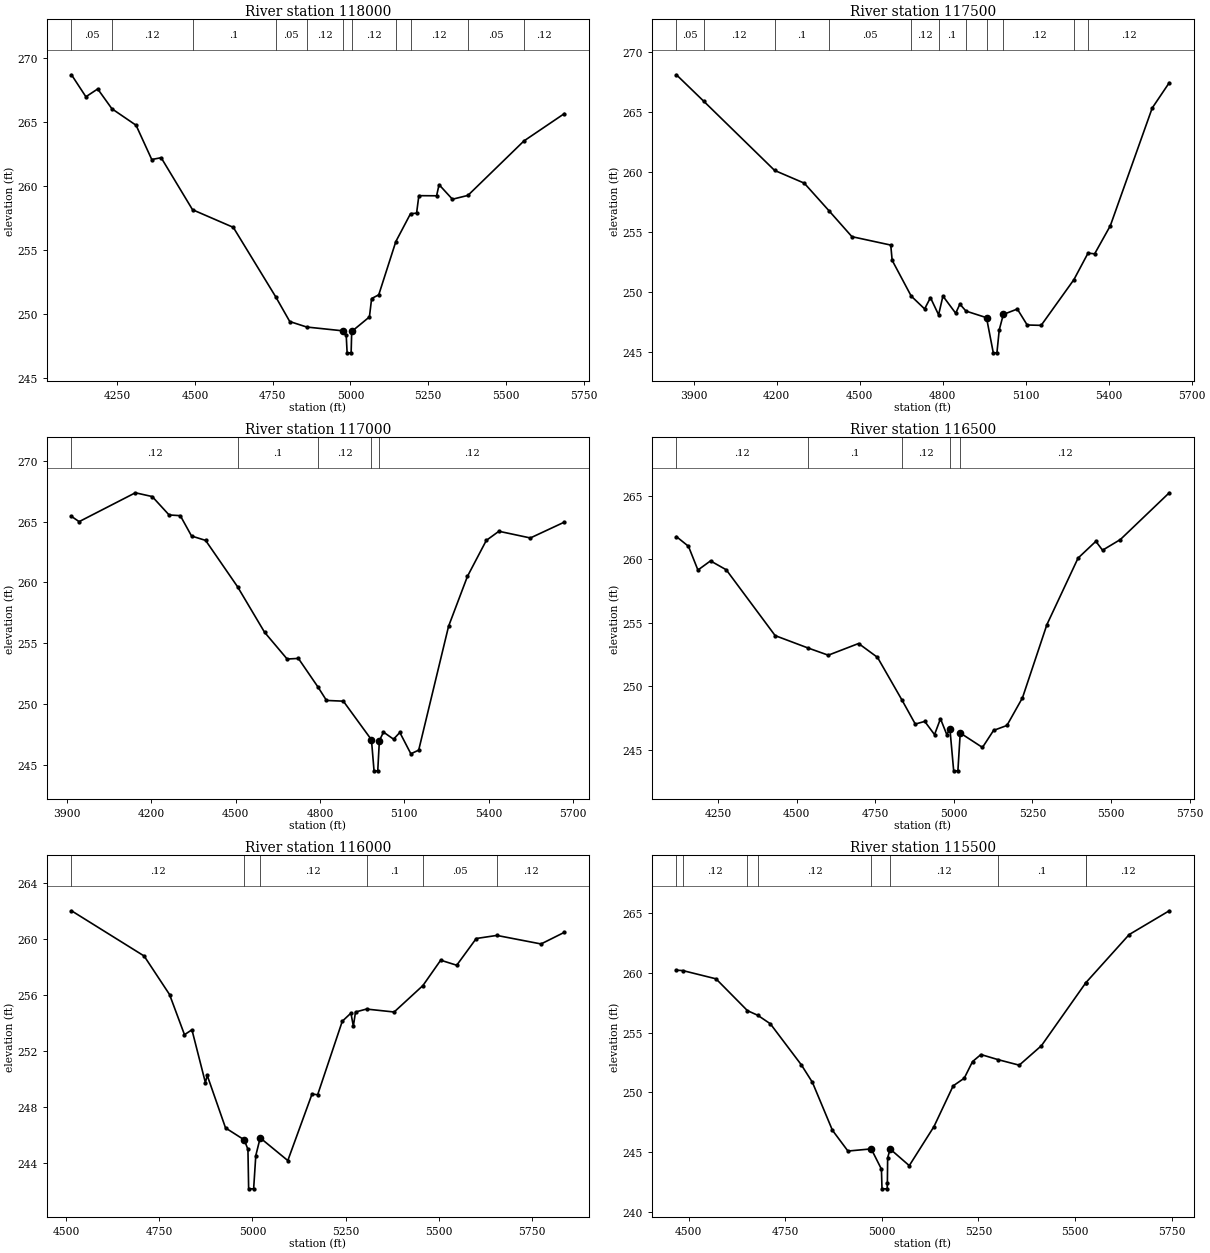
Type RM Length L Ch R = 1 ,118000  ,500,500,500
BEGIN DESCRIPTION:
CRYSTAL CREEK 232.0
END DESCRIPTION:
XS GIS Cut Line= 3
      3836664.28     10139786.96       3836546.3     10138897.55
      3836162.46      10138326.7
#Sta/Elev= 30
  4102.8  268.72  4149.1     267  4187.1  267.61  4232.8  266.06  4310.5  264.77
  4360.9  262.09  4391.2  262.23  4492.1  258.16  4623.2  256.78  4759.7  251.34
  4804.8  249.41  4859.3  248.98  4976.3  248.68  4986.4  248.32  4989.3  246.96
  5002.2  246.96    5004  248.63    5061  249.77  5068.1  251.21    5091   251.5
    5146  255.67  5193.2  257.85  5212.7  257.89    5220  259.26    5277  259.25
    5285  260.12    5328  258.98  5377.8  259.28  5557.9  263.54  5687.9  265.68
#Mann= 11 ,-1 , 0
  4102.8     .05       0  4232.8     .12       0  4492.1      .1       0
  4759.7     .05       0  4859.3     .12       0  4976.3     .07       0
    5004     .12       0    5146      .1       0  5193.2     .12       0
  5377.8     .05       0  5557.9     .12       0
Bank Sta=4976.3,5004
XS Rating Curve= 0 ,0
Exp/Cntr=0.3,0.1

Type RM Length L Ch R = 1 ,117500  ,500,500,500
BEGIN DESCRIPTION:
CRYSTAL CREEK 231.0
END DESCRIPTION:
XS GIS Cut Line= 3
      3836716.36     10139786.91      3836905.25     10138640.27
      3836548.09      10138134.7
#Sta/Elev= 30
  3837.9  268.13  3936.5  265.93  4192.8  260.16  4299.9   259.1  4389.3   256.8
  4472.2  254.64  4612.5  253.94  4617.6  252.67  4686.4  249.69  4734.9  248.62
    4756  249.56  4785.4  248.13  4801.1  249.69  4847.2  248.26  4862.3  249.02
  4884.4  248.44  4958.6  247.89  4983.1  244.96  4996.2  244.96  5004.6  246.87
  5019.4  248.16  5069.9  248.61  5105.6  247.28  5156.1  247.25  5274.4  251.06
  5325.5  253.27  5349.4  253.21    5406  255.55  5557.4  265.36    5619  267.47
#Mann= 11 ,-1 , 0
  3837.9     .05       0  3936.5     .12       0  4192.8      .1       0
  4389.3     .05       0  4686.4     .12       0  4785.4      .1       0
  4884.4     .12       0  4958.6     .07       0  5019.4     .12       0
  5274.4     .05       0  5325.5     .12       0
Bank Sta=4958.6,5019.4
XS Rating Curve= 0 ,0
Exp/Cntr=0.3,0.1

Type RM Length L Ch R = 1 ,117000  ,500,500,500
BEGIN DESCRIPTION:
CRYSTAL CREEK 230.0
END DESCRIPTION:
XS GIS Cut Line= 3
      3837271.92     10139548.24      3837289.05     10138464.48
      3836990.27     10137865.12
#Sta/Elev= 30
  3916.1  265.42  3943.3  264.99  4143.3  267.36  4203.3  267.05  4263.3  265.54
  4303.3  265.48  4343.3  263.81  4393.3  263.45  4506.8  259.65    4603  255.91
  4683.4  253.71  4723.4  253.76  4793.2  251.41  4823.4  250.31  4883.4  250.25
  4983.4  247.08  4992.6  244.53  5005.8  244.53  5011.6  247.01  5026.2  247.71
    5062  247.13  5084.4  247.68  5123.6  245.93  5151.5  246.23  5257.8   256.4
    5325   260.5  5392.1  263.45  5436.9   264.2  5548.8  263.65  5669.7  264.95
#Mann= 5 ,-1 , 0
  3916.1     .12       0  4506.8      .1       0  4793.2     .12       0
  4983.4     .07       0  5011.6     .12       0
Bank Sta=4983.4,5011.6
XS Rating Curve= 0 ,0
Exp/Cntr=0.3,0.1

Type RM Length L Ch R = 1 ,116500  ,500,500,500
BEGIN DESCRIPTION:
CRYSTAL CREEK 229.0
END DESCRIPTION:
XS GIS Cut Line= 3
      3837701.61     10139179.32      3837648.96     10138298.79
      3837167.84     10137811.06
#Sta/Elev= 30
  4117.9  261.79  4156.2  261.03  4186.3  259.16  4226.3  259.88  4276.4  259.18
  4431.9     254  4536.1  253.03  4600.8  252.46  4697.2  253.38  4757.3  252.29
  4835.2  248.93  4877.5  247.04  4907.6  247.25  4938.7  246.21  4957.6  247.46
  4977.7  246.21  4987.7  246.65  4999.6  243.36    5013  243.36  5020.4  246.34
  5091.1   245.2  5126.4  246.54  5168.9  246.93  5218.4  249.11  5296.1  254.87
  5395.1   260.1  5451.7  261.42    5473  260.72  5529.6  261.56  5685.1  265.24
#Mann= 5 ,-1 , 0
  4117.9     .12       0  4536.1      .1       0  4835.2     .12       0
  4987.7     .07       0  5020.4     .12       0
Bank Sta=4987.7,5020.4
XS Rating Curve= 0 ,0
Exp/Cntr=0.3,0.1

Type RM Length L Ch R = 1 ,116000  ,500,500,500
BEGIN DESCRIPTION:
CRYSTAL CREEK 228.0
END DESCRIPTION:
XS GIS Cut Line= 3
      3838031.47     10138853.73      3838060.29     10138368.99
      3837636.52     10137647.19
#Sta/Elev= 30
  4514.4  261.99  4709.3  258.76  4777.5  256.01  4817.6  253.14  4837.6  253.49
  4873.7  249.72  4878.7  250.23  4927.8  246.48  4977.9  245.63  4987.9  244.95
  4989.8  242.13  5003.2  242.13    5009  244.51  5020.8  245.77  5094.9  244.15
  5159.9   248.9    5175  248.85  5241.1   254.1  5264.3  254.68  5270.8  253.75
  5276.6  254.76  5306.1  254.97  5380.3  254.76  5457.5  256.65  5505.2  258.46
  5548.2   258.1  5600.6  260.01  5655.9  260.23  5774.5  259.62    5837  260.45
#Mann= 6 ,-1 , 0
  4514.4     .12       0  4977.9     .07       0  5020.8     .12       0
  5306.1      .1       0  5457.5     .05       0  5655.9     .12       0
Bank Sta=4977.9,5020.8
XS Rating Curve= 0 ,0
Exp/Cntr=0.3,0.1

Type RM Length L Ch R = 1 ,115500  ,477,477,477
BEGIN DESCRIPTION:
CRYSTAL CREEK 227.0
END DESCRIPTION:
XS GIS Cut Line= 3
      3838357.85     10138753.06       3838305.5     10138223.64
      3837837.98     10137644.88
#Sta/Elev= 30
    4468  260.21  4484.5  260.18  4570.5  259.49  4651.9  256.83  4678.7  256.44
  4711.2  255.73  4791.6  252.29  4820.2  250.83  4871.9  246.83  4912.1  245.09
  4972.4  245.27  4998.8  243.58  5000.3  241.93  5013.7  241.93  5014.2  242.43
  5014.9  244.52  5021.4  245.26  5070.9  243.87  5134.9  247.14  5184.5  250.54
  5213.2  251.18  5234.7  252.57  5256.4  253.16  5301.1  252.73  5355.6  252.27
  5413.1   253.9  5527.9  259.16  5528.2  259.17  5640.2  263.19    5744  265.18
#Mann= 9 ,-1 , 0
    4468     .05       0  4484.5     .12       0  4651.9     .05       0
  4678.7     .12       0  4972.4     .07       0  5021.4     .12       0
  5301.1      .1       0  5527.9     .05       0  5528.2     .12       0
Bank Sta=4972.4,5021.4
XS Rating Curve= 0 ,0
Exp/Cntr=0.3,0.1

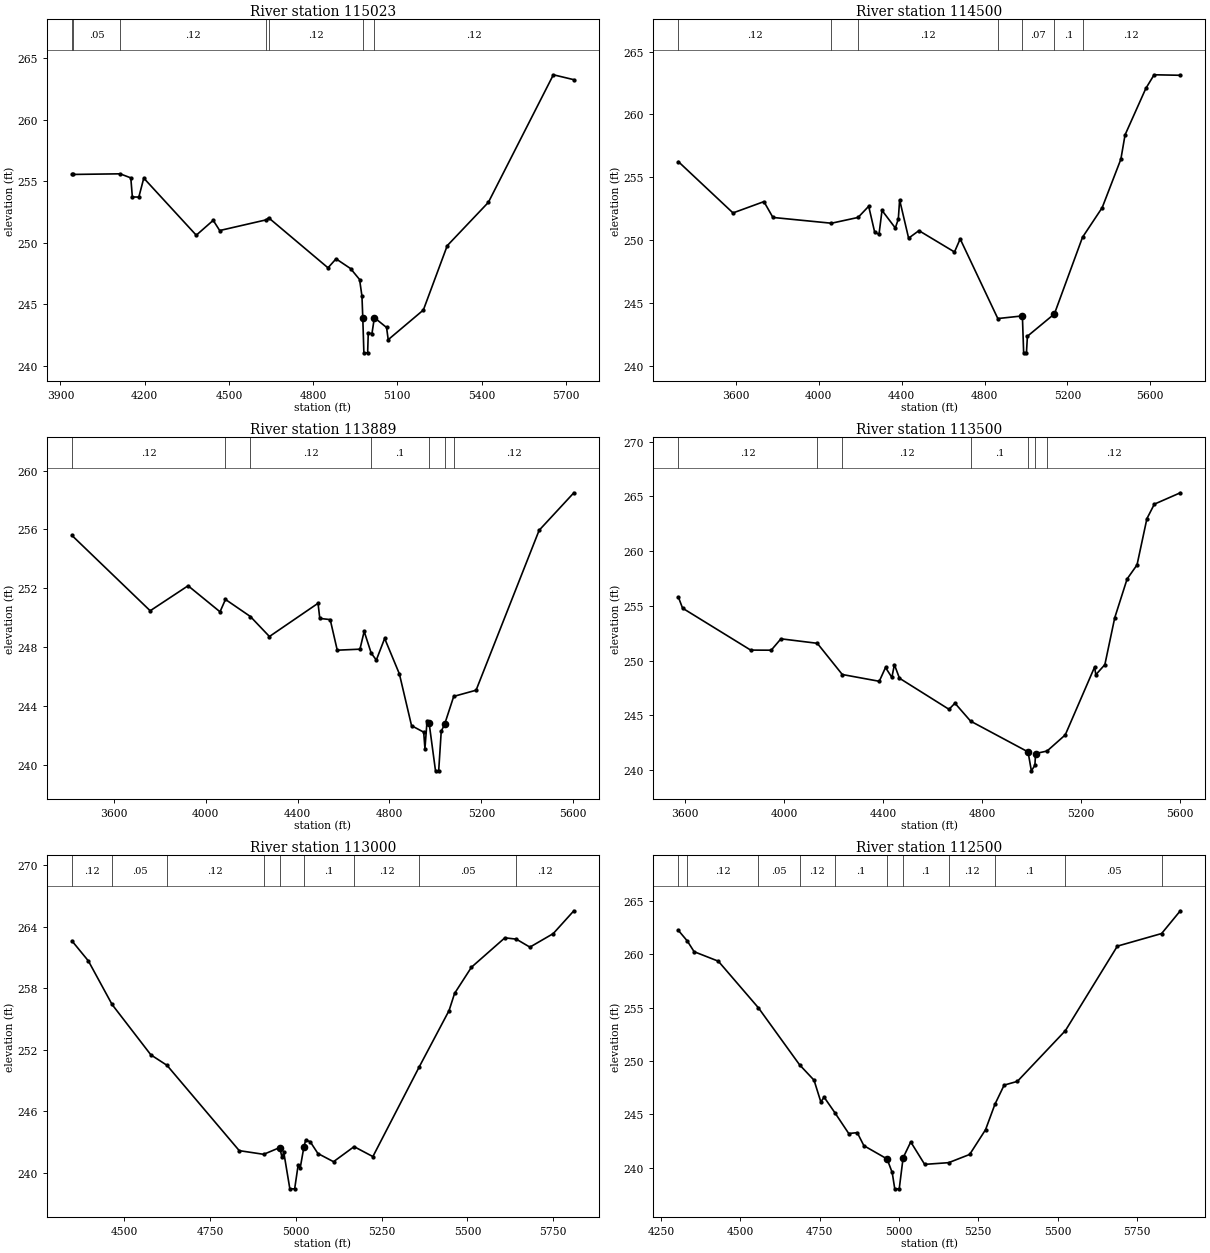
Type RM Length L Ch R = 1 ,115023  ,523,523,523
BEGIN DESCRIPTION:
CRYSTAL CREEK 226.0
END DESCRIPTION:
XS GIS Cut Line= 3
      3839050.56     10138914.51      3838613.38     10137949.74
      3837993.67     10137565.82
#Sta/Elev= 30
  3940.8  255.54  3944.2  255.54  4112.5  255.59  4150.5  255.26    4156  253.71
  4179.1   253.7  4196.7  255.24  4383.7   250.6  4444.1  251.81  4467.2  250.98
    4633  251.85  4641.4  252.02  4853.1  247.95  4881.7  248.68  4933.4  247.89
  4965.6     247  4974.1  245.64 4976.97 243.908  4980.9  241.04  4994.3  241.04
  4996.5  242.64  5009.7  242.61  5018.3   243.9  5061.7   243.1  5067.6  242.11
  5192.8  244.52  5277.9  249.75  5424.4  253.27    5656  263.64    5729  263.24
#Mann= 7 ,-1 , 0
  3940.8     .12       0  3944.2     .05       0  4112.5     .12       0
    4633     .05       0  4641.4     .12       0 4976.97     .07       0
  5018.3     .12       0
Bank Sta=4976.97,5018.3
XS Rating Curve= 0 ,0
Exp/Cntr=0.3,0.1

Type RM Length L Ch R = 1 ,114500  ,611,611,611
BEGIN DESCRIPTION:
CRYSTAL CREEK 225.0
END DESCRIPTION:
XS GIS Cut Line= 3
       3839826.6      10138841.6      3838794.85     10137519.16
       3838051.7     10137466.69
#Sta/Elev= 30
  3322.7  256.24  3586.1  252.16  3735.4  253.06  3778.8   251.8  4061.2  251.34
  4189.7   251.8    4241  252.69    4270  250.62  4290.8  250.46  4305.3  252.36
  4369.5  250.96    4384  251.67  4390.3   253.2  4433.7  250.15  4483.5  250.75
  4655.1  249.05  4682.5  250.09  4864.2  243.75  4982.8  243.96  4988.9  241.02
  5002.4  241.02    5007  242.34  5137.3  244.12  5272.9  250.22  5367.9  252.58
  5458.1  256.44  5478.2  258.37  5578.4  262.07  5618.5  263.16    5745  263.12
#Mann= 7 ,-1 , 0
  3322.7     .12       0  4061.2     .05       0  4189.7     .12       0
  4864.2      .1       0  4982.8     .07       0  5137.3      .1       0
  5272.9     .12       0
Bank Sta=4982.8,5137.3
XS Rating Curve= 0 ,0
Exp/Cntr=0.3,0.1

Type RM Length L Ch R = 1 ,113889  ,389,389,389
BEGIN DESCRIPTION:
Mapping XS 47638649
END DESCRIPTION:
XS GIS Cut Line= 3
      3839847.84     10138784.74      3839233.66     10137327.37
      3838993.76     10136775.02
#Sta/Elev= 30
  3418.5  255.59  3758.9  250.47  3923.8  252.17  4062.7   250.4  4086.4  251.24
  4194.8  250.08  4277.7  248.72  4489.2  250.98  4496.8  249.95  4542.1  249.87
  4572.8  247.79  4671.6  247.86  4689.9  249.07  4720.5  247.59  4742.8  247.12
    4779  248.59  4843.1  246.18    4896  242.66  4948.9  242.22  4954.3   241.1
  4963.4  242.95  4972.6  242.82  5000.3  239.59  5014.1  239.59  5025.2  242.28
  5039.6  242.74  5079.5  244.65  5176.8  245.07  5451.1  255.94  5602.2  258.49
#Mann= 7 ,-1 , 0
  3418.5     .12       0  4086.4     .05       0  4194.8     .12       0
  4720.5      .1       0  4972.6     .07       0  5039.6      .1       0
  5079.5     .12       0
Bank Sta=4972.6,5039.6
XS Rating Curve= 0 ,0
Exp/Cntr=0.3,0.1

Type RM Length L Ch R = 1 ,113500  ,500,500,500
BEGIN DESCRIPTION:
CRYSTAL CREEK 224.0
END DESCRIPTION:
XS GIS Cut Line= 3
      3839894.73     10138727.51      3839618.58     10137327.18
      3839605.25     10136726.13
#Sta/Elev= 30
  3572.7  255.79  3589.5  254.79  3864.7  250.96  3947.7  250.95    3987  251.99
    4134  251.58    4235  248.73  4384.5  248.11  4409.7  249.37  4435.4  248.46
  4445.6  249.63  4466.1  248.39  4666.3  245.55  4690.3  246.11  4753.6  244.47
  4985.8  241.66  4999.2  239.93  5013.5  240.43  5016.1  241.51  5062.7  241.74
  5136.1  243.21  5254.7  249.41  5259.7  248.71  5296.2  249.63  5336.2  253.92
  5386.2  257.46  5426.2  258.74  5466.2  262.97  5496.2  264.29  5601.2  265.33
#Mann= 7 ,-1 , 0
  3572.7     .12       0    4134     .05       0    4235     .12       0
  4753.6      .1       0  4985.8     .07       0  5013.5      .1       0
  5062.7     .12       0
Bank Sta=4985.8,5016.1
XS Rating Curve= 0 ,0
Exp/Cntr=0.3,0.1

Type RM Length L Ch R = 1 ,113000  ,500,500,500
BEGIN DESCRIPTION:
CRYSTAL CREEK 223.0
END DESCRIPTION:
XS GIS Cut Line= 3
       3840283.6     10138055.56      3840048.77     10137447.53
      3839656.16     10136739.15
#Sta/Elev= 30
  4348.2  262.62  4395.9  260.67  4465.1  256.41  4578.1  251.49    4625  250.47
  4835.4  242.14  4906.6  241.78  4953.3  242.44  4959.8   241.5  4965.2  241.96
  4982.8  238.41  4996.8  238.41  5006.9  240.72  5012.7   240.4 5023.58 242.473
  5028.7  243.15  5041.7  243.03  5064.5  241.86    5110  241.06  5169.9  242.53
  5224.6  241.56  5359.3   250.3  5446.5  255.82  5462.5  257.49  5511.7  260.05
    5609  262.92  5642.3  262.79  5681.9  262.01  5749.8  263.33  5809.9  265.56
#Mann= 9 ,-1 , 0
  4348.2     .12       0  4465.1     .05       0    4625     .12       0
  4906.6      .1       0  4953.3     .07       0 5023.58      .1       0
  5169.9     .12       0  5359.3     .05       0  5642.3     .12       0
Bank Sta=4953.3,5023.58
XS Rating Curve= 0 ,0
Exp/Cntr=0.3,0.1

Type RM Length L Ch R = 1 ,112500  ,500,500,500
BEGIN DESCRIPTION:
CRYSTAL CREEK 222.0
END DESCRIPTION:
XS GIS Cut Line= 3
      3840617.86      10137911.1      3840416.83     10137245.08
       3839702.5     10136718.58
#Sta/Elev= 30
  4304.3  262.22  4332.4  261.23  4353.8  260.23  4430.2  259.34  4556.8  254.97
  4686.5  249.64  4732.1   248.2  4753.5  246.17  4763.9  246.61  4797.5  245.17
  4841.5  243.21  4868.4  243.29  4889.3  242.07  4962.4  240.83  4978.6  239.56
  4986.7  238.03  5000.8  238.03 5013.03 240.938  5037.1  242.42    5081  240.32
  5156.7  240.48    5223  241.25  5273.1  243.57  5302.7  245.95  5331.7  247.74
  5373.4  248.09  5524.9  252.84  5688.8  260.75  5828.4  261.93  5887.4  264.06
#Mann= 11 ,-1 , 0
  4304.3     .05       0  4332.4     .12       0  4556.8     .05       0
  4686.5     .12       0  4797.5      .1       0  4962.4     .07       0
 5013.03      .1       0  5156.7     .12       0  5302.7      .1       0
  5524.9     .05       0  5828.4     .12       0
Bank Sta=4962.4,5013.03
XS Rating Curve= 0 ,0
Exp/Cntr=0.3,0.1