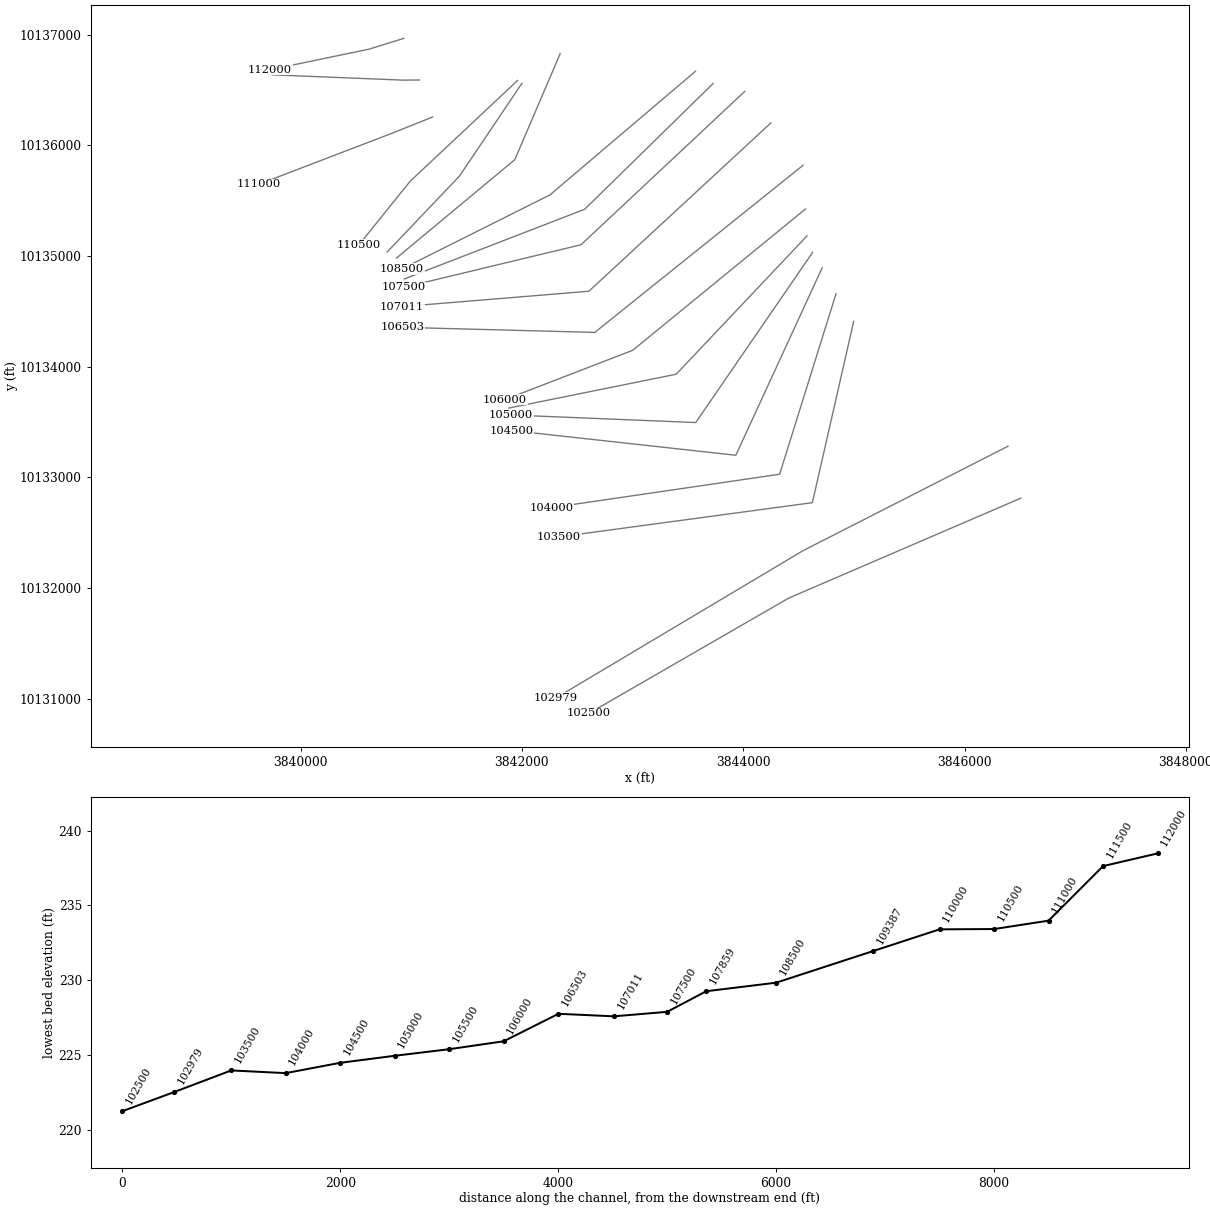
HEC-RAS study CRYSTAL CREEK.prj: CRYSTAL CREEK Base Level Engineering

--- CRYSTAL CREEK.g10 (geometry) --- (continued)

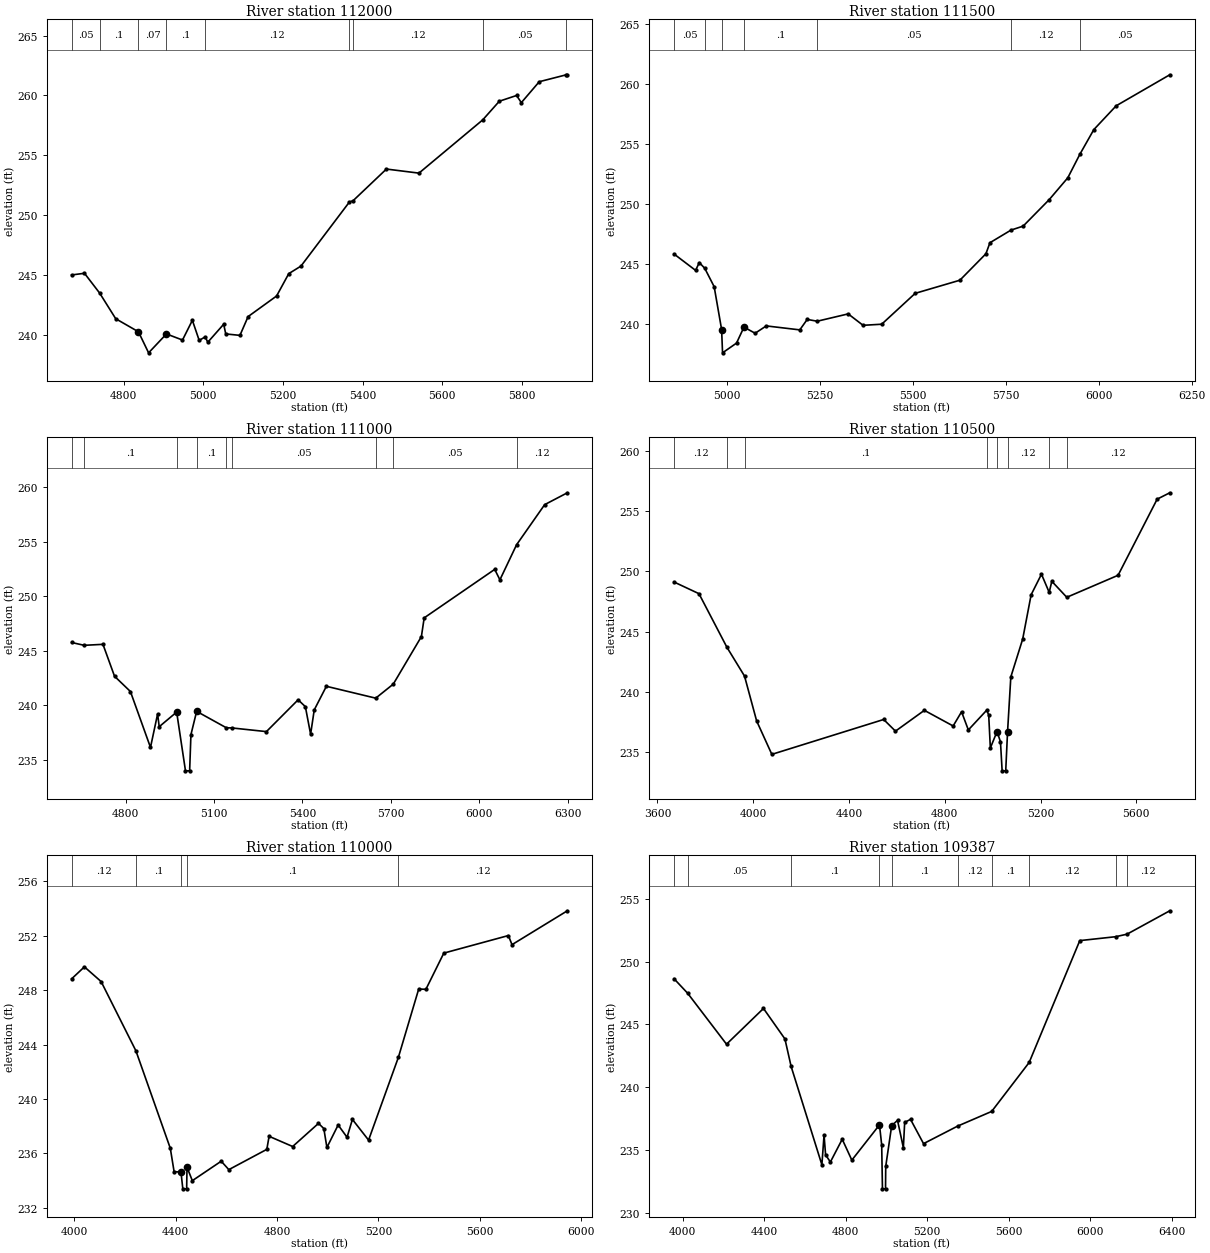
Type RM Length L Ch R = 1 ,112000  ,500,500,500
BEGIN DESCRIPTION:
CRYSTAL CREEK 221.0
END DESCRIPTION:
XS GIS Cut Line= 3
      3840933.58     10136965.66      3840617.98     10136867.56
      3839723.03     10136681.89
#Sta/Elev= 30
  4669.5  244.99  4701.7  245.13  4739.9  243.47  4780.2  241.33  4837.2  240.24
  4862.7  238.48  4907.5  240.06  4947.8  239.55  4972.6   241.2  4989.7  239.52
  5004.5  239.81  5011.4  239.37  5051.2  240.87  5056.4  240.06    5092  239.94
  5112.5  241.51    5184  243.23  5214.6   245.1  5245.2  245.73  5366.9  251.09
  5375.9  251.19  5459.7  253.84  5541.4   253.5  5701.5  257.95  5743.2  259.51
  5786.5  259.99  5798.4  259.39  5843.4  261.14  5911.4  261.72    5914  261.72
#Mann= 9 ,-1 , 0
  4669.5     .05       0  4739.9      .1       0  4837.2     .07       0
  4907.5      .1       0  5004.5     .12       0  5366.9      .1       0
  5375.9     .12       0  5701.5     .05       0  5911.4     .12       0
Bank Sta=4837.2,4907.5
XS Rating Curve= 0 ,0
Exp/Cntr=0.3,0.1

Type RM Length L Ch R = 1 ,111500  ,500,500,500
BEGIN DESCRIPTION:
CRYSTAL CREEK 220.0
END DESCRIPTION:
XS GIS Cut Line= 3
      3841075.79     10136589.36       3840933.9     10136587.74
      3839743.86     10136635.71
#Sta/Elev= 30
  4858.1  245.85    4916  244.49    4926  245.14  4940.7  244.66    4966  243.13
    4986  239.57  4988.5  237.63  5026.1  238.44  5046.1  239.77  5046.3 239.764
  5076.1  239.26  5106.1  239.87  5196.2  239.54  5216.2  240.41    5243  240.26
  5326.3  240.87  5366.3  239.92  5416.4  240.01  5506.5  242.58  5626.6  243.67
  5696.6  245.87  5707.5  246.79  5764.1  247.84  5796.7  248.17  5866.7  250.37
  5916.8  252.19  5949.3  254.15  5986.8   256.2  6046.9  258.18    6191  260.76
#Mann= 7 ,-1 , 0
  4858.1     .05       0  4940.7      .1       0    4986     .07       0
  5046.1      .1       0    5243     .05       0  5764.1     .12       0
  5949.3     .05       0
Bank Sta=4986,5046.3
XS Rating Curve= 0 ,0
Exp/Cntr=0.3,0.1

Type RM Length L Ch R = 1 ,111000  ,500,500,500
BEGIN DESCRIPTION:
CRYSTAL CREEK 219.0
END DESCRIPTION:
XS GIS Cut Line= 3
      3841192.94     10136255.16       3840837.3      10136112.2
      3839624.03     10135647.27
#Sta/Elev= 30
  4616.7  245.76  4659.2   245.5    4723  245.59  4762.3  242.66  4816.2  241.26
  4884.3  236.13  4908.5   239.2  4913.9  238.03 4973.18 239.373  5003.1  233.98
  5017.2  233.98  5021.6   237.3    5041  239.44  5141.9  237.93  5159.8  237.92
  5277.8  237.58  5385.4   240.5    5410  239.87  5427.8  237.34  5440.1  239.57
  5481.3  241.74  5648.8  240.65  5708.4  241.94  5803.8   246.3  5813.3  248.02
  6052.7  252.47  6070.3  251.51  6126.9  254.73  6222.2  258.41  6299.3   259.5
#Mann= 9 ,-1 , 0
  4616.7     .05       0  4659.2      .1       0 4973.18     .07       0
    5041      .1       0  5141.9     .12       0  5159.8     .05       0
  5648.8     .12       0  5708.4     .05       0  6126.9     .12       0
Bank Sta=4973.18,5041
XS Rating Curve= 0 ,0
Exp/Cntr=0.3,0.1

Type RM Length L Ch R = 1 ,110500  ,500,500,500
BEGIN DESCRIPTION:
CRYSTAL CREEK 218.0
END DESCRIPTION:
XS GIS Cut Line= 3
      3841961.19     10136585.05      3840990.77     10135674.68
      3840526.84     10135098.68
#Sta/Elev= 30
  3669.4  249.12  3773.5  248.15  3890.3  243.69  3963.7   241.3  4014.3  237.57
  4077.8  234.79  4544.8  237.69  4594.1  236.72  4714.7  238.45  4834.9  237.15
  4870.1  238.33  4898.4  236.82    4975  238.46  4983.4  238.07  4990.3  235.32
  5018.3  236.69  5032.6  235.83  5039.5  233.42  5054.5  233.42 5062.16  236.67
  5075.8  241.23  5125.4  244.38  5160.6  248.06  5203.8  249.77    5236  248.26
    5247  249.18  5309.5  247.85  5523.7  249.68  5686.9  256.01  5739.6  256.54
#Mann= 8 ,-1 , 0
  3669.4     .12       0  3890.3     .05       0  3963.7      .1       0
    4975     .12       0  5018.3     .07       0 5062.16     .12       0
    5236     .05       0  5309.5     .12       0
Bank Sta=5018.3,5062.16
XS Rating Curve= 0 ,0
Exp/Cntr=0.3,0.1

Type RM Length L Ch R = 1 ,110000  ,613,613,613
BEGIN DESCRIPTION:
CRYSTAL CREEK 217.0
END DESCRIPTION:
XS GIS Cut Line= 3
      3842000.23     10136558.99      3841436.01     10135721.04
      3840783.75     10135036.14
#Sta/Elev= 30
  3989.8  248.83  4040.2  249.71  4106.1  248.63  4243.4  243.54  4379.1  236.38
    4394  234.67  4421.3  234.62  4428.5   233.4  4443.6   233.4    4445  234.99
    4466     234    4580  235.43    4610  234.81  4759.9   236.3  4768.9  237.26
  4861.9  236.51  4963.8  238.21  4984.8  237.83    4997  236.44  5041.3  238.09
  5076.5  237.19  5097.6   238.5  5161.4  236.98    5279  243.06  5359.2  248.08
  5387.6  248.06  5458.3  250.72  5713.1  252.01  5727.3  251.34  5945.8  253.83
#Mann= 5 ,-1 , 0
  3989.8     .12       0  4243.4      .1       0  4421.3     .07       0
    4445      .1       0    5279     .12       0
Bank Sta=4421.3,4445
XS Rating Curve= 0 ,0
Exp/Cntr=0.3,0.1

Type RM Length L Ch R = 1 ,109387  ,887,887,887
BEGIN DESCRIPTION:
CRYSTAL CREEK 216.0
END DESCRIPTION:
XS GIS Cut Line= 3
      3842346.28     10136827.83      3841936.16     10135869.61
       3840867.1      10134980.6
#Sta/Elev= 30
  3957.7  248.63  4024.4  247.48  4215.2  243.43  4396.6  246.27  4501.8  243.85
  4532.3  241.66  4683.2  233.85  4693.8  236.21  4701.4  234.64  4724.9  234.07
    4783  235.88  4830.2  234.22  4965.8  237.02  4976.7  235.43  4980.4  231.94
  4995.5  231.94  4996.5  233.72  5025.7  236.96  5054.4  237.38    5083  235.21
  5089.5  237.22  5118.2  237.46    5182  235.53  5348.9  236.92  5516.4  238.09
  5700.4  241.98  5948.8  251.66  6124.6  251.97  6180.5  252.17  6390.4  254.03
#Mann= 10 ,-1 , 0
  3957.7     .12       0  4024.4     .05       0  4532.3      .1       0
  4965.8     .07       0  5025.7      .1       0  5348.9     .12       0
  5516.4      .1       0  5700.4     .12       0  6124.6     .05       0
  6180.5     .12       0
Bank Sta=4965.8,5025.7
XS Rating Curve= 0 ,0
Exp/Cntr=0.3,0.1

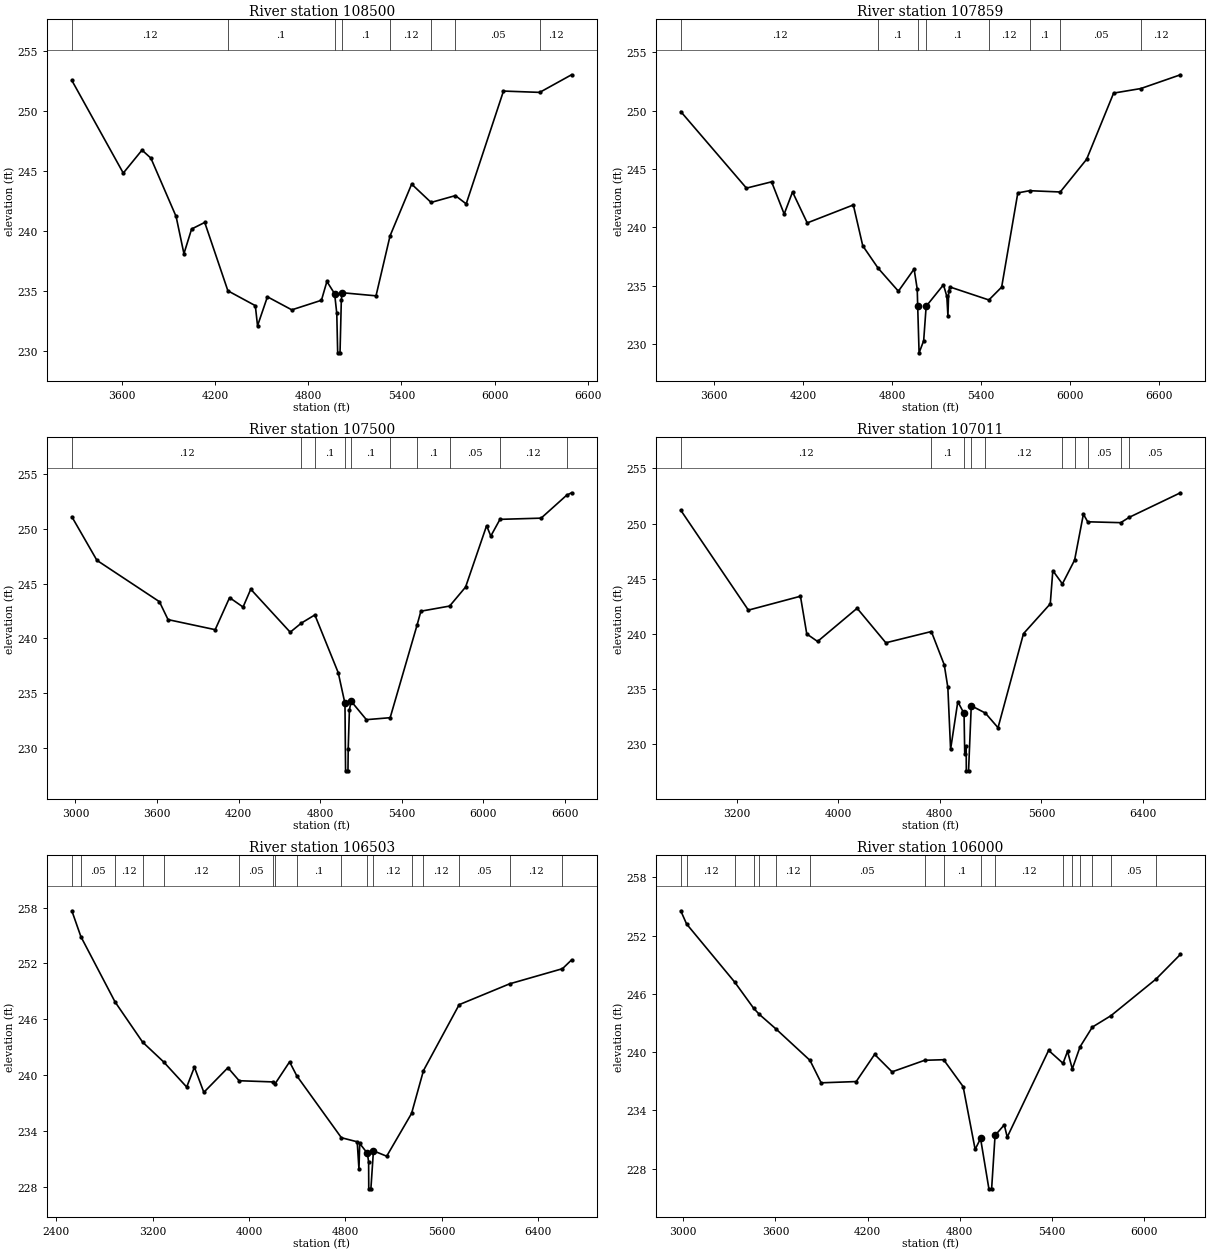
Type RM Length L Ch R = 1 ,108500  ,641,641,641
BEGIN DESCRIPTION:
CRYSTAL CREEK 215.0
END DESCRIPTION:
XS GIS Cut Line= 3
      3843568.49     10136668.11      3842254.37     10135551.57
      3840916.42     10134881.86
#Sta/Elev= 30
  3275.6  252.58  3607.1  244.84  3727.9  246.76    3785  246.09  3947.5  241.22
  3998.1  238.11  4047.5  240.17  4132.1  240.72  4281.4  235.01  4458.2  233.77
  4472.5  232.09  4536.2  234.51  4693.3  233.42  4884.4  234.22  4919.5  235.79
  4969.2  234.77  4983.2  233.13    4989  229.83  5004.1  229.83  5012.6  234.27
  5018.5  234.85  5236.1  234.59  5326.6   239.6  5465.8  243.92    5591  242.39
  5747.7  242.96  5817.3  242.27  6057.6  251.69    6291  251.58  6496.2  253.05
#Mann= 8 ,-1 , 0
  3275.6     .12       0  4281.4      .1       0  4969.2     .07       0
  5018.5      .1       0  5326.6     .12       0    5591      .1       0
  5747.7     .05       0    6291     .12       0
Bank Sta=4969.2,5018.5
XS Rating Curve= 0 ,0
Exp/Cntr=0.3,0.1

Type RM Length L Ch R = 1 ,107859  ,359,359,359
BEGIN DESCRIPTION:
Mapping XS eeb99dc1
END DESCRIPTION:
XS GIS Cut Line= 3
      3843728.09     10136557.79      3842567.07     10135420.98
      3840937.29     10134791.27
#Sta/Elev= 30
  3375.1  249.93  3818.5  243.37  3988.2  243.91  4073.1  241.15  4129.6  243.04
  4228.7  240.39  4539.7  241.93  4603.4  238.43  4707.2  236.51  4843.9  234.54
  4949.9  236.44    4971  234.72    4974 233.299  4983.5  229.26  5014.4  230.29
  5031.3  233.25  5148.1  235.09  5170.7   234.1  5178.1  232.42  5183.4  234.55
  5192.1   234.9  5454.5  233.79  5540.7  234.89  5649.8  242.96  5729.3  243.15
  5936.2  243.04  6114.1  245.84  6296.3  251.51  6479.6   251.9  6747.2  253.08
#Mann= 8 ,-1 , 0
  3375.1     .12       0  4707.2      .1       0    4974     .07       0
  5031.3      .1       0  5454.5     .12       0  5729.3      .1       0
  5936.2     .05       0  6479.6     .12       0
Bank Sta=4974,5031.3
XS Rating Curve= 0 ,0
Exp/Cntr=0.3,0.1

Type RM Length L Ch R = 1 ,107500  ,489,489,489
BEGIN DESCRIPTION:
CRYSTAL CREEK 214.0
END DESCRIPTION:
XS GIS Cut Line= 3
      3844013.63     10136486.01      3842534.26     10135100.44
      3840930.28     10134715.19
#Sta/Elev= 30
  2973.1  251.12  3157.7  247.13  3617.4  243.35  3680.9  241.71  4027.7  240.79
  4133.7  243.72  4232.9  242.86  4289.5  244.49  4579.7  240.56  4662.8   241.4
  4761.1  242.14  4933.3  236.85  4982.7  234.04  4987.1  227.88  5004.7  227.88
  5006.6  229.92  5015.2   233.4  5027.2  234.26  5140.3  232.56  5315.2  232.74
    5513   241.2  5541.4  242.48  5752.8  242.95  5870.2  244.69  6024.8   250.3
  6055.6  249.35  6123.2  250.88  6425.8  250.99  6614.1  253.09  6649.6  253.31
#Mann= 10 ,-1 , 0
  2973.1     .12       0  4662.8     .05       0  4761.1      .1       0
  4982.7     .07       0  5027.2      .1       0  5315.2     .12       0
    5513      .1       0  5752.8     .05       0  6123.2     .12       0
  6614.1     .05       0
Bank Sta=4982.7,5027.2
XS Rating Curve= 0 ,0
Exp/Cntr=0.3,0.1

Type RM Length L Ch R = 1 ,107011  ,508,508,508
BEGIN DESCRIPTION:
CRYSTAL CREEK 213.0
END DESCRIPTION:
XS GIS Cut Line= 3
      3844249.78     10136201.33      3842605.04     10134680.52
      3840916.45     10134541.58
#Sta/Elev= 30
  2759.9  251.21  3292.4  242.15  3702.4  243.41  3752.2  239.99  3837.3  239.31
  4148.6  242.32  4374.8  239.19  4733.1  240.21  4834.7  237.19    4863  235.14
  4884.6  229.53  4941.3  233.85  4990.6  232.78  4995.9  229.12  5007.2  229.85
  5008.4  227.58    5026  227.58  5047.4  233.48  5158.2  232.82  5258.1  231.49
  5458.7  240.02  5669.4  242.72  5689.5  245.73  5764.9  244.53  5861.1  246.69
  5930.3  250.85  5964.2  250.16    6224  250.08    6292  250.57  6694.3  252.79
#Mann= 10 ,-1 , 0
  2759.9     .12       0  4733.1      .1       0  4990.6     .07       0
  5047.4      .1       0  5158.2     .12       0  5764.9     .05       0
  5861.1     .12       0  5964.2     .05       0    6224     .12       0
    6292     .05       0
Bank Sta=4990.6,5047.4
XS Rating Curve= 0 ,0
Exp/Cntr=0.3,0.1

Type RM Length L Ch R = 1 ,106503  ,503,503,503
BEGIN DESCRIPTION:
CRYSTAL CREEK 212.0
END DESCRIPTION:
XS GIS Cut Line= 3
      3844541.42     10135819.36      3842658.65     10134308.58
      3840923.32     10134354.08
#Sta/Elev= 30
    2529  257.66  2604.1  254.88  2887.8  247.86  3116.9  243.53    3291  241.41
  3482.9   238.7  3546.9  240.84  3625.3  238.13  3825.3  240.78  3918.5  239.38
  4201.3  239.25  4215.9  239.03  4337.4  241.41  4396.6  239.92  4767.6  233.25
  4899.1  232.81  4913.5  229.88  4919.9  232.63  4983.8  231.57  4993.8  230.63
  4994.9  227.75  5012.6  227.75  5033.8  231.84  5143.8  231.26  5350.5  235.86
  5449.3  240.47  5745.7  247.56  6164.5   249.8  6603.7  251.43  6678.9  252.37
#Mann= 17 ,-1 , 0
    2529     .12       0  2604.1     .05       0  2887.8     .12       0
  3116.9     .05       0    3291     .12       0  3918.5     .05       0
  4201.3     .12       0  4215.9     .05       0  4396.6      .1       0
  4767.6     .12       0  4983.8     .07       0  5033.8     .12       0
  5350.5     .05       0  5449.3     .12       0  5745.7     .05       0
  6164.5     .12       0  6603.7     .05       0
Bank Sta=4983.8,5033.8
XS Rating Curve= 0 ,0
Exp/Cntr=0.3,0.1

Type RM Length L Ch R = 1 ,106000  ,500,500,500
BEGIN DESCRIPTION:
CRYSTAL CREEK 211.0
END DESCRIPTION:
XS GIS Cut Line= 3
      3844562.28     10135423.55       3843001.3     10134146.84
      3841846.99     10133701.31
#Sta/Elev= 30
  2983.4  254.55  3021.4  253.19  3335.4  247.19    3459  244.49  3495.1  243.88
  3602.7  242.39  3825.1  239.14  3897.7  236.83    4126  236.96  4245.9  239.76
  4359.3  237.96  4571.6  239.15  4695.3  239.21  4822.3  236.44  4900.5  229.97
  4935.7   231.1  4990.1  225.91  5007.8  225.91  5030.2  231.41  5090.1   232.5
  5109.4  231.24  5378.9  240.17  5472.7  238.84  5502.1  240.07  5533.2  238.27
  5583.7  240.54  5663.7  242.57  5785.4  243.75  6078.6  247.52  6237.3  250.06
#Mann= 17 ,-1 , 0
  2983.4     .05       0  3021.4     .12       0  3335.4     .05       0
    3459     .12       0  3495.1     .05       0  3602.7     .12       0
  3825.1     .05       0  4571.6     .12       0  4695.3      .1       0
  4935.7     .07       0  5030.2     .12       0  5472.7     .05       0
  5533.2     .12       0  5583.7     .05       0  5663.7     .12       0
  5785.4     .05       0  6078.6     .12       0
Bank Sta=4935.7,5030.2
XS Rating Curve= 0 ,0
Exp/Cntr=0.3,0.1

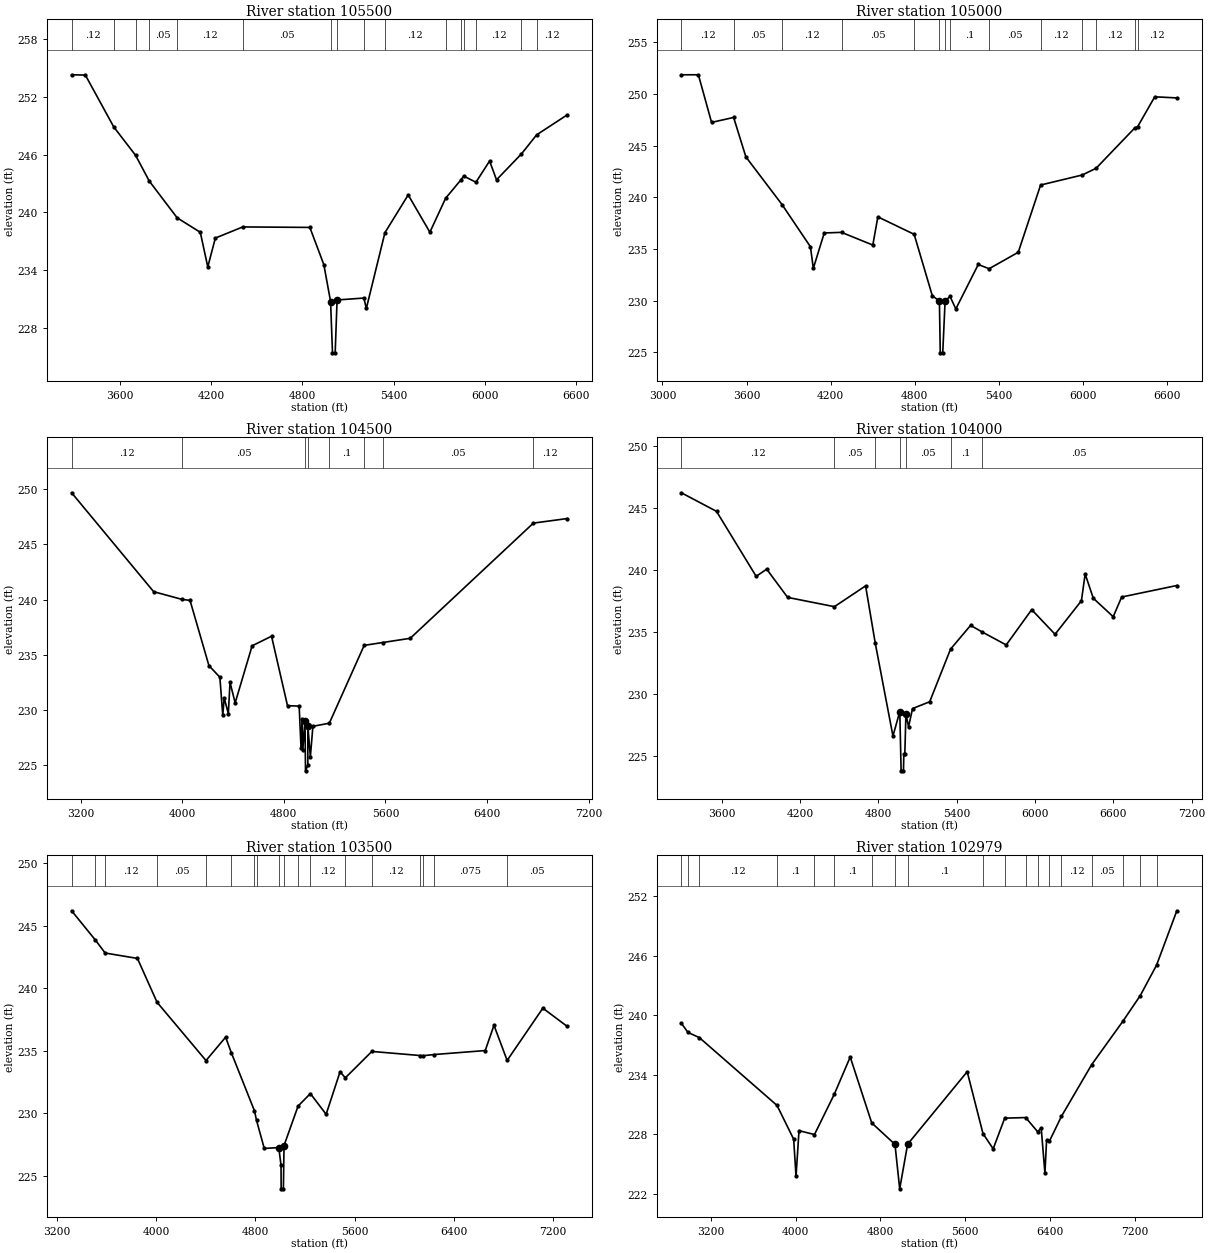
Type RM Length L Ch R = 1 ,105500  ,500,500,500
BEGIN DESCRIPTION:
CRYSTAL CREEK 210.0
END DESCRIPTION:
XS GIS Cut Line= 3
      3844576.13     10135180.46      3843394.42     10133930.81
      3841882.23     10133625.02
#Sta/Elev= 30
  3280.1  254.31  3370.5  254.28  3557.7  248.88  3701.3  245.93  3791.4  243.25
  3974.9  239.43  4127.4  237.92  4176.7  234.32  4226.5  237.32    4407  238.48
  4848.7  238.43  4940.9  234.56 4985.33  230.72  4997.9  225.38  5015.6  225.38
  5028.1  230.88  5204.6  231.08  5220.8     230  5343.2  237.88  5496.4  241.81
  5639.2  237.93  5742.8  241.46  5842.7  243.36    5862  243.77  5942.6  243.13
  6032.5  245.34    6078  243.38  6242.3  246.08  6342.2  248.06  6542.8  250.13
#Mann= 16 ,-1 , 0
  3280.1     .12       0  3557.7     .05       0  3701.3     .12       0
  3791.4     .05       0  3974.9     .12       0    4407     .05       0
 4985.33     .05       0  5028.1     .05       0  5204.6     .05       0
  5343.2     .12       0  5742.8     .05       0  5842.7     .12       0
    5862     .05       0  5942.6     .12       0  6242.3     .05       0
  6342.2     .12       0
Bank Sta=4985.33,5028.1
XS Rating Curve= 0 ,0
Exp/Cntr=0.3,0.1

Type RM Length L Ch R = 1 ,105000  ,500,500,500
BEGIN DESCRIPTION:
CRYSTAL CREEK 209.0
END DESCRIPTION:
XS GIS Cut Line= 3
      3844626.48     10135031.15      3843570.85     10133494.03
      3841902.65     10133562.41
#Sta/Elev= 30
  3135.3  251.85  3256.7  251.85  3350.7  247.24  3508.1  247.72  3595.6   243.9
  3853.9  239.28  4055.8  235.21  4076.7  233.12  4154.5  236.54  4277.7   236.6
    4501  235.37  4536.9   238.1  4795.9  236.41  4925.3  230.47    4976  229.95
    4982  224.94  4999.8  224.94 5016.51 229.949  5051.7   230.4  5093.1  229.19
  5253.2  233.49  5330.5  233.08  5538.3  234.67  5697.8  241.18  5994.6  242.15
  6093.5   242.8  6369.3   246.7  6390.2  246.83  6512.1  249.72  6669.6  249.61
#Mann= 14 ,-1 , 0
  3135.3     .12       0  3508.1     .05       0  3853.9     .12       0
  4277.7     .05       0  4795.9     .12       0    4976     .07       0
 5016.51     .12       0  5051.7      .1       0  5330.5     .05       0
  5697.8     .12       0  5994.6     .05       0  6093.5     .12       0
  6369.3     .05       0  6390.2     .12       0
Bank Sta=4976,5016.51
XS Rating Curve= 0 ,0
Exp/Cntr=0.3,0.1

Type RM Length L Ch R = 1 ,104500  ,500,500,500
BEGIN DESCRIPTION:
CRYSTAL CREEK 208.0
END DESCRIPTION:
XS GIS Cut Line= 3
       3844713.3     10134892.29      3843933.22      10133198.5
      3841907.78     10133421.78
#Sta/Elev= 30
  3128.7  249.69  3774.7  240.72  3998.5  240.02  4061.2  239.93    4210  234.02
  4296.3  232.96  4319.1  229.51  4330.3  231.08  4363.1  229.66  4376.2   232.5
  4416.7  230.63  4550.3  235.81  4703.2  236.68    4829  230.38  4920.9  230.34
  4935.6  226.56  4943.8  229.18  4949.3  226.36  4966.8  228.99  4970.8  224.47
  4989.1  224.97  4989.3  228.56    5009  225.73  5029.1  228.51  5158.5  228.79
  5432.9  235.85  5579.3  236.11  5795.7  236.49  6765.8  246.94  7031.2  247.35
#Mann= 8 ,-1 , 0
  3128.7     .12       0  3998.5     .05       0  4966.8     .07       0
  4989.1     .05       0  5158.5      .1       0  5432.9     .12       0
  5579.3     .05       0  6765.8     .12       0
Bank Sta=4966.8,4989.3
XS Rating Curve= 0 ,0
Exp/Cntr=0.3,0.1

Type RM Length L Ch R = 1 ,104000  ,500,500,500
BEGIN DESCRIPTION:
CRYSTAL CREEK 207.0
END DESCRIPTION:
XS GIS Cut Line= 3
      3844838.29      10134657.9      3844328.98     10133026.87
      3842264.85      10132724.9
#Sta/Elev= 30
  3291.3  246.24  3560.4  244.74  3864.2  239.49  3944.9  240.07  4105.1  237.79
  4463.5  237.04  4702.3  238.72  4776.2   234.1  4911.8  226.59  4964.2  228.57
  4974.4  223.78  4992.4  223.78  4995.2  225.16  5002.8  225.16  5011.2  228.36
  5031.5  227.34  5061.8  228.81  5193.2  229.36  5352.9  233.61  5506.5  235.53
  5590.9  235.02  5779.3  233.95  5974.5   236.8  6153.3  234.81  6355.4  237.52
  6383.9  239.68  6446.4  237.72  6598.7  236.23  6663.6  237.82  7086.1  238.75
#Mann= 7 ,-1 , 0
  3291.3     .12       0  4463.5     .05       0  4776.2      .1       0
  4964.2     .07       0  5011.2     .05       0  5352.9      .1       0
  5590.9     .05       0
Bank Sta=4964.2,5011.2
XS Rating Curve= 0 ,0
Exp/Cntr=0.3,0.1

Type RM Length L Ch R = 1 ,103500  ,521,521,521
BEGIN DESCRIPTION:
CRYSTAL CREEK 206.0
END DESCRIPTION:
XS GIS Cut Line= 3
      3844998.03     10134407.94       3844624.6     10132770.07
      3842334.26     10132461.01
#Sta/Elev= 30
  3320.1   246.2  3512.1  243.85  3590.4  242.82  3850.2  242.39  4008.3  238.88
  4402.6  234.22  4560.5  236.09    4606  234.86  4792.9   230.2  4809.4  229.44
  4871.8  227.19  4988.7  227.26  5006.8  225.85  5007.9  223.96  5025.9  223.96
    5031  227.42  5144.2  230.58  5243.2  231.58  5370.1  229.92  5482.3  233.32
    5525  232.84  5738.5  234.95  6130.1  234.62  6154.1  234.61  6237.8   234.7
  6651.6  235.02  6722.2  237.04  6828.1  234.23  7115.8  238.41  7311.1  236.96
#Mann= 18 ,-1 , 0
  3320.1     .12       0  3512.1     .05       0  3590.4     .12       0
  4008.3     .05       0  4402.6    .075       0    4606      .1       0
  4792.9     .12       0  4809.4      .1       0  4988.7     .07       0
    5031      .1       0  5144.2     .05       0  5243.2     .12       0
    5525      .1       0  5738.5     .12       0  6130.1      .1       0
  6154.1     .05       0  6237.8    .075       0  6828.1     .05       0
Bank Sta=4988.7,5031
XS Rating Curve= 0 ,0
Exp/Cntr=0.3,0.1

Type RM Length L Ch R = 1 ,102979  ,479,479,479
BEGIN DESCRIPTION:
CRYSTAL CREEK 205.0
END DESCRIPTION:
XS GIS Cut Line= 3
      3846392.45     10133280.26      3844540.79     10132336.73
      3842307.85      10131005.6
#Sta/Elev= 30
  2921.8   239.2  2983.6  238.28  3092.2  237.75  3825.1  230.92    3982  227.52
  4004.4  223.77  4032.4  228.38  4178.6  227.99  4366.4  232.07    4516   235.8
  4719.1  229.16  4938.5     227  4983.1  222.52  5057.8  227.01  5620.4  234.32
  5769.4  228.09  5865.7  226.55  5974.5  229.64  6172.5   229.7  6284.9  228.28
    6319  228.65  6354.3   224.1  6369.8   227.4  6397.2  227.33  6509.5  229.81
  6794.9  235.02  7088.7  239.38  7252.9  241.96  7408.1  245.05  7599.6  250.53
#Mann= 19 ,-1 , 0
  2921.8     .12       0  2983.6    .075       0  3092.2     .12       0
  3825.1      .1       0  4178.6     .12       0  4366.4      .1       0
  4719.1     .12       0  4938.5     .07       0  5057.8      .1       0
  5769.4      .1       0  5974.5     .05       0  6172.5     .12       0
  6284.9      .1       0  6397.2      .1       0  6509.5     .12       0
  6794.9     .05       0  7088.7     .12       0  7252.9     .05       0
  7408.1     .12       0
Bank Sta=4938.5,5057.8
XS Rating Curve= 0 ,0
Exp/Cntr=0.3,0.1

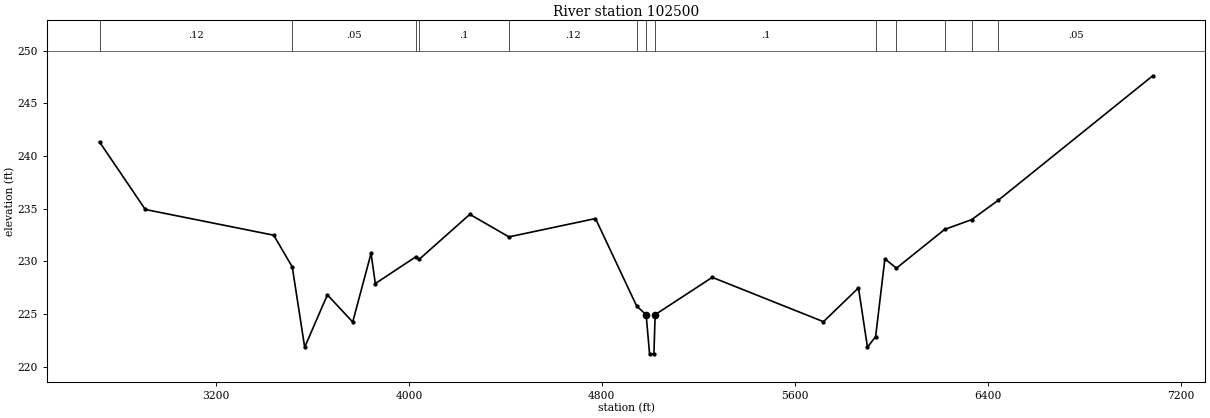
Type RM Length L Ch R = 1 ,102500  ,500,500,500
BEGIN DESCRIPTION:
CRYSTAL CREEK 204.0
END DESCRIPTION:
XS GIS Cut Line= 3
      3846508.43     10132810.68      3844411.37     10131908.21
      3842605.64     10130866.23
#Sta/Elev= 30
    2717  241.34  2906.9  234.93  3439.3  232.49  3516.3  229.48  3567.8  221.86
    3662  226.83    3767  224.25  3843.1  230.77  3860.7   227.9  4029.3  230.45
  4042.3  230.19  4252.7  234.47  4414.9  232.33  4773.8  234.07  4944.5  225.77
  4983.8  224.94  4998.1  221.23  5016.1  221.23 5021.25 224.948  5258.1  228.49
  5719.3  224.28  5864.4  227.49  5901.7  221.86  5935.6  222.87  5973.9  230.25
  6021.8  229.36  6221.9  233.04  6333.4  233.96  6444.9  235.82  7084.8  247.62
#Mann= 13 ,-1 , 0
    2717     .12       0  3516.3     .05       0  4029.3     .12       0
  4042.3      .1       0  4414.9     .12       0  4944.5      .1       0
  4983.8     .07       0 5021.25      .1       0  5935.6     .05       0
  6021.8     .12       0  6221.9     .05       0  6333.4     .12       0
  6444.9     .05       0
Bank Sta=4983.8,5021.25
XS Rating Curve= 0 ,0
Exp/Cntr=0.3,0.1