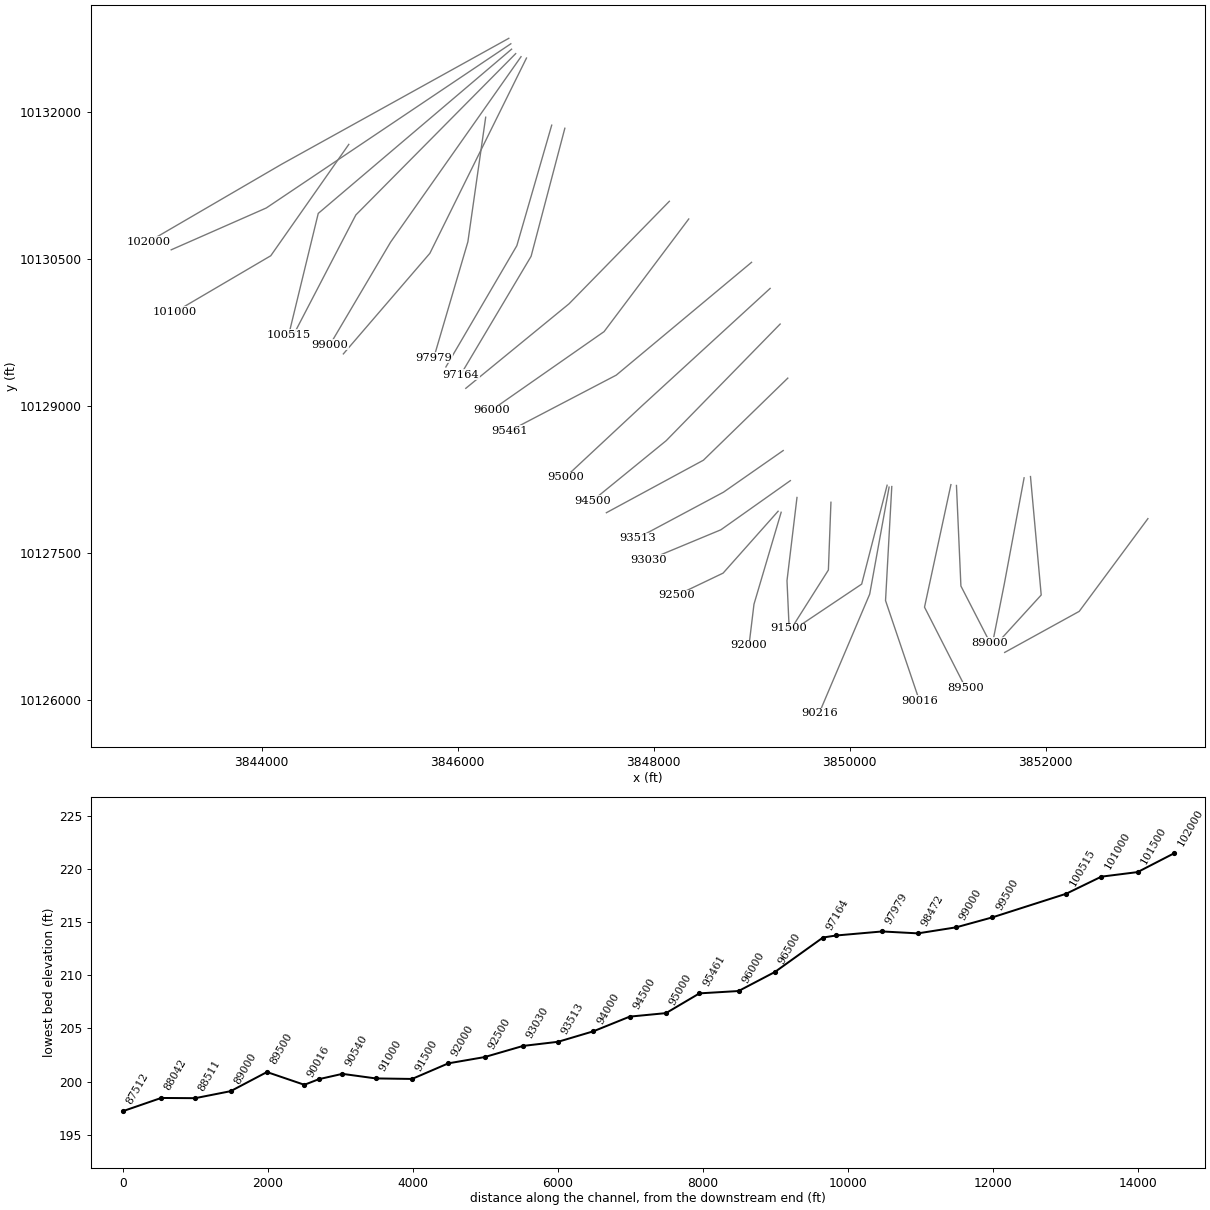
HEC-RAS study CRYSTAL CREEK.prj: CRYSTAL CREEK Base Level Engineering

--- CRYSTAL CREEK.g10 (geometry) --- (continued)

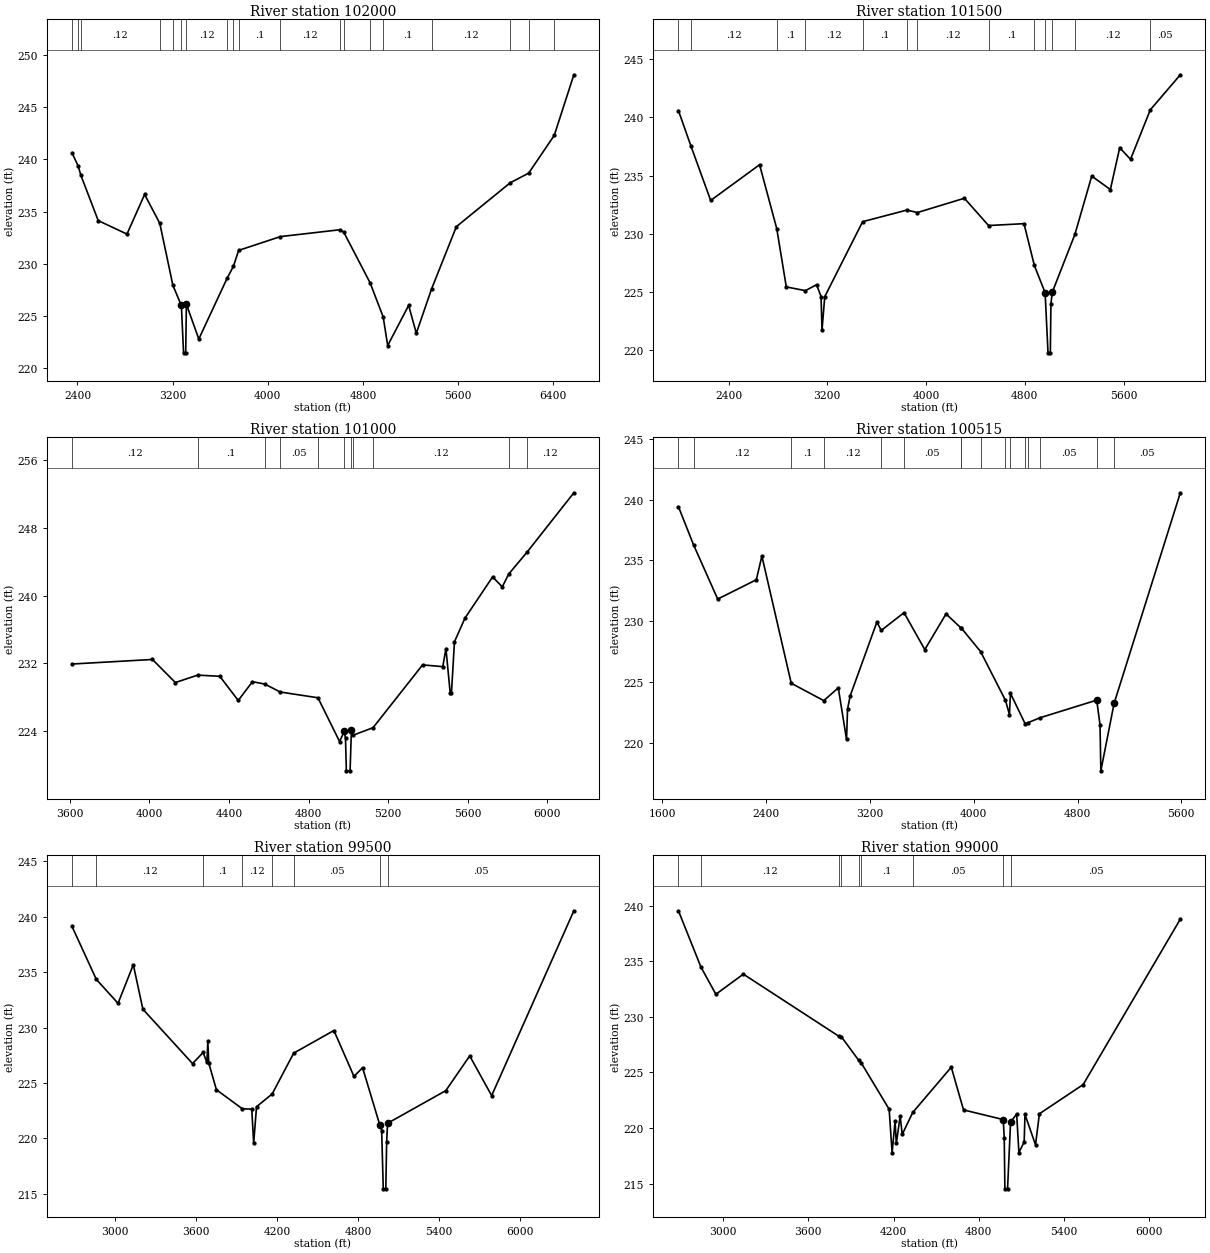
Type RM Length L Ch R = 1 ,102000  ,500,500,500
BEGIN DESCRIPTION:
CRYSTAL CREEK 203.0
END DESCRIPTION:
XS GIS Cut Line= 3
      3846522.35     10132755.14      3844208.23      10131471.5
      3842848.69     10130678.72
#Sta/Elev= 30
  2353.7  240.62  2405.7  239.36  2429.1  238.45  2574.5  234.13  2816.3  232.84
  2964.7  236.63  3092.2  233.87  3202.7  227.93  3273.7  226.01  3292.1  221.48
  3310.2  221.48 3315.97 226.131  3420.2   222.8  3658.2  228.61  3711.5  229.76
  3755.2  231.28  4106.4   232.6  4610.3  233.26  4639.2  233.02  4860.2  228.19
  4970.7  224.91  5008.5  222.18  5184.7  226.02  5249.2  223.35  5377.4  227.59
  5585.8  233.55  6037.9  237.74    6194  238.67  6408.9  242.28  6573.8  248.08
#Mann= 19 ,-1 , 0
  2353.7     .12       0  2405.7     .05       0  2429.1     .12       0
  3092.2      .1       0  3202.7     .05       0  3273.7     .07       0
 3315.97     .12       0  3658.2      .1       0  3711.5     .12       0
  3755.2      .1       0  4106.4     .12       0  4610.3     .05       0
  4639.2     .12       0  4860.2     .05       0  4970.7      .1       0
  5377.4     .12       0  6037.9     .05       0    6194     .05       0
  6408.9     .12       0
Bank Sta=3273.7,3315.97
XS Rating Curve= 0 ,0
Exp/Cntr=0.3,0.1

Type RM Length L Ch R = 1 ,101500  ,500,500,500
BEGIN DESCRIPTION:
CRYSTAL CREEK 202.0
END DESCRIPTION:
XS GIS Cut Line= 3
      3846543.16     10132699.57      3844048.25     10131022.83
      3843078.64     10130595.74
#Sta/Elev= 30
    1994   240.6  2095.1  237.55  2255.4  232.85  2651.4  235.93  2790.6  230.42
  2867.9   225.4  3022.5  225.08  3113.3  225.59  3149.3  224.57  3157.1  221.68
  3179.3  224.56  3486.1  231.02  3843.8  232.02    3930  231.81  4310.3  233.04
  4506.2  230.69  4793.3  230.85  4877.1  227.25  4964.3   224.9  4987.9  219.72
  5006.6  219.72  5011.3  223.94  5022.3  224.94  5205.7  229.93    5342  234.95
  5492.9  233.79  5568.6   237.4  5656.1  236.39  5816.3  240.66  6059.5  243.68
#Mann= 13 ,-1 , 0
    1994     .05       0  2095.1     .12       0  2790.6      .1       0
  3022.5     .12       0  3486.1      .1       0  3843.8     .05       0
    3930     .12       0  4506.2      .1       0  4877.1     .12       0
  4964.3     .07       0  5022.3      .1       0  5205.7     .12       0
  5816.3     .05       0
Bank Sta=4964.3,5022.3
XS Rating Curve= 0 ,0
Exp/Cntr=0.3,0.1

Type RM Length L Ch R = 1 ,101000  ,485,485,485
BEGIN DESCRIPTION:
CRYSTAL CREEK 201.0
END DESCRIPTION:
XS GIS Cut Line= 3
      3844890.22     10131672.17      3844094.17     10130535.01
      3843117.87     10129961.08
#Sta/Elev= 30
  3611.9  231.92  4016.1  232.46  4131.2  229.73  4243.4  230.61  4354.4  230.47
  4446.9  227.61  4518.4  229.83  4580.5  229.55  4657.9  228.61  4847.4  227.93
    4956  222.75  4979.6  223.98  4985.7  223.13    4990  219.29  5008.7  219.29
  5015.4  224.15  5024.3  223.51    5124  224.39  5372.8  231.82  5474.3  231.61
    5490  233.75  5511.4  228.54  5517.7  228.46  5532.9  234.55  5585.7  237.35
  5724.4  242.22  5773.1  241.05  5805.7  242.57  5897.1  245.14  6132.5  252.17
#Mann= 11 ,-1 , 0
  3611.9     .12       0  4243.4      .1       0  4580.5     .12       0
  4657.9     .05       0  4847.4     .12       0  4979.6     .07       0
  5015.4     .12       0  5024.3     .05       0    5124     .12       0
  5805.7     .05       0  5897.1     .12       0
Bank Sta=4979.6,5015.4
XS Rating Curve= 0 ,0
Exp/Cntr=0.3,0.1

Type RM Length L Ch R = 1 ,100515  ,1015,1015,1015
BEGIN DESCRIPTION:
CRYSTAL CREEK 200.0
END DESCRIPTION:
XS GIS Cut Line= 3
      3846550.77     10132644.43      3844578.57     10130967.36
       3844276.7     10129725.16
#Sta/Elev= 30
  1724.7  239.43  1841.1  236.29  2027.4  231.82    2325  233.41  2367.8  235.36
  2593.9  224.89  2844.8  223.46  2956.5  224.51  3020.2  220.26  3027.9  222.77
  3048.7  223.87  3254.1  229.93  3287.3  229.24  3463.1   230.7  3623.1  227.66
  3786.8   230.6  3899.1  229.47  3904.1  229.44  4052.8   227.5  4244.8  223.48
  4275.4  222.31    4283  224.06    4396  221.56  4419.6  221.65  4511.1  222.05
  4947.8   223.5  4973.2  221.46  4979.5  217.68  5081.6  223.23  5591.9  240.57
#Mann= 16 ,-1 , 0
  1724.7     .05       0  1841.1     .12       0  2593.9      .1       0
  2844.8     .12       0  3287.3      .1       0  3463.1     .05       0
  3899.1     .12       0  3904.1     .05       0  4052.8     .12       0
  4244.8      .1       0    4283     .05       0    4396      .1       0
  4419.6     .12       0  4511.1     .05       0  4947.8     .07       0
  5081.6     .05       0
Bank Sta=4947.8,5081.6
XS Rating Curve= 0 ,0
Exp/Cntr=0.3,0.1

Type RM Length L Ch R = 1 ,99500   ,500,500,500
BEGIN DESCRIPTION:
CRYSTAL CREEK 198.0
END DESCRIPTION:
XS GIS Cut Line= 3
      3846592.61     10132598.85      3844961.94     10130951.41
      3844317.85     10129711.07
#Sta/Elev= 30
    2682  239.12  2862.2  234.34  3023.2  232.18  3136.3  235.66  3207.1  231.65
  3574.8  226.75  3653.3  227.75  3680.8  226.85  3687.9  228.75  3694.9  226.79
  3751.5  224.39  3942.8  222.68  4013.2  222.64  4027.3  219.58  4048.5  222.86
  4164.1  224.01  4323.6  227.69  4621.3  229.73  4769.8  225.59  4833.4  226.38
  4960.7  221.23  4974.8  220.71  4986.7  215.46  5005.5  215.46  5011.6  219.65
  5018.5  221.37  5449.6  224.31  5626.5  227.44  5789.1  223.86  6397.6  240.52
#Mann= 8 ,-1 , 0
    2682     .05       0  2862.2     .12       0  3653.3      .1       0
  3942.8     .12       0  4164.1      .1       0  4323.6     .05       0
  4960.7     .07       0  5018.5     .05       0
Bank Sta=4960.7,5018.5
XS Rating Curve= 0 ,0
Exp/Cntr=0.3,0.1

Type RM Length L Ch R = 1 ,99000   ,528,528,528
BEGIN DESCRIPTION:
CRYSTAL CREEK 197.0
END DESCRIPTION:
XS GIS Cut Line= 3
      3846647.35     10132567.66      3845316.31     10130673.82
      3844696.76     10129624.58
#Sta/Elev= 30
  2685.2  239.53  2843.7  234.47  2948.9  232.02  3142.3  233.83  3815.3  228.24
  3831.4  228.22  3954.9  226.07  3973.5  225.82  4168.7  221.68  4189.6  217.76
  4210.5  220.61  4219.2   218.6  4246.2  221.06    4261  219.42  4334.8  221.39
  4606.1  225.46  4692.3  221.62    4972  220.75  4978.9  219.09  4983.5  214.52
  5002.3  214.52  5023.5  220.53  5066.4  221.25  5082.1  217.78  5119.2  218.74
    5125  221.21  5199.1  218.48  5226.4  221.27  5534.7   223.9  6218.5  238.78
#Mann= 9 ,-1 , 0
  2685.2     .05       0  2843.7     .12       0  3815.3      .1       0
  3831.4     .12       0  3954.9     .05       0  3973.5      .1       0
  4334.8     .05       0    4972     .05       0  5023.5     .05       0
Bank Sta=4972,5023.5
XS Rating Curve= 0 ,0
Exp/Cntr=0.3,0.1

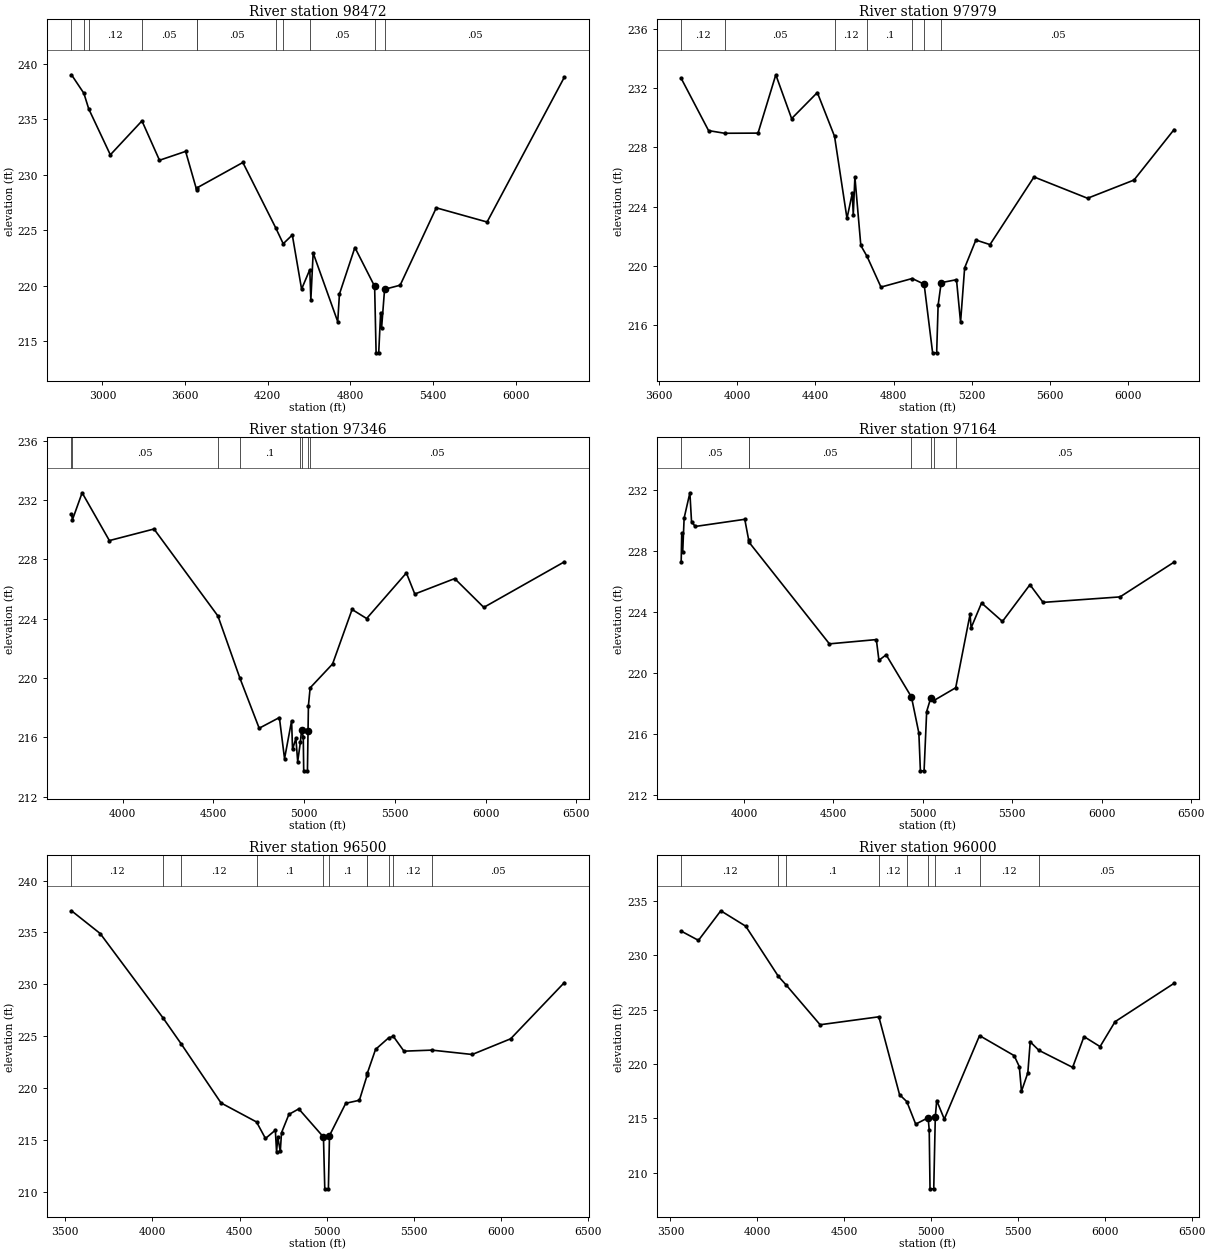
Type RM Length L Ch R = 1 ,98472   ,493,493,493
BEGIN DESCRIPTION:
CRYSTAL CREEK 196.0
END DESCRIPTION:
XS GIS Cut Line= 3
      3846702.88     10132553.74      3845717.15     10130559.78
      3844834.81     10129532.89
#Sta/Elev= 30
  2775.7  239.03  2865.6  237.36  2900.9  235.95  3057.6  231.81  3287.2  234.87
  3414.5  231.32  3604.2  232.12  3683.4  228.68  3688.1  228.84  4019.7  231.12
  4257.2  225.25  4312.7  223.79  4378.7  224.58    4446   219.7  4505.6  221.45
  4513.3  218.74    4530  222.96  4708.5  216.76  4720.8  219.25    4833  223.45
  4976.3  219.95    4987  213.95  5005.9  213.95    5020  217.58  5026.6  216.15
  5048.5  219.68  5161.6  220.05  5423.8  227.03  5792.6  225.75  6353.9  238.82
#Mann= 11 ,-1 , 0
  2775.7     .12       0  2865.6     .05       0  2900.9     .12       0
  3287.2     .05       0  3683.4     .12       0  3688.1     .05       0
  4257.2     .12       0  4312.7      .1       0  4505.6     .05       0
  4976.3     .05       0  5048.5     .05       0
Bank Sta=4976.3,5048.5
XS Rating Curve= 0 ,0
Exp/Cntr=0.3,0.1

Type RM Length L Ch R = 1 ,97979   ,633,633,633
BEGIN DESCRIPTION:
CRYSTAL CREEK 195.0
END DESCRIPTION:
XS GIS Cut Line= 3
      3846286.59     10131949.62      3846105.07      10130677.6
      3845757.53     10129494.59
#Sta/Elev= 30
  3715.1  232.67    3855  229.14  3936.9  228.96  4107.6  228.97  4198.5  232.91
  4279.3  229.95  4410.6  231.71  4498.6  228.75  4562.1  223.21  4589.2  224.91
  4594.2  223.45  4602.5  226.01  4632.8  221.38  4664.7  220.64  4735.7  218.57
  4895.1  219.15  4956.1  218.77  4999.6  214.13  5020.2  214.13  5027.7  217.35
  5043.3  218.87  5121.5  219.07  5142.3   216.2  5163.1  219.87  5220.6  221.75
  5292.6  221.44  5517.5  226.01    5791  224.57  6028.2   225.8    6233  229.21
#Mann= 7 ,-1 , 0
  3715.1     .12       0  3936.9     .05       0  4498.6     .12       0
  4664.7      .1       0  4895.1     .05       0  4956.1     .07       0
  5043.3     .05       0
Bank Sta=4956.1,5043.3
XS Rating Curve= 0 ,0
Exp/Cntr=0.3,0.1

Type RM Length L Ch R = 1 ,97346   ,182,182,182
BEGIN DESCRIPTION:
CRYSTAL CREEK 194.0
END DESCRIPTION:
XS GIS Cut Line= 3
       3846960.2     10131868.63      3846604.46     10130637.81
      3845880.68     10129399.52
#Sta/Elev= 30
  3718.8  231.03  3724.2  230.67  3777.4  232.48  3927.5  229.26  4173.3  230.04
  4525.5  224.18  4646.4     220  4752.8  216.62  4864.1  217.34  4892.5  214.57
  4931.4  217.12  4936.6  215.19    4955  215.94    4965  214.37  4979.8  215.68
  4986.2  216.48  4995.7  216.05  4998.1  213.75  5018.7  213.75 5021.99 216.465
  5024.1  218.14  5033.5  219.34  5157.2  220.95  5264.6  224.62  5344.8  224.01
  5563.8  227.08  5610.1  225.66  5829.9   226.7  5990.3  224.76  6434.3  227.83
#Mann= 8 ,-1 , 0
  3718.8      .1       0  3724.2     .05       0  4525.5     .12       0
  4646.4      .1       0  4979.8     .05       0  4986.2     .07       0
 5021.99     .05       0  5033.5     .05       0
Bank Sta=4986.2,5021.99
XS Rating Curve= 0 ,0
Exp/Cntr=0.3,0.1

Type RM Length L Ch R = 1 ,97164   ,664,664,664
BEGIN DESCRIPTION:
CRYSTAL CREEK 193.0
END DESCRIPTION:
XS GIS Cut Line= 3
      3847094.24     10131837.02        3846750.     10130529.37
      3846031.89     10129321.17
#Sta/Elev= 30
  3647.8  227.28    3651  229.17  3656.2  227.89  3664.3  230.14  3696.5   231.8
  3705.7  229.91  3726.3  229.59  4003.6  230.06  4025.5   228.7  4028.6  228.54
  4477.1  221.89  4739.7  222.17  4754.2  220.81  4794.5  221.17  4936.2   218.4
  4977.6  216.04  4986.2  213.56  5006.8  213.56  5021.3  217.45  5044.6  218.36
  5059.8  218.16  5183.7  219.01  5264.1  223.83  5269.9  222.94  5328.4  224.57
  5445.2  223.36  5599.1  225.77  5672.7  224.61  6103.2  224.97  6405.5  227.25
#Mann= 7 ,-1 , 0
  3647.8     .05       0  4025.5     .12       0  4028.6     .05       0
  4936.2     .07       0  5044.6     .05       0  5059.8      .1       0
  5183.7     .05       0
Bank Sta=4936.2,5044.6
XS Rating Curve= 0 ,0
Exp/Cntr=0.3,0.1

Type RM Length L Ch R = 1 ,96500   ,500,500,500
BEGIN DESCRIPTION:
CRYSTAL CREEK 192.0
END DESCRIPTION:
XS GIS Cut Line= 3
      3848160.25      10131091.1      3847137.47     10130044.88
      3846083.82     10129181.35
#Sta/Elev= 30
  3536.9  237.09  3701.3   234.9  4062.1  226.76  4167.4  224.23  4394.2  218.58
  4597.6  216.75  4648.8  215.16  4705.4  215.96  4712.4  213.87  4719.6  215.28
  4733.7  213.91  4740.7  215.71  4783.1  217.48  4839.7  218.01  4981.2   215.3
  4988.8  210.31  5009.5  210.31 5015.75 215.437    5109  218.55  5187.2  218.84
  5231.5  221.25    5233  221.46  5279.8  223.74  5355.3  224.86    5382  224.99
  5442.7  223.57  5602.7  223.67  5833.8  223.25  6054.2  224.76  6362.3  230.18
#Mann= 11 ,-1 , 0
  3536.9     .12       0  4062.1     .05       0  4167.4     .12       0
  4597.6      .1       0  4981.2     .07       0 5015.75      .1       0
  5231.5     .05       0    5233     .12       0  5355.3      .1       0
    5382     .12       0  5602.7     .05       0
Bank Sta=4981.2,5015.75
XS Rating Curve= 0 ,0
Exp/Cntr=0.3,0.1

Type RM Length L Ch R = 1 ,96000   ,539,539,539
BEGIN DESCRIPTION:
CRYSTAL CREEK 191.0
END DESCRIPTION:
XS GIS Cut Line= 3
      3848358.15     10130910.53      3847494.43     10129760.33
      3846347.78     10128959.18
#Sta/Elev= 30
  3561.6  232.22    3661  231.37  3789.6  234.09  3933.3  232.67    4121  228.06
  4164.6  227.29  4361.3  223.61  4699.4  224.34  4818.6  217.18  4860.4  216.54
  4911.5  214.47  4983.1  215.06  4989.4  213.93    4994  208.52  5015.4  208.52
  5024.3 215.103  5032.4  216.64  5076.2  214.93    5279  222.61  5478.3  220.77
  5507.9  219.76  5520.4  217.49    5557  219.19  5570.7  222.04  5620.5  221.26
  5814.9  219.69  5880.3  222.52  5972.8   221.6  6059.1  223.89  6398.8  227.42
#Mann= 9 ,-1 , 0
  3561.6     .12       0    4121     .05       0  4164.6      .1       0
  4699.4     .12       0  4860.4      .1       0  4983.1     .07       0
  5024.3      .1       0    5279     .12       0  5620.5     .05       0
Bank Sta=4983.1,5024.3
XS Rating Curve= 0 ,0
Exp/Cntr=0.3,0.1

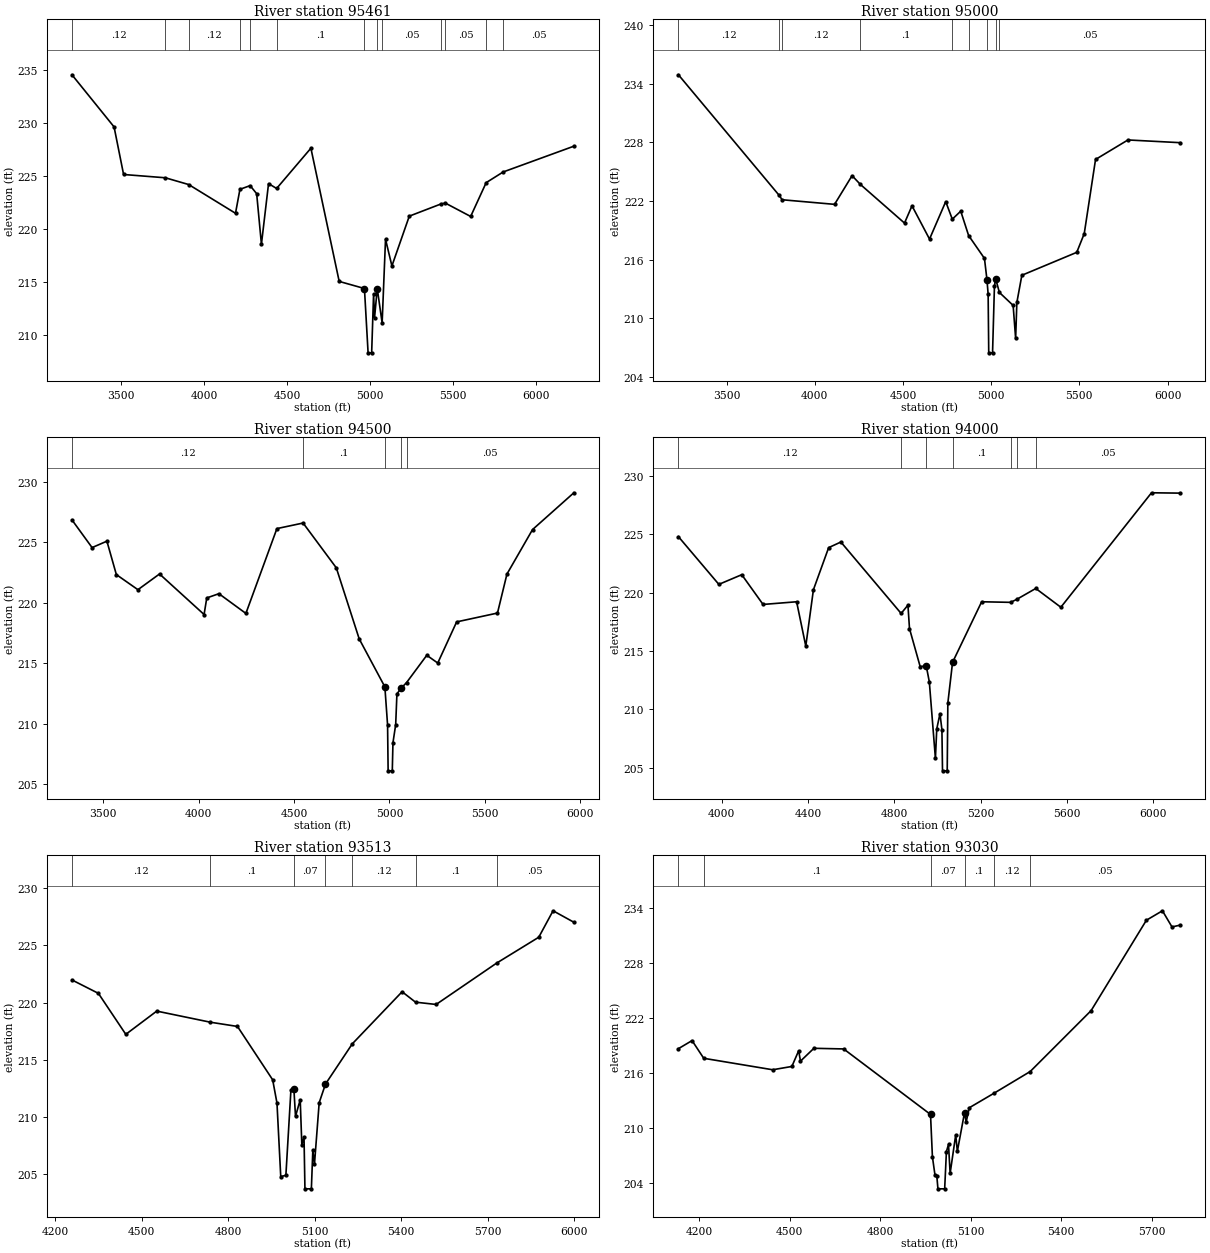
Type RM Length L Ch R = 1 ,95461   ,461,461,461
BEGIN DESCRIPTION:
CRYSTAL CREEK 190.0
END DESCRIPTION:
XS GIS Cut Line= 3
      3848998.77     10130467.82      3847618.57     10129315.95
      3846532.13     10128747.88
#Sta/Elev= 30
  3202.3  234.54  3456.1  229.62  3513.4  225.13    3765  224.82  3905.8  224.18
  4187.6  221.47  4214.3  223.73  4275.7  224.08  4315.1  223.32  4343.8  218.55
  4386.7  224.27  4435.3  223.81  4641.8  227.61  4812.3  215.04  4964.4  214.37
  4986.4   208.3  5007.9   208.3  5019.5  213.87  5025.2   211.6  5041.6  214.37
    5071  211.12  5091.4  219.02  5129.9   216.5  5234.6   221.2  5425.7  222.35
  5451.9  222.43  5604.3  221.17  5697.7  224.36  5800.4  225.37    6226   227.8
#Mann= 13 ,-1 , 0
  3202.3     .12       0    3765     .05       0  3905.8     .12       0
  4214.3     .05       0  4275.7     .12       0  4435.3      .1       0
  4964.4     .07       0  5041.6      .1       0    5071     .05       0
  5425.7    .075       0  5451.9     .05       0  5697.7    .075       0
  5800.4     .05       0
Bank Sta=4964.4,5041.6
XS Rating Curve= 0 ,0
Exp/Cntr=0.3,0.1

Type RM Length L Ch R = 1 ,95000   ,500,500,500
BEGIN DESCRIPTION:
CRYSTAL CREEK 189.0
END DESCRIPTION:
XS GIS Cut Line= 3
      3849188.31     10130201.42      3847881.85     10129003.24
      3847097.74     10128271.65
#Sta/Elev= 30
  3227.3  234.94  3796.6  222.62  3815.5  222.13  4112.4  221.66  4211.7   224.6
  4258.3  223.71  4508.9  219.74  4551.4  221.51  4650.7   218.1  4742.6  221.94
  4779.8  220.14  4827.7  220.96  4872.4  218.46  4962.1  216.12  4976.3  213.94
    4983  212.45  4986.4  206.44    5008  206.44  5018.7  213.26  5025.6  214.04
  5046.7  212.63  5124.7   211.3  5138.9  207.91  5145.8   211.6  5174.1  214.39
  5485.3  216.74  5527.8  218.66  5591.8  226.26  5775.5  228.26  6072.4  227.98
#Mann= 9 ,-1 , 0
  3227.3     .12       0  3796.6     .05       0  3815.5     .12       0
  4258.3      .1       0  4779.8     .12       0  4872.4      .1       0
  4976.3     .07       0  5025.6      .1       0  5046.7     .05       0
Bank Sta=4976.3,5025.6
XS Rating Curve= 0 ,0
Exp/Cntr=0.3,0.1

Type RM Length L Ch R = 1 ,94500   ,500,500,500
BEGIN DESCRIPTION:
CRYSTAL CREEK 188.0
END DESCRIPTION:
XS GIS Cut Line= 3
      3849290.44     10129837.61      3848128.07     10128646.76
      3847379.31      10128035.8
#Sta/Elev= 30
  3335.9  226.85  3441.4  224.56  3519.1  225.09  3568.6  222.33  3681.7  221.08
  3794.9  222.38  4028.4  219.03  4042.5   220.4  4106.1  220.75  4247.5  219.12
  4410.1  226.13  4547.3  226.59  4721.3  222.89  4841.5  217.01  4975.9  213.05
  4990.1   209.9    4993  206.11  5014.8  206.11  5018.3  208.43  5032.6  209.93
  5039.1  212.47  5061.4  212.94  5089.9  213.41  5195.6  215.66  5253.1  215.02
  5352.1  218.42  5566.1  219.15  5615.7  222.37  5749.9  226.05  5966.4  229.09
#Mann= 5 ,-1 , 0
  3335.9     .12       0  4547.3      .1       0  4975.9     .07       0
  5061.4      .1       0  5089.9     .05       0
Bank Sta=4975.9,5061.4
XS Rating Curve= 0 ,0
Exp/Cntr=0.3,0.1

Type RM Length L Ch R = 1 ,94000   ,487,487,487
BEGIN DESCRIPTION:
CRYSTAL CREEK 187.0
END DESCRIPTION:
XS GIS Cut Line= 3
      3849368.56     10129285.53      3848507.93     10128447.41
      3847517.87     10127911.08
#Sta/Elev= 30
  3798.7   224.8  3986.2  220.71  4092.4  221.54  4191.2  218.99  4346.8  219.22
  4389.3  215.42  4424.7  220.25  4495.4  223.86    4552  224.34  4831.4  218.22
    4863  218.93  4870.2  216.92  4919.6  213.67  4947.9  213.72  4962.1  212.36
  4990.4  205.79  4996.6  208.32  5011.5  209.63  5020.5  208.27  5023.3  204.73
  5045.1  204.73    5048  210.54  5069.9  214.03  5204.8  219.22  5338.9  219.17
  5366.9  219.42  5455.7  220.36    5572  218.75  5992.4  228.56    6126  228.53
#Mann= 7 ,-1 , 0
  3798.7     .12       0  4831.4      .1       0  4947.9     .07       0
  5069.9      .1       0  5338.9     .05       0  5366.9      .1       0
  5455.7     .05       0
Bank Sta=4947.9,5069.9
XS Rating Curve= 0 ,0
Exp/Cntr=0.3,0.1

Type RM Length L Ch R = 1 ,93513   ,483,483,483
BEGIN DESCRIPTION:
CRYSTAL CREEK 186.0
END DESCRIPTION:
XS GIS Cut Line= 3
      3849321.73     10128545.98      3848713.29     10128121.28
      3847832.49     10127650.33
#Sta/Elev= 30
    4258  221.98  4349.7  220.81  4444.8  217.23  4552.1  219.26  4738.1  218.29
  4832.1  217.92  4954.2  213.26  4969.1  211.23  4982.2  204.81    5000  204.92
  5017.5  212.37  5027.7  212.48  5033.4  210.07  5049.7  211.52  5055.3  207.58
  5062.9  208.27  5066.1  203.74  5088.4  203.74  5093.5  207.13  5099.2  205.91
  5115.5  211.26  5137.4  212.89  5230.3   216.4  5403.1  220.95  5449.6  220.04
  5521.1  219.84  5730.9  223.45  5877.1  225.71  5926.7  228.02  5998.8  227.02
#Mann= 7 ,-1 , 0
    4258     .12       0  4738.1      .1       0  5027.7     .07       0
  5137.4      .1       0  5230.3     .12       0  5449.6      .1       0
  5730.9     .05       0
Bank Sta=5027.7,5137.4
XS Rating Curve= 0 ,0
Exp/Cntr=0.3,0.1

Type RM Length L Ch R = 1 ,93030   ,530,530,530
BEGIN DESCRIPTION:
CRYSTAL CREEK 185.0
END DESCRIPTION:
XS GIS Cut Line= 3
      3849394.65     10128238.69      3848686.14     10127736.92
      3847952.34     10127431.56
#Sta/Elev= 30
  4131.8  218.63    4177  219.51  4215.7  217.58  4444.1  216.33  4507.7  216.69
  4530.2   218.4  4536.3  217.27  4580.7  218.67  4679.3   218.6  4967.1  211.46
  4973.4  206.84  4981.8  204.88    4988  204.74  4991.7  203.35    5014  203.35
  5019.8  207.42  5026.7  208.19  5032.1  205.04  5050.6  209.23    5056  207.44
  5079.8  211.66  5085.2  210.63  5095.6  212.19  5176.4  213.75  5297.5  216.14
  5499.3  222.78  5682.4  232.63  5735.5  233.66  5767.2   231.9  5794.8   232.1
#Mann= 6 ,-1 , 0
  4131.8     .12       0  4215.7      .1       0  4967.1     .07       0
  5079.8      .1       0  5176.4     .12       0  5297.5     .05       0
Bank Sta=4967.1,5079.8
XS Rating Curve= 0 ,0
Exp/Cntr=0.3,0.1

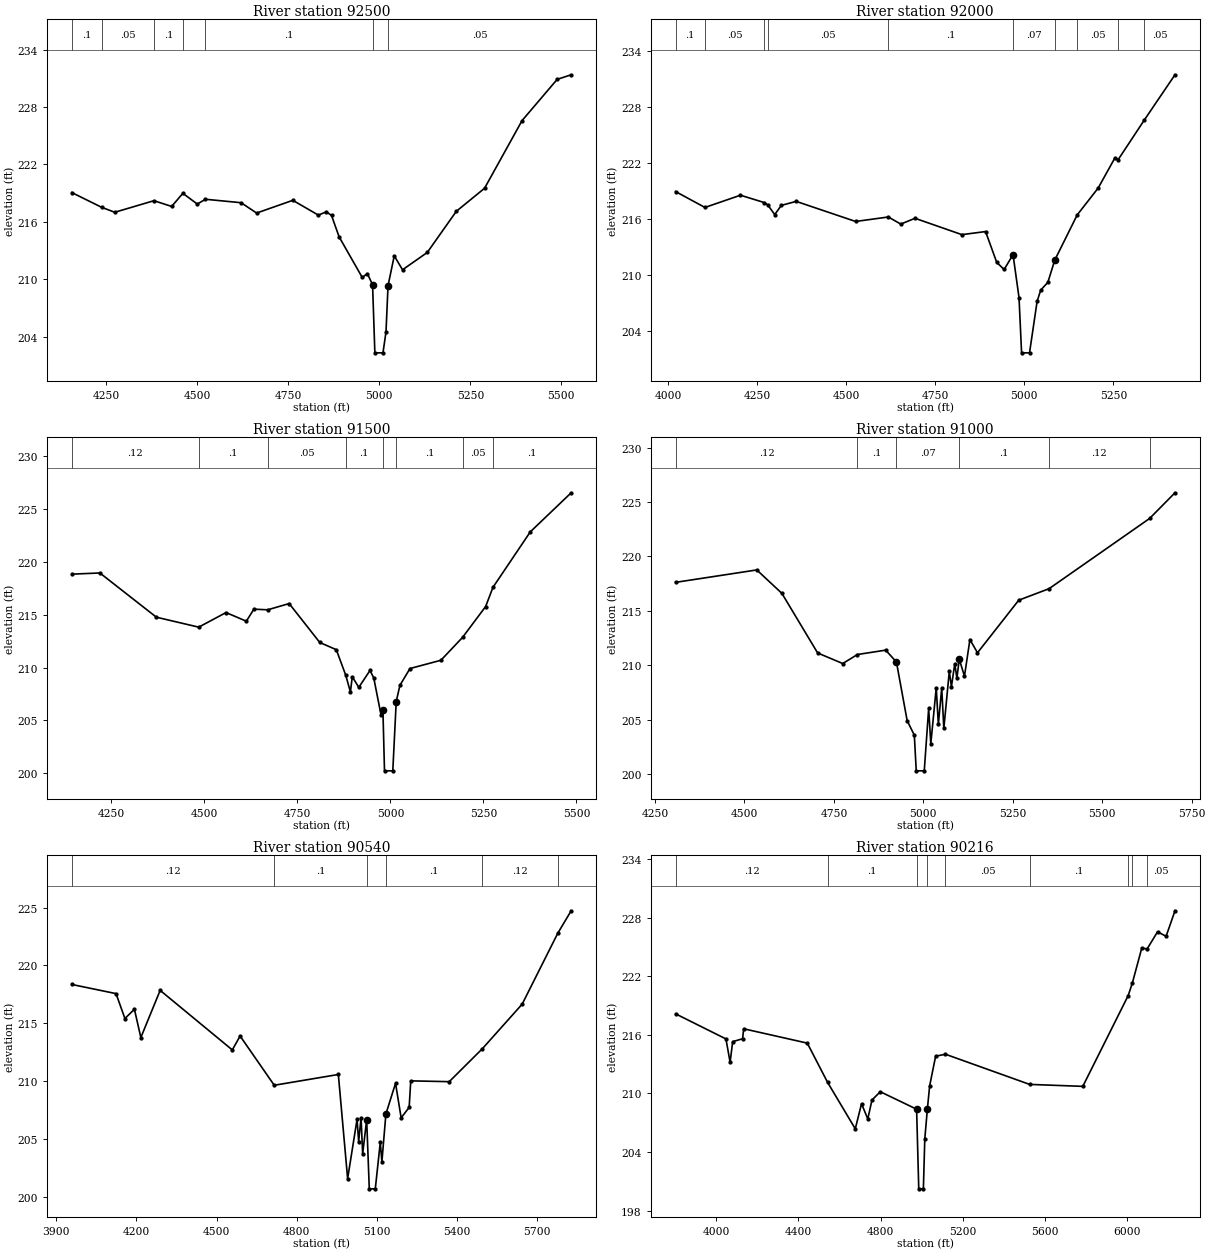
Type RM Length L Ch R = 1 ,92500   ,500,500,500
BEGIN DESCRIPTION:
CRYSTAL CREEK 184.0
END DESCRIPTION:
XS GIS Cut Line= 3
       3849269.6     10127926.15      3848708.61     10127294.37
      3848233.16      10127066.8
#Sta/Elev= 30
  4155.1  219.05    4237  217.51  4273.1  216.99  4380.7   218.2  4429.4   217.6
  4460.2  218.97  4499.8  217.85  4522.3  218.35  4620.2  217.99  4662.8  216.91
  4762.3  218.24  4832.6  216.69  4854.3  217.04  4868.6  216.66  4889.5  214.42
    4953  210.18  4967.2  210.58  4981.4  209.41  4987.7   202.3    5010   202.3
  5018.3  204.49  5023.9  209.32    5041  212.44  5063.7  210.98  5131.7  212.79
  5211.5  217.09  5289.1   219.5  5392.1  226.57  5488.6  230.88  5527.1  231.36
#Mann= 7 ,-1 , 0
  4155.1      .1       0    4237     .05       0  4380.7      .1       0
  4460.2     .05       0  4522.3      .1       0  4981.4     .07       0
  5023.9     .05       0
Bank Sta=4981.4,5023.9
XS Rating Curve= 0 ,0
Exp/Cntr=0.3,0.1

Type RM Length L Ch R = 1 ,92000   ,500,500,500
BEGIN DESCRIPTION:
CRYSTAL CREEK 183.0
END DESCRIPTION:
XS GIS Cut Line= 3
      3849300.87     10127915.75      3849023.61     10126976.83
       3848972.8      10126556.8
#Sta/Elev= 30
    4021  218.97  4103.3  217.27  4203.1  218.58  4269.3   217.8  4279.5  217.55
  4299.3  216.51  4317.8  217.49  4359.5  217.92  4526.4  215.77  4618.2  216.25
  4653.2  215.49  4693.2  216.11  4824.8  214.36  4891.3  214.69  4922.6  211.39
  4943.4  210.63  4968.4  212.22  4985.2  207.62  4992.4  201.71  5014.7  201.71
    5036  207.22  5046.1  208.42  5066.2  209.26  5085.5  211.63  5148.7  216.48
  5207.3  219.34  5254.4  222.57  5263.1  222.36  5337.4  226.65  5423.1  231.47
#Mann= 10 ,-1 , 0
    4021      .1       0  4103.3     .05       0  4269.3      .1       0
  4279.5     .05       0  4618.2      .1       0  4968.4     .07       0
  5085.5      .1       0  5148.7     .05       0  5263.1      .1       0
  5337.4     .05       0
Bank Sta=4968.4,5085.5
XS Rating Curve= 0 ,0
Exp/Cntr=0.3,0.1

Type RM Length L Ch R = 1 ,91500   ,500,500,500
BEGIN DESCRIPTION:
CRYSTAL CREEK 182.0
END DESCRIPTION:
XS GIS Cut Line= 3
      3849462.33     10128066.77      3849360.37     10127216.77
      3849382.47     10126731.37
#Sta/Elev= 30
  4143.9  218.83  4219.3  218.94  4371.2  214.76  4484.9  213.82  4558.4   215.2
  4612.9  214.38  4633.1  215.52  4670.3  215.46    4728  216.05  4810.3  212.37
  4854.7  211.69  4879.8   209.3  4892.6   207.7  4897.6  209.13  4915.1  208.13
  4945.3  209.73  4955.4  209.01  4974.8  205.54  4979.9  206.03  4984.2  200.24
  5006.5  200.24  5015.7  206.79  5025.7  208.33  5052.7  209.91  5135.8  210.69
  5193.9  212.85    5256  215.77  5275.6  217.58  5376.1  222.83  5485.9  226.52
#Mann= 8 ,-1 , 0
  4143.9     .12       0  4484.9      .1       0  4670.3     .05       0
  4879.8      .1       0  4979.9     .07       0  5015.7      .1       0
  5193.9     .05       0  5275.6      .1       0
Bank Sta=4979.9,5015.7
XS Rating Curve= 0 ,0
Exp/Cntr=0.3,0.1

Type RM Length L Ch R = 1 ,91000   ,460,460,460
BEGIN DESCRIPTION:
CRYSTAL CREEK 181.0
END DESCRIPTION:
XS GIS Cut Line= 3
      3849808.68     10128017.83      3849782.59     10127325.93
      3849406.76     10126731.35
#Sta/Elev= 30
  4307.6  217.61  4534.5  218.75  4604.6   216.6  4704.6  211.12  4774.7  210.15
  4815.9  210.98  4894.8  211.38  4924.8  210.29  4954.8   204.9  4974.8  203.57
  4980.2  200.29  5002.6  200.29  5014.9  206.02  5020.9  202.78  5036.1  207.92
    5042  204.56  5051.4  207.89  5057.3  204.19  5072.6  209.43  5078.5  208.02
  5087.9  210.14  5093.8  208.79  5100.4  210.55    5115  208.99  5130.2  212.35
  5151.4  211.14  5266.7  215.97  5351.6  217.03  5632.5  223.48  5703.4  225.84
#Mann= 6 ,-1 , 0
  4307.6     .12       0  4815.9      .1       0  4924.8     .07       0
  5100.4      .1       0  5351.6     .12       0  5632.5      .1       0
Bank Sta=4924.8,5100.4
XS Rating Curve= 0 ,0
Exp/Cntr=0.3,0.1

Type RM Length L Ch R = 1 ,90540   ,324,324,324
BEGIN DESCRIPTION:
CRYSTAL CREEK 180.0
END DESCRIPTION:
XS GIS Cut Line= 3
       3850381.6     10128191.44      3850122.26     10127182.12
      3849434.57     10126720.97
#Sta/Elev= 30
  3957.9  218.36  4123.5  217.57  4156.7  215.42  4192.3  216.22  4216.4  213.78
  4288.7  217.85  4558.9  212.71  4588.1  213.91    4716  209.66    4956  210.59
  4990.8   201.6  5026.1  206.72  5032.1   204.8  5041.1  206.86  5047.1  203.74
  5062.1  206.69  5071.9  200.72  5094.4  200.72  5113.1  204.74  5119.1  203.06
  5134.1  207.18  5170.2  209.83  5191.2  206.85  5221.2  207.75  5227.2  210.04
  5371.3  209.97  5495.6  212.82  5644.4  216.66    5778  222.79    5828  224.72
#Mann= 6 ,-1 , 0
  3957.9     .12       0    4716      .1       0  5062.1     .07       0
  5134.1      .1       0  5495.6     .12       0    5778      .1       0
Bank Sta=5062.1,5134.1
XS Rating Curve= 0 ,0
Exp/Cntr=0.3,0.1

Type RM Length L Ch R = 1 ,90216   ,200,200,200
BEGIN DESCRIPTION:
Mapping XS 095e7c73
END DESCRIPTION:
XS GIS Cut Line= 3
       3850401.9     10128172.34      3850204.01     10127079.65
      3849687.75     10125862.15
#Sta/Elev= 30
  3801.5  218.15  4046.7  215.58    4067  213.19  4079.5   215.3  4127.9   215.6
    4133  216.62    4443  215.15  4541.6  211.14  4676.8  206.37  4707.3  208.94
  4737.8  207.38  4758.1  209.32  4798.7  210.17  4975.6  208.38  4986.1  200.22
  5008.6  200.22  5015.5  205.34    5028 208.381  5039.2  210.78  5068.3  213.81
  5116.2  214.01  5526.4  210.92  5785.3  210.72  6006.4  220.02  6026.9  221.32
  6072.9  224.91  6098.3  224.79  6149.3  226.55  6191.2   226.1  6234.4  228.71
#Mann= 9 ,-1 , 0
  3801.5     .12       0  4541.6      .1       0  4975.6     .07       0
    5028      .1       0  5116.2     .05       0  5526.4      .1       0
  6006.4     .05       0  6026.9     .12       0  6098.3     .05       0
Bank Sta=4975.6,5028
XS Rating Curve= 0 ,0
Exp/Cntr=0.3,0.1

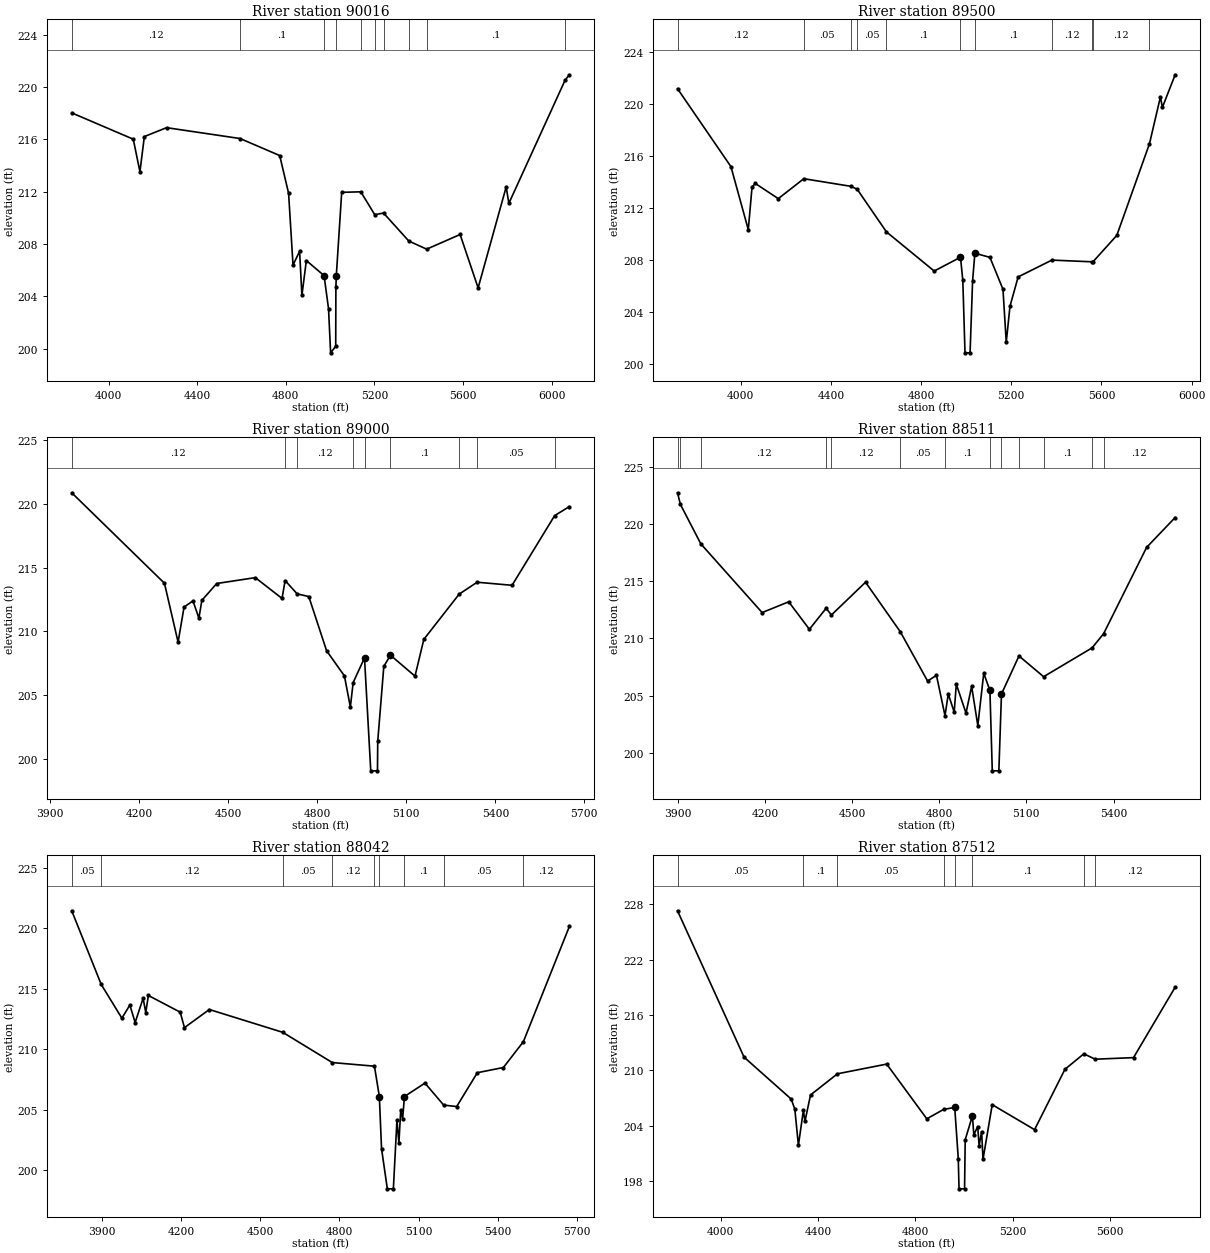
Type RM Length L Ch R = 1 ,90016   ,516,516,516
BEGIN DESCRIPTION:
CRYSTAL CREEK 179.0
END DESCRIPTION:
XS GIS Cut Line= 3
      3850429.34     10128178.39      3850365.58     10127013.83
      3850711.46     10125990.93
#Sta/Elev= 30
  3833.7  218.02  4111.4  216.01  4141.5  213.53  4161.5  216.21  4261.7  216.89
  4593.5  216.06  4772.4  214.76  4812.5  211.88  4832.5   206.4  4862.2  207.44
  4872.6  204.07  4892.6  206.74  4972.7  205.59  4992.8  203.06  5002.2  199.69
  5025.2  200.19    5026  204.69 5027.83 205.571  5052.2  211.95  5138.5  211.99
  5201.5  210.24  5240.9  210.37  5355.1  208.23  5435.8  207.61  5586.7  208.73
    5668  204.65  5794.6  212.36  5806.8  211.11  6060.6  220.52  6079.8  220.93
#Mann= 10 ,-1 , 0
  3833.7     .12       0  4593.5      .1       0  4972.7     .07       0
  5025.2      .1       0  5138.5     .05       0  5201.5     .12       0
  5240.9      .1       0  5355.1     .12       0  5435.8      .1       0
  6060.6     .05       0
Bank Sta=4972.7,5027.83
XS Rating Curve= 0 ,0
Exp/Cntr=0.3,0.1

Type RM Length L Ch R = 1 ,89500   ,500,500,500
BEGIN DESCRIPTION:
CRYSTAL CREEK 178.0
END DESCRIPTION:
XS GIS Cut Line= 3
      3851032.65     10128197.99      3850763.23     10126946.56
      3851183.71     10126120.63
#Sta/Elev= 30
  3719.9  221.17  3956.8  215.19  4033.8  210.35  4050.4  213.61  4064.5   213.9
  4166.8  212.73  4280.1  214.26  4487.3  213.68  4516.4  213.46  4646.4  210.18
  4858.3  207.17  4974.9  208.23  4985.2  206.46  4994.9  200.89  5017.4  200.89
  5028.6  206.43  5038.7  208.54  5105.5  208.22  5163.3  205.77  5177.8   201.7
  5194.4  204.47  5230.6  206.72  5380.2  208.01  5557.8  207.88  5560.4  207.84
  5668.2  209.91  5813.1  216.95  5861.7  220.55  5870.2  219.73  5926.8  222.24
#Mann= 11 ,-1 , 0
  3719.9     .12       0  4280.1     .05       0  4487.3     .12       0
  4516.4     .05       0  4646.4      .1       0  4974.9     .07       0
  5038.7      .1       0  5380.2     .12       0  5557.8     .05       0
  5560.4     .12       0  5813.1     .05       0
Bank Sta=4974.9,5038.7
XS Rating Curve= 0 ,0
Exp/Cntr=0.3,0.1

Type RM Length L Ch R = 1 ,89000   ,489,489,489
BEGIN DESCRIPTION:
CRYSTAL CREEK 177.0
END DESCRIPTION:
XS GIS Cut Line= 3
      3851089.07     10128189.26      3851134.55     10127162.47
      3851431.27     10126584.71
#Sta/Elev= 30
  3972.2  220.85  4284.7  213.77  4330.7  209.16  4350.8  211.91  4380.8  212.39
  4400.8  211.04  4410.8  212.43  4460.9  213.75    4591  214.21  4681.1  212.58
  4691.4  213.98    4732  212.94  4771.2  212.73  4831.2  208.49  4891.3  206.52
  4911.3  204.09  4920.8     206    4959  207.93  4980.1  199.09  5002.7  199.09
  5003.6   201.4  5024.1  207.26  5046.5  208.14  5129.2   206.5    5159  209.38
  5278.1  212.92  5338.7  213.85  5456.4  213.61  5599.8  219.06  5649.5  219.77
#Mann= 9 ,-1 , 0
  3972.2     .12       0  4691.4     .05       0    4732     .12       0
  4920.8      .1       0    4959     .07       0  5046.5      .1       0
  5278.1     .12       0  5338.7     .05       0  5599.8     .12       0
Bank Sta=4959,5046.5
XS Rating Curve= 0 ,0
Exp/Cntr=0.3,0.1

Type RM Length L Ch R = 1 ,88511   ,469,469,469
BEGIN DESCRIPTION:
CRYSTAL CREEK 176.0
END DESCRIPTION:
XS GIS Cut Line= 3
      3851779.17     10128267.39      3851577.42     10127185.14
      3851458.26     10126584.75
#Sta/Elev= 30
  3899.1  222.71    3909   221.7  3979.4  218.25  4190.4  212.25  4281.9  213.19
  4353.1  210.79  4410.6  212.62    4429  212.04  4546.4   214.9  4665.9  210.58
    4760  206.27  4790.5  206.77  4819.9  203.25  4831.2  205.14  4851.5  203.56
  4858.9  205.99  4892.2  203.47  4911.6  205.81  4932.9  202.38  4953.3  206.95
  4974.5  205.45  4982.7  198.43  5005.3  198.43  5014.3  205.14  5074.6  208.46
  5159.4  206.65  5326.4  209.17    5366  210.41  5513.9  217.94  5612.1  220.55
#Mann= 13 ,-1 , 0
  3899.1     .12       0    3909     .05       0  3979.4     .12       0
  4410.6     .05       0    4429     .12       0  4665.9     .05       0
  4819.9      .1       0  4974.5     .07       0  5014.3      .1       0
  5074.6     .05       0  5159.4      .1       0  5326.4     .05       0
    5366     .12       0
Bank Sta=4974.5,5014.3
XS Rating Curve= 0 ,0
Exp/Cntr=0.3,0.1

Type RM Length L Ch R = 1 ,88042   ,530,530,530
BEGIN DESCRIPTION:
CRYSTAL CREEK 175.0
END DESCRIPTION:
XS GIS Cut Line= 3
      3851844.27     10128280.44      3851953.64     10127070.87
      3851501.37     10126574.67
#Sta/Elev= 30
  3785.5  221.46  3897.3  215.36  3975.6  212.57  4005.8  213.66  4025.8  212.21
    4056  214.22    4066  213.04    4076  214.45  4196.5  213.07  4212.7  211.79
    4307  213.29  4585.4   211.4  4772.9   208.9  4932.7   208.6 4951.32 206.084
  4959.6  201.77  4981.6  198.45  5004.4  198.45    5018  204.14  5025.4  202.23
  5032.2  204.95  5039.6  204.25  5046.4  206.09  5124.1   207.2  5195.1  205.38
  5244.4  205.26  5322.7  208.06  5421.4  208.49  5497.2  210.63  5671.4  220.16
#Mann= 9 ,-1 , 0
  3785.5     .05       0  3897.3     .12       0  4585.4     .05       0
  4772.9     .12       0  4932.7     .05       0 4951.32     .07       0
  5046.4      .1       0  5195.1     .05       0  5497.2     .12       0
Bank Sta=4951.32,5046.4
XS Rating Curve= 0 ,0
Exp/Cntr=0.3,0.1

Type RM Length L Ch R = 1 ,87512   ,461,461,461
BEGIN DESCRIPTION:
CRYSTAL CREEK 174.0
END DESCRIPTION:
XS GIS Cut Line= 3
      3853042.19     10127850.73      3852341.27      10126903.7
      3851581.21     10126484.49
#Sta/Elev= 30
  3821.8  227.27  4095.5  211.44  4289.6   206.9  4304.3   205.8  4318.9  201.91
  4339.4  205.69  4345.9  204.51  4368.8  207.35  4479.3  209.64    4682  210.69
  4846.9  204.77    4916  205.79  4961.7     206  4976.3  200.46  4979.4   197.2
  5002.2   197.2  5004.8  202.51  5034.5   205.1  5040.2  203.04  5056.2  203.94
    5062  201.87  5072.3  203.39    5078  200.39  5115.9   206.3    5290   203.6
    5415  210.13  5492.6   211.8  5539.2  211.22  5696.9  211.39    5868     219
#Mann= 8 ,-1 , 0
  3821.8     .05       0  4339.4      .1       0  4479.3     .05       0
    4916      .1       0  4961.7     .07       0  5034.5      .1       0
  5492.6     .05       0  5539.2     .12       0
Bank Sta=4961.7,5034.5
XS Rating Curve= 0 ,0
Exp/Cntr=0.3,0.1