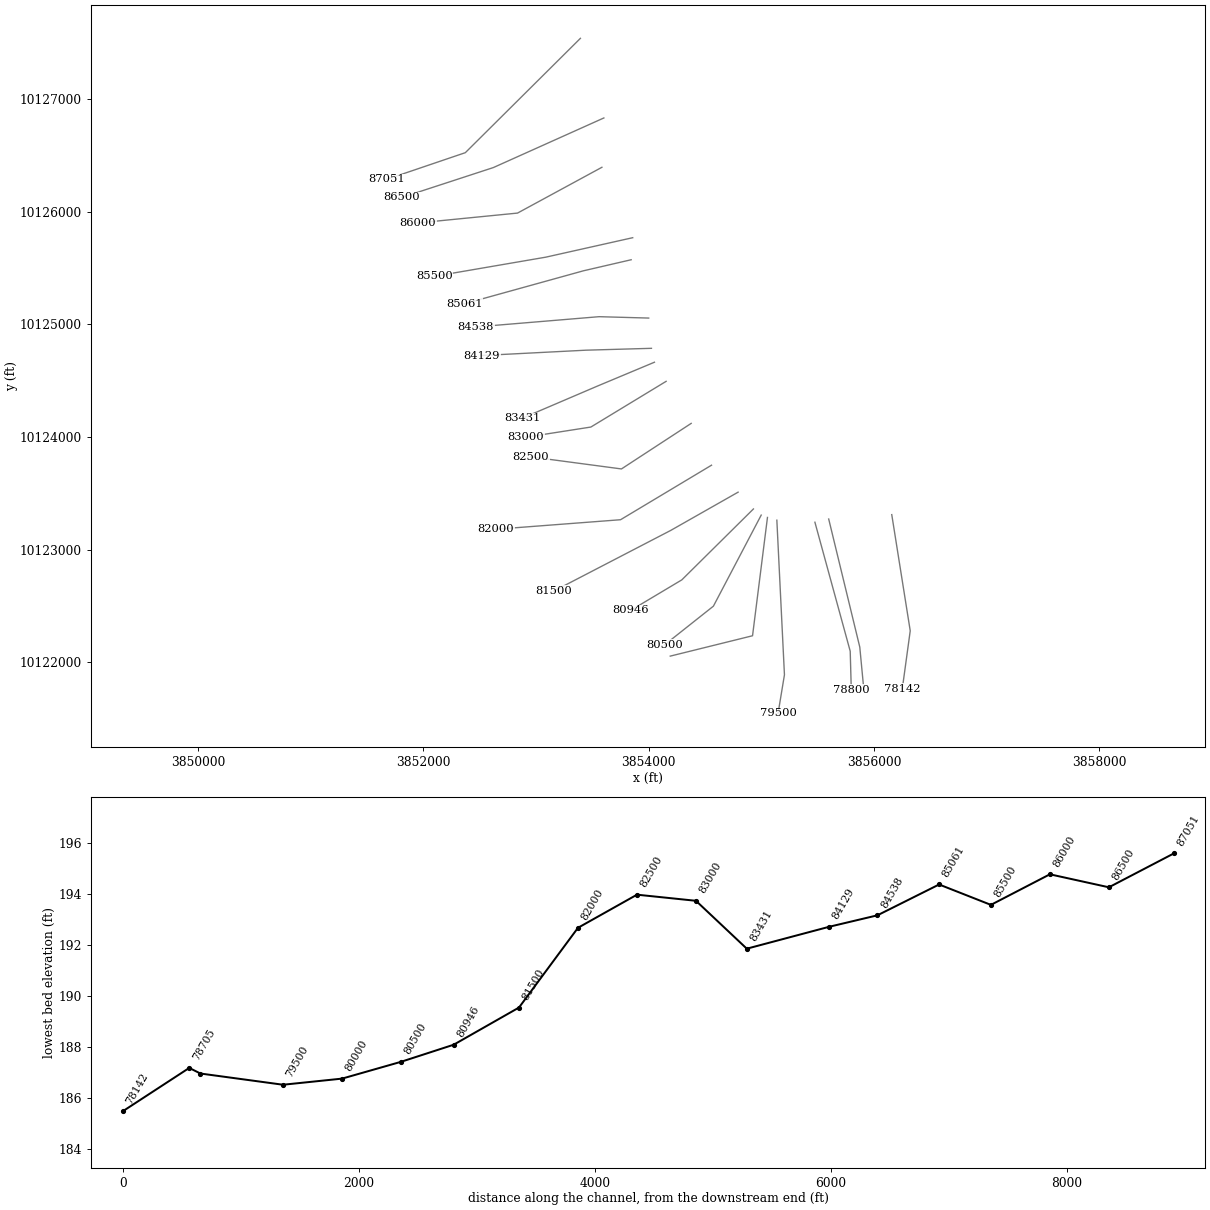
HEC-RAS study CRYSTAL CREEK.prj: CRYSTAL CREEK Base Level Engineering

--- CRYSTAL CREEK.g10 (geometry) --- (continued)

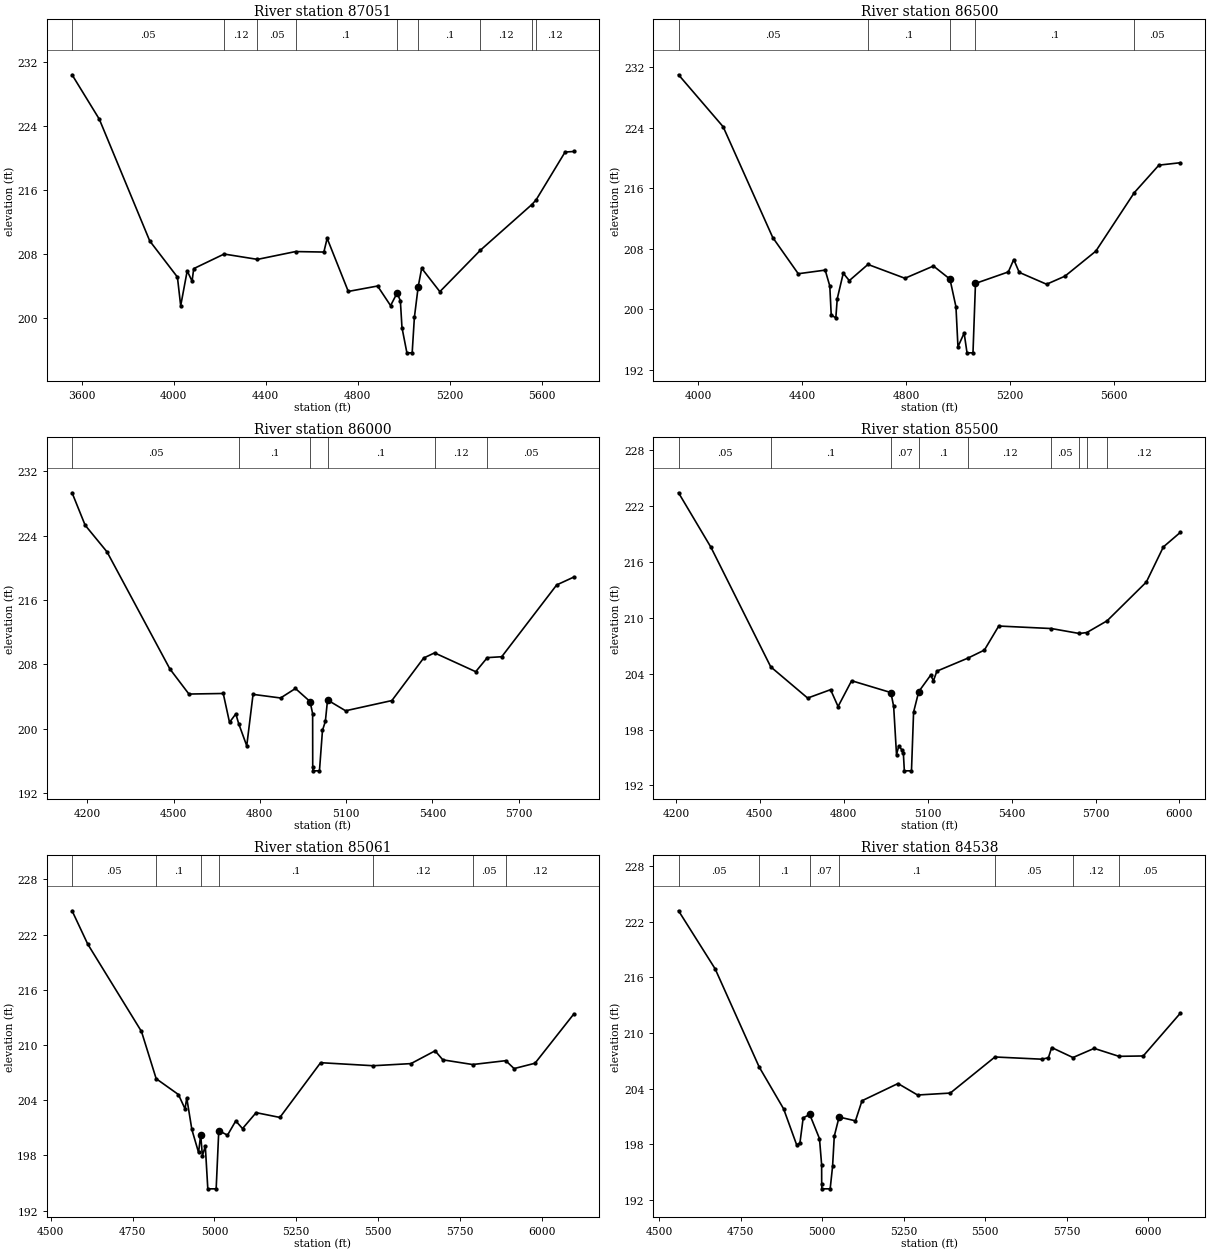
Type RM Length L Ch R = 1 ,87051   ,551,551,551
BEGIN DESCRIPTION:
CRYSTAL CREEK 173.0
END DESCRIPTION:
XS GIS Cut Line= 3
      3853393.78     10127542.61      3852371.91      10126526.6
      3851671.76     10126288.61
#Sta/Elev= 30
    3559  230.46  3677.4  224.89  3896.6  209.62  4016.8  205.09    4031  201.49
  4059.3  205.87  4080.5  204.58  4087.6  206.15  4219.7  207.98  4364.7  207.31
    4530  208.29  4653.2  208.23  4667.4  209.95  4759.3  203.29  4886.6  203.97
  4943.1  201.51  4971.4  203.09  4985.6  202.12  4992.6  198.76    5014  195.59
  5036.9  195.59  5046.5  200.03  5063.1  203.89  5078.2   206.2  5157.2  203.26
  5333.7  208.47  5556.7  214.18  5575.4  214.77  5701.4  220.77  5739.5  220.84
#Mann= 9 ,-1 , 0
    3559     .05       0  4219.7     .12       0  4364.7     .05       0
    4530      .1       0  4971.4     .07       0  5063.1      .1       0
  5333.7     .12       0  5556.7     .05       0  5575.4     .12       0
Bank Sta=4971.4,5063.1
XS Rating Curve= 0 ,0
Exp/Cntr=0.3,0.1

Type RM Length L Ch R = 1 ,86500   ,500,500,500
BEGIN DESCRIPTION:
CRYSTAL CREEK 172.0
END DESCRIPTION:
XS GIS Cut Line= 3
      3853602.06      10126835.1      3852620.74     10126394.25
      3851808.98       10126129.
#Sta/Elev= 30
  3924.2  231.03  4095.7  224.16  4286.5  209.51  4384.6  204.72  4488.2   205.2
  4505.9   203.1  4511.4  199.28  4529.1  198.87  4534.6  201.42  4557.7  204.79
  4580.9  203.81  4652.7  205.95  4794.9  204.12  4904.5  205.74    4968  204.01
  4991.1  200.35  4998.8  195.06  5022.6  196.87  5033.7  194.26  5056.6  194.26
  5066.2  203.44  5192.5  204.96  5213.4   206.6  5234.5   204.9  5339.7  203.33
  5410.4   204.4  5529.1  207.71  5676.9  215.44  5771.6  219.08    5854   219.4
#Mann= 5 ,-1 , 0
  3924.2     .05       0  4652.7      .1       0    4968     .07       0
  5066.2      .1       0  5676.9     .05       0
Bank Sta=4968,5066.2
XS Rating Curve= 0 ,0
Exp/Cntr=0.3,0.1

Type RM Length L Ch R = 1 ,86000   ,500,500,500
BEGIN DESCRIPTION:
CRYSTAL CREEK 171.0
END DESCRIPTION:
XS GIS Cut Line= 3
      3853584.69     10126396.72      3852835.46     10125989.81
       3851948.4     10125901.95
#Sta/Elev= 30
  4147.4  229.35  4192.8  225.32  4268.9     222  4487.4  207.44  4553.5  204.32
  4672.8  204.39  4694.6   200.8  4716.5  201.85  4726.6  200.63  4754.5  197.88
  4776.4  204.28  4872.1  203.83  4923.7  205.01  4974.5  203.39  4983.5  201.88
  4983.8  195.27  4984.3  194.77  5007.2  194.77  5017.7   199.8  5027.7  200.92
  5035.3  203.58  5098.1  202.24  5258.9  203.51  5369.4   208.8  5407.2  209.44
  5550.3   207.1  5590.6  208.85  5640.7  208.96  5831.7  217.89  5891.4  218.87
#Mann= 6 ,-1 , 0
  4147.4     .05       0  4726.6      .1       0  4974.5     .07       0
  5035.3      .1       0  5407.2     .12       0  5590.6     .05       0
Bank Sta=4974.5,5035.3
XS Rating Curve= 0 ,0
Exp/Cntr=0.3,0.1

Type RM Length L Ch R = 1 ,85500   ,439,439,439
BEGIN DESCRIPTION:
CRYSTAL CREEK 170.0
END DESCRIPTION:
XS GIS Cut Line= 3
      3853858.21     10125771.03      3853086.75     10125598.13
      3852098.16     10125428.13
#Sta/Elev= 30
  4209.4  223.41  4325.6  217.54    4539  204.73  4670.9  201.38  4752.9  202.28
  4779.7  200.47  4828.1  203.24  4968.5  201.97  4978.4  200.48  4988.6  195.31
  4996.9  196.26  5008.1   195.8  5013.1  195.44  5016.6  193.57  5042.1  193.57
  5049.6  199.87    5068  202.07  5110.5  203.83  5120.6  203.24    5133  204.27
    5244  205.67  5302.7  206.53    5354  209.11  5542.4  208.84  5641.8  208.31
  5668.8  208.41  5741.3  209.67  5881.6  213.83  5942.5   217.6  6003.1  219.16
#Mann= 9 ,-1 , 0
  4209.4     .05       0    4539      .1       0  4968.5     .07       0
    5068      .1       0    5244     .12       0  5542.4     .05       0
  5641.8     .12       0  5668.8     .05       0  5741.3     .12       0
Bank Sta=4968.5,5068
XS Rating Curve= 0 ,0
Exp/Cntr=0.3,0.1

Type RM Length L Ch R = 1 ,85061   ,523,523,523
BEGIN DESCRIPTION:
CRYSTAL CREEK 169.0
END DESCRIPTION:
XS GIS Cut Line= 3
       3853844.6     10125575.15      3853420.74     10125476.93
      3852361.77     10125183.38
#Sta/Elev= 30
  4564.9  224.59  4612.9  220.96  4777.1  211.47    4822  206.34    4890  204.62
  4910.3  203.06  4915.5  204.25  4931.1  200.82  4951.6  198.32  4958.1  200.25
  4963.3  197.97  4972.2  199.01  4979.9  194.37  5005.4  194.37  5013.4   200.7
    5040   200.2  5065.3  201.75    5086  200.92  5127.5  202.65  5200.2  202.13
  5324.7  208.08  5485.4  207.75  5600.9  207.98  5674.7  209.37  5698.3  208.39
  5789.4  207.88  5890.7   208.3  5916.2  207.44  5980.1  208.02  6098.9  213.38
#Mann= 7 ,-1 , 0
  4564.9     .05       0    4822      .1       0  4958.1     .07       0
  5013.4      .1       0  5485.4     .12       0  5789.4     .05       0
  5890.7     .12       0
Bank Sta=4958.1,5013.4
XS Rating Curve= 0 ,0
Exp/Cntr=0.3,0.1

Type RM Length L Ch R = 1 ,84538   ,409,409,409
BEGIN DESCRIPTION:
CRYSTAL CREEK 168.0
END DESCRIPTION:
XS GIS Cut Line= 3
      3854000.23     10125056.88       3853559.7     10125069.18
       3852464.4     10124977.84
#Sta/Elev= 30
  4559.3  223.21  4671.7  216.93  4806.6  206.34  4881.8   201.8  4921.8  197.91
  4931.8  198.11  4941.8  200.83  4961.8   201.2  4991.8  198.59  4998.4  195.77
  4998.6  193.66  4999.1  193.16  5024.6  193.16    5032  195.59  5037.2  198.85
    5052  200.92  5102.2  200.51  5122.3  202.68  5232.7  204.54  5292.9   203.3
  5393.2  203.51  5530.2  207.41  5674.2  207.17  5694.3  207.33  5704.3  208.43
  5769.6  207.35  5834.7  208.34  5910.7  207.48  5985.3  207.52  6099.1  212.14
#Mann= 7 ,-1 , 0
  4559.3     .05       0  4806.6      .1       0  4961.8     .07       0
    5052      .1       0  5530.2     .05       0  5769.6     .12       0
  5910.7     .05       0
Bank Sta=4961.8,5052
XS Rating Curve= 0 ,0
Exp/Cntr=0.3,0.1

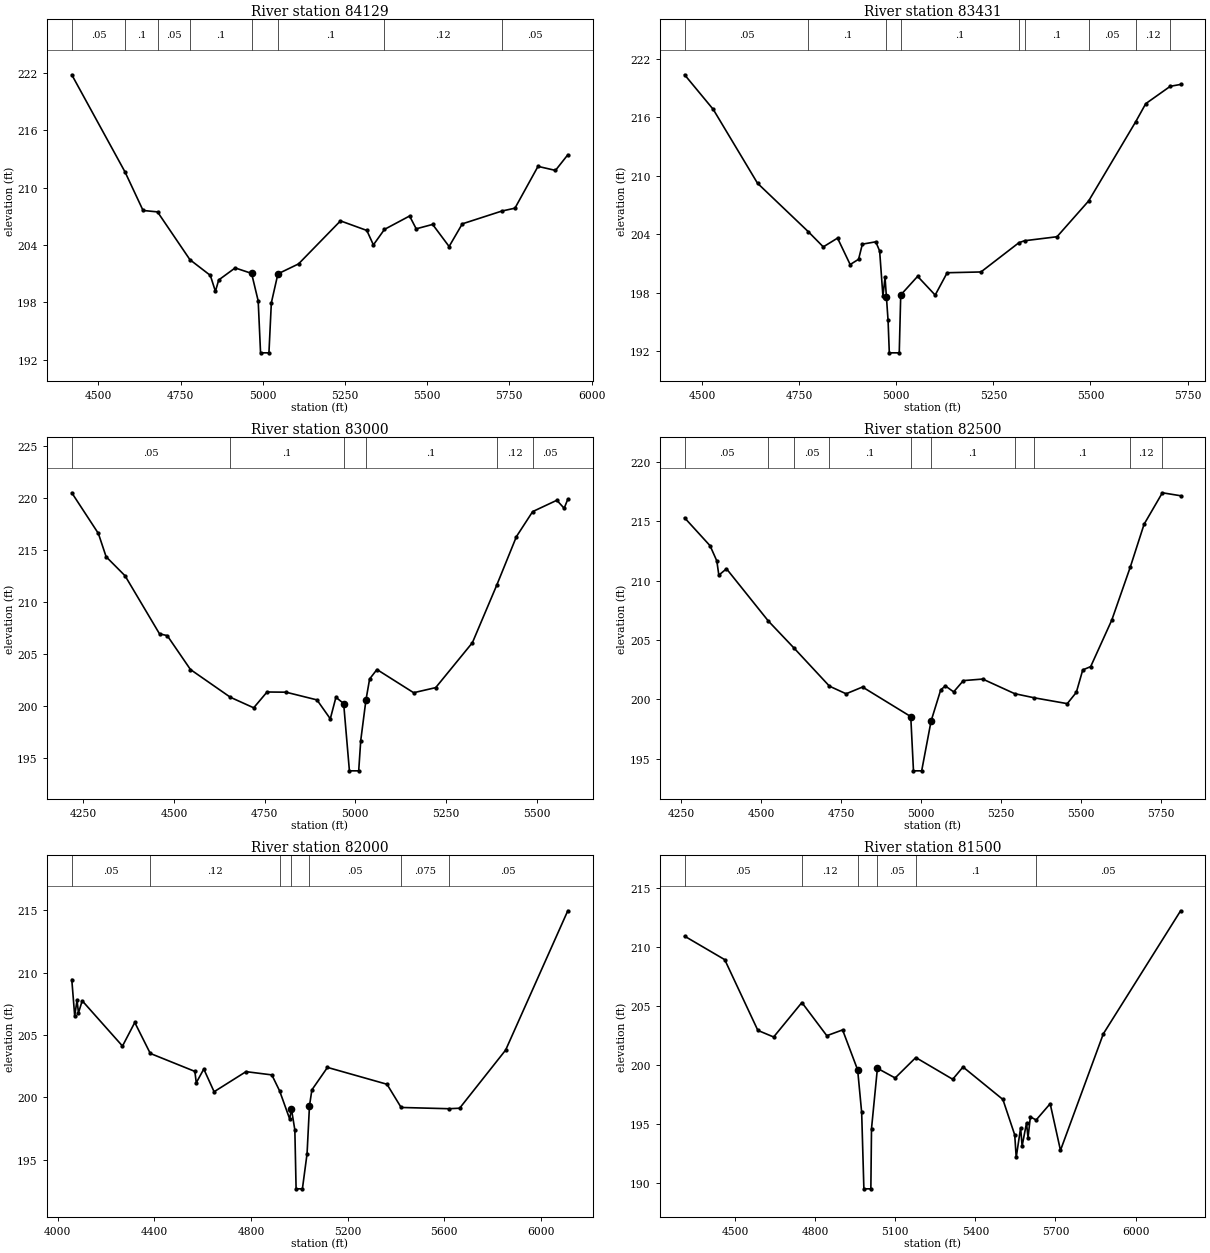
Type RM Length L Ch R = 1 ,84129   ,698,698,698
BEGIN DESCRIPTION:
CRYSTAL CREEK 167.0
END DESCRIPTION:
XS GIS Cut Line= 3
      3854024.57     10124788.06      3853443.81     10124771.51
      3852517.32     10124724.06
#Sta/Elev= 30
    4419  221.79  4581.2  211.61  4635.8   207.6  4679.8  207.45  4778.4  202.45
  4840.4  200.81  4855.9  199.14  4865.9  200.33  4915.9  201.59  4965.9  201.02
    4986  198.14  4993.2  192.71  5018.7  192.71    5026  197.94    5046  200.97
  5108.7  202.01  5236.3  206.51  5316.4  205.51  5336.4     204  5370.1  205.62
  5446.5  207.02  5466.6  205.68  5516.6  206.14  5566.7  203.83  5606.8   206.2
  5727.3  207.54    5767  207.84  5837.1  212.21  5890.2  211.79  5927.7  213.42
#Mann= 8 ,-1 , 0
    4419     .05       0  4581.2      .1       0  4679.8     .05       0
  4778.4      .1       0  4965.9     .07       0    5046      .1       0
  5370.1     .12       0  5727.3     .05       0
Bank Sta=4965.9,5046
XS Rating Curve= 0 ,0
Exp/Cntr=0.3,0.1

Type RM Length L Ch R = 1 ,83431   ,431,431,431
BEGIN DESCRIPTION:
CRYSTAL CREEK 166.0
END DESCRIPTION:
XS GIS Cut Line= 3
      3854051.12     10124664.49      3853548.31     10124453.97
      3852875.26     10124165.91
#Sta/Elev= 30
  4454.9  220.35  4528.7   216.8  4642.7  209.23  4773.6  204.26    4812  202.71
  4848.7  203.61  4881.2   200.9  4902.9  201.44  4912.6  202.99  4947.2  203.23
  4957.1  202.29  4965.6  197.65    4971  199.58  4974.5 197.606  4978.8  195.18
    4982  191.85  5007.6  191.85  5011.4  197.78  5054.9  199.69  5100.1  197.77
    5131  200.06    5218  200.14  5315.8  203.14  5330.3  203.34  5413.8  203.75
  5495.3  207.42  5616.8  215.56  5642.3  217.39  5705.5  219.17  5732.1  219.36
#Mann= 9 ,-1 , 0
  4454.9     .05       0  4773.6      .1       0  4974.5     .07       0
  5011.4      .1       0  5315.8     .05       0  5330.3      .1       0
  5495.3     .05       0  5616.8     .12       0  5705.5     .05       0
Bank Sta=4974.5,5011.4
XS Rating Curve= 0 ,0
Exp/Cntr=0.3,0.1

Type RM Length L Ch R = 1 ,83000   ,500,500,500
BEGIN DESCRIPTION:
CRYSTAL CREEK 165.0
END DESCRIPTION:
XS GIS Cut Line= 3
      3854154.83     10124494.57      3853486.65     10124088.49
      3852907.98     10123998.02
#Sta/Elev= 30
  4218.1  220.46  4291.4  216.55  4312.8  214.31    4365  212.48    4460   206.9
  4481.3  206.73  4545.3  203.47  4655.5   200.8  4719.7  199.79  4756.5  201.31
  4808.8  201.29  4894.1  200.55  4930.9  198.73  4946.4   200.8  4967.7   200.2
  4983.6  193.73  5009.2  193.73  5014.8  196.64  5029.1  200.52  5039.3  202.56
  5059.5  203.47  5160.7  201.24  5221.5  201.73  5322.7  206.05  5389.6  211.56
  5444.1  216.25  5488.8  218.65  5555.5  219.74  5575.7  218.97  5585.7  219.84
#Mann= 6 ,-1 , 0
  4218.1     .05       0  4655.5      .1       0  4967.7     .07       0
  5029.1      .1       0  5389.6     .12       0  5488.8     .05       0
Bank Sta=4967.7,5029.1
XS Rating Curve= 0 ,0
Exp/Cntr=0.3,0.1

Type RM Length L Ch R = 1 ,82500   ,500,500,500
BEGIN DESCRIPTION:
CRYSTAL CREEK 164.0
END DESCRIPTION:
XS GIS Cut Line= 3
      3854377.41     10124120.98      3853758.17      10123716.2
      3852954.67     10123823.25
#Sta/Elev= 30
  4260.2  215.28  4339.8  212.93  4360.9  211.65  4367.2  210.45  4391.1  210.99
  4522.2  206.58  4601.2  204.34    4713   201.1    4765  200.46  4816.3  201.03
  4967.1  198.54  4975.6  193.97  5001.2  193.97  5030.6  198.16  5060.9   200.8
  5075.4  201.12  5101.2  200.62  5131.5  201.57    5192   201.7  5291.9  200.47
  5353.4  200.12  5456.3  199.63  5484.6  200.58  5504.7  202.47  5529.5  202.75
  5595.5  206.67  5653.5  211.15  5696.4  214.74  5753.6  217.39  5810.6  217.14
#Mann= 10 ,-1 , 0
  4260.2     .05       0  4522.2      .1       0  4601.2     .05       0
    4713      .1       0  4967.1     .07       0  5030.6      .1       0
  5291.9     .05       0  5353.4      .1       0  5653.5     .12       0
  5753.6     .05       0
Bank Sta=4967.1,5030.6
XS Rating Curve= 0 ,0
Exp/Cntr=0.3,0.1

Type RM Length L Ch R = 1 ,82000   ,500,500,500
BEGIN DESCRIPTION:
CRYSTAL CREEK 163.0
END DESCRIPTION:
XS GIS Cut Line= 3
      3854557.98     10123749.46      3853750.15     10123264.92
      3852641.18     10123180.14
#Sta/Elev= 30
    4058  209.44  4070.1  206.53  4079.8  207.78  4085.7  206.77  4101.2  207.74
    4268  204.11  4318.9     206  4383.1  203.52  4567.7  202.08  4573.6  201.17
  4604.7  202.27  4647.4  200.45  4779.6  202.06  4886.5   201.8  4918.7  200.52
  4960.4  198.27  4967.7  199.07  4981.8  197.39    4987  192.67  5013.1  192.67
  5032.4  195.48  5042.4  199.32  5052.4   200.6  5116.9   202.4  5363.4  201.05
    5422  199.19  5619.4  199.09  5664.2  199.13  5854.8  203.79  6112.2  214.95
#Mann= 7 ,-1 , 0
    4058     .05       0  4383.1     .12       0  4918.7      .1       0
  4967.7     .07       0  5042.4     .05       0    5422    .075       0
  5619.4     .05       0
Bank Sta=4967.7,5042.4
XS Rating Curve= 0 ,0
Exp/Cntr=0.3,0.1

Type RM Length L Ch R = 1 ,81500   ,554,554,554
BEGIN DESCRIPTION:
CRYSTAL CREEK 162.0
END DESCRIPTION:
XS GIS Cut Line= 3
       3854794.1     10123509.88      3854195.65     10123169.86
      3853158.71     10122631.43
#Sta/Elev= 30
  4311.7  210.94  4461.9  208.95  4585.9  202.96    4645   202.4  4750.7  205.32
    4844  202.51  4903.1     203 4959.44 199.614  4974.5  196.01  4982.8  189.54
  5008.9  189.54  5011.3  194.63  5033.4  199.75  5099.8  198.93  5177.1  200.66
  5315.3  198.82  5353.9  199.86  5503.1  197.11  5547.4  194.11    5553   192.2
  5569.5  194.71  5575.1  193.17  5591.6  195.12  5597.2  193.87    5606  195.64
  5627.5  195.37  5680.1  196.75  5718.7   192.8  5879.1  202.67  6168.4  213.09
#Mann= 6 ,-1 , 0
  4311.7     .05       0  4750.7     .12       0 4959.44     .07       0
  5033.4     .05       0  5177.1      .1       0  5627.5     .05       0
Bank Sta=4959.44,5033.4
XS Rating Curve= 0 ,0
Exp/Cntr=0.3,0.1

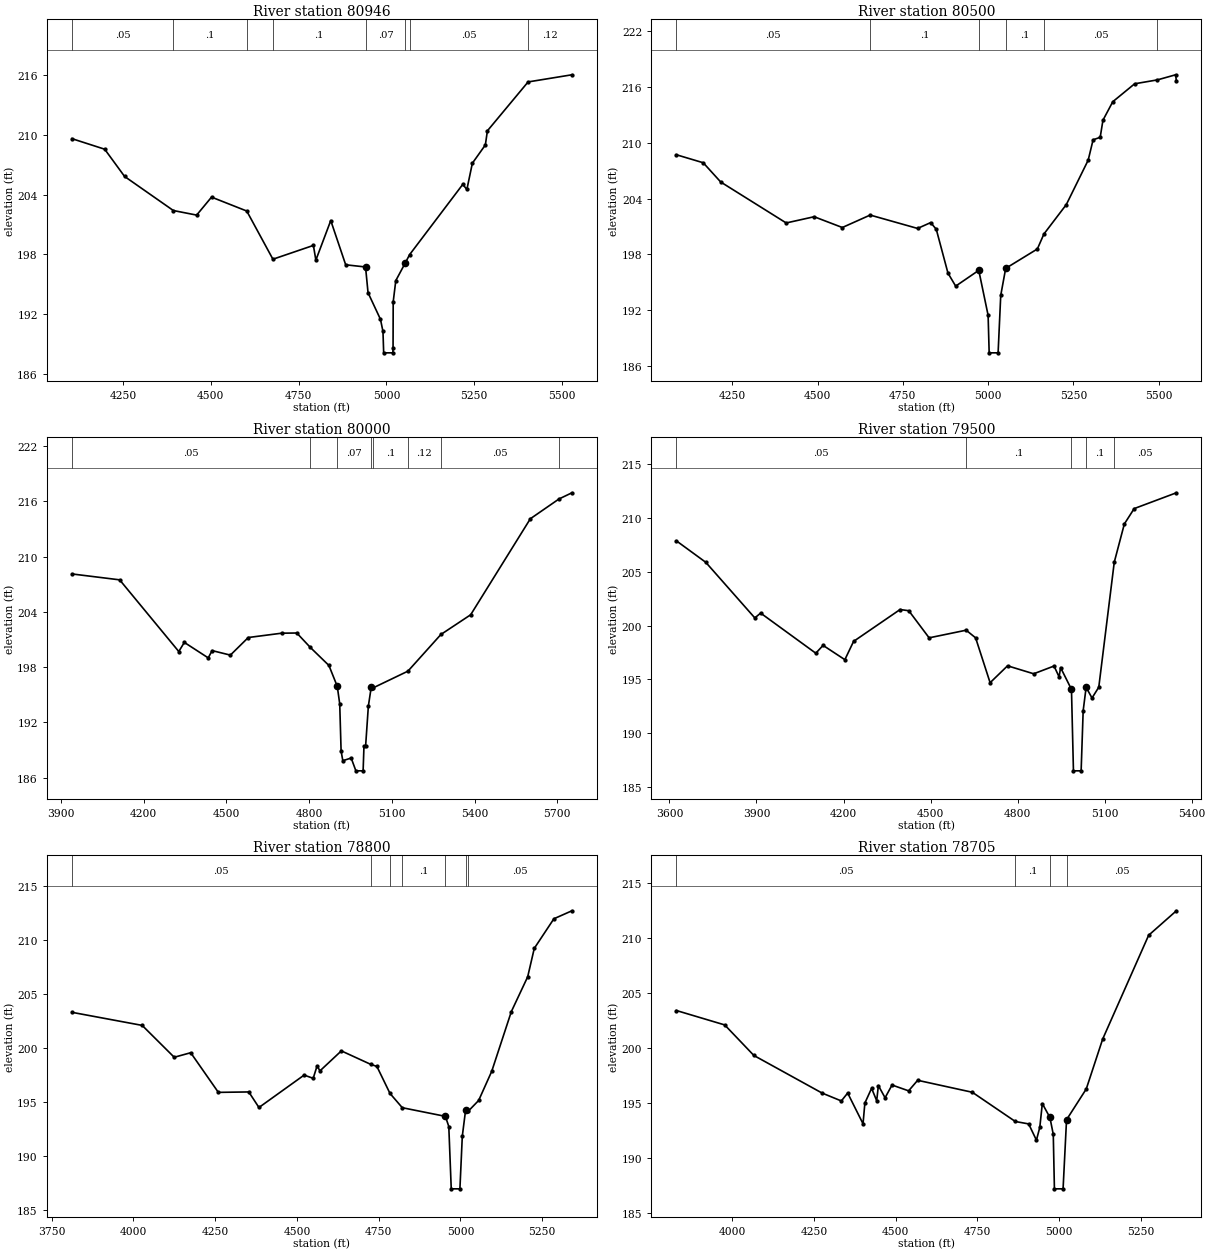
Type RM Length L Ch R = 1 ,80946   ,446,446,446
BEGIN DESCRIPTION:
CRYSTAL CREEK 161.0
END DESCRIPTION:
XS GIS Cut Line= 3
      3854930.01     10123360.57      3854294.34     10122730.54
      3853841.14     10122459.81
#Sta/Elev= 30
    4105  209.63  4198.1  208.57  4254.7  205.83  4393.5   202.4  4459.8  201.94
  4502.2  203.75  4602.4  202.35  4676.9   197.5  4792.1  198.89  4799.1  197.41
  4841.5  201.39    4884  196.94  4940.5  196.72  4947.6  194.13    4983  191.45
  4990.1  190.23  4992.1  188.08  5018.3  188.08  5018.8  188.58  5019.2  193.21
  5026.6  195.35  5054.1  197.16  5065.9  197.96  5217.2  205.03  5228.9  204.52
  5244.5  207.16  5281.5     209  5287.3  210.42  5403.1  215.34  5527.9  216.06
#Mann= 8 ,-1 , 0
    4105     .05       0  4393.5      .1       0  4602.4     .12       0
  4676.9      .1       0  4940.5     .07       0  5054.1      .1       0
  5065.9     .05       0  5403.1     .12       0
Bank Sta=4940.5,5054.1
XS Rating Curve= 0 ,0
Exp/Cntr=0.3,0.1

Type RM Length L Ch R = 1 ,80500   ,500,500,500
BEGIN DESCRIPTION:
CRYSTAL CREEK 160.0
END DESCRIPTION:
XS GIS Cut Line= 3
       3854999.2     10123306.04      3854574.71     10122496.82
      3854142.23     10122153.79
#Sta/Elev= 30
  4086.2  208.73  4164.8  207.87    4216   205.8    4408  201.39    4490  202.06
  4572.6   200.9  4654.2  202.24  4793.2   200.8  4831.6  201.43    4848  200.71
  4882.3  195.99  4904.9  194.59  4972.6  196.29    5000  191.45  5003.1  187.41
  5029.3  187.41    5037  193.59  5051.5   196.5  5144.4  198.59  5163.6   200.2
  5229.3  203.37  5293.4  208.15  5307.8  210.34  5328.6  210.61  5336.7  212.45
  5365.5  214.44  5429.6  216.37  5496.3  216.79  5549.8  217.34    5552  216.64
#Mann= 6 ,-1 , 0
  4086.2     .05       0  4654.2      .1       0  4972.6     .07       0
  5051.5      .1       0  5163.6     .05       0  5496.3     .12       0
Bank Sta=4972.6,5051.5
XS Rating Curve= 0 ,0
Exp/Cntr=0.3,0.1

Type RM Length L Ch R = 1 ,80000   ,500,500,500
BEGIN DESCRIPTION:
CRYSTAL CREEK 159.0
END DESCRIPTION:
XS GIS Cut Line= 3
      3855054.75      10123285.2      3854922.19     10122233.92
      3854191.48     10122052.89
#Sta/Elev= 30
  3940.4  208.12  4113.2  207.48  4327.6   199.7  4347.7  200.69  4434.3  199.01
  4448.5   199.8  4514.6  199.31  4579.5  201.22  4700.5  201.69  4755.4  201.71
  4803.9  200.16  4871.8  198.19  4902.1  195.92    4911  194.02    4916   188.9
  4922.2  187.85  4952.5  188.14  4969.6  186.75  4995.8  186.75  4998.9  189.41
  5004.8  189.41  5014.8  193.77  5025.1  195.81    5031  195.74  5158.3  197.57
  5277.8  201.55  5385.7  203.69    5602  214.11    5706  216.26  5752.8  216.93
#Mann= 8 ,-1 , 0
  3940.4     .05       0  4803.9      .1       0  4902.1     .07       0
  5025.1     .05       0    5031      .1       0  5158.3     .12       0
  5277.8     .05       0    5706     .12       0
Bank Sta=4902.1,5025.1
XS Rating Curve= 0 ,0
Exp/Cntr=0.3,0.1

Type RM Length L Ch R = 1 ,79500   ,700,700,700
BEGIN DESCRIPTION:
CRYSTAL CREEK 158.0
END DESCRIPTION:
XS GIS Cut Line= 3
      3855138.08     10123260.91      3855205.52     10121886.67
      3855148.83     10121544.13
#Sta/Elev= 30
  3624.1  207.88  3725.2  205.89  3894.3  200.72  3914.3  201.17  4104.5  197.44
  4129.5  198.17  4204.6  196.84  4234.7  198.54  4394.9   201.5  4424.9  201.39
    4495  198.87  4622.6  199.58  4655.2  198.87  4705.2   194.7  4765.3  196.27
  4855.4  195.53  4925.5  196.25    4943  195.24    4948  196.11  4985.6  194.08
  4992.4  186.51  5018.9  186.51  5025.9  192.09  5036.1  194.27  5056.4  193.28
  5079.7  194.28  5133.1   205.9  5167.8  209.45  5201.7  210.88  5347.2  212.35
#Mann= 5 ,-1 , 0
  3624.1     .05       0  4622.6      .1       0  4985.6     .07       0
  5036.1      .1       0  5133.1     .05       0
Bank Sta=4985.6,5036.1
XS Rating Curve= 0 ,0
Exp/Cntr=0.3,0.1

Type RM Length L Ch R = 1 ,78800   ,95,95,95
BEGIN DESCRIPTION:
CRYSTAL CREEK 157.0
END DESCRIPTION:
XS GIS Cut Line= 3
      3855476.05     10123242.65      3855789.47     10122096.64
      3855798.96     10121755.87
#Sta/Elev= 30
  3811.9  203.29  4026.6  202.08  4124.6  199.13    4175  199.55  4259.6  195.88
  4352.6  195.92  4383.7  194.48  4521.9  197.48  4549.6  197.18  4561.5  198.33
  4570.3  197.87  4635.7  199.72  4725.1  198.48  4744.4  198.28  4784.5  195.78
  4822.1  194.46  4953.9  193.66  4964.3  192.72  4971.8  186.95  4998.3  186.95
  5005.6  191.82  5015.6  194.22  5023.5  194.13  5055.6  195.13  5095.6  197.83
  5155.6  203.36  5205.6  206.58  5225.7  209.21  5285.7  211.95  5340.9  212.69
#Mann= 7 ,-1 , 0
  3811.9     .05       0  4725.1      .1       0  4784.5     .05       0
  4822.1      .1       0  4953.9     .07       0  5015.6      .1       0
  5023.5     .05       0
Bank Sta=4953.9,5015.6
XS Rating Curve= 0 ,0
Exp/Cntr=0.3,0.1

Type RM Length L Ch R = 1 ,78705   ,563,563,563
BEGIN DESCRIPTION:
CRYSTAL CREEK 156.0
END DESCRIPTION:
XS GIS Cut Line= 3
      3855598.45     10123271.27      3855874.39     10122133.45
      3855908.33     10121776.56
#Sta/Elev= 30
  3829.2   203.4  3976.9  202.09  4066.1  199.31  4274.6  195.89  4333.6  195.17
    4353  195.89    4400  193.09  4405.6  194.98  4426.2  196.32  4441.8  195.19
  4446.9  196.57  4467.4  195.46  4488.7  196.62  4539.4  196.09  4567.1  197.05
  4734.3  195.96  4865.8   193.3  4906.6  193.08  4930.4   191.6  4940.7  192.77
  4948.4  194.93  4971.6  193.67  4981.9  192.13  4985.4  187.17  5011.9  187.17
  5022.5  193.46  5082.8  196.26    5133   200.8  5273.6  210.25  5358.5  212.48
#Mann= 4 ,-1 , 0
  3829.2     .05       0  4865.8      .1       0  4971.6     .07       0
  5022.5     .05       0
Bank Sta=4971.6,5022.5
XS Rating Curve= 0 ,0
Exp/Cntr=0.3,0.1

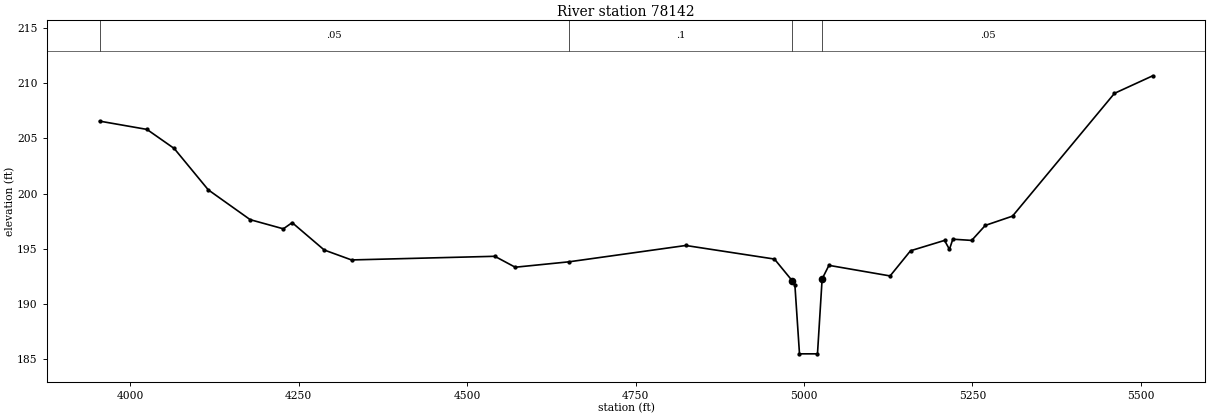
Type RM Length L Ch R = 1 ,78142   ,642,642,642
BEGIN DESCRIPTION:
CRYSTAL CREEK 155.0
END DESCRIPTION:
XS GIS Cut Line= 3
      3856158.34     10123310.36      3856322.41     10122277.71
      3856252.26     10121764.78
#Sta/Elev= 30
  3954.4  206.56  4024.6  205.81  4065.1  204.08  4115.7  200.33  4177.9  197.63
  4227.1   196.8  4240.2  197.36  4287.8  194.88  4328.3  193.98    4541  194.31
  4571.3  193.32  4651.1  193.81  4824.5  195.29  4956.1  194.06  4982.3  192.11
  4986.5  191.68  4993.3  185.47    5020  185.47  5026.9  192.26    5037  193.49
  5127.8  192.53  5158.1  194.81  5208.6  195.75  5215.9  194.94  5220.9  195.86
  5248.9  195.75  5269.1  197.11  5309.5  197.95  5460.9  209.08  5517.7  210.67
#Mann= 4 ,-1 , 0
  3954.4     .05       0  4651.1      .1       0  4982.3     .07       0
  5026.9     .05       0
Bank Sta=4982.3,5026.9
XS Rating Curve= 0 ,0
Exp/Cntr=0.3,0.1