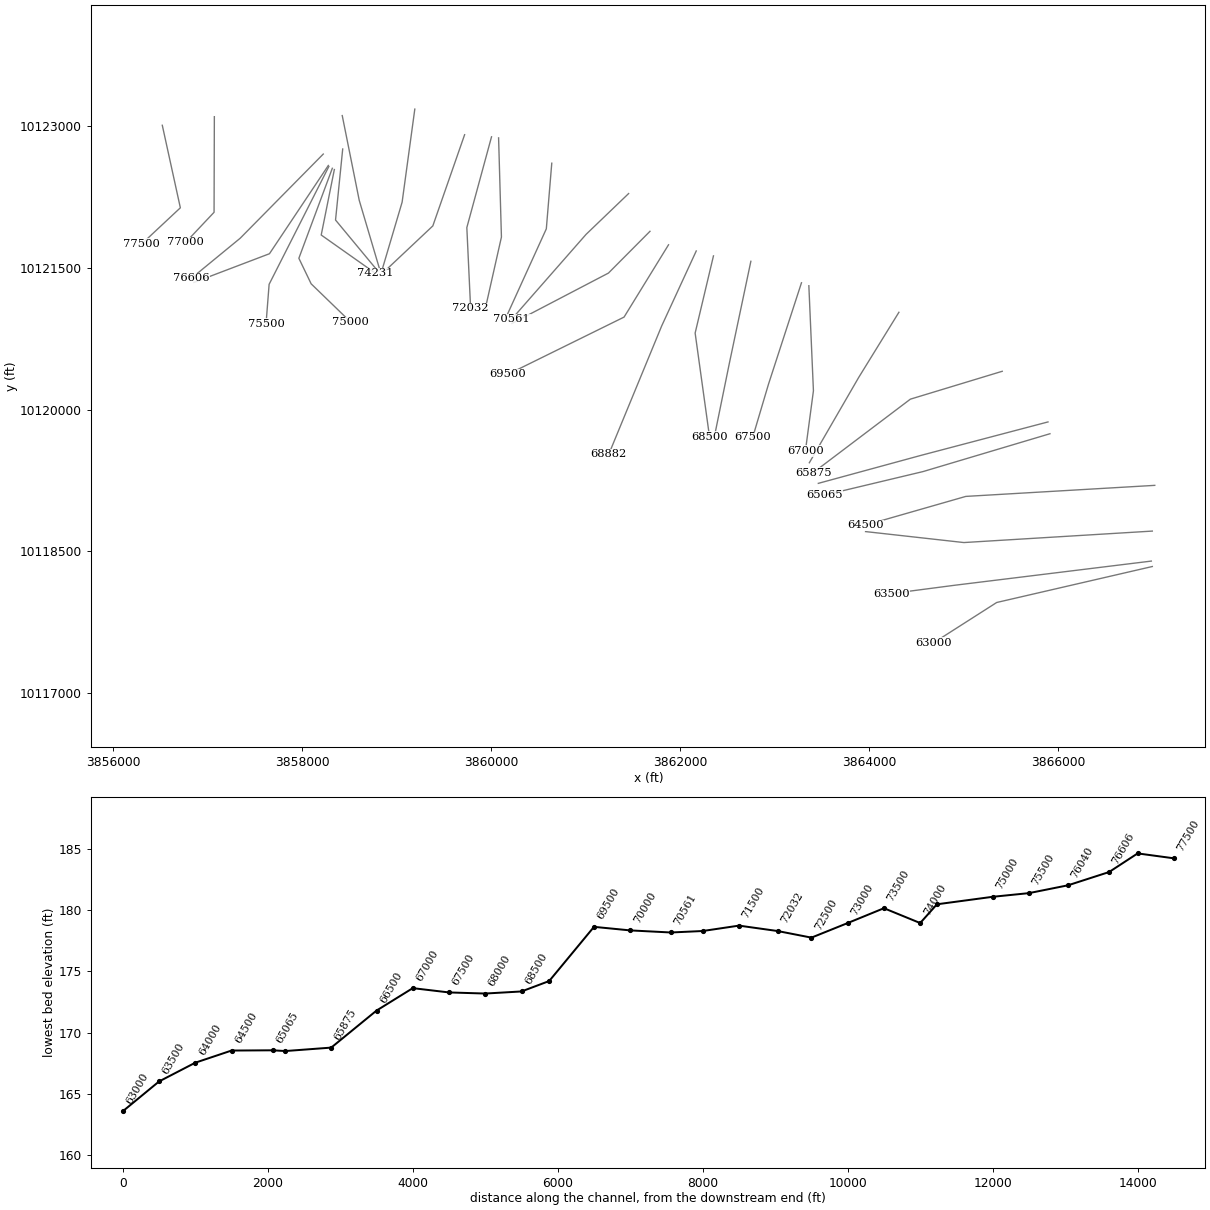
HEC-RAS study CRYSTAL CREEK.prj: CRYSTAL CREEK Base Level Engineering

--- CRYSTAL CREEK.g10 (geometry) --- (continued)

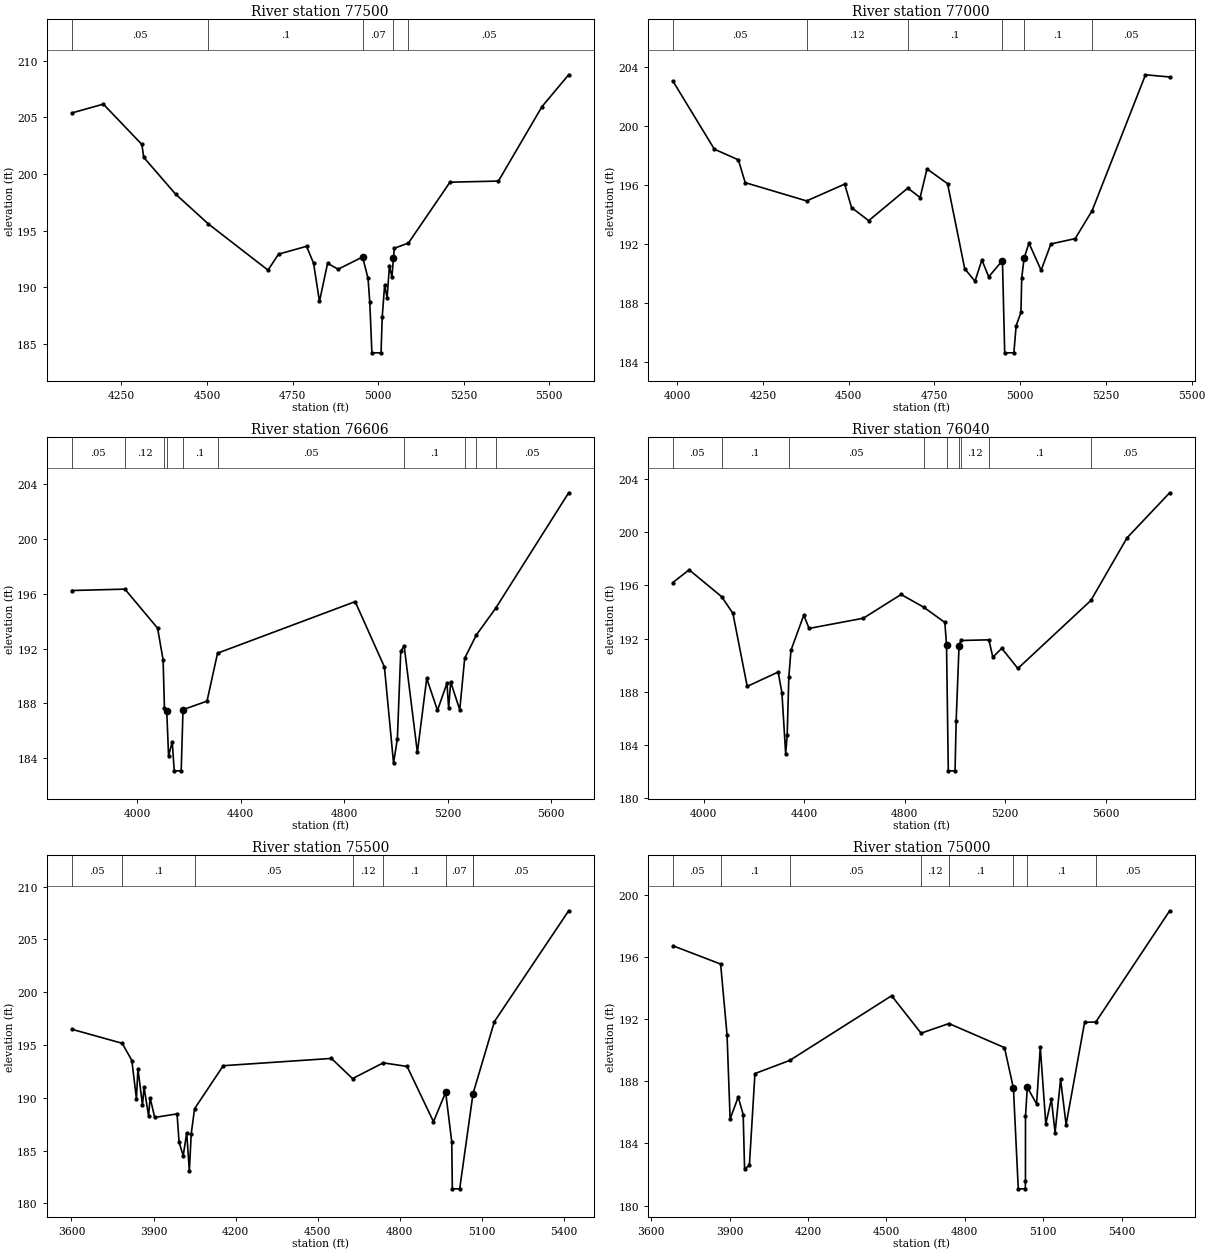
Type RM Length L Ch R = 1 ,77500   ,500,500,500
BEGIN DESCRIPTION:
CRYSTAL CREEK 154.0
END DESCRIPTION:
XS GIS Cut Line= 3
      3856517.85     10123011.08      3856709.03     10122136.84
       3856302.4     10121756.47
#Sta/Elev= 30
  4105.1  205.39  4197.2  206.17  4309.8  202.61  4315.3  201.47  4408.2  198.23
  4503.9   195.6  4678.3  191.52  4709.1  192.93  4790.9  193.62  4811.4  192.14
  4828.7  188.76  4852.4  192.12  4883.1   191.6  4954.7  192.68  4970.6  190.79
  4975.7  188.69  4981.9  184.22  5008.6  184.22  5012.1   187.4    5019  190.18
  5026.3   189.1  5033.1  191.86  5040.4  190.93  5044.9 192.574  5047.3  193.45
  5088.6  193.91    5210  199.28  5351.6  199.38  5479.1  205.96  5556.8  208.76
#Mann= 5 ,-1 , 0
  4105.1     .05       0  4503.9      .1       0  4954.7     .07       0
  5044.9      .1       0  5088.6     .05       0
Bank Sta=4954.7,5044.9
XS Rating Curve= 0 ,0
Exp/Cntr=0.3,0.1

Type RM Length L Ch R = 1 ,77000   ,394,394,394
BEGIN DESCRIPTION:
CRYSTAL CREEK 153.0
END DESCRIPTION:
XS GIS Cut Line= 3
      3857068.93     10123102.05      3857065.93     10122089.36
      3856766.88     10121772.22
#Sta/Elev= 30
  3987.3  203.07  4108.3  198.44  4178.3  197.72  4198.3  196.17  4377.4  194.93
  4488.3  196.07  4508.3  194.48  4558.3  193.59  4672.4   195.8  4708.3  195.16
  4728.3   197.1  4788.3   196.1  4838.3  190.33  4868.3  189.48  4888.3  190.92
  4908.3  189.78  4948.3  190.88  4954.9  184.62  4981.6  184.62  4988.3  186.47
  5002.2  187.36  5004.5  189.71  5011.4  191.03  5025.5  192.07  5061.1  190.22
  5089.5  192.01  5160.3  192.37  5209.8  194.27  5365.4  203.49  5435.9  203.34
#Mann= 6 ,-1 , 0
  3987.3     .05       0  4377.4     .12       0  4672.4      .1       0
  4948.3     .07       0  5011.4      .1       0  5209.8     .05       0
Bank Sta=4948.3,5011.4
XS Rating Curve= 0 ,0
Exp/Cntr=0.3,0.1

Type RM Length L Ch R = 1 ,76606   ,566,566,566
BEGIN DESCRIPTION:
CRYSTAL CREEK 152.0
END DESCRIPTION:
XS GIS Cut Line= 3
      3858221.74     10122706.24      3857342.38     10121814.48
      3856825.87     10121390.24
#Sta/Elev= 30
  3747.6  196.22  3952.8  196.32  4079.2  193.48  4100.5  191.17  4105.6   187.7
  4114.6  187.45  4121.7  184.18  4135.8  185.22  4143.6   183.1  4170.5   183.1
 4177.44 187.551  4270.2  188.17    4311  191.66    4843  195.41  4956.1  190.66
  4991.4  183.66  5006.2  185.43  5019.3   191.8  5032.4  192.19  5083.5  184.44
  5119.7  189.82  5161.3   187.5  5197.9  189.48  5204.4  187.66  5212.3  189.56
  5247.4  187.54  5266.4  191.29  5311.4  192.98  5386.2  194.93  5668.4  203.33
#Mann= 10 ,-1 , 0
  3747.6     .05       0  3952.8     .12       0  4105.6      .1       0
  4114.6     .07       0 4177.44      .1       0    4311     .05       0
  5032.4      .1       0  5266.4     .05       0  5311.4      .1       0
  5386.2     .05       0
Bank Sta=4114.6,4177.44
XS Rating Curve= 0 ,0
Exp/Cntr=0.3,0.1

Type RM Length L Ch R = 1 ,76040   ,540,540,540
BEGIN DESCRIPTION:
CRYSTAL CREEK 151.0
END DESCRIPTION:
XS GIS Cut Line= 3
      3858275.34      10122585.2      3857652.27     10121650.42
      3856852.83     10121346.11
#Sta/Elev= 30
  3876.6  196.22  3941.6  197.18  4071.2  195.15  4115.7   193.9  4172.8  188.39
    4296  189.47    4311  187.91    4326   183.3    4332  184.72  4338.6  189.09
  4347.1  191.11  4398.1  193.76  4419.2  192.76  4635.5  193.53  4785.7  195.32
    4876  194.36    4960  193.21 4966.63 191.508  4973.7  182.02  5000.6  182.02
    5005  185.78  5016.5  191.46  5024.2  191.85  5135.4   191.9    5151  190.59
  5186.6  191.26  5250.8  189.74  5541.6  194.87  5685.5  199.59  5855.4  202.99
#Mann= 9 ,-1 , 0
  3876.6     .05       0  4071.2      .1       0  4338.6     .05       0
    4876     .12       0 4966.63     .07       0  5016.5     .12       0
  5024.2     .12       0  5135.4      .1       0  5541.6     .05       0
Bank Sta=4966.63,5016.5
XS Rating Curve= 0 ,0
Exp/Cntr=0.3,0.1

Type RM Length L Ch R = 1 ,75500   ,500,500,500
BEGIN DESCRIPTION:
CRYSTAL CREEK 150.0
END DESCRIPTION:
XS GIS Cut Line= 3
      3858280.74     10122574.28      3857648.61     10121326.46
      3857616.23     10120910.52
#Sta/Elev= 30
  3601.2  196.49  3785.6  195.16  3820.6  193.53  3837.3  189.93  3842.9  192.76
  3859.5  189.31  3865.2  191.01  3881.8  188.27  3887.4     190  3904.1  188.14
  3985.9  188.48  3993.2  185.79  4008.4  184.52  4021.1  186.68  4030.8  183.09
  4037.7  186.61  4049.9  188.97  4154.7  193.04    4550  193.73  4627.3  191.82
  4739.6  193.31  4826.7  192.97  4923.1  187.74  4967.6  190.52  4989.9  185.82
    4992  181.38  5018.9  181.38  5067.6  190.39  5145.8  197.22  5417.2  207.71
#Mann= 8 ,-1 , 0
  3601.2     .05       0  3785.6      .1       0  4049.9     .05       0
  4627.3     .12       0  4739.6      .1       0  4967.6     .07       0
  5067.6      .1       0  5067.6     .05       0
Bank Sta=4967.6,5067.6
XS Rating Curve= 0 ,0
Exp/Cntr=0.3,0.1

Type RM Length L Ch R = 1 ,75000   ,769,769,769
BEGIN DESCRIPTION:
CRYSTAL CREEK 149.0
END DESCRIPTION:
XS GIS Cut Line= 4
      3858317.62     10122555.52      3857963.45     10121602.37
      3858093.43     10121331.69      3858512.52     10120925.68
#Sta/Elev= 30
  3682.9  196.73  3865.7  195.55  3890.3  190.98    3902  185.58    3933  186.99
    3952  185.86  3957.3  182.37  3975.7  182.59    3997   188.5  4130.4  189.35
  4519.8  193.51  4632.5   191.1  4739.1  191.72  4951.6  190.17 4985.78 187.558
  5004.3  181.08  5031.3  181.08  5031.8  181.58  5031.9  185.74  5038.9  187.61
  5074.4  186.55  5088.5   190.2  5109.6  185.27    5131  186.85  5145.1   184.7
  5166.2  188.12  5187.3  185.21  5258.1   191.8  5300.9  191.82  5583.5  198.98
#Mann= 8 ,-1 , 0
  3682.9     .05       0  3865.7      .1       0  4130.4     .05       0
  4632.5     .12       0  4739.1      .1       0 4985.78     .07       0
  5038.9      .1       0  5300.9     .05       0
Bank Sta=4985.78,5038.9
XS Rating Curve= 0 ,0
Exp/Cntr=0.3,0.1

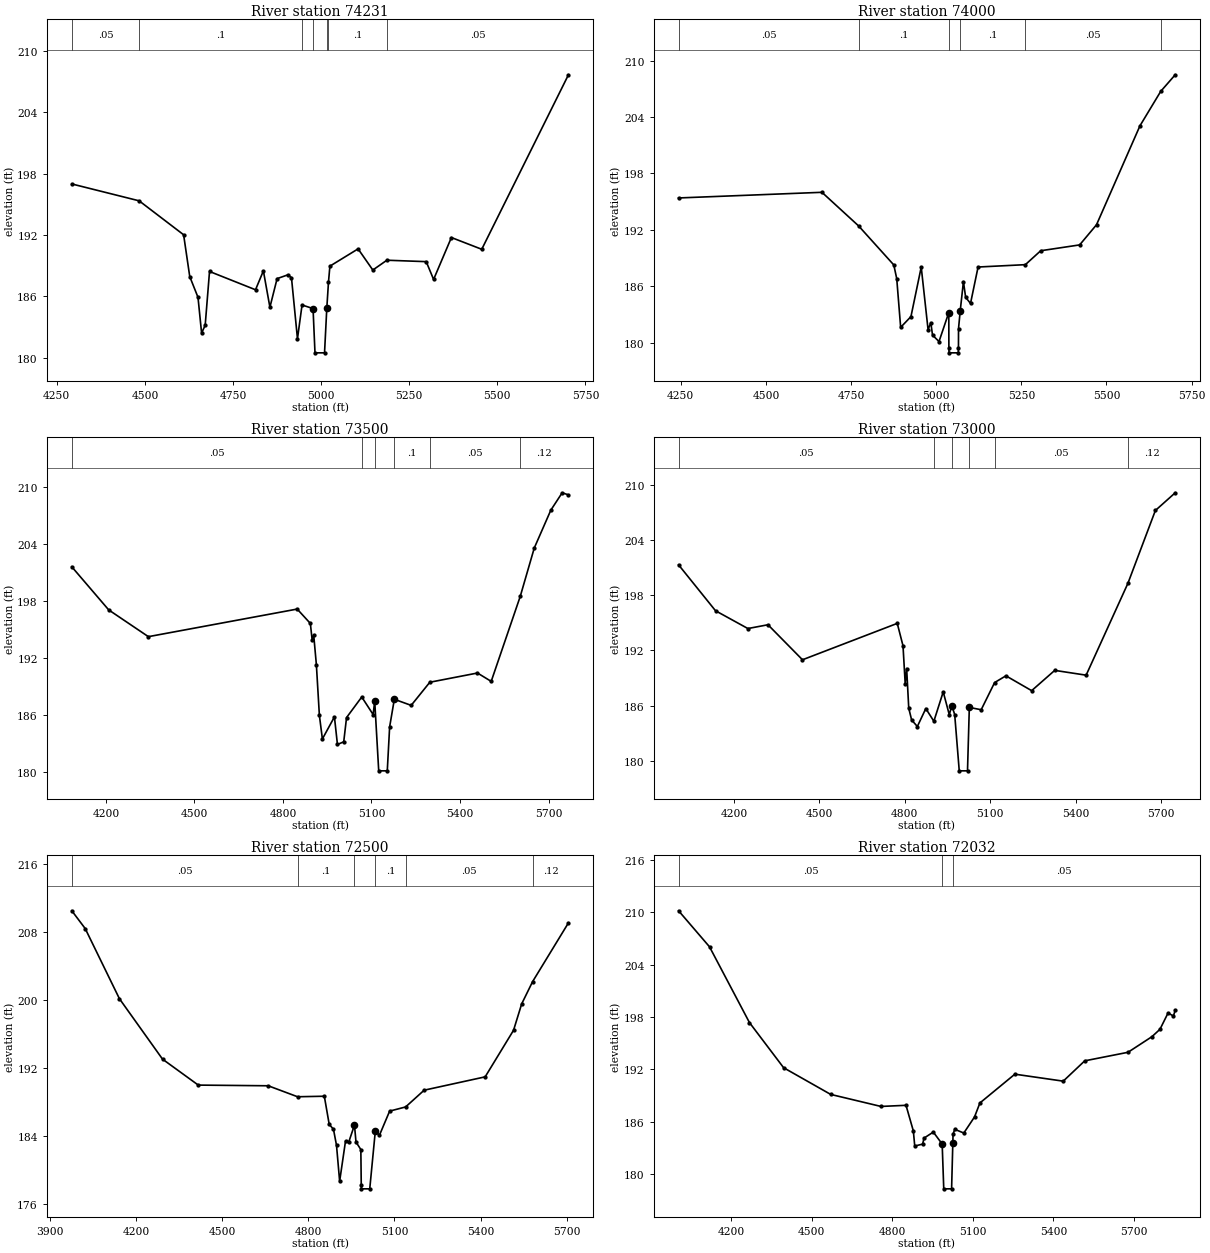
Type RM Length L Ch R = 1 ,74231   ,231,231,231
BEGIN DESCRIPTION:
CRYSTAL CREEK 148.0
END DESCRIPTION:
XS GIS Cut Line= 3
      3858339.05     10122542.11      3858200.01     10121848.62
      3858773.09      10121443.7
#Sta/Elev= 30
  4292.7  196.99  4483.7  195.34  4609.9  192.02  4627.3  187.93  4650.7   185.9
  4660.9   182.4  4671.1  183.17  4683.4  188.43  4813.9  186.64  4836.2  188.49
  4854.7  184.93  4875.1  187.73  4905.7   188.1  4915.9  187.82  4932.9  181.85
  4945.9  185.15  4977.1   184.8  4982.6  180.47  5009.7  180.47 5016.09 184.823
  5020.9  187.39  5024.9  188.95  5104.9  190.64  5146.7  188.57  5186.6  189.53
  5298.2  189.39  5319.1  187.65  5369.6  191.75  5455.7   190.6  5701.7  207.67
#Mann= 7 ,-1 , 0
  4292.7     .05       0  4483.7      .1       0  4945.9     .05       0
  4977.1     .07       0 5016.09     .05       0  5020.9      .1       0
  5186.6     .05       0
Bank Sta=4977.1,5016.09
XS Rating Curve= 0 ,0
Exp/Cntr=0.3,0.1

Type RM Length L Ch R = 1 ,74000   ,500,500,500
BEGIN DESCRIPTION:
CRYSTAL CREEK 147.0
END DESCRIPTION:
XS GIS Cut Line= 3
       3858427.5     10122759.82      3858351.58     10122007.34
      3858799.37     10121466.97
#Sta/Elev= 30
  4243.7   195.4  4664.6     196  4772.2  192.43  4875.6  188.28  4884.2  186.82
  4895.7  181.65  4925.9  182.79  4956.1  188.05  4976.2   181.4  4984.2  182.15
  4989.3  180.82  5008.3  180.14    5037  183.22  5037.3  179.44  5037.8  178.94
  5064.9  178.94  5065.4  179.44  5065.6  181.52 5070.53 183.393    5080  186.51
  5086.5  184.84  5100.8  184.19    5123  188.06  5261.8  188.31  5306.9  189.79
  5421.2  190.41  5470.7  192.55  5598.3  203.07  5659.3  206.73  5701.8  208.49
#Mann= 6 ,-1 , 0
  4243.7     .05       0  4772.2      .1       0    5037     .07       0
 5070.53      .1       0  5261.8     .05       0  5659.3     .12       0
Bank Sta=5037,5070.53
XS Rating Curve= 0 ,0
Exp/Cntr=0.3,0.1

Type RM Length L Ch R = 1 ,73500   ,500,500,500
BEGIN DESCRIPTION:
CRYSTAL CREEK 146.0
END DESCRIPTION:
XS GIS Cut Line= 3
      3858422.52     10123113.72      3858602.43     10122215.98
      3858820.21     10121480.02
#Sta/Elev= 30
  4084.4  201.59  4209.5  197.06  4343.9  194.25  4848.2  197.15  4892.8  195.64
  4899.1  193.85  4904.2   194.4  4913.2  191.32  4923.4  185.98  4933.6   183.5
  4974.4  185.82  4984.6  182.92  5005.9   183.2  5015.5  185.75    5067  187.91
  5105.7  186.06  5110.9  187.49  5124.5  180.15  5153.5  180.15  5161.5  184.77
  5177.4  187.67  5234.5  187.03  5297.7  189.46  5459.2  190.43  5505.7  189.55
  5604.1  198.48  5651.7  203.57  5707.7  207.54  5746.2  209.37  5767.5  209.15
#Mann= 6 ,-1 , 0
  4084.4     .05       0    5067      .1       0  5110.9     .07       0
  5177.4      .1       0  5297.7     .05       0  5604.1     .12       0
Bank Sta=5110.9,5177.4
XS Rating Curve= 0 ,0
Exp/Cntr=0.3,0.1

Type RM Length L Ch R = 1 ,73000   ,500,500,500
BEGIN DESCRIPTION:
CRYSTAL CREEK 145.0
END DESCRIPTION:
XS GIS Cut Line= 3
      3859190.68     10123182.34      3859056.43     10122196.84
      3858843.65     10121477.35
#Sta/Elev= 30
  4005.4  201.29  4135.2  196.31  4248.9  194.38  4319.5  194.79  4440.7  190.99
  4773.7  194.94  4793.9  192.51  4801.6   188.4  4806.7  190.04  4814.1  185.73
  4824.2  184.46  4844.3  183.75    4874   185.7  4902.3  184.32  4935.2  187.51
  4956.4  185.04  4965.5  186.01  4975.5  185.05  4991.5  178.94  5020.5  178.94
  5026.9  185.82  5068.6  185.57  5115.8  188.52  5155.5  189.25  5245.9  187.64
    5327  189.84  5437.3  189.32    5584  199.28  5680.6  207.19  5750.3  209.11
#Mann= 6 ,-1 , 0
  4005.4     .05       0  4902.3      .1       0  4965.5     .07       0
  5026.9      .1       0  5115.8     .05       0    5584     .12       0
Bank Sta=4965.5,5026.9
XS Rating Curve= 0 ,0
Exp/Cntr=0.3,0.1

Type RM Length L Ch R = 1 ,72500   ,468,468,468
BEGIN DESCRIPTION:
CRYSTAL CREEK 144.0
END DESCRIPTION:
XS GIS Cut Line= 3
      3859717.85     10122911.08      3859381.39     10121944.99
      3858867.87     10121461.09
#Sta/Elev= 30
    3977  210.45  4023.6  208.36  4142.7  200.11  4292.8     193  4417.2  189.95
  4660.6  189.87  4762.7  188.58  4855.9  188.64  4872.9  185.33  4887.7  184.76
  4898.3  182.87  4909.2  178.64  4929.7  183.38  4940.6  183.22  4960.8  185.25
  4966.1  183.26    4983  182.37  4984.4  178.25  4984.9  177.75    5014  177.75
  5033.4  184.56  5047.6  184.04  5083.2  186.89  5138.8  187.38  5203.3  189.35
  5415.7  190.92  5514.5   196.4  5542.8   199.5    5581  202.13  5705.6  209.03
#Mann= 6 ,-1 , 0
    3977     .05       0  4762.7      .1       0  4960.8     .07       0
  5033.4      .1       0  5138.8     .05       0    5581     .12       0
Bank Sta=4960.8,5033.4
XS Rating Curve= 0 ,0
Exp/Cntr=0.3,0.1

Type RM Length L Ch R = 1 ,72032   ,532,532,532
BEGIN DESCRIPTION:
CRYSTAL CREEK 143.0
END DESCRIPTION:
XS GIS Cut Line= 3
      3860002.66     10122888.69      3859741.29     10121927.18
      3859781.28     10121074.32
#Sta/Elev= 30
  4003.6  210.18  4118.8  206.05  4267.6  197.36  4394.9  192.18  4570.3  189.12
  4757.6  187.74  4850.9  187.87  4878.2  184.93  4883.4   183.2  4912.8  183.42
    4918  184.11  4952.6   184.8  4985.6  183.43  4991.5  178.29  5020.7  178.29
  5025.3 183.601  5026.1  184.54  5032.3  185.12  5066.2  184.69  5106.2  186.54
  5126.2  188.14  5256.4  191.44  5436.6  190.64  5516.7  192.97  5677.9  193.95
    5767  195.74    5797  196.59    5827  198.45    5847  198.12  5853.8  198.75
#Mann= 3 , 0 , 0
  4003.6     .05       0  4985.6     .03       0  5025.3     .05       0
Bank Sta=4985.6,5025.3
XS Rating Curve= 0 ,0
Exp/Cntr=0.3,0.1

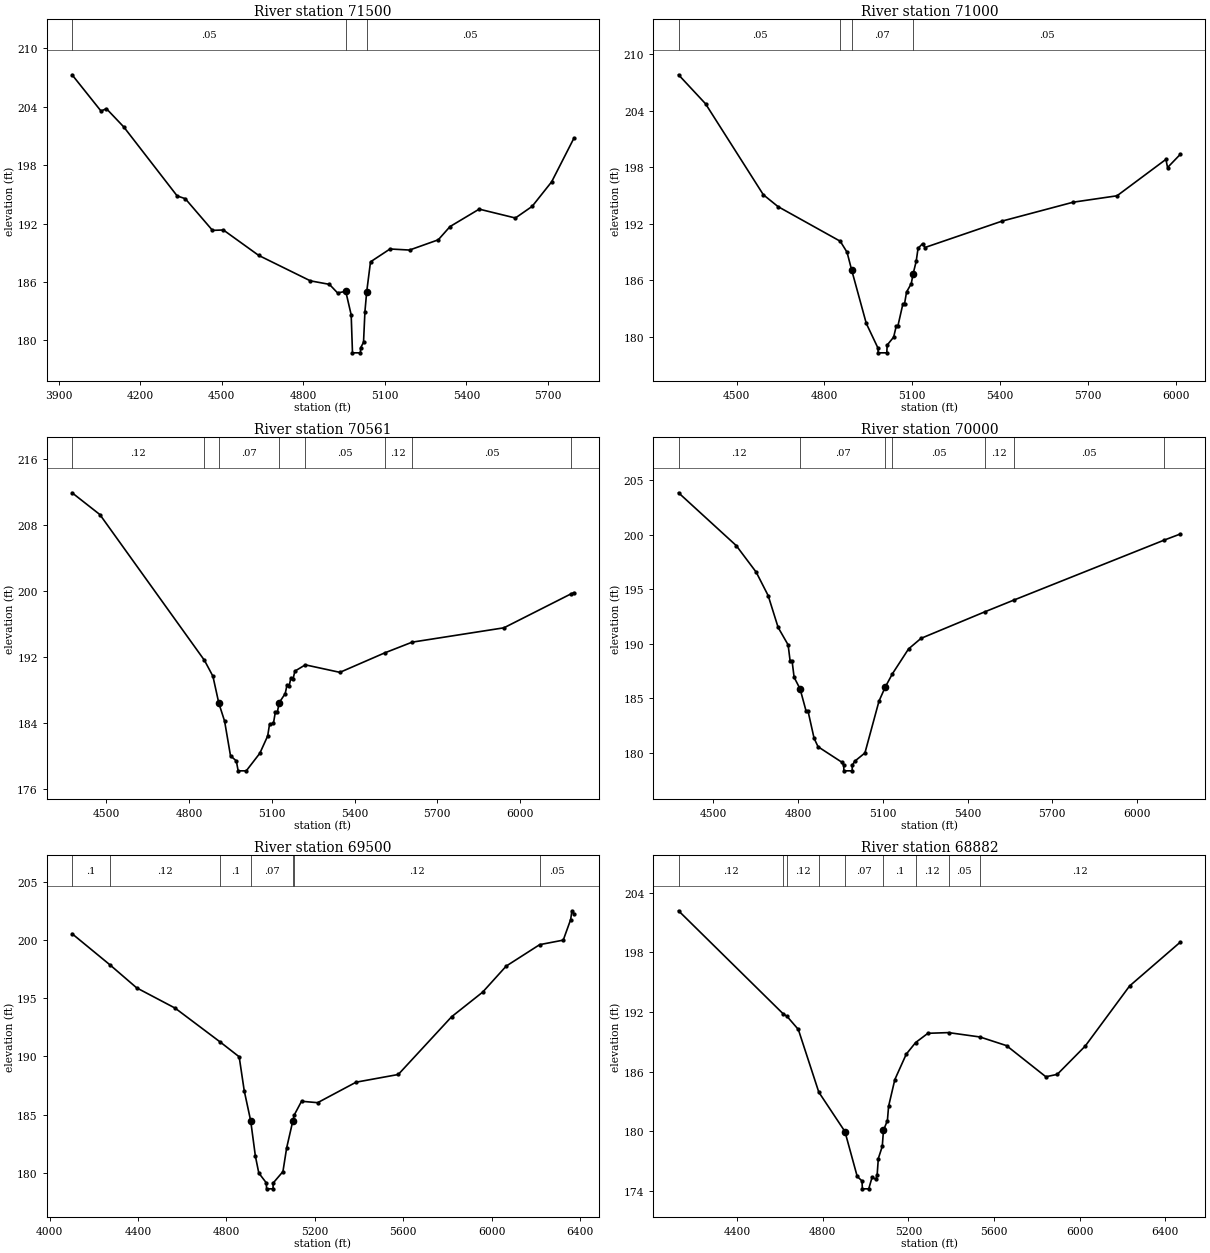
Type RM Length L Ch R = 1 ,71500   ,500,500,500
BEGIN DESCRIPTION:
CRYSTAL CREEK 142.0
END DESCRIPTION:
XS GIS Cut Line= 3
      3860077.44     10122877.41      3860107.56     10121827.24
      3859932.86     10121051.26
#Sta/Elev= 30
  3949.4  207.27  4055.8  203.55  4075.8  203.79  4139.5  201.92  4335.9  194.84
  4365.9  194.55    4466   191.3    4506  191.34    4636  188.73  4826.1  186.12
  4896.1  185.76  4926.1  184.88  4956.2  185.04  4976.2  182.63    4981  178.73
  5010.2  178.73  5010.7  179.23  5021.6  179.81  5026.8  182.96 5033.09 184.951
  5047.3  188.07  5119.1  189.39  5190.8  189.28  5296.5  190.33  5339.8  191.69
  5447.1  193.48  5580.3  192.57  5641.8  193.76  5713.6  196.28  5795.4  200.75
#Mann= 3 , 0 , 0
  3949.4     .05       0  4956.2     .07       0 5033.09     .05       0
Bank Sta=4956.2,5033.09
XS Rating Curve= 0 ,0
Exp/Cntr=0.3,0.1

Type RM Length L Ch R = 1 ,71000   ,439,439,439
BEGIN DESCRIPTION:
CRYSTAL CREEK 141.0
END DESCRIPTION:
XS GIS Cut Line= 3
      3860640.34     10122609.46      3860582.68     10121914.04
      3860162.92     10120990.57
#Sta/Elev= 30
  4302.2  207.84  4394.3  204.76  4591.6  195.09  4641.7  193.83    4854  190.15
  4877.2  188.98  4892.6  187.13  4942.8  181.42  4982.8  178.79  4983.3  178.29
  5012.7  178.29  5014.2  179.12  5036.2  179.96  5044.8   181.1  5050.3  181.09
  5067.9  183.51  5073.4   183.5  5080.2  184.75  5096.4  185.65  5102.1  186.62
  5113.1  188.01  5119.5   189.4  5135.1   189.9  5142.6  189.48  5407.3   192.3
    5649   194.3  5798.4  194.98  5965.3  198.85  5970.8  197.98  6014.4  199.39
#Mann= 4 ,-1 , 0
  4302.2     .05       0    4854      .1       0  4892.6     .07       0
  5102.1     .05       0
Bank Sta=4892.6,5102.1
XS Rating Curve= 0 ,0
Exp/Cntr=0.3,0.1

Type RM Length L Ch R = 1 ,70561   ,561,561,561
BEGIN DESCRIPTION:
CRYSTAL CREEK 140.0
END DESCRIPTION:
XS GIS Cut Line= 3
      3861453.67      10122287.7      3861003.14     10121855.09
       3860215.1     10120955.95
#Sta/Elev= 30
  4375.4  211.88  4476.2  209.24  4855.7  191.56  4886.3  189.64  4907.7  186.38
  4928.7  184.19  4950.1     180  4971.2  179.37  4977.9  178.17  5007.3  178.17
  5056.5   180.3    5085   182.4  5091.6   183.8  5105.9  183.93  5112.5  185.25
  5120.1   185.3  5126.7  186.43  5148.6  187.54  5155.2  188.59  5162.8  188.46
  5169.4  189.47    5177  189.31  5183.7  190.26  5221.5  191.02  5346.9  190.11
  5508.8  192.46    5609  193.77  5941.9  195.51    6185  199.62  6195.6  199.77
#Mann= 8 ,-1 , 0
  4375.4     .12       0  4855.7      .1       0  4907.7     .07       0
  5126.7      .1       0  5221.5     .05       0  5508.8     .12       0
    5609     .05       0    6185     .12       0
Bank Sta=4907.7,5126.7
XS Rating Curve= 0 ,0
Exp/Cntr=0.3,0.1

Type RM Length L Ch R = 1 ,70000   ,500,500,500
BEGIN DESCRIPTION:
CRYSTAL CREEK 139.0
END DESCRIPTION:
XS GIS Cut Line= 3
      3861679.93     10121887.96      3861240.41     10121445.57
      3860217.88     10120911.09
#Sta/Elev= 30
  4376.4  203.84  4580.7     199  4651.5  196.56  4693.9  194.41  4729.2  191.49
  4764.6  189.89  4771.6  188.42  4778.7  188.39  4785.8  186.92    4807  185.85
  4828.2  183.82  4835.3  183.79  4856.5  181.33  4870.6  180.55  4955.5  179.12
  4961.5  178.84    4962  178.34  4991.4  178.34  4991.9  178.84    5000  179.21
  5036.6  179.98  5086.4  184.73  5108.5  186.02    5134  187.24  5191.1  189.52
  5235.3  190.49    5462  192.93  5563.2  193.99  6097.7  199.51  6153.8  200.06
#Mann= 7 ,-1 , 0
  4376.4     .12       0    4807     .07       0  5108.5      .1       0
    5134     .05       0    5462     .12       0  5563.2     .05       0
  6097.7     .12       0
Bank Sta=4807,5108.5
XS Rating Curve= 0 ,0
Exp/Cntr=0.3,0.1

Type RM Length L Ch R = 1 ,69500   ,618,618,618
BEGIN DESCRIPTION:
CRYSTAL CREEK 138.0
END DESCRIPTION:
XS GIS Cut Line= 3
      3861876.13     10121744.93      3861405.41     10120979.13
      3860174.76     10120372.37
#Sta/Elev= 30
  4101.1  200.54  4271.1  197.89  4393.5  195.89  4567.5  194.15  4770.8  191.25
  4857.4  189.97  4880.3  187.05  4909.5  184.47  4930.8  181.43  4946.2  179.99
  4980.7  179.13  4981.2  178.63  5010.7  178.63  5011.2  179.13  5055.4  180.11
  5072.3  182.15  5100.3  184.47  5106.3  184.96  5139.6  186.15  5212.6  186.03
  5386.6  187.79  5577.4  188.45  5818.9  193.41  5959.2  195.52  6065.9  197.76
  6217.3   199.6  6324.1  199.99  6357.5  201.75  6363.4  202.51  6372.1  202.26
#Mann= 7 ,-1 , 0
  4101.1      .1       0  4271.1     .12       0  4770.8      .1       0
  4909.5     .07       0  5100.3      .1       0  5106.3     .12       0
  6217.3     .05       0
Bank Sta=4909.5,5100.3
XS Rating Curve= 0 ,0
Exp/Cntr=0.3,0.1

Type RM Length L Ch R = 1 ,68882   ,382,382,382
BEGIN DESCRIPTION:
CRYSTAL CREEK 137.0
END DESCRIPTION:
XS GIS Cut Line= 3
      3862169.54     10121679.67      3861803.61     10120885.19
      3861243.21     10119525.23
#Sta/Elev= 30
  4125.3  202.17  4612.9  191.84    4633  191.54  4685.2  190.24    4781  183.93
  4903.1  179.97  4960.5  175.46    4983     175  4984.6  174.21  5014.4  174.21
  5029.9  175.36  5047.7  175.17  5053.8  175.64  5059.2  177.26  5077.7  178.48
  5083.2  180.09  5101.7  181.08  5107.1   182.5  5136.4   185.2  5189.7  187.75
  5233.5  188.92  5290.9  189.85  5387.5  189.92  5534.3  189.48  5658.5  188.61
  5842.3  185.48  5895.6  185.72  6026.1  188.56  6233.8  194.61  6470.9  199.02
#Mann= 9 ,-1 , 0
  4125.3     .12       0  4612.9     .05       0    4633     .12       0
    4781      .1       0  4903.1     .07       0  5083.2      .1       0
  5233.5     .12       0  5387.5     .05       0  5534.3     .12       0
Bank Sta=4903.1,5083.2
XS Rating Curve= 0 ,0
Exp/Cntr=0.3,0.1

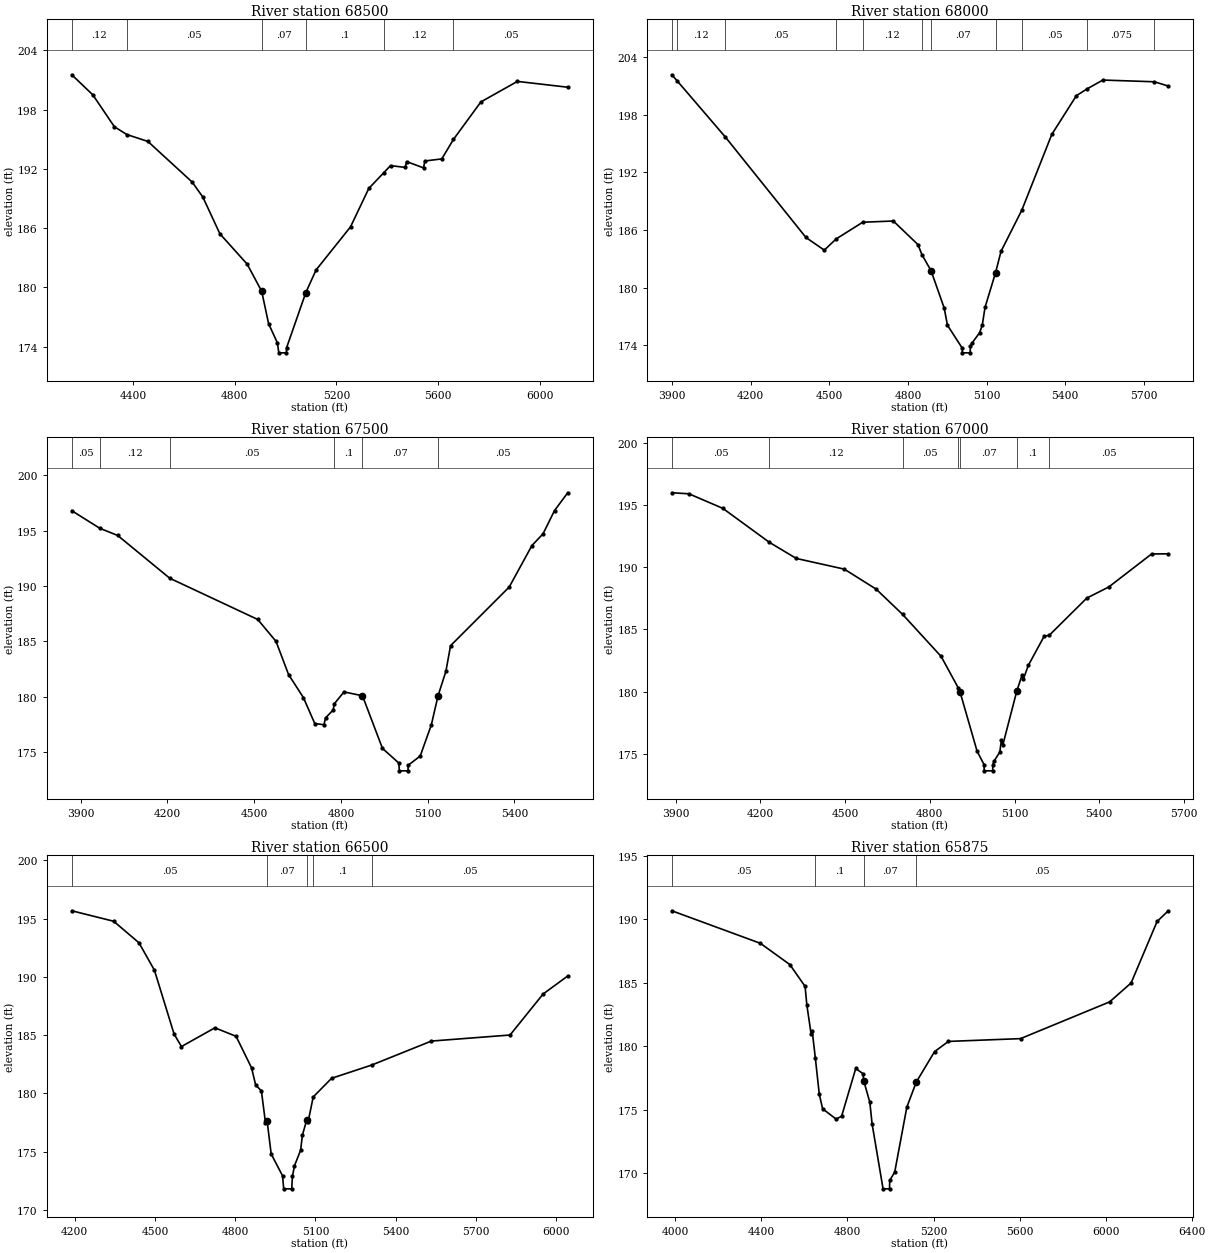
Type RM Length L Ch R = 1 ,68500   ,500,500,500
BEGIN DESCRIPTION:
CRYSTAL CREEK 136.0
END DESCRIPTION:
XS GIS Cut Line= 3
      3862351.82     10121627.55      3862157.84     10120810.05
      3862310.15     10119710.95
#Sta/Elev= 30
  4159.8  201.52  4242.8  199.48  4327.2  196.26  4376.1  195.47    4459  194.77
  4632.9  190.66  4675.2  189.13    4742  185.42  4849.1  182.35  4906.4   179.6
  4933.6  176.31  4968.1  174.37  4973.8  173.36  5003.6  173.36  5004.1  173.86
  5079.7  179.45  5120.1  181.75  5255.7  186.12  5327.5  190.01    5386  191.59
  5412.9  192.32    5471  192.14    5476  192.73  5542.8  192.09  5547.8  192.79
  5614.5     193  5660.2  194.97  5768.1  198.77  5911.7  200.85  6109.6  200.26
#Mann= 6 ,-1 , 0
  4159.8     .12       0  4376.1     .05       0  4906.4     .07       0
  5079.7      .1       0    5386     .12       0  5660.2     .05       0
Bank Sta=4906.4,5079.7
XS Rating Curve= 0 ,0
Exp/Cntr=0.3,0.1

Type RM Length L Ch R = 1 ,68000   ,500,500,500
BEGIN DESCRIPTION:
CRYSTAL CREEK 135.0
END DESCRIPTION:
XS GIS Cut Line= 3
      3862747.66     10121570.29      3862520.68     10120493.14
      3862362.55      10119717.6
#Sta/Elev= 30
  3899.2  202.19  3918.5  201.59  4103.7  195.69    4411  185.22  4480.9   183.9
  4526.2  185.07  4627.5  186.81  4744.3  186.94  4838.6  184.47  4853.3  183.44
  4888.5  181.74  4938.3  177.87    4951  176.06  5007.1  173.69  5007.6  173.19
  5037.4  173.19  5038.5  173.87  5043.6  174.17  5073.6  175.29  5083.8  176.09
  5094.2  177.93  5134.5  181.56  5155.2  183.77  5234.9  188.09  5349.1  195.98
  5442.8  200.01  5484.8  200.74  5543.9  201.64  5740.5  201.46  5791.5  201.03
#Mann= 11 ,-1 , 0
  3899.2     .05       0  3918.5     .12       0  4103.7     .05       0
  4526.2      .1       0  4627.5     .12       0  4853.3      .1       0
  4888.5     .07       0  5134.5      .1       0  5234.9     .05       0
  5484.8    .075       0  5740.5     .05       0
Bank Sta=4888.5,5134.5
XS Rating Curve= 0 ,0
Exp/Cntr=0.3,0.1

Type RM Length L Ch R = 1 ,67500   ,500,500,500
BEGIN DESCRIPTION:
CRYSTAL CREEK 134.0
END DESCRIPTION:
XS GIS Cut Line= 3
      3863283.33     10121342.65      3862933.86     10120267.31
      3862767.71     10119707.24
#Sta/Elev= 30
  3869.3  196.81  3966.1  195.22    4028  194.57  4208.1   190.7  4512.4  186.97
  4575.5  184.99  4618.9  181.99  4670.1  179.91  4709.5  177.56  4741.4  177.45
  4746.7  178.07  4773.4  178.79  4776.6  179.33  4810.6  180.42  4874.5  180.07
  4943.6  175.31    5000  173.99    5002  173.28  5031.9  173.28  5032.4  173.78
  5074.1  174.62  5112.5  177.43  5135.6 180.054    5163  182.29    5179   184.6
    5382  189.91  5460.4  193.66  5498.9  194.72  5538.5  196.82  5584.2  198.43
#Mann= 6 ,-1 , 0
  3869.3     .05       0  3966.1     .12       0  4208.1     .05       0
  4776.6      .1       0  4874.5     .07       0  5135.6     .05       0
Bank Sta=4874.5,5135.6
XS Rating Curve= 0 ,0
Exp/Cntr=0.3,0.1

Type RM Length L Ch R = 1 ,67000   ,500,500,500
BEGIN DESCRIPTION:
CRYSTAL CREEK 133.0
END DESCRIPTION:
XS GIS Cut Line= 3
      3863361.46     10121311.42      3863409.91     10120198.57
        3863325.     10119561.41
#Sta/Elev= 30
  3886.1  195.99  3946.5  195.91  4066.6  194.74  4231.3  192.01  4326.9  190.71
    4497  189.85  4609.9  188.24  4703.5  186.21    4840  182.83    4900  180.33
  4907.4  179.94  4967.5   175.2  4992.1  174.13  4992.6  173.63  5022.6  173.63
  5023.1  174.13  5027.7  174.42  5047.9  175.14  5053.2  176.07  5058.3  175.69
  5108.5  180.09  5126.4   181.3  5131.4  181.01  5148.8  182.11  5204.6  184.44
  5223.4  184.54  5355.9  187.52  5434.1  188.42  5585.5  191.07  5642.8  191.08
#Mann= 7 ,-1 , 0
  3886.1     .05       0  4231.3     .12       0  4703.5     .05       0
    4900     .12       0  4907.4     .07       0  5108.5      .1       0
  5223.4     .05       0
Bank Sta=4907.4,5108.5
XS Rating Curve= 0 ,0
Exp/Cntr=0.3,0.1

Type RM Length L Ch R = 1 ,66500   ,625,625,625
BEGIN DESCRIPTION:
CRYSTAL CREEK 132.0
END DESCRIPTION:
XS GIS Cut Line= 3
       3864314.6      10121030.2       3863888.8     10120339.62
      3863366.65     10119436.38
#Sta/Elev= 30
  4188.7  195.68  4345.4  194.78    4440  192.93  4497.9  190.57  4571.3  185.09
  4598.9  184.02  4723.9  185.63  4803.1   184.9    4861  182.19  4876.4  180.71
  4897.7  180.22  4913.1  177.47    4919  177.65  4934.4  174.79  4976.9  172.92
  4981.2   171.8  5011.2   171.8  5013.8  172.87  5021.4  173.78  5044.5  175.12
  5051.1  176.41  5066.8  177.68  5072.6  177.57  5091.5  179.69    5160  181.29
  5311.3  182.44  5533.4  184.49  5827.6  185.01  5951.1  188.53  6043.3  190.08
#Mann= 5 ,-1 , 0
  4188.7     .05       0    4919     .07       0  5066.8     .05       0
  5091.5      .1       0  5311.3     .05       0
Bank Sta=4919,5066.8
XS Rating Curve= 0 ,0
Exp/Cntr=0.3,0.1

Type RM Length L Ch R = 1 ,65875   ,633,633,633
BEGIN DESCRIPTION:
CRYSTAL CREEK 131.0
END DESCRIPTION:
XS GIS Cut Line= 3
       3865408.3     10120405.16      3864435.95     10120109.87
      3863408.32     10119332.24
#Sta/Elev= 30
  3983.8  190.66  4395.4   188.1  4532.1  186.43  4603.1  184.71  4611.3  183.25
  4630.8     181    4636  181.23  4650.6   179.1  4668.9  176.25  4684.5  175.08
  4747.2  174.27  4772.8  174.49  4838.5  178.25  4871.4  177.85  4876.6  177.23
    4904  175.59  4914.7  173.87  4965.5  168.78  4995.5  168.78  4996.4  169.44
  5019.7   170.1  5075.9   175.2  5119.5  177.17  5204.9  179.58  5269.3  180.38
  5604.4   180.6  6018.4  183.49  6118.3  184.98  6239.1  189.82  6288.7  190.62
#Mann= 4 ,-1 , 0
  3983.8     .05       0  4650.6      .1       0  4876.6     .07       0
  5119.5     .05       0
Bank Sta=4876.6,5119.5
XS Rating Curve= 0 ,0
Exp/Cntr=0.3,0.1

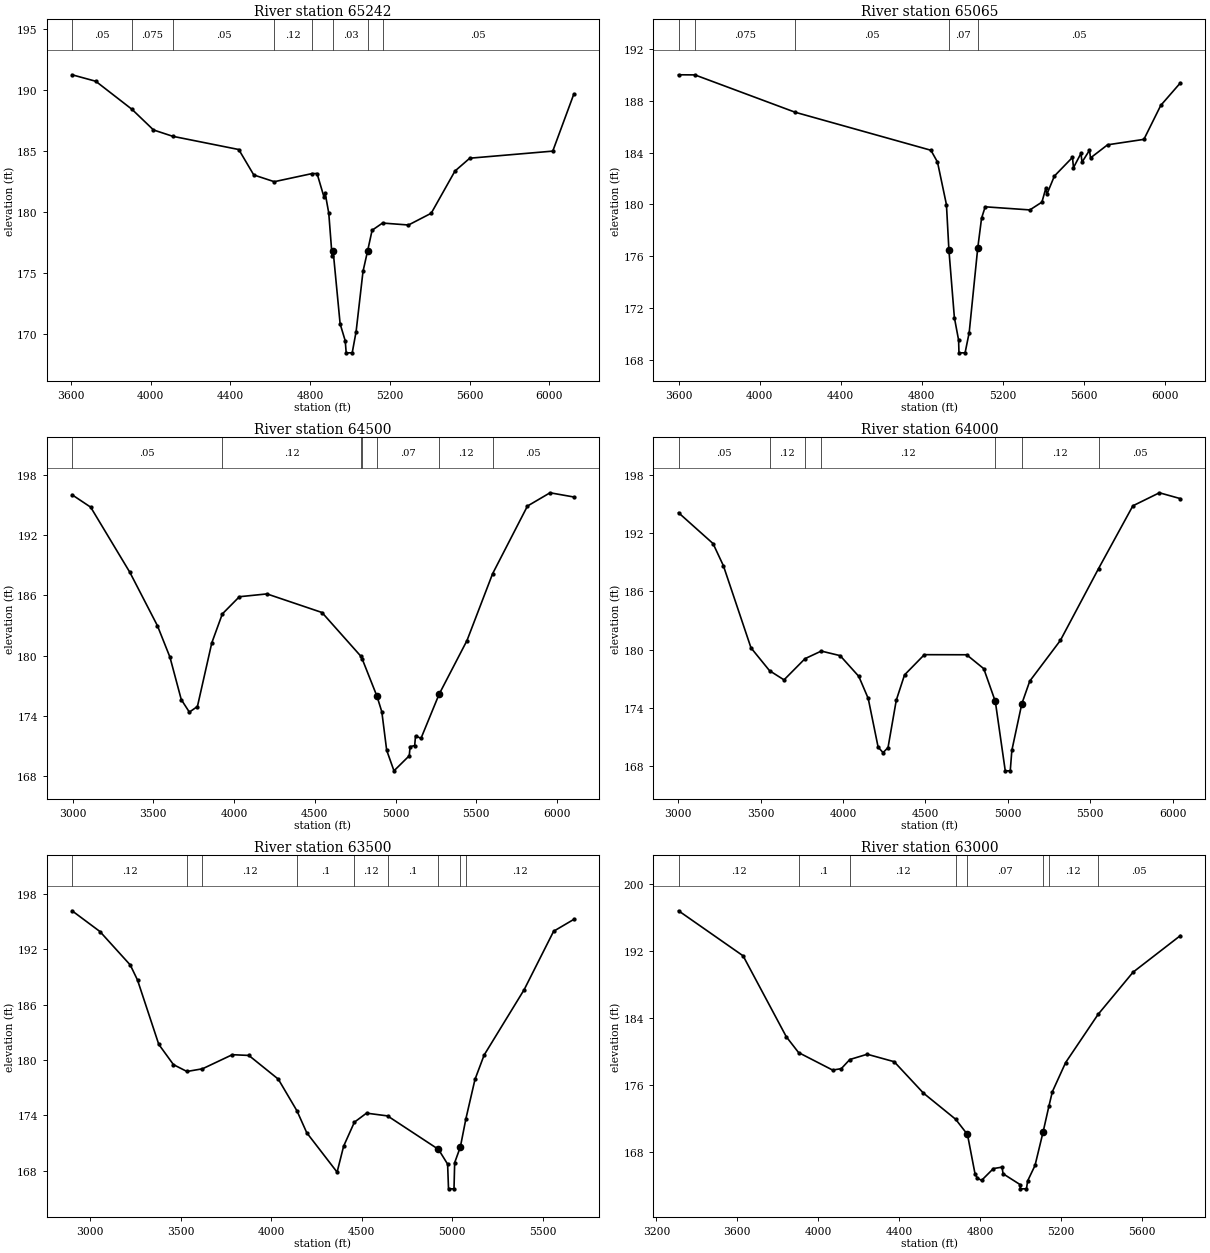
Type RM Length L Ch R = 1 ,65242   ,177,177,177
BEGIN DESCRIPTION:
CRYSTAL CREEK 130.0
END DESCRIPTION:
XS GIS Cut Line= 3
      3865892.72     10119868.71      3864544.64     10119513.47
      3863461.62       10119218.
#Sta/Elev= 30
  3605.9  191.23  3724.7   190.7  3906.8   188.4  4014.2  186.72  4111.1   186.2
  4441.9  185.12  4517.3  183.04    4620  182.49  4808.6  183.15  4834.6  183.16
  4869.7  181.22  4874.9  181.58  4893.3  179.93    4910   176.4  4915.2  176.84
  4950.3  170.87    4976  169.48  4980.7   168.5  5010.9   168.5  5030.5  170.24
  5065.1  175.16  5088.3 176.844  5110.7  178.52    5163  179.11  5293.1  178.95
  5407.1  179.91  5526.3  183.36  5600.5  184.41  6016.8  184.99  6122.6  189.66
#Mann= 8 ,-1 , 0
  3605.9     .05       0  3906.8    .075       0  4111.1     .05       0
    4620     .12       0  4808.6     .05       0  4915.2     .03       0
  5088.3      .1       0    5163     .05       0
Bank Sta=4915.2,5088.3
XS Rating Curve= 0 ,0
Exp/Cntr=0.3,0.1

Type RM Length L Ch R = 1 ,65065   ,565,565,565
BEGIN DESCRIPTION:
CRYSTAL CREEK 129.0
END DESCRIPTION:
XS GIS Cut Line= 3
       3865913.5      10119743.7      3864570.52     10119342.95
       3863522.9     10119092.67
#Sta/Elev= 30
  3598.5     190  3679.4  189.99  4174.8  187.11  4845.1  184.18  4877.6  183.27
  4921.8  179.99 4934.11 176.472    4961  171.28  4981.9  169.54  4983.7  168.56
  5013.9  168.56  5034.2  170.12  5076.2  176.61  5095.3  178.94  5113.2  179.82
  5333.9  179.58  5393.4  180.18  5412.9  181.26    5418  180.79    5455  182.19
  5544.3  183.63  5549.4  182.84  5586.3  183.94  5591.5  183.26  5628.4  184.18
  5633.6  183.59  5717.7   184.6  5897.2  185.02  5980.5  187.64  6077.1  189.37
#Mann= 5 ,-1 , 0
  3598.5     .05       0  3679.4    .075       0  4174.8     .05       0
 4934.11     .07       0  5076.2     .05       0
Bank Sta=4934.11,5076.2
XS Rating Curve= 0 ,0
Exp/Cntr=0.3,0.1

Type RM Length L Ch R = 1 ,64500   ,500,500,500
BEGIN DESCRIPTION:
CRYSTAL CREEK 128.0
END DESCRIPTION:
XS GIS Cut Line= 3
      3867022.87     10119196.84      3865022.89     10119079.81
      3863961.62     10118775.31
#Sta/Elev= 30
  2996.6     196  3111.8  194.77  3354.7  188.28  3525.4  182.97  3602.7  179.85
  3672.8  175.63  3722.9  174.38  3772.9  174.94  3861.9  181.27  3927.2  184.15
  4032.6  185.86  4203.4  186.14  4544.3  184.29  4786.2  179.92  4794.1  179.64
  4884.8  175.96  4914.9  174.41  4944.9  170.59  4990.1  168.54  5084.7  170.04
  5089.9  170.94  5118.4  171.06  5123.6  172.02  5157.4  171.77    5269  176.14
  5442.2   181.5  5600.9  188.15  5816.7  194.88  5956.7   196.2  6104.1  195.78
#Mann= 7 ,-1 , 0
  2996.6     .05       0  3927.2     .12       0  4786.2      .1       0
  4794.1     .12       0  4884.8     .07       0    5269     .12       0
  5600.9     .05       0
Bank Sta=4884.8,5269
XS Rating Curve= 0 ,0
Exp/Cntr=0.3,0.1

Type RM Length L Ch R = 1 ,64000   ,500,500,500
BEGIN DESCRIPTION:
CRYSTAL CREEK 127.0
END DESCRIPTION:
XS GIS Cut Line= 3
      3866996.88     10118712.46      3865002.28     10118590.97
      3863961.64     10118707.12
#Sta/Elev= 30
  3001.7  194.08  3211.1  190.91  3273.8  188.64  3441.5  180.19  3554.3  177.84
  3641.9   176.9  3769.4  179.08    3868  179.86  3982.5  179.39  4095.7  177.26
  4152.9  174.99    4213  169.99    4243  169.42  4273.1  169.94  4323.2  174.81
  4373.3  177.41  4493.5  179.49  4750.3  179.48  4854.2  178.05  4924.3  174.68
  4984.6  167.55  5014.9  167.55  5024.6  169.65    5085  174.44  5133.2  176.77
  5318.9  180.95  5550.5  188.33  5759.1  194.79  5920.1  196.13  6047.1  195.53
#Mann= 7 ,-1 , 0
  3001.7     .05       0  3554.3     .12       0  3769.4     .05       0
    3868     .12       0  4924.3     .07       0    5085     .12       0
  5550.5     .05       0
Bank Sta=4924.3,5085
XS Rating Curve= 0 ,0
Exp/Cntr=0.3,0.1

Type RM Length L Ch R = 1 ,63500   ,500,500,500
BEGIN DESCRIPTION:
CRYSTAL CREEK 126.0
END DESCRIPTION:
XS GIS Cut Line= 3
       3866986.5     10118394.76      3864902.32     10118138.29
      3864236.42       10118051.
#Sta/Elev= 30
  2900.1  196.18    3054  193.93  3221.5   190.3  3261.5  188.67    3379  181.69
  3460.2  179.49  3534.5  178.75  3620.3  179.04  3785.2  180.57  3876.5  180.49
    4039  177.92  4142.5  174.47  4196.4   172.1  4363.9  167.83    4400  170.65
  4459.4  173.25  4526.4  174.23  4642.7  173.93  4923.9   170.3  4974.3   168.7
  4979.3  166.02  5009.6  166.02  5013.3  168.86  5044.8  170.57  5075.5  173.64
  5125.5  177.89    5176  180.53  5397.3  187.63  5559.9  193.96  5671.6  195.25
#Mann= 9 ,-1 , 0
  2900.1     .12       0  3534.5      .1       0  3620.3     .12       0
  4142.5      .1       0  4459.4     .12       0  4642.7      .1       0
  4923.9     .03       0  5044.8     .05       0  5075.5     .12       0
Bank Sta=4923.9,5044.8
XS Rating Curve= 0 ,0
Exp/Cntr=0.3,0.1

Type RM Length L Ch R = 1 ,63000   ,610,610,610
BEGIN DESCRIPTION:
CRYSTAL CREEK 125.0
END DESCRIPTION:
XS GIS Cut Line= 3
      3866997.07      10118337.2      3865349.76     10117956.15
       3864684.8     10117531.12
#Sta/Elev= 30
  3309.2  196.79  3628.3  191.41  3841.8  181.75  3902.5  179.86  4070.8  177.77
  4113.5  177.94  4155.6  179.03  4241.7  179.66  4374.9  178.77  4519.6  175.02
  4678.7   171.9  4737.2  170.08  4774.8  165.35  4786.4  164.87  4806.9   164.6
  4865.3  166.01    4908  166.18  4913.2  165.39  4997.8  164.09  4998.3  163.59
  5028.7  163.59  5034.6  164.54    5071  166.38 5110.53 170.337  5139.4  173.43
  5156.6  175.18  5222.4  178.67  5382.4  184.41  5555.7  189.46  5789.2  193.82
#Mann= 8 ,-1 , 0
  3309.2     .12       0  3902.5      .1       0  4155.6     .12       0
  4678.7      .1       0  4737.2     .07       0 5110.53      .1       0
  5139.4     .12       0  5382.4     .05       0
Bank Sta=4737.2,5110.53
XS Rating Curve= 0 ,0
Exp/Cntr=0.3,0.1