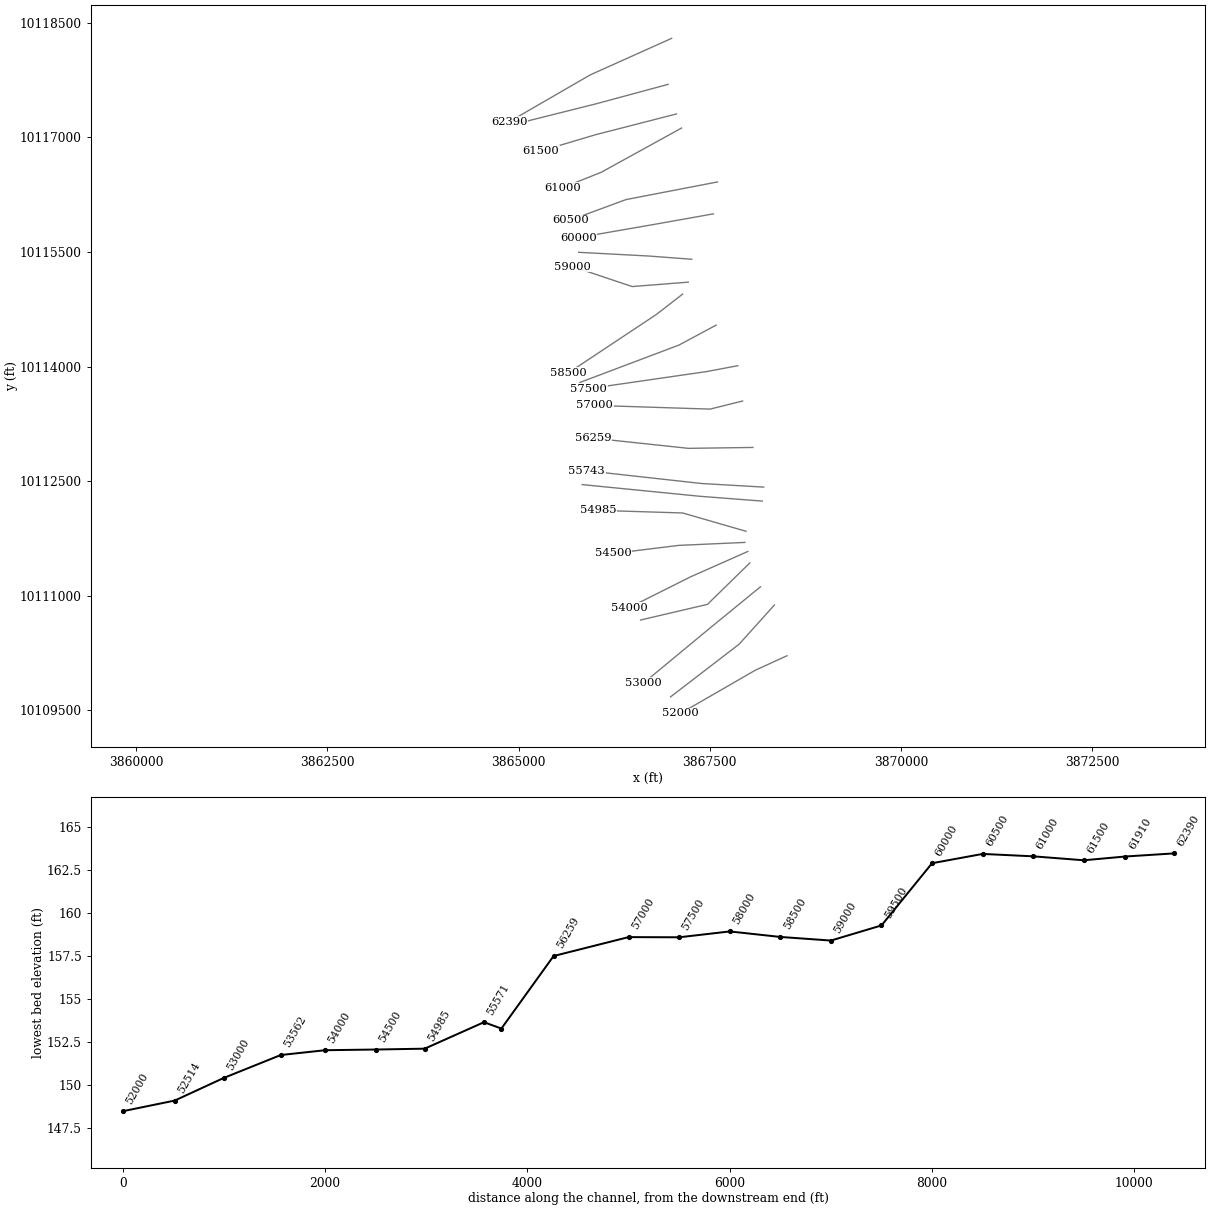
HEC-RAS study CRYSTAL CREEK.prj: CRYSTAL CREEK Base Level Engineering

--- CRYSTAL CREEK.g10 (geometry) --- (continued)

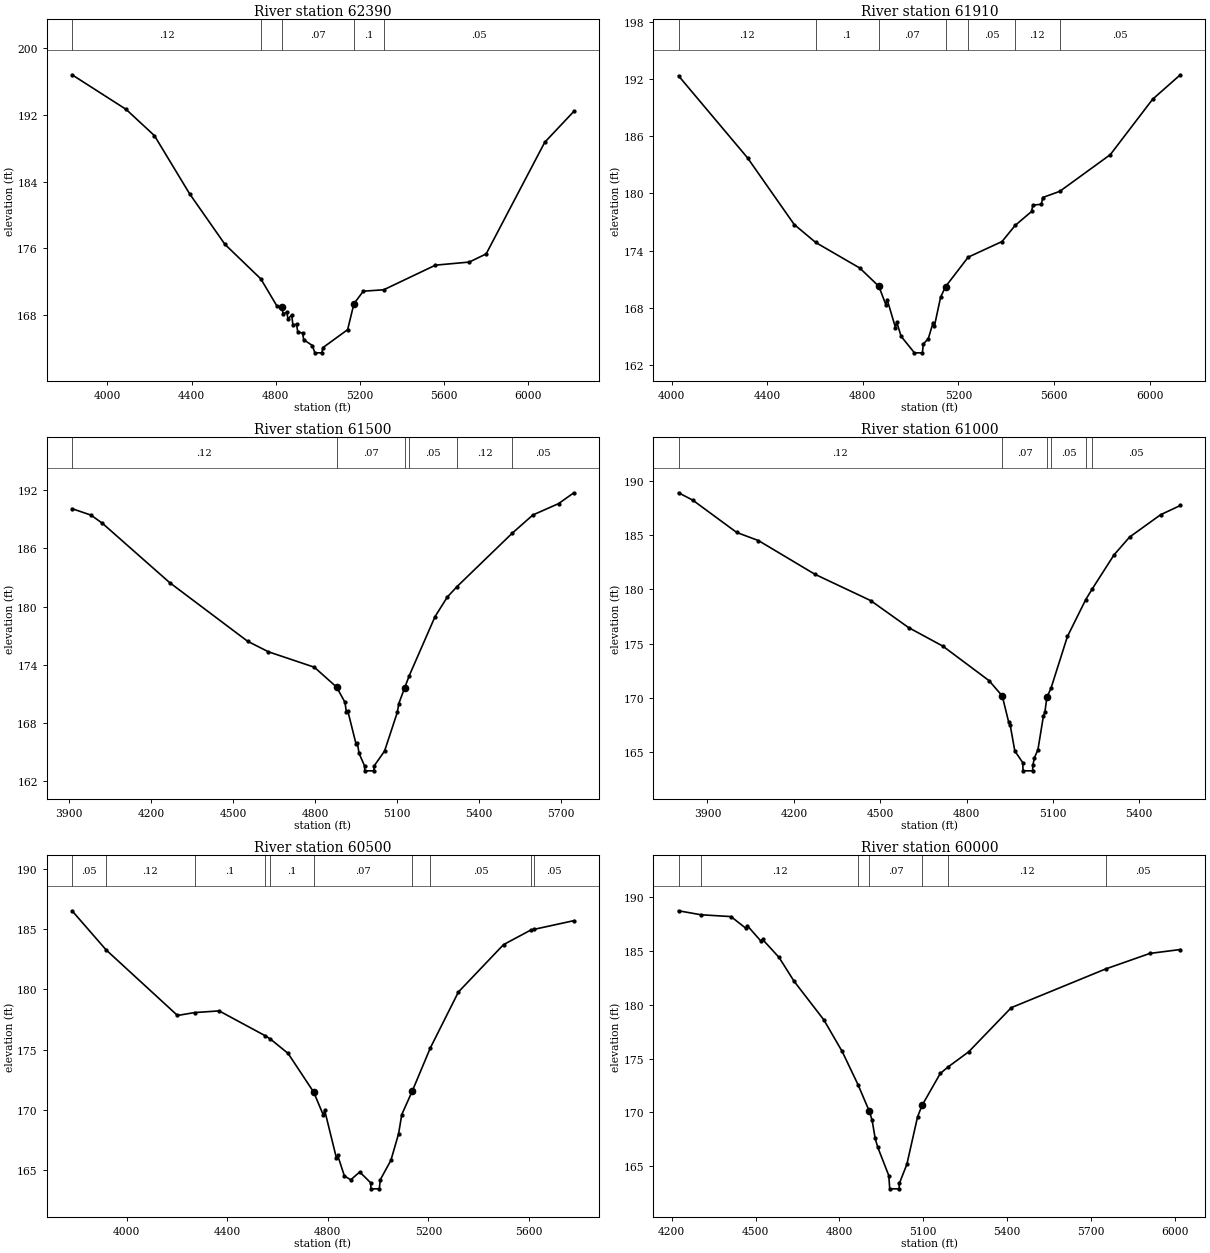
Type RM Length L Ch R = 1 ,62390   ,480,480,480
BEGIN DESCRIPTION:
CRYSTAL CREEK 124.0
END DESCRIPTION:
XS GIS Cut Line= 3
      3867002.31     10118295.54      3865936.67     10117816.65
      3864882.64     10117206.87
#Sta/Elev= 30
  3831.7  196.83  4088.7  192.68  4223.3  189.53  4390.9  182.54  4558.5  176.49
  4729.2  172.34  4806.5  169.06  4829.7  168.95  4835.2  168.14  4852.9  168.37
  4858.3  167.51    4876  168.02  4881.5  166.86  4899.2  166.87  4904.7  166.01
  4927.8  165.82  4933.3  165.04  4974.1  164.35  4986.2  163.47  5019.4  163.47
  5024.3  164.09    5142  166.25  5171.9  169.36  5216.6  170.87  5313.1  171.03
  5559.6  173.99  5720.4  174.36  5800.7  175.34  6079.2  188.73  6217.7  192.44
#Mann= 5 ,-1 , 0
  3831.7     .12       0  4729.2      .1       0  4829.7     .07       0
  5171.9      .1       0  5313.1     .05       0
Bank Sta=4829.7,5171.9
XS Rating Curve= 0 ,0
Exp/Cntr=0.3,0.1

Type RM Length L Ch R = 1 ,61910   ,410,410,410
BEGIN DESCRIPTION:
CRYSTAL CREEK 123.0
END DESCRIPTION:
XS GIS Cut Line= 3
      3866956.46     10117693.16      3866019.43      10117440.1
      3864925.63     10117165.69
#Sta/Elev= 30
  4029.4  192.33    4318  183.73  4513.2  176.74    4603  174.86  4787.3  172.18
  4867.1  170.26  4896.6  168.32  4901.8  168.87  4936.5  165.94  4941.7  166.52
  4960.2  165.02  5015.9  163.29  5049.2  163.29  5052.8  164.22  5073.8  164.77
    5094  166.47  5099.2  166.07  5125.3  169.13    5146  170.23  5240.6  173.32
  5382.2  174.96  5436.7  176.64  5505.7  178.11  5510.8  178.78  5546.8  178.86
    5552  179.57  5623.6  180.22    5835  184.07    6012  189.88  6127.7  192.44
#Mann= 7 ,-1 , 0
  4029.4     .12       0    4603      .1       0  4867.1     .07       0
    5146      .1       0  5240.6     .05       0  5436.7     .12       0
  5623.6     .05       0
Bank Sta=4867.1,5146
XS Rating Curve= 0 ,0
Exp/Cntr=0.3,0.1

Type RM Length L Ch R = 1 ,61500   ,500,500,500
BEGIN DESCRIPTION:
CRYSTAL CREEK 122.0
END DESCRIPTION:
XS GIS Cut Line= 3
       3867064.8     10117305.96       3866009.7     10117034.77
      3865293.97     10116821.58
#Sta/Elev= 30
  3910.6  190.09  3979.7  189.43    4021   188.6  4267.7  182.47  4552.8  176.43
  4629.1  175.34  4797.2  173.75  4878.7   171.7    4909  170.14  4914.3  169.17
  4919.5  169.25  4949.9  165.82    4955  165.89  4960.6  164.89    4981  163.57
  4981.7  163.07    5015  163.07  5015.8  163.57  5054.1  165.11  5100.8   169.1
  5106.3  170.01  5127.1  171.59  5144.6  172.89  5238.7  178.96  5283.6  180.98
  5318.9  182.05  5521.1  187.56  5596.7  189.44  5690.6  190.61  5746.8  191.73
#Mann= 6 ,-1 , 0
  3910.6     .12       0  4878.7     .07       0  5127.1      .1       0
  5144.6     .05       0  5318.9     .12       0  5521.1     .05       0
Bank Sta=4878.7,5127.1
XS Rating Curve= 0 ,0
Exp/Cntr=0.3,0.1

Type RM Length L Ch R = 1 ,61000   ,500,500,500
BEGIN DESCRIPTION:
CRYSTAL CREEK 121.0
END DESCRIPTION:
XS GIS Cut Line= 3
       3867132.6     10117121.95      3866081.25      10116542.2
      3865577.09     10116341.59
#Sta/Elev= 30
  3799.4   188.9  3848.9  188.22  4001.3  185.25    4077   184.5    4273   181.4
  4467.2  178.97  4598.5  176.49  4717.7  174.78  4878.3   171.6  4923.9   170.2
  4945.8  167.84  4951.5  167.52  4967.6  165.13  4995.1  164.06  4996.2   163.3
  5029.5   163.3  5030.2   163.8  5035.9  164.52  5047.9  165.24  5066.8  168.32
  5072.1   168.7    5079  170.06  5093.5  170.92  5150.4  175.67  5214.1  179.07
  5236.6  180.05  5312.2  183.18  5366.2  184.82  5474.1  186.88  5542.6  187.73
#Mann= 6 ,-1 , 0
  3799.4     .12       0  4923.9     .07       0    5079      .1       0
  5093.5     .05       0  5214.1     .12       0  5236.6     .05       0
Bank Sta=4923.9,5079
XS Rating Curve= 0 ,0
Exp/Cntr=0.3,0.1

Type RM Length L Ch R = 1 ,60500   ,500,500,500
BEGIN DESCRIPTION:
CRYSTAL CREEK 120.0
END DESCRIPTION:
XS GIS Cut Line= 3
      3867601.87     10116416.05      3866406.21     10116185.45
      3865675.28     10115915.73
#Sta/Elev= 30
  3782.3  186.52  3917.9  183.27  4201.8  177.83  4269.7  178.07  4367.5  178.21
  4550.7  176.15  4571.7  175.87  4641.9  174.68  4743.7  171.47  4782.4  169.55
  4787.5  169.96  4834.3  165.99  4839.4  166.21  4865.9  164.51  4891.3  164.19
    4927  164.84  4970.7  163.94  4971.5  163.44  5004.8  163.44  5008.9   164.2
  5051.1  165.81  5081.5     168  5094.2   169.6  5136.8  171.59  5207.6  175.12
  5319.7  179.78  5499.2  183.71  5606.8  184.91    5621  184.98  5779.1   185.7
#Mann= 10 ,-1 , 0
  3782.3     .05       0  3917.9     .12       0  4269.7      .1       0
  4550.7     .12       0  4571.7      .1       0  4743.7     .07       0
  5136.8      .1       0  5207.6     .05       0  5606.8     .12       0
    5621     .05       0
Bank Sta=4743.7,5136.8
XS Rating Curve= 0 ,0
Exp/Cntr=0.3,0.1

Type RM Length L Ch R = 1 ,60000   ,500,500,500
BEGIN DESCRIPTION:
CRYSTAL CREEK 119.0
END DESCRIPTION:
XS GIS Cut Line= 3
      3867549.23     10115998.67      3866786.06     10115862.61
      3865782.43     10115688.03
#Sta/Elev= 30
  4224.8  188.73  4304.7  188.36  4412.3  188.19  4466.2  187.09  4471.3  187.33
  4520.1  185.89  4525.2  186.07  4584.1   184.4    4638  182.18  4744.2   178.6
  4809.8  175.66  4866.4  172.58  4906.8  170.11  4916.9  169.27  4927.7  167.59
  4937.2  166.75  4976.5  164.13  4979.8   162.9  5013.3   162.9  5014.1   163.4
    5041  165.17  5079.4   169.6  5095.6  170.66  5160.6  173.62  5188.8  174.23
  5262.1  175.63  5414.3  179.73  5751.2  183.32    5910  184.77  6018.7  185.13
#Mann= 7 ,-1 , 0
  4224.8     .05       0  4304.7     .12       0  4866.4      .1       0
  4906.8     .07       0  5095.6      .1       0  5188.8     .12       0
  5751.2     .05       0
Bank Sta=4906.8,5095.6
XS Rating Curve= 0 ,0
Exp/Cntr=0.3,0.1

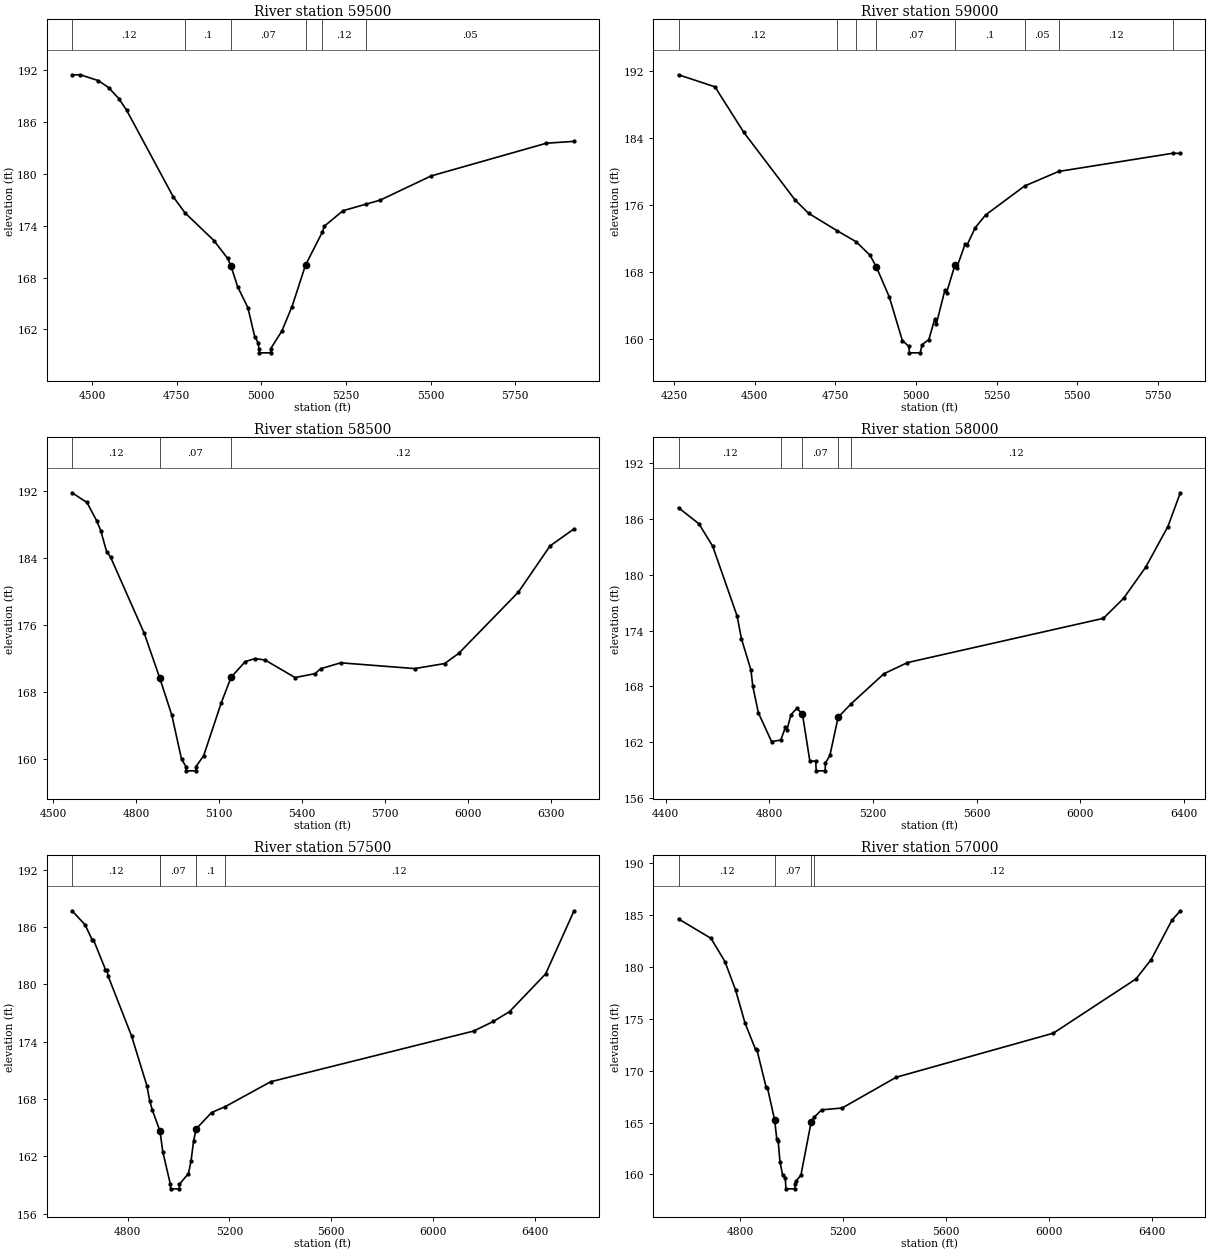
Type RM Length L Ch R = 1 ,59500   ,500,500,500
BEGIN DESCRIPTION:
CRYSTAL CREEK 118.0
END DESCRIPTION:
XS GIS Cut Line= 3
      3867265.41     10115404.09      3866708.49     10115446.16
       3865787.1     10115495.23
#Sta/Elev= 30
  4441.5  191.45    4466  191.47  4519.3  190.79  4549.4  189.99  4579.4  188.72
  4602.5  187.37  4739.9  177.36  4774.8  175.49  4860.2  172.28  4900.4  170.23
  4910.4  169.35  4930.4  166.92  4960.5  164.51  4980.6  161.16  4990.6  160.46
  4993.2  159.78  4993.9  159.28  5027.4  159.28  5028.2  159.78  5060.7   161.8
  5090.8  164.64  5130.8  169.46  5180.7  173.29  5186.1  173.94    5241  175.73
    5308  176.48  5351.1  176.96  5501.4  179.76  5841.8  183.55  5922.7  183.76
#Mann= 6 ,-1 , 0
  4441.5     .12       0  4774.8      .1       0  4910.4     .07       0
  5130.8      .1       0  5180.7     .12       0    5308     .05       0
Bank Sta=4910.4,5130.8
XS Rating Curve= 0 ,0
Exp/Cntr=0.3,0.1

Type RM Length L Ch R = 1 ,59000   ,500,500,500
BEGIN DESCRIPTION:
CRYSTAL CREEK 117.0
END DESCRIPTION:
XS GIS Cut Line= 3
      3867219.47     10115104.61      3866485.63     10115047.01
      3865709.02     10115307.73
#Sta/Elev= 30
  4263.9  191.59  4376.9  190.15  4466.1  184.72  4625.1  176.65  4666.8  175.06
  4755.6  172.97    4814  171.67  4857.3  170.06  4877.4  168.62  4917.5  165.03
  4957.6  159.87  4977.7  159.17  4979.6   158.4  5013.1   158.4  5018.8  159.38
  5039.8  159.99  5057.8  162.41  5063.1  161.87  5089.3  165.86  5094.6  165.57
  5120.8   168.9  5126.1  168.54  5152.4  171.42  5157.7  171.23  5183.9  173.36
  5215.4  174.85  5336.5  178.31  5441.9  180.05  5796.8  182.23  5819.2   182.2
#Mann= 8 ,-1 , 0
  4263.9     .12       0  4755.6      .1       0    4814     .12       0
  4877.4     .07       0  5120.8      .1       0  5336.5     .05       0
  5441.9     .12       0  5796.8     .05       0
Bank Sta=4877.4,5120.8
XS Rating Curve= 0 ,0
Exp/Cntr=0.3,0.1

Type RM Length L Ch R = 1 ,58500   ,500,500,500
BEGIN DESCRIPTION:
CRYSTAL CREEK 116.0
END DESCRIPTION:
XS GIS Cut Line= 3
      3867146.54     10114948.37      3866804.63     10114683.18
      3865652.32      10113917.5
#Sta/Elev= 30
  4567.3  191.84  4621.3  190.68  4656.6  188.48  4671.1  187.32  4692.2  184.82
  4706.4  184.17  4828.6  175.04  4884.7   169.7  4928.2  165.28  4963.5  160.01
  4979.7  159.11  4980.5  158.61  5014.7  158.61  5015.6  159.11  5043.6  160.42
  5106.7  166.68  5142.8  169.79  5193.9  171.66    5230  172.03    5266  171.85
  5374.3  169.76  5446.4  170.22  5467.5  170.82  5539.6  171.52  5807.2  170.83
  5915.5  171.43  5966.6  172.64    6183  179.98  6297.3  185.49  6383.5  187.51
#Mann= 3 , 0 , 0
  4567.3     .12       0  4884.7     .07       0  5142.8     .12       0
Bank Sta=4884.7,5142.8
XS Rating Curve= 0 ,0
Exp/Cntr=0.3,0.1

Type RM Length L Ch R = 1 ,58000   ,500,500,500
BEGIN DESCRIPTION:
CRYSTAL CREEK 115.0
END DESCRIPTION:
XS GIS Cut Line= 3
      3867584.04     10114542.12      3867099.07     10114281.63
      3865802.82     10113792.13
#Sta/Elev= 30
  4449.5  187.22    4528   185.5  4581.4  183.08  4675.7  175.56    4692  173.15
    4729  169.76  4735.8  168.06  4757.7  165.16  4808.4  162.08  4844.2  162.24
  4861.7  163.62  4867.3  163.28  4883.6  164.98  4905.5  165.64  4927.4  165.07
    4956  160.01  4978.7  159.96  4980.8  158.93    5015  158.93  5016.5  159.78
  5033.4  160.58  5065.4   164.7    5116  166.16    5242  169.37  5332.7  170.57
  6088.8  175.33  6166.4  177.47    6252  180.83  6337.5  185.19  6385.6  188.83
#Mann= 5 ,-1 , 0
  4449.5     .12       0  4844.2      .1       0  4927.4     .07       0
  5065.4      .1       0    5116     .12       0
Bank Sta=4927.4,5065.4
XS Rating Curve= 0 ,0
Exp/Cntr=0.3,0.1

Type RM Length L Ch R = 1 ,57500   ,500,500,500
BEGIN DESCRIPTION:
CRYSTAL CREEK 114.0
END DESCRIPTION:
XS GIS Cut Line= 3
      3867867.86     10114011.07      3867456.33      10113933.9
      3865917.89     10113711.08
#Sta/Elev= 30
  4581.3   187.7  4632.2  186.24  4660.2  184.67  4665.2  184.68  4712.7  181.55
  4717.8  181.52  4723.7  180.82  4815.3  174.59  4875.5  169.39  4886.5  167.81
  4896.7  166.86  4926.2  164.69  4927.2   164.6  4938.2  162.45  4967.7  159.09
  4968.6  158.59  5002.9  158.59  5003.7  159.09  5038.9  160.18    5049  161.49
  5059.4  163.64  5069.2  164.86  5129.8  166.58  5182.4  167.18  5362.2   169.8
  6160.5  175.11  6238.4  176.12  6301.9  177.15  6443.4  181.09  6554.5  187.65
#Mann= 5 ,-1 , 0
  4581.3     .12       0  4926.2      .1       0  4927.2     .07       0
  5069.2      .1       0  5182.4     .12       0
Bank Sta=4927.2,5069.2
XS Rating Curve= 0 ,0
Exp/Cntr=0.3,0.1

Type RM Length L Ch R = 1 ,57000   ,741,741,741
BEGIN DESCRIPTION:
CRYSTAL CREEK 113.0
END DESCRIPTION:
XS GIS Cut Line= 3
      3867930.36     10113549.05      3867504.85      10113443.1
      3865994.63     10113491.76
#Sta/Elev= 30
  4561.5  184.64  4687.7  182.77  4741.9  180.52  4783.2  177.78  4819.4  174.63
  4860.7  172.05  4865.8  172.04    4902  168.38  4907.1  168.34  4935.1  165.21
  4943.3  163.37  4948.4  163.26  4955.7   161.2    4966   159.9  4976.3  159.64
  4978.7   158.6    5013   158.6  5013.9   159.1    5017  159.32    5037  159.92
    5077  165.08  5089.5  165.53  5117.1  166.22  5197.1   166.4  5407.5  169.37
  6017.5  173.62  6338.6  178.85  6397.7  180.72  6477.8   184.5    6511  185.43
#Mann= 4 ,-1 , 0
  4561.5     .12       0  4935.1     .07       0    5077      .1       0
  5089.5     .12       0
Bank Sta=4935.1,5077
XS Rating Curve= 0 ,0
Exp/Cntr=0.3,0.1

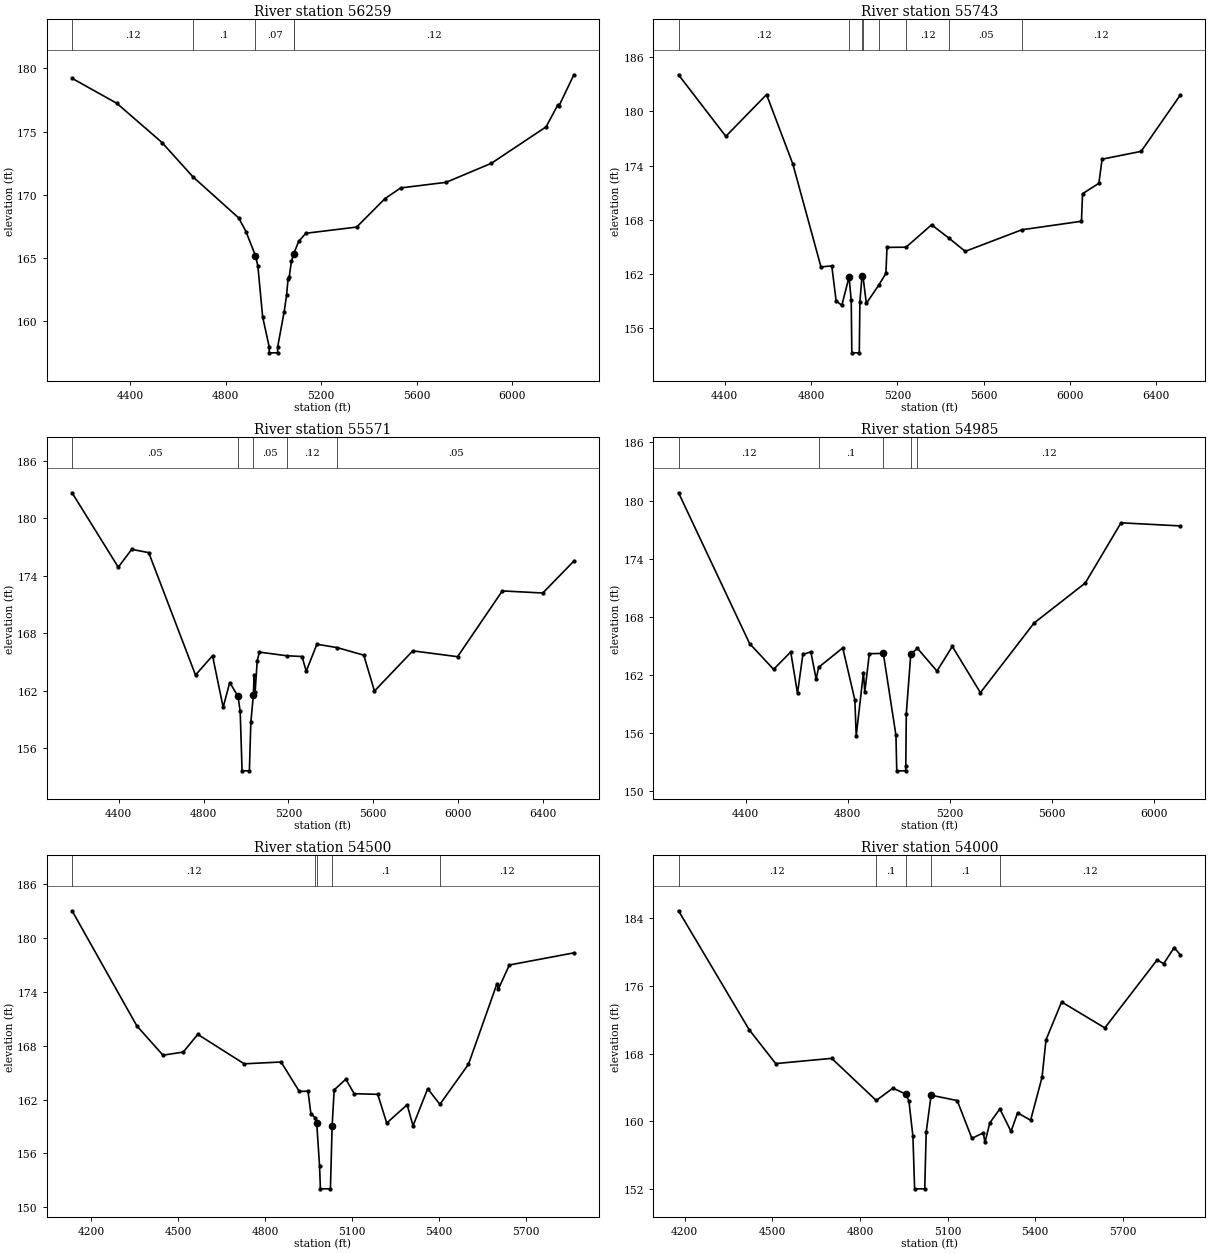
Type RM Length L Ch R = 1 ,56259   ,516,516,516
BEGIN DESCRIPTION:
CRYSTAL CREEK 112.0
END DESCRIPTION:
XS GIS Cut Line= 3
      3868065.47     10112941.48      3867222.66     10112929.49
      3865972.26     10113062.95
#Sta/Elev= 30
  4157.1  179.22  4344.7  177.24  4533.6  174.14  4662.8  171.43  4854.8  168.17
  4884.8   167.1  4924.8  165.19  4934.8  164.37  4954.8  160.35  4981.9     158
  4982.7   157.5  5017.1   157.5    5018     158  5045.1  160.77  5055.1  162.09
  5061.1  163.31  5066.1  163.51  5075.2  164.73  5084.5  165.32  5105.4  166.31
  5135.6  166.96  5348.2  167.45  5467.4  169.71    5533  170.55  5722.7  170.99
  5912.5   172.5  6141.3  175.38  6189.6  177.09  6194.6  177.01  6257.5   179.5
#Mann= 5 ,-1 , 0
  4157.1     .12       0  4662.8      .1       0  4924.8     .07       0
  5084.5      .1       0  5084.5     .12       0
Bank Sta=4924.8,5084.5
XS Rating Curve= 0 ,0
Exp/Cntr=0.3,0.1

Type RM Length L Ch R = 1 ,55743   ,172,172,172
BEGIN DESCRIPTION:
CRYSTAL CREEK 111.0
END DESCRIPTION:
XS GIS Cut Line= 3
      3868206.44     10112422.31       3867394.4     10112469.32
      3865892.83     10112636.07
#Sta/Elev= 30
  4186.6  184.05  4405.6  177.24  4594.3  181.86  4716.1  174.17  4846.3  162.79
  4896.4   162.9  4916.4  159.06  4942.6  158.52  4976.5  161.67  4986.5  159.08
  4989.3  153.28  5023.8  153.28  5026.7  158.96  5036.8  161.83    5041  161.72
  5056.5  158.75  5113.4  160.75  5147.1  162.07  5152.1  164.95  5240.4  164.97
  5358.7  167.45  5439.8  165.96  5514.4  164.51  5777.1   166.9  6052.9  167.84
  6057.9  170.89  6133.5  172.04  6148.5  174.71  6329.6  175.58  6510.8  181.81
#Mann= 8 ,-1 , 0
  4186.6     .12       0  4976.5     .07       0  5036.8     .12       0
    5041     .05       0  5113.4      .1       0  5240.4     .12       0
  5439.8     .05       0  5777.1     .12       0
Bank Sta=4976.5,5036.8
XS Rating Curve= 0 ,0
Exp/Cntr=0.3,0.1

Type RM Length L Ch R = 1 ,55571   ,586,586,586
BEGIN DESCRIPTION:
CRYSTAL CREEK 110.0
END DESCRIPTION:
XS GIS Cut Line= 3
      3868188.16     10112239.16       3867370.6     10112302.27
      3865832.18     10112455.22
#Sta/Elev= 30
    4180  182.64  4397.9  174.88  4461.1  176.74  4541.4   176.4    4762  163.64
  4842.3  165.65  4892.4  160.28  4923.5  162.86  4962.6  161.41  4972.7  159.85
  4981.6  153.65  5016.1  153.65  5022.9   158.7  5034.8 161.538  5038.2  163.61
  5043.2  161.87    5053  165.13  5063.1  166.03  5191.2  165.65    5264  165.57
  5284.1  164.04  5334.4  166.85  5429.6   166.5  5555.5  165.71  5605.7  161.97
  5786.6  166.16  5997.6  165.55  6208.7  172.41  6399.6  172.19    6546  175.52
#Mann= 5 ,-1 , 0
    4180     .05       0  4962.6     .07       0  5034.8     .05       0
  5191.2     .12       0  5429.6     .05       0
Bank Sta=4962.6,5034.8
XS Rating Curve= 0 ,0
Exp/Cntr=0.3,0.1

Type RM Length L Ch R = 1 ,54985   ,485,485,485
BEGIN DESCRIPTION:
CRYSTAL CREEK 109.0
END DESCRIPTION:
XS GIS Cut Line= 3
      3867975.18     10111844.25      3867146.61     10112083.77
      3866045.94     10112118.13
#Sta/Elev= 30
  4137.5  180.81  4415.8  165.24  4509.5  162.59  4576.6  164.38  4603.1  160.11
    4624  164.12  4655.2  164.39    4676  161.59    4686   162.8  4780.1   164.8
  4827.6  159.42  4832.8  155.72  4861.2  162.26  4866.4  160.24  4884.2   164.2
  4938.9  164.23  4988.3  155.78  4991.5  152.11    5026  152.11  5026.9  152.61
  5028.8  158.01 5046.41 164.165  5072.5  164.75  5148.8  162.41  5208.9  164.95
  5318.9  160.18    5529  167.37  5729.1  171.49  5869.2  177.71  6101.2  177.39
#Mann= 5 ,-1 , 0
  4137.5     .12       0    4686      .1       0  4938.9     .07       0
 5046.41      .1       0  5072.5     .12       0
Bank Sta=4938.9,5046.41
XS Rating Curve= 0 ,0
Exp/Cntr=0.3,0.1

Type RM Length L Ch R = 1 ,54500   ,500,500,500
BEGIN DESCRIPTION:
CRYSTAL CREEK 108.0
END DESCRIPTION:
XS GIS Cut Line= 3
      3867961.24     10111698.43       3867096.6     10111659.73
      3866236.89      10111553.9
#Sta/Elev= 30
  4134.5  183.04  4358.1  170.21  4448.2  166.95  4518.3   167.3  4568.3  169.27
  4728.5  165.99  4855.8  166.19  4918.7  162.91  4948.7  162.94  4958.7  160.43
  4974.5  159.95  4978.7  159.44  4988.7  154.55  4991.5  152.06  5026.1  152.06
    5032  159.07    5039  163.08  5079.3  164.28  5108.1  162.66  5189.4  162.59
  5220.4  159.39  5290.9  161.43  5311.1  159.08  5361.9  163.22  5403.8  161.47
  5502.5  165.94  5600.6  174.89  5605.6  174.31  5643.6     177  5866.2  178.35
#Mann= 5 ,-1 , 0
  4134.5     .12       0  4974.5      .1       0  4978.7     .07       0
    5032      .1       0  5403.8     .12       0
Bank Sta=4978.7,5032
XS Rating Curve= 0 ,0
Exp/Cntr=0.3,0.1

Type RM Length L Ch R = 1 ,54000   ,438,438,438
BEGIN DESCRIPTION:
CRYSTAL CREEK 107.0
END DESCRIPTION:
XS GIS Cut Line= 3
      3867998.99     10111579.92      3867248.39     10111247.31
      3866446.87     10110845.27
#Sta/Elev= 30
    4179   184.9  4420.9  170.83  4511.6  166.83  4703.3  167.45  4855.8  162.47
  4913.1  163.93    4958   163.2  4967.8  162.36  4981.3  158.24  4987.2  152.02
  5021.8  152.02  5026.8  158.72  5043.6  163.09  5132.9  162.46  5183.2  157.99
  5222.3  158.64  5227.9   157.5  5244.6  159.82  5278.9  161.47  5317.2  158.81
  5339.6     161  5384.2  160.14  5423.3   165.2  5436.9  169.64  5490.3  174.12
  5638.3  171.05  5817.3  179.09  5839.7  178.64  5875.7  180.55  5896.7  179.68
#Mann= 5 ,-1 , 0
    4179     .12       0  4855.8      .1       0    4958     .07       0
  5043.6      .1       0  5278.9     .12       0
Bank Sta=4958,5043.6
XS Rating Curve= 0 ,0
Exp/Cntr=0.3,0.1

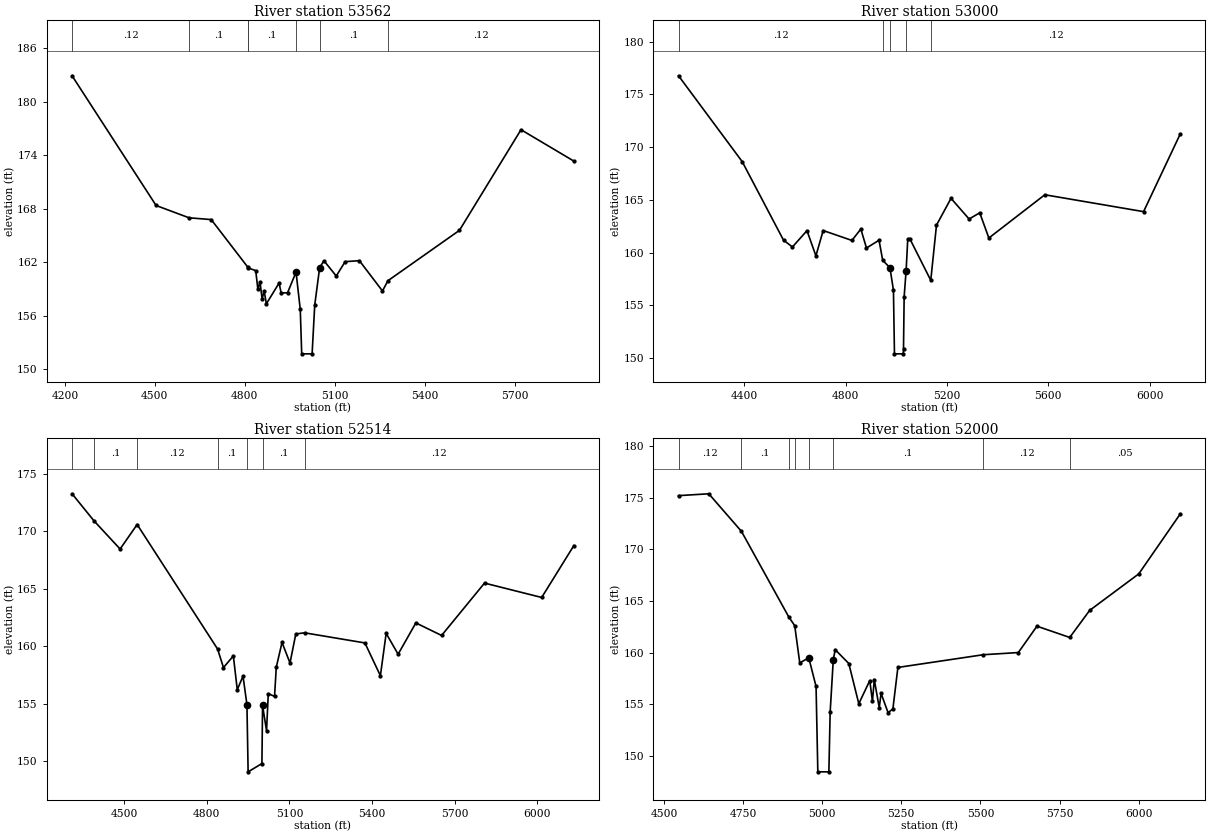
Type RM Length L Ch R = 1 ,53562   ,562,562,562
BEGIN DESCRIPTION:
CRYSTAL CREEK 106.0
END DESCRIPTION:
XS GIS Cut Line= 3
      3868025.04     10111430.35      3867470.58     10110887.72
      3866596.24     10110682.97
#Sta/Elev= 30
  4224.2  182.93  4504.5  168.38  4614.3     167  4688.4   166.8  4810.7  161.45
  4811.5  161.38  4836.8  161.07    4844  158.98    4851  159.81  4858.1  157.93
  4865.1  158.76  4872.3  157.35  4914.7  159.68  4921.7  158.57    4943  158.59
  4971.3  160.91  4985.4  156.72  4990.2  151.74  5024.9  151.74  5033.6   157.2
    5050  161.41  5064.4  162.18  5105.5  160.47    5135  162.08  5182.6  162.19
  5259.6  158.79  5277.7  159.94  5516.3  165.59  5721.7  176.88    5898  173.36
#Mann= 7 ,-1 , 0
  4224.2     .12       0  4614.3      .1       0  4810.7     .12       0
  4811.5      .1       0  4971.3     .07       0    5050      .1       0
  5277.7     .12       0
Bank Sta=4971.3,5050
XS Rating Curve= 0 ,0
Exp/Cntr=0.3,0.1

Type RM Length L Ch R = 1 ,53000   ,486,486,486
BEGIN DESCRIPTION:
CRYSTAL CREEK 105.0
END DESCRIPTION:
XS GIS Cut Line= 3
      3868163.92     10111117.84      3867499.38     10110574.01
      3866636.14     10109859.16
#Sta/Elev= 30
  4141.3  176.77  4392.5  168.63  4555.4  161.19  4590.6  160.54    4648  162.09
  4683.2   159.7  4711.9   162.1  4825.3  161.16  4860.5  162.24  4882.7  160.44
  4932.2  161.18  4946.7  159.28  4975.3  158.57  4989.1  156.44  4993.1  150.41
  5027.9  150.41  5028.8  150.91  5031.3  155.81  5039.1  158.31  5045.6   161.3
  5053.5  161.33  5136.3  157.38  5158.9  162.61  5216.2  165.15  5287.6  163.19
  5329.5  163.78  5365.5  161.39  5586.2  165.49  5975.8  163.89  6120.8  171.27
#Mann= 5 ,-1 , 0
  4141.3     .12       0  4946.7      .1       0  4975.3     .07       0
  5039.1      .1       0  5136.3     .12       0
Bank Sta=4975.3,5039.1
XS Rating Curve= 0 ,0
Exp/Cntr=0.3,0.1

Type RM Length L Ch R = 1 ,52514   ,514,514,514
BEGIN DESCRIPTION:
CRYSTAL CREEK 104.0
END DESCRIPTION:
XS GIS Cut Line= 3
      3868346.26     10110879.17      3867885.34     10110366.91
      3866987.71     10109676.88
#Sta/Elev= 30
  4310.9  173.25  4390.1  170.91  4485.2  168.45  4547.1  170.58  4839.1  159.76
  4860.4  158.15  4896.3  159.16  4910.5  156.23  4931.4   157.4  4945.6  154.93
  4949.9  149.09    5000  149.81  5002.3  154.86  5016.8  152.66  5023.1  155.89
  5045.8  155.64  5052.1  158.18  5072.9  160.33  5101.9  158.55    5123  161.07
  5154.7  161.17  5373.8  160.29    5430  157.44  5450.9  161.12  5494.3  159.31
  5558.7  162.03  5652.1  160.94  5807.9  165.49  6015.4  164.24  6132.2  168.75
#Mann= 7 ,-1 , 0
  4310.9     .12       0  4390.1      .1       0  4547.1     .12       0
  4839.1      .1       0  4945.6     .07       0  5002.3      .1       0
  5154.7     .12       0
Bank Sta=4945.6,5002.3
XS Rating Curve= 0 ,0
Exp/Cntr=0.3,0.1

Type RM Length L Ch R = 1 ,52000   ,500,500,500
BEGIN DESCRIPTION:
CRYSTAL CREEK 103.0
END DESCRIPTION:
XS GIS Cut Line= 3
       3868511.2     10110215.11      3868098.13     10110026.72
      3867117.83     10109461.06
#Sta/Elev= 30
    4546  175.19  4641.6  175.37  4744.7  171.74  4894.3  163.46  4913.2  162.61
  4929.1  159.01  4957.6   159.5  4980.6  156.73  4986.2  148.47  5021.1  148.47
  5025.2  154.27    5035   159.3    5041  160.29  5084.1  158.95  5115.7  155.06
  5150.4   157.3  5158.8  155.29  5164.6  157.39  5180.3  154.68  5186.1  156.06
  5208.1   154.2  5223.4  154.55  5239.2  158.57  5509.1   159.8  5619.8  160.01
  5678.7  162.56  5782.3  161.47  5845.3  164.09  6000.4  167.62  6131.8  173.43
#Mann= 8 ,-1 , 0
    4546     .12       0  4744.7      .1       0  4894.3     .12       0
  4913.2      .1       0  4957.6     .07       0    5035      .1       0
  5509.1     .12       0  5782.3     .05       0
Bank Sta=4957.6,5035
XS Rating Curve= 0 ,0
Exp/Cntr=0.3,0.1