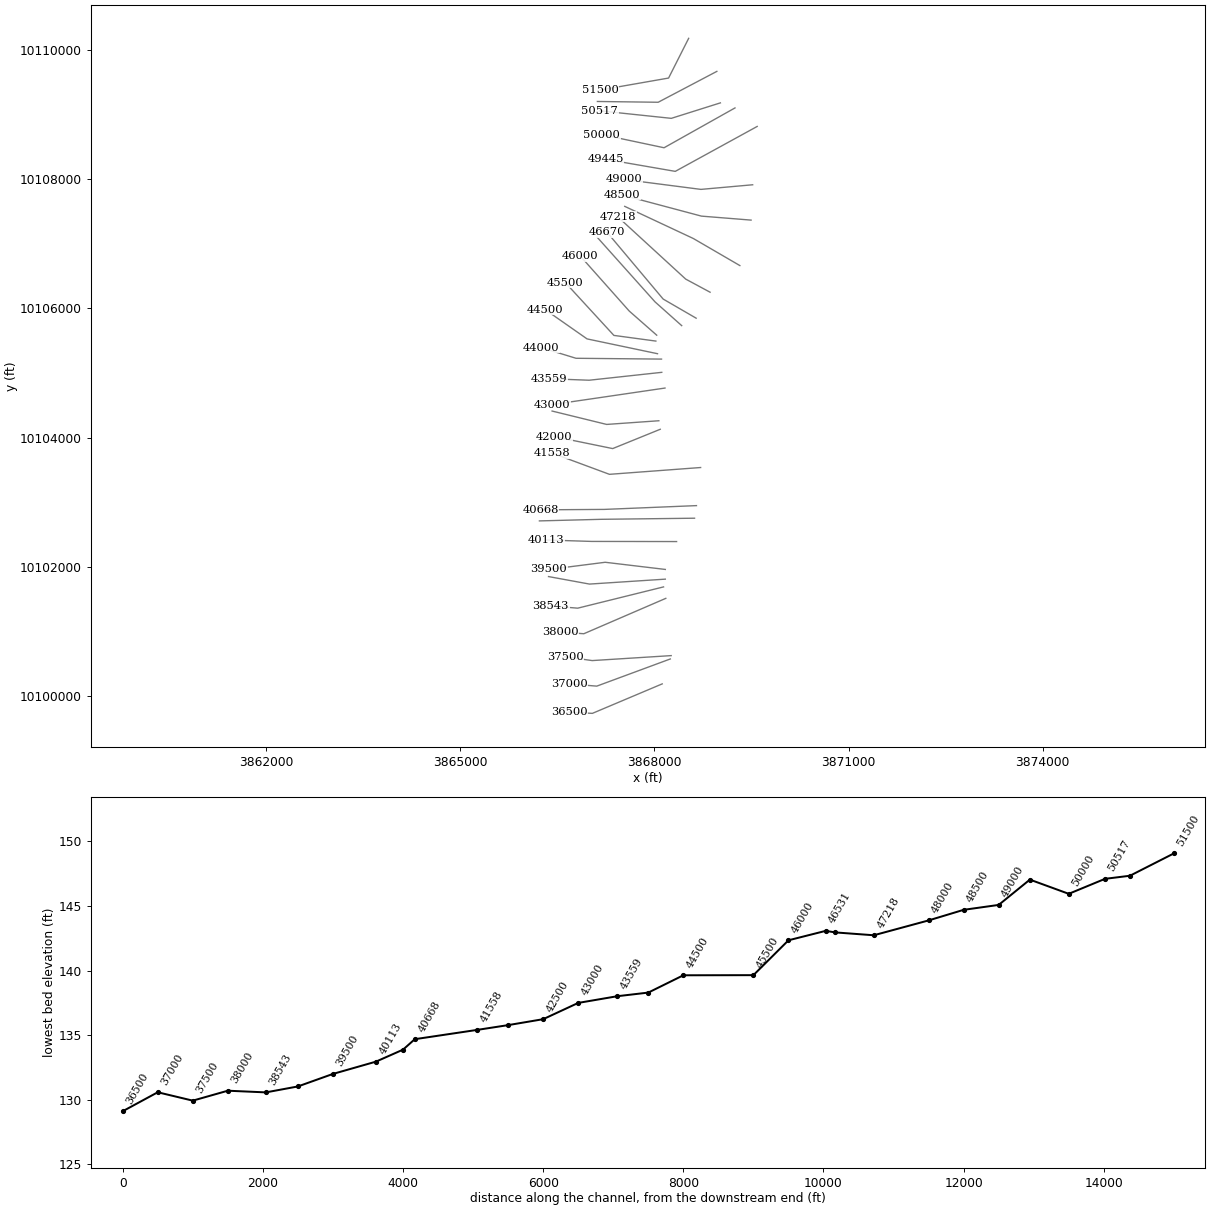
HEC-RAS study CRYSTAL CREEK.prj: CRYSTAL CREEK Base Level Engineering

--- CRYSTAL CREEK.g10 (geometry) --- (continued)

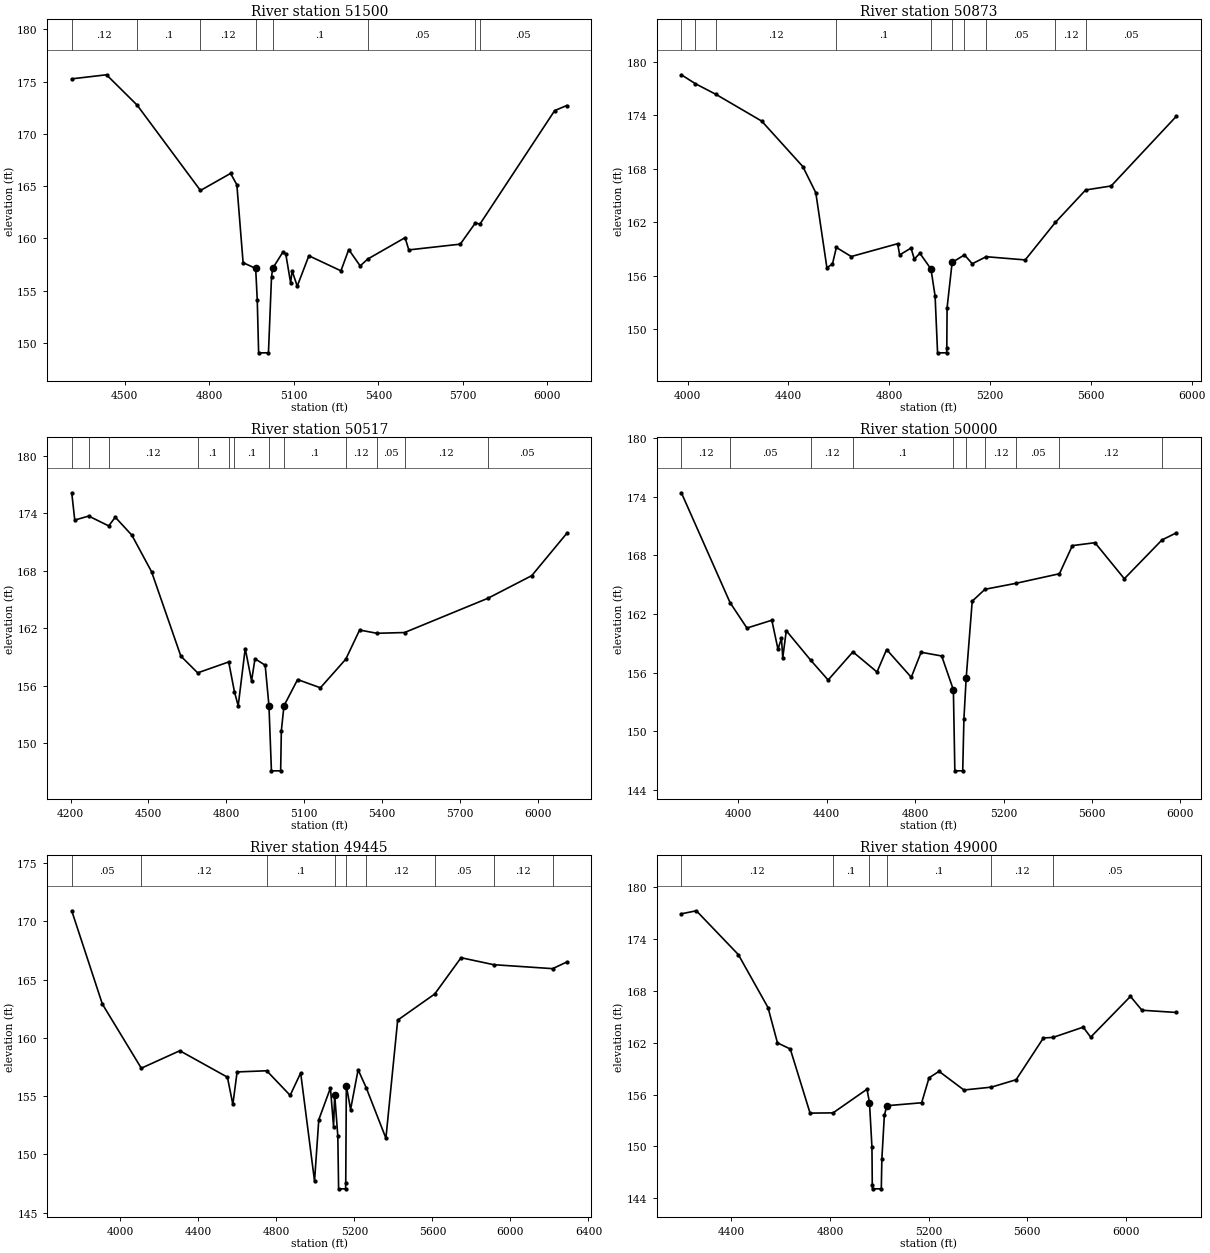
Type RM Length L Ch R = 1 ,51500   ,627,627,627
BEGIN DESCRIPTION:
CRYSTAL CREEK 102.0
END DESCRIPTION:
XS GIS Cut Line= 3
      3868528.55     10110176.05       3868218.3     10109561.75
      3867165.71     10109377.43
#Sta/Elev= 30
  4311.8  175.26  4435.2  175.65  4543.9  172.75  4768.6  164.59  4875.5  166.22
  4897.8  165.14    4920  157.69  4964.6  157.14  4970.2  154.14  4975.1  149.07
    5010  149.07  5020.8  156.31 5024.99 157.148  5061.4  158.71  5071.5  158.51
  5088.8  155.74  5093.9  156.92  5112.1  155.44  5153.4  158.35  5267.2  156.91
  5294.9  158.94  5335.5  157.38  5362.6  158.04  5494.8  160.08  5508.1  158.91
  5690.8  159.46  5744.1  161.48  5760.6  161.38  6025.8  172.23  6068.6  172.71
#Mann= 8 ,-1 , 0
  4311.8     .12       0  4543.9      .1       0  4768.6     .12       0
  4964.6     .07       0 5024.99      .1       0  5362.6     .05       0
  5744.1     .12       0  5760.6     .05       0
Bank Sta=4964.6,5024.99
XS Rating Curve= 0 ,0
Exp/Cntr=0.3,0.1

Type RM Length L Ch R = 1 ,50873   ,356,356,356
BEGIN DESCRIPTION:
CRYSTAL CREEK 101.0
END DESCRIPTION:
XS GIS Cut Line= 3
      3868964.27     10109664.98      3868057.37     10109187.32
      3867117.94     10109199.47
#Sta/Elev= 30
    3975  178.55  4029.9  177.56    4113  176.34  4293.8  173.35  4456.9  168.25
  4508.5  165.31  4552.5  156.89  4574.6  157.31    4590  159.17  4649.1  158.15
  4833.3  159.59  4841.2  158.33  4886.4   159.1  4899.4  157.86  4921.4  158.52
  4965.5  156.75  4981.9  153.71  4991.7  147.34  5027.3  147.34  5028.3  147.84
  5029.5   152.4  5049.5  157.49  5098.3  158.33  5129.5  157.34  5184.5  158.13
  5339.5  157.77  5458.9  161.97  5579.3  165.62  5680.6  166.07  5939.5   173.9
#Mann= 10 ,-1 , 0
    3975     .12       0  4029.9     .05       0    4113     .12       0
    4590      .1       0  4965.5     .07       0  5049.5      .1       0
  5098.3     .12       0  5184.5     .05       0  5458.9     .12       0
  5579.3     .05       0
Bank Sta=4965.5,5049.5
XS Rating Curve= 0 ,0
Exp/Cntr=0.3,0.1

Type RM Length L Ch R = 1 ,50517   ,517,517,517
BEGIN DESCRIPTION:
CRYSTAL CREEK 100.0
END DESCRIPTION:
XS GIS Cut Line= 3
      3869018.99     10109177.77      3868260.33     10108938.49
      3867153.74       10109055.
#Sta/Elev= 30
  4204.5  176.13  4216.2  173.28    4270   173.7  4347.1  172.67  4372.3  173.58
  4436.4   171.7  4512.2  167.89  4625.1  159.08    4690  157.33  4809.6  158.47
  4831.8  155.34  4846.2  153.89  4873.3  159.87  4897.7  156.49  4910.9   158.8
  4950.2  158.13 4964.75 153.909  4974.3   147.1  5009.9   147.1  5012.5  151.27
  5022.6  153.89  5075.2  156.63  5163.1  155.77    5261  158.76  5314.2   161.8
  5381.5  161.46  5487.6  161.54  5809.1  165.12  5977.9  167.48  6112.7  171.89
#Mann= 12 ,-1 , 0
  4204.5     .12       0    4270     .05       0  4347.1     .12       0
    4690      .1       0  4809.6     .05       0  4831.8      .1       0
 4964.75     .07       0  5022.6      .1       0    5261     .12       0
  5381.5     .05       0  5487.6     .12       0  5809.1     .05       0
Bank Sta=4964.75,5022.6
XS Rating Curve= 0 ,0
Exp/Cntr=0.3,0.1

Type RM Length L Ch R = 1 ,50000   ,555,555,555
BEGIN DESCRIPTION:
CRYSTAL CREEK 99.0
END DESCRIPTION:
XS GIS Cut Line= 3
      3869244.69     10109099.65      3868148.19     10108483.61
      3867187.35     10108687.33
#Sta/Elev= 30
  3742.3  174.41  3962.7  163.16    4039  160.56  4151.6  161.36  4179.3   158.4
  4195.2   159.5    4201  157.51  4216.9  160.29    4327  157.28  4406.3  155.24
  4518.5  158.12  4627.5  156.06  4670.9  158.36  4782.5  155.52  4827.1  158.08
  4920.1   157.7  4973.1  154.24  4979.7  145.94  5015.3  145.94  5020.8  151.29
    5031  155.44  5058.3  163.31  5116.1  164.53  5256.1  165.14  5452.9  166.12
  5511.5     169  5613.7   169.3  5746.6  165.61  5916.9  169.58  5982.2  170.31
#Mann= 10 ,-1 , 0
  3742.3     .12       0  3962.7     .05       0    4327     .12       0
  4518.5      .1       0  4973.1     .07       0    5031      .1       0
  5116.1     .12       0  5256.1     .05       0  5452.9     .12       0
  5916.9     .05       0
Bank Sta=4973.1,5031
XS Rating Curve= 0 ,0
Exp/Cntr=0.3,0.1

Type RM Length L Ch R = 1 ,49445   ,445,445,445
BEGIN DESCRIPTION:
CRYSTAL CREEK 98.0
END DESCRIPTION:
XS GIS Cut Line= 3
       3869587.6     10108813.21      3868321.65     10108118.38
      3867243.85     10108305.37
#Sta/Elev= 30
  3750.8  170.92  3907.8  162.91  4107.5   157.4  4304.9   158.9    4549  156.63
  4576.9  154.29  4598.7  157.08  4750.5  157.18  4870.6  155.07  4924.6  156.99
  4995.7  147.71  5017.5  152.98  5077.2   155.7  5093.3  152.38    5099  155.13
  5115.1  151.55  5119.1  147.04  5154.7  147.04  5155.7  147.54  5158.7  155.91
  5180.5  153.85  5219.1  157.27  5261.2   155.7  5361.6  151.39    5422  161.53
  5611.8  163.77  5746.8  166.89  5914.2  166.29  6216.6  165.95  6288.8  166.52
#Mann= 9 ,-1 , 0
  3750.8     .05       0  4107.5     .12       0  4750.5      .1       0
    5099     .07       0  5158.7      .1       0  5261.2     .12       0
  5611.8     .05       0  5914.2     .12       0  6216.6     .05       0
Bank Sta=5099,5158.7
XS Rating Curve= 0 ,0
Exp/Cntr=0.3,0.1

Type RM Length L Ch R = 1 ,49000   ,500,500,500
BEGIN DESCRIPTION:
CRYSTAL CREEK 97.0
END DESCRIPTION:
XS GIS Cut Line= 3
      3869517.82     10107911.07      3868718.51      10107839.6
      3867523.02     10107993.82
#Sta/Elev= 30
  4197.5  176.94  4258.2  177.29  4428.4  172.22  4548.9  166.08  4587.2  161.99
  4639.2  161.28  4719.5  153.85  4812.8  153.88  4950.5  156.62  4960.5  155.07
  4970.5  149.91  4971.8  145.58  4972.8  145.08  5008.4  145.08  5010.7  148.54
  5020.8  153.59  5030.9  154.71  5172.1  155.05  5202.1  157.94  5242.7  158.69
  5343.5  156.53  5454.9  156.86  5555.2  157.72  5666.1  162.56  5704.9  162.62
  5827.3  163.81  5857.7  162.65    6019  167.37  6065.6  165.77  6205.4  165.51
#Mann= 6 ,-1 , 0
  4197.5     .12       0  4812.8      .1       0  4960.5     .07       0
  5030.9      .1       0  5454.9     .12       0  5704.9     .05       0
Bank Sta=4960.5,5030.9
XS Rating Curve= 0 ,0
Exp/Cntr=0.3,0.1

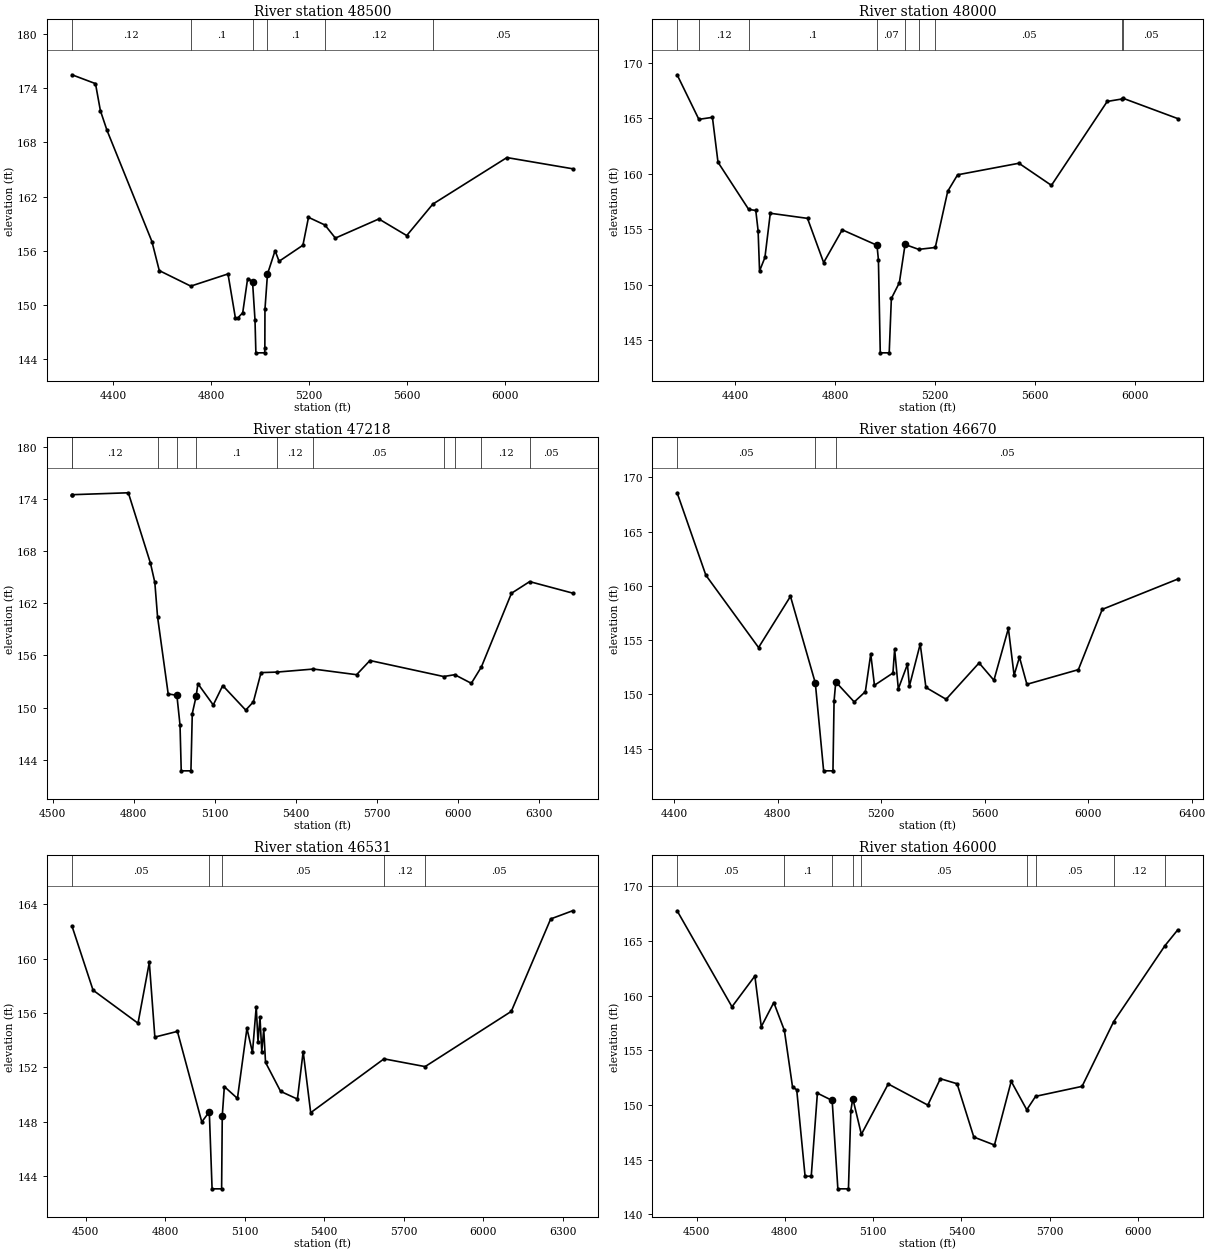
Type RM Length L Ch R = 1 ,48500   ,500,500,500
BEGIN DESCRIPTION:
CRYSTAL CREEK 96.0
END DESCRIPTION:
XS GIS Cut Line= 3
      3869493.52     10107364.47      3868726.39     10107426.07
      3867492.71     10107755.08
#Sta/Elev= 30
  4230.4   175.5  4326.4  174.52  4346.4  171.53  4373.4  169.35  4557.1  157.03
  4587.2  153.81    4716  152.09  4868.1  153.44  4898.2  148.59  4908.2  148.56
  4928.3  149.14  4948.4  152.93  4968.4   152.6  4978.5  148.36  4982.1   144.7
  5017.8   144.7  5018.8   145.2  5019.2  149.51  5029.5  153.42  5060.6  156.02
  5076.9  154.84  5174.4  156.62  5197.2  159.71  5264.4  158.86  5307.1  157.41
  5484.9  159.53  5598.8  157.69  5705.3  161.17  6008.3  166.33  6276.8  165.09
#Mann= 6 ,-1 , 0
  4230.4     .12       0    4716      .1       0  4968.4     .07       0
  5029.5      .1       0  5264.4     .12       0  5705.3     .05       0
Bank Sta=4968.4,5029.5
XS Rating Curve= 0 ,0
Exp/Cntr=0.3,0.1

Type RM Length L Ch R = 1 ,48000   ,782,782,782
BEGIN DESCRIPTION:
CRYSTAL CREEK 95.0
END DESCRIPTION:
XS GIS Cut Line= 3
      3869319.94     10106661.33      3868600.76     10107079.85
      3867540.38     10107577.15
#Sta/Elev= 30
  4167.9   168.9  4254.9  164.89  4309.2  165.07  4331.5  161.03  4454.2  156.79
  4482.7  156.69    4492  154.87  4497.8  151.25  4519.3  152.46  4540.8  156.44
  4689.7  155.98  4754.3     152  4828.7  154.95  4967.7  153.56  4973.5  152.26
  4980.9  143.88  5016.7  143.88  5025.3  148.77  5057.3  150.19  5080.2  153.63
  5134.6  153.19  5201.1  153.36  5250.9  158.42  5290.4   159.9  5535.8  160.94
  5665.9  158.95  5889.2   166.5  5950.3  166.73  5953.3  166.78  6171.2  164.96
#Mann= 9 ,-1 , 0
  4167.9     .05       0  4254.9     .12       0  4454.2      .1       0
  4967.7     .07       0  5080.2      .1       0  5134.6     .12       0
  5201.1     .05       0  5950.3     .12       0  5953.3     .05       0
Bank Sta=4967.7,5080.2
XS Rating Curve= 0 ,0
Exp/Cntr=0.3,0.1

Type RM Length L Ch R = 1 ,47218   ,548,548,548
BEGIN DESCRIPTION:
CRYSTAL CREEK 94.0
END DESCRIPTION:
XS GIS Cut Line= 3
      3868859.86     10106249.01      3868482.92     10106451.96
      3867432.61      10107415.9
#Sta/Elev= 30
  4571.9  174.47    4572  174.47  4780.5  174.69  4862.4   166.6  4878.6  164.39
  4888.7  160.43  4928.1  151.57  4960.3  151.41  4971.9  147.99  4976.4  142.73
  5012.3  142.73  5017.3  149.31  5031.5  151.29  5038.2  152.74    5095   150.3
  5130.1  152.53  5215.2  149.71  5243.6  150.66  5271.9  154.02  5330.5  154.08
  5466.1  154.43  5625.8  153.78  5675.2  155.41  5948.2  153.57  5989.2  153.78
  6050.7  152.79  6087.9  154.67  6199.3  163.14  6266.7  164.48  6425.6  163.16
#Mann= 11 ,-1 , 0
  4571.9     .05       0    4572     .12       0  4888.7      .1       0
  4960.3     .07       0  5031.5      .1       0  5330.5     .12       0
  5466.1     .05       0  5948.2     .12       0  5989.2     .05       0
  6087.9     .12       0  6266.7     .05       0
Bank Sta=4960.3,5031.5
XS Rating Curve= 0 ,0
Exp/Cntr=0.3,0.1

Type RM Length L Ch R = 1 ,46670   ,139,139,139
BEGIN DESCRIPTION:
CRYSTAL CREEK 93.0
END DESCRIPTION:
XS GIS Cut Line= 3
      3868644.16     10105847.53      3868134.51     10106143.19
      3867269.16      10107173.9
#Sta/Elev= 30
  4410.8  168.59  4521.9  160.99  4725.6  154.32    4849  159.04    4945  151.05
  4977.2  142.95  5013.2  142.95  5017.5  149.38    5024  151.15  5095.5   149.3
  5138.4  150.25  5159.3  153.73  5173.6  150.84  5245.1  151.97  5251.6  154.17
  5265.9  150.51  5301.1  152.77  5308.8  150.77  5350.5  154.64  5372.6  150.64
  5450.6  149.55  5578.1   152.9  5635.4   151.3  5691.3  156.08  5713.4  151.77
  5734.2  153.43  5762.9  150.93  5961.9  152.28  6054.2  157.84  6345.8  160.63
#Mann= 3 , 0 , 0
  4410.8     .05       0    4945     .07       0    5024     .05       0
Bank Sta=4945,5024
XS Rating Curve= 0 ,0
Exp/Cntr=0.3,0.1

Type RM Length L Ch R = 1 ,46531   ,531,531,531
BEGIN DESCRIPTION:
CRYSTAL CREEK 92.0
END DESCRIPTION:
XS GIS Cut Line= 3
      3868421.02     10105732.12       3868008.9     10106099.66
      3867117.03     10107096.79
#Sta/Elev= 30
  4447.8  162.39  4527.3  157.68    4697  155.25  4739.7  159.72  4760.6  154.23
  4845.8  154.65  4937.8  147.99  4966.2  148.73  4976.7  143.07  5012.7  143.07
 5015.12  148.43    5023  150.59  5072.4  149.72  5108.3  154.87  5129.2   153.1
  5143.4  156.47  5150.1  153.89  5157.6  155.68  5164.3  153.17  5171.8   154.8
  5178.5  152.37  5235.4  150.24  5298.9  149.67  5320.6  153.17    5349  148.67
  5625.8  152.63    5781  152.06  6106.4  156.12  6255.2  162.92  6337.8  163.52
#Mann= 5 ,-1 , 0
  4447.8     .05       0  4966.2     .07       0 5015.12     .05       0
  5625.8     .12       0    5781     .05       0
Bank Sta=4966.2,5015.12
XS Rating Curve= 0 ,0
Exp/Cntr=0.3,0.1

Type RM Length L Ch R = 1 ,46000   ,500,500,500
BEGIN DESCRIPTION:
CRYSTAL CREEK 91.0
END DESCRIPTION:
XS GIS Cut Line= 3
      3868034.75     10105584.53      3867609.49     10105958.34
      3866855.26     10106807.29
#Sta/Elev= 30
  4433.8  167.74  4620.3  158.97  4698.1  161.78  4719.9  157.15  4762.5  159.36
  4798.5  156.81  4826.2  151.64  4840.4  151.39  4868.9  143.48  4889.8   143.5
  4910.7  151.08  4960.9  150.41  4980.3  142.34  5016.3  142.34  5024.4  149.48
  5031.1  150.59  5060.2  147.32  5151.5  151.92  5286.1  149.99  5328.8   152.4
  5385.6  151.94  5442.5  147.07  5512.7  146.34  5569.6  152.16  5622.5  149.56
  5652.6  150.79  5810.5   151.7  5917.9  157.61  6092.2  164.55  6135.6  165.99
#Mann= 9 ,-1 , 0
  4433.8     .05       0  4798.5      .1       0  4960.9     .07       0
  5031.1      .1       0  5060.2     .05       0  5622.5     .12       0
  5652.6     .05       0  5917.9     .12       0  6092.2     .05       0
Bank Sta=4960.9,5031.1
XS Rating Curve= 0 ,0
Exp/Cntr=0.3,0.1

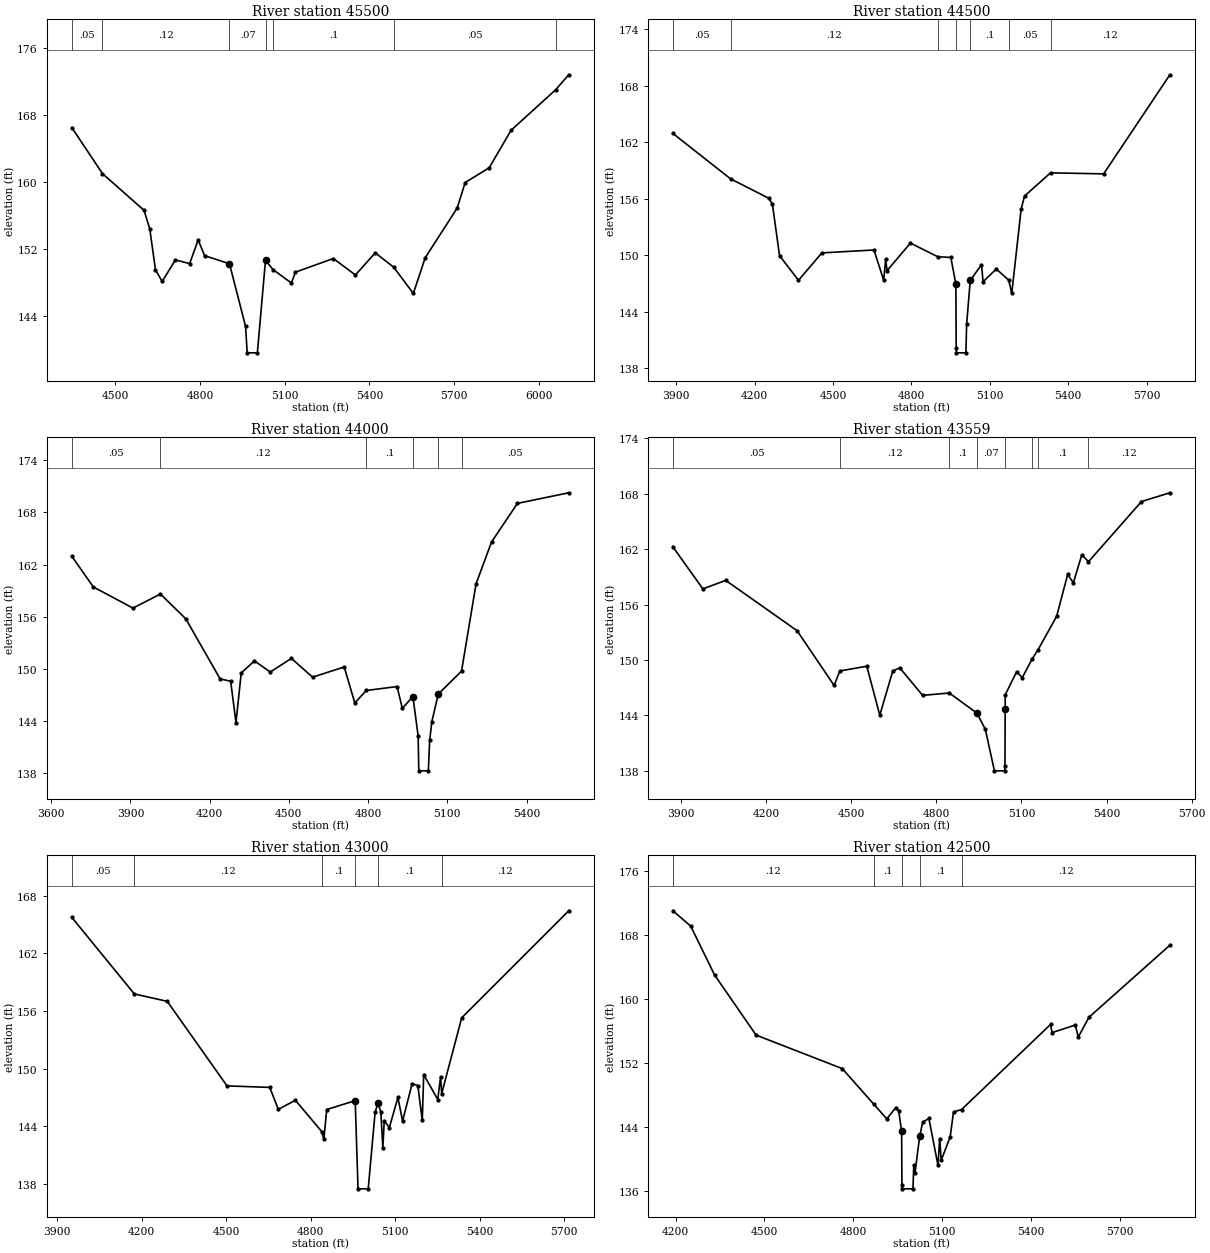
Type RM Length L Ch R = 1 ,45500   ,1000,1000,1000
BEGIN DESCRIPTION:
CRYSTAL CREEK 90.0
END DESCRIPTION:
XS GIS Cut Line= 3
      3868021.76     10105493.38      3867372.86     10105581.08
       3866624.2     10106396.12
#Sta/Elev= 30
  4345.2  166.55  4453.9  161.05  4601.4  156.66  4621.6  154.42  4641.8  149.55
  4665.5  148.17  4712.4  150.74  4762.9   150.3  4793.1  153.13  4815.8  151.25
  4904.1  150.28  4961.1  142.79  4966.9  139.64  5002.9  139.64  5031.8  150.71
  5058.2  149.59  5123.6  147.98  5137.8  149.28  5272.2  150.91  5350.5  148.94
  5420.9  151.59  5486.1  149.87  5555.8  146.74  5597.8  150.99  5711.2  156.94
  5739.6  159.99  5824.7  161.75  5902.3  166.23  6060.3  171.07  6106.7  172.86
#Mann= 7 ,-1 , 0
  4345.2     .05       0  4453.9     .12       0  4904.1     .07       0
  5031.8     .12       0  5058.2      .1       0  5486.1     .05       0
  6060.3    .075       0
Bank Sta=4904.1,5031.8
XS Rating Curve= 0 ,0
Exp/Cntr=0.3,0.1

Type RM Length L Ch R = 1 ,44500   ,500,500,500
BEGIN DESCRIPTION:
CRYSTAL CREEK 89.0
END DESCRIPTION:
XS GIS Cut Line= 3
      3868046.92     10105298.06      3866958.35     10105527.05
      3866312.27     10105979.06
#Sta/Elev= 30
  3887.6  162.92  4108.1   158.1  4254.5  156.04  4268.2   155.4  4295.4  149.95
  4367.9  147.33  4457.3  150.24  4656.7  150.55  4693.9  147.33  4701.4  149.61
  4706.5  148.35    4796  151.28    4901  149.83  4950.6  149.76  4969.9  146.93
  4971.2  140.13  4972.2  139.63  5008.3  139.63  5011.2  142.72    5025  147.31
  5067.9  148.99    5074  147.18  5124.6  148.53  5172.1  147.35  5183.7  145.93
  5219.6  154.89  5232.5  156.27    5332  158.74  5535.3  158.63  5788.5  169.15
#Mann= 7 ,-1 , 0
  3887.6     .05       0  4108.1     .12       0    4901      .1       0
  4969.9     .07       0    5025      .1       0  5172.1     .05       0
    5332     .12       0
Bank Sta=4969.9,5025
XS Rating Curve= 0 ,0
Exp/Cntr=0.3,0.1

Type RM Length L Ch R = 1 ,44000   ,441,441,441
BEGIN DESCRIPTION:
CRYSTAL CREEK 88.0
END DESCRIPTION:
XS GIS Cut Line= 3
      3868109.38     10105214.73      3866787.54     10105227.23
      3866252.33     10105391.65
#Sta/Elev= 30
  3678.1  162.96  3759.6  159.43  3909.6     157  4013.6  158.62  4109.7  155.77
  4239.7  148.86  4279.7  148.59  4299.7  143.84  4319.7  149.55  4369.7  150.93
  4429.7  149.65  4509.7  151.22  4589.7  149.06  4709.7  150.23  4749.7   146.1
  4793.3  147.53  4909.7  147.98  4929.7  145.47  4969.7  146.83  4989.7  142.28
    4992  138.29  5028.2  138.29  5033.2  141.78  5041.5  143.95  5065.9  147.12
  5153.9  149.75  5208.9  159.79  5267.5   164.6  5365.6  169.04  5559.9  170.26
#Mann= 6 ,-1 , 0
  3678.1     .05       0  4013.6     .12       0  4793.3      .1       0
  4969.7     .07       0  5065.9      .1       0  5153.9     .05       0
Bank Sta=4969.7,5065.9
XS Rating Curve= 0 ,0
Exp/Cntr=0.3,0.1

Type RM Length L Ch R = 1 ,43559   ,559,559,559
BEGIN DESCRIPTION:
CRYSTAL CREEK 87.0
END DESCRIPTION:
XS GIS Cut Line= 3
      3868112.87     10105009.87      3866990.48      10104887.9
      3866367.81     10104911.07
#Sta/Elev= 30
    3871  162.24  3976.6   157.7  4057.1  158.62  4308.6  153.18  4439.3  147.25
  4459.6  148.82  4554.6  149.33  4600.3  144.03  4646.1  148.81  4670.7  149.16
  4751.2  146.18  4845.5  146.43  4942.3  144.27  4972.5  142.51  5004.5  138.01
  5040.7  138.01  5041.7  138.51  5042.5 144.693  5042.7  146.24  5082.7  148.73
  5102.7   148.1  5138.4  150.16  5157.7  151.08  5223.8  154.72  5262.8  159.26
  5282.8  158.36  5312.8   161.4  5336.2  160.64    5523  167.15  5623.1   168.1
#Mann= 8 ,-1 , 0
    3871     .05       0  4459.6     .12       0  4845.5      .1       0
  4942.3     .07       0  5042.5      .1       0  5138.4     .12       0
  5157.7      .1       0  5336.2     .12       0
Bank Sta=4942.3,5042.5
XS Rating Curve= 0 ,0
Exp/Cntr=0.3,0.1

Type RM Length L Ch R = 1 ,43000   ,500,500,500
BEGIN DESCRIPTION:
CRYSTAL CREEK 86.0
END DESCRIPTION:
XS GIS Cut Line= 3
      3868162.91      10104766.9      3867126.26     10104614.48
      3866417.86     10104511.07
#Sta/Elev= 30
  3952.2  165.75  4174.1  157.78  4290.9  157.01    4503  148.21  4654.7  148.05
  4685.1  145.77  4745.7  146.71  4839.6  143.44  4846.6  142.63  4856.9  145.75
    4958  146.67    4968  137.49  5004.2  137.49  5028.7  145.48  5038.8  146.42
  5048.9  145.49  5056.1  141.78  5061.1  144.58  5079.2  143.87  5109.6     147
  5126.1  144.55  5160.1  148.45  5180.3  148.23  5196.1  144.61  5201.1  149.38
    5251  146.79    5261  149.15  5264.9  147.41    5336   155.3  5715.9  166.44
#Mann= 6 ,-1 , 0
  3952.2     .05       0  4174.1     .12       0  4839.6      .1       0
    4958     .07       0  5038.8      .1       0  5264.9     .12       0
Bank Sta=4958,5038.8
XS Rating Curve= 0 ,0
Exp/Cntr=0.3,0.1

Type RM Length L Ch R = 1 ,42500   ,500,500,500
BEGIN DESCRIPTION:
CRYSTAL CREEK 85.0
END DESCRIPTION:
XS GIS Cut Line= 3
      3868067.87     10104261.07      3867261.18      10104204.1
      3866417.81     10104411.08
#Sta/Elev= 30
  4191.3  171.01  4251.5  169.08  4331.7  162.99    4472  155.46  4762.7  151.27
  4868.6  146.84  4913.1  144.98  4943.2  146.39  4953.2     146  4963.2  143.41
  4964.1  136.73  4965.1  136.23  5001.4  136.23  5004.1  139.21  5008.4  138.27
    5024   142.8  5034.3  144.57  5055.1  145.03  5085.8  139.18  5091.6  142.51
  5096.7  139.79    5127  142.74  5138.3  145.85  5165.5  146.15  5465.7  156.79
  5470.9  155.77  5548.8  156.71  5559.5  155.23  5595.6   157.7  5868.4   166.7
#Mann= 5 ,-1 , 0
  4191.3     .12       0  4868.6      .1       0  4963.2     .07       0
    5024      .1       0  5165.5     .12       0
Bank Sta=4963.2,5024
XS Rating Curve= 0 ,0
Exp/Cntr=0.3,0.1

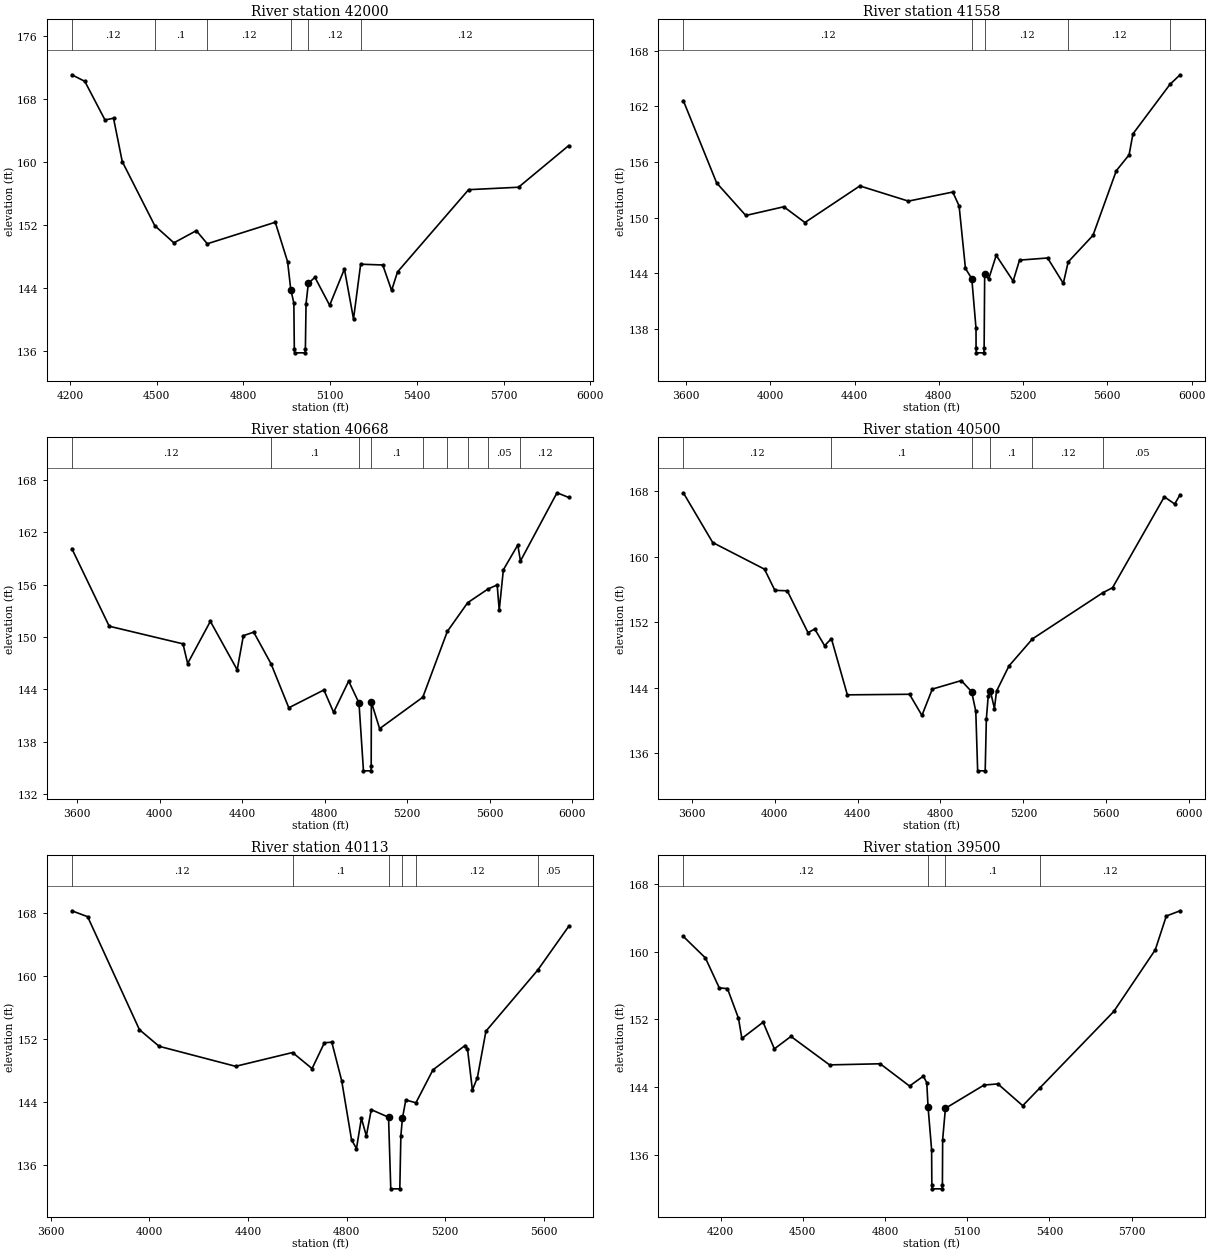
Type RM Length L Ch R = 1 ,42000   ,442,442,442
BEGIN DESCRIPTION:
CRYSTAL CREEK 84.0
END DESCRIPTION:
XS GIS Cut Line= 3
      3868089.42      10104129.2      3867354.39     10103830.53
      3866448.06     10104016.44
#Sta/Elev= 30
  4206.6  171.03  4251.5   170.2  4321.4   165.3  4350.9  165.52    4381  160.03
  4493.7  151.89  4559.7  149.72  4637.3  151.26  4675.3   149.6  4910.4  152.33
  4953.1  147.32    4964   143.8  4974.7  142.08  4976.3  136.27  4977.3  135.77
  5013.6  135.77  5014.6  136.27  5016.9     142  5024.8  144.58  5047.5  145.35
  5098.5   141.8  5149.6   146.4  5181.1  140.07  5205.8  147.01  5282.3  146.91
  5312.9  143.68  5333.3  146.03  5579.2  156.46  5751.9  156.77  5925.2  162.04
#Mann= 6 ,-1 , 0
  4206.6     .12       0  4493.7      .1       0  4675.3     .12       0
    4964     .07       0  5024.8     .12       0  5205.8     .12       0
Bank Sta=4964,5024.8
XS Rating Curve= 0 ,0
Exp/Cntr=0.3,0.1

Type RM Length L Ch R = 1 ,41558   ,890,890,890
BEGIN DESCRIPTION:
CRYSTAL CREEK 83.0
END DESCRIPTION:
XS GIS Cut Line= 3
      3868713.56     10103537.65      3867304.29     10103432.36
      3866417.87     10103761.06
#Sta/Elev= 30
  3586.8  162.63  3745.1  153.74  3883.3  150.23  4063.8  151.17  4164.1  149.47
  4424.8  153.42  4655.5  151.78  4866.1  152.76  4896.1  151.26  4926.2  144.51
  4956.3  143.41  4976.4  138.03  4976.6   135.9  4977.6   135.4  5013.9   135.4
  5014.9   135.9  5017.5  143.89  5036.5  143.37  5072.2  145.92  5152.7  143.15
    5183  145.41  5316.2  145.64  5390.8   142.9  5414.1  145.22  5531.6  148.08
  5642.4  155.06  5703.2  156.78  5721.4  159.04  5897.4  164.39  5945.4  165.42
#Mann= 5 ,-1 , 0
  3586.8     .12       0  4956.3     .07       0  5017.5     .12       0
  5414.1     .12       0  5897.4     .05       0
Bank Sta=4956.3,5017.5
XS Rating Curve= 0 ,0
Exp/Cntr=0.3,0.1

Type RM Length L Ch R = 1 ,40668   ,168,168,168
BEGIN DESCRIPTION:
CRYSTAL CREEK 82.0
END DESCRIPTION:
XS GIS Cut Line= 3
      3868648.98     10102948.32      3867223.98     10102889.71
       3866241.5     10102883.22
#Sta/Elev= 30
  3573.8  160.13  3755.1  151.24  4112.8  149.22  4135.4  146.97  4245.5   151.8
  4375.6  146.25  4405.6  150.16  4455.7  150.56  4539.7  146.94  4625.8   141.9
    4796  143.94  4843.1  141.38  4916.1  144.96  4966.1  142.45  4987.9  134.68
  5024.3  134.68  5025.3  135.18  5026.1  142.56  5066.1  139.51  5275.6  143.11
  5394.4  150.64    5493  153.93  5591.6   155.5  5636.1  155.97  5646.1  153.08
  5666.1   157.7  5736.1  160.54  5749.1  158.71  5926.2  166.52  5982.5  165.99
#Mann= 9 ,-1 , 0
  3573.8     .12       0  4539.7      .1       0  4966.1     .07       0
  5026.1      .1       0  5275.6     .12       0  5394.4     .05       0
    5493     .12       0  5591.6     .05       0  5749.1     .12       0
Bank Sta=4966.1,5026.1
XS Rating Curve= 0 ,0
Exp/Cntr=0.3,0.1

Type RM Length L Ch R = 1 ,40500   ,387,387,387
BEGIN DESCRIPTION:
CRYSTAL CREEK 81.0
END DESCRIPTION:
XS GIS Cut Line= 3
      3868619.73     10102753.53      3867178.33     10102736.52
      3866221.65     10102711.89
#Sta/Elev= 30
  3558.5  167.79  3700.4  161.72  3950.4  158.47  4000.4  155.89  4060.4  155.83
  4160.4  150.73    4193  151.17  4240.4  149.14  4273.5  149.99  4350.4  143.14
  4650.5  143.21  4710.5  140.63  4760.5  143.84  4900.5  144.88  4950.5  143.52
  4970.5  141.13  4979.5  133.87  5015.9  133.87  5021.5  140.21  5030.5  142.99
  5040.5  143.65  5060.5  141.47  5070.5  143.58  5130.5  146.66  5244.2  149.97
  5583.3  155.59  5630.7  156.21  5880.8   167.3  5930.8  166.42    5957  167.56
#Mann= 6 ,-1 , 0
  3558.5     .12       0  4273.5      .1       0  4950.5     .07       0
  5040.5      .1       0  5244.2     .12       0  5583.3     .05       0
Bank Sta=4950.5,5040.5
XS Rating Curve= 0 ,0
Exp/Cntr=0.3,0.1

Type RM Length L Ch R = 1 ,40113   ,613,613,613
BEGIN DESCRIPTION:
CRYSTAL CREEK 80.0
END DESCRIPTION:
XS GIS Cut Line= 3
      3868341.94     10102392.42      3867028.04     10102394.49
      3866328.09     10102416.72
#Sta/Elev= 30
  3686.1  168.23  3750.2  167.48  3960.2  153.14  4040.2  151.03  4350.2  148.49
    4581  150.24  4660.2   148.2  4710.2  151.48  4740.2  151.55  4780.2  146.67
  4820.2  139.17  4840.2  138.05  4860.2  141.91  4880.2  139.65  4900.2  142.99
  4970.2  142.03  4979.3  132.94  5015.9  132.94  5020.2  139.66 5026.41 141.877
  5040.2  144.22  5081.2  143.86  5150.3  148.04  5280.3  151.13  5290.3  150.71
  5310.3  145.49  5330.4  147.05  5365.1  152.95  5575.3  160.71  5700.3  166.24
#Mann= 6 ,-1 , 0
  3686.1     .12       0    4581      .1       0  4970.2     .07       0
 5026.41      .1       0  5081.2     .12       0  5575.3     .05       0
Bank Sta=4970.2,5026.41
XS Rating Curve= 0 ,0
Exp/Cntr=0.3,0.1

Type RM Length L Ch R = 1 ,39500   ,500,500,500
BEGIN DESCRIPTION:
CRYSTAL CREEK 79.0
END DESCRIPTION:
XS GIS Cut Line= 3
      3868167.84     10101961.07      3867238.34       10102072.
      3866367.88     10101961.07
#Sta/Elev= 30
  4063.9   161.8  4144.5  159.26  4195.2  155.72    4225  155.64  4265.3  152.13
  4277.6  149.75  4355.1  151.67  4396.2  148.52  4456.7  149.99  4597.7  146.63
  4782.6  146.76  4889.7  144.13  4940.1   145.3  4952.6  144.53  4957.3 141.655
  4970.3   136.6  4971.1  132.49  4972.1  131.99  5008.7  131.99  5009.7  132.49
  5010.6  137.81  5020.7   141.5  5161.8  144.25  5212.2  144.38  5302.9  141.81
  5366.4  143.94  5635.6  152.95  5786.8  160.22  5827.1  164.21  5877.5  164.83
#Mann= 4 ,-1 , 0
  4063.9     .12       0  4957.3     .07       0  5020.7      .1       0
  5366.4     .12       0
Bank Sta=4957.3,5020.7
XS Rating Curve= 0 ,0
Exp/Cntr=0.3,0.1

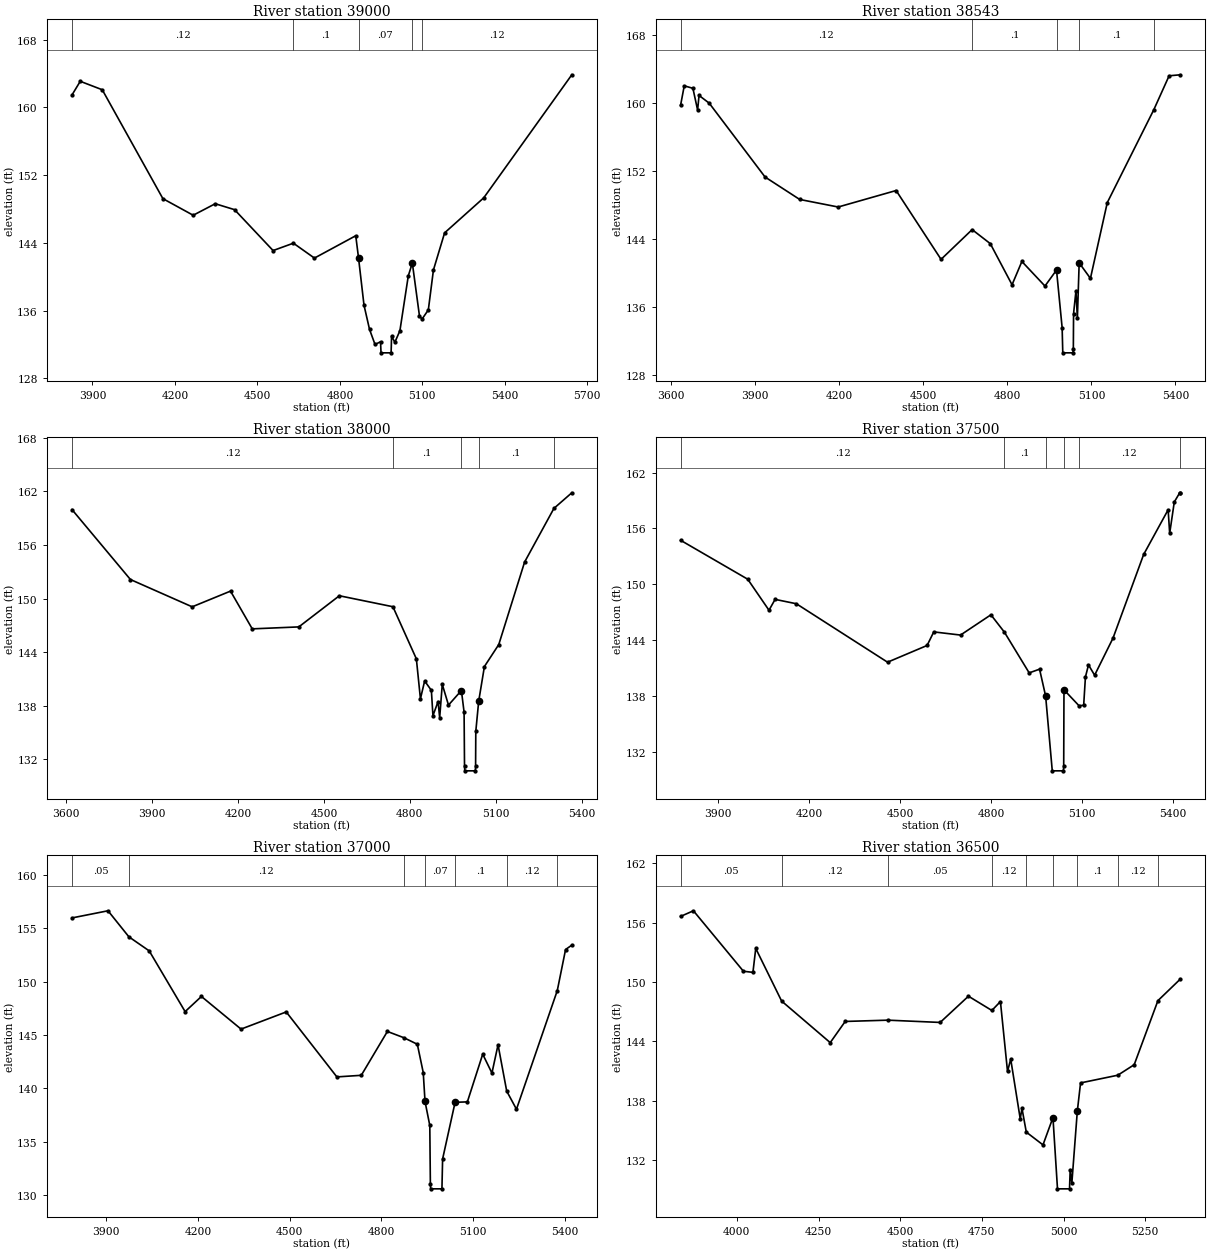
Type RM Length L Ch R = 1 ,39000   ,457,457,457
BEGIN DESCRIPTION:
CRYSTAL CREEK 78.0
END DESCRIPTION:
XS GIS Cut Line= 3
      3868167.85     10101811.07      3866995.84     10101734.73
      3866362.78     10101850.75
#Sta/Elev= 30
  3825.5  161.47  3855.6  163.09  3935.7  162.09  4156.2  149.23  4266.4  147.27
  4346.6  148.63  4416.8  147.93    4557   143.1  4630.9  143.97  4707.4  142.21
  4857.7  144.85  4867.7  142.26  4887.7  136.65  4907.8  133.79  4927.8  132.01
  4947.9  132.33  4949.6  131.02  4986.3  131.02    4988  132.99    5000  132.27
  5018.3  133.63  5048.8  140.11  5063.5  141.63  5089.4  135.39  5098.7     135
  5121.7  136.09  5140.3  140.81  5180.9  145.19  5323.3  149.33  5643.6  163.86
#Mann= 5 ,-1 , 0
  3825.5     .12       0  4630.9      .1       0  4867.7     .07       0
  5063.5      .1       0  5098.7     .12       0
Bank Sta=4867.7,5063.5
XS Rating Curve= 0 ,0
Exp/Cntr=0.3,0.1

Type RM Length L Ch R = 1 ,38543   ,543,543,543
BEGIN DESCRIPTION:
CRYSTAL CREEK 77.0
END DESCRIPTION:
XS GIS Cut Line= 3
      3868140.55     10101691.02       3866813.9     10101362.16
      3866397.56     10101395.89
#Sta/Elev= 30
  3633.2  159.69  3646.3  161.98  3677.2  161.69    3694  159.13  3699.1  160.85
  3735.4  159.94  3934.8  151.25  4058.4  148.61  4195.8  147.72  4402.7  149.66
  4563.1  141.56  4674.1  145.06  4738.9  143.41  4816.6  138.57  4851.7  141.31
  4934.1  138.42  4975.3   140.3  4995.4  133.52  4997.7  130.56  5034.4  130.56
  5035.4  131.06  5036.2  135.17  5044.8  137.87  5049.8  134.61  5056.2  141.15
  5096.4  139.32  5156.6  148.24    5323  159.19  5377.3  163.16  5417.7  163.28
#Mann= 5 ,-1 , 0
  3633.2     .12       0  4674.1      .1       0  4975.3     .07       0
  5056.2      .1       0    5323     .05       0
Bank Sta=4975.3,5056.2
XS Rating Curve= 0 ,0
Exp/Cntr=0.3,0.1

Type RM Length L Ch R = 1 ,38000   ,500,500,500
BEGIN DESCRIPTION:
CRYSTAL CREEK 76.0
END DESCRIPTION:
XS GIS Cut Line= 3
      3868175.27     10101513.93      3866908.31     10100966.68
      3866543.36     10100993.11
#Sta/Elev= 30
  3619.9  159.97  3824.1  152.13  4039.8  149.07  4173.7  150.83  4249.6   146.6
  4412.3  146.82  4553.9  150.31    4741  149.08  4822.9  143.24  4837.1  138.76
  4851.8  140.76  4875.3  139.71  4880.8  136.87  4898.8  138.46  4904.3  136.64
  4913.4  140.38  4935.1  138.06  4980.2  139.69  4989.6  137.27  4991.1  131.19
  4992.1  130.69  5028.8  130.69  5029.8  131.19  5030.5  135.11  5040.6  138.49
  5060.6  142.38  5110.7  144.84    5201  154.09  5303.4   160.1  5365.9  161.85
#Mann= 5 ,-1 , 0
  3619.9     .12       0    4741      .1       0  4980.2     .07       0
  5040.6      .1       0  5303.4     .05       0
Bank Sta=4980.2,5040.6
XS Rating Curve= 0 ,0
Exp/Cntr=0.3,0.1

Type RM Length L Ch R = 1 ,37500   ,500,500,500
BEGIN DESCRIPTION:
CRYSTAL CREEK 75.0
END DESCRIPTION:
XS GIS Cut Line= 3
      3868258.71     10100628.29      3867037.23     10100551.42
      3866617.85     10100611.07
#Sta/Elev= 30
  3776.1  154.73  3997.4  150.54  4067.5   147.2  4087.6  148.37  4157.7   147.9
  4458.3  141.61  4588.6  143.41  4610.6  144.87  4698.8  144.53    4799  146.71
  4843.5  144.84  4925.1  140.46  4959.3  140.86  4979.3  137.97  5001.2  129.92
  5037.9  129.92  5038.9  130.42  5039.8  138.64  5089.2  136.93  5104.7  136.97
  5110.5  140.02  5120.6  141.32  5140.8  140.21  5201.4   144.2  5302.4   153.2
  5383.1  158.01  5388.2  155.48  5403.4  158.85  5421.3  159.84  5423.6  159.84
#Mann= 6 ,-1 , 0
  3776.1     .12       0  4843.5      .1       0  4979.3     .07       0
  5039.8      .1       0  5089.2     .12       0  5421.3     .05       0
Bank Sta=4979.3,5039.8
XS Rating Curve= 0 ,0
Exp/Cntr=0.3,0.1

Type RM Length L Ch R = 1 ,37000   ,500,500,500
BEGIN DESCRIPTION:
CRYSTAL CREEK 74.0
END DESCRIPTION:
XS GIS Cut Line= 3
      3868244.72     10100576.43      3867108.51      10100156.3
      3866687.55     10100189.93
#Sta/Elev= 30
  3788.6  155.96  3906.4  156.63  3974.6  154.19  4041.1  152.87  4158.4  147.18
  4211.7   148.6  4341.2  145.54  4488.9  147.15  4654.4  141.06  4734.2  141.21
  4819.5  145.32  4873.7  144.73  4917.4  144.12  4936.7  141.47  4942.5  138.76
  4958.1  136.51    4960  131.07    4961  130.57  4997.8  130.57    5000  133.37
  5040.8  138.68  5080.9  138.72  5131.1  143.19  5161.2  141.42  5181.2  144.07
  5209.5  139.73  5241.4  138.03  5374.8  149.15  5401.9     153  5422.3  153.41
#Mann= 7 ,-1 , 0
  3788.6     .05       0  3974.6     .12       0  4873.7      .1       0
  4942.5     .07       0  5040.8      .1       0  5209.5     .12       0
  5374.8     .05       0
Bank Sta=4942.5,5040.8
XS Rating Curve= 0 ,0
Exp/Cntr=0.3,0.1

Type RM Length L Ch R = 1 ,36500   ,512,512,512
BEGIN DESCRIPTION:
CRYSTAL CREEK 73.0
END DESCRIPTION:
XS GIS Cut Line= 3
      3868119.79     10100191.04      3867040.01     10099734.83
       3866682.6     10099753.51
#Sta/Elev= 30
  3827.8  156.62  3867.1  157.19  4020.2  151.08  4049.3  150.97  4057.9  153.39
  4137.1  148.07  4285.9  143.87  4331.7  146.01  4462.2  146.14  4622.4  145.91
    4709  148.56  4780.7  147.12  4806.9  148.02  4828.6  140.96  4838.4   142.2
  4867.5  136.18  4872.9  137.22  4886.1  134.83  4937.2  133.54  4967.7   136.3
  4981.6   129.1  5018.4   129.1  5020.5  131.04  5025.5  129.67  5042.2  136.92
  5052.2   139.8  5166.3  140.58  5216.4  141.64    5289  148.11  5357.9   150.3
#Mann= 9 ,-1 , 0
  3827.8     .05       0  4137.1     .12       0  4462.2     .05       0
  4780.7     .12       0  4886.1      .1       0  4967.7     .07       0
  5042.2      .1       0  5166.3     .12       0    5289     .05       0
Bank Sta=4967.7,5042.2
XS Rating Curve= 0 ,0
Exp/Cntr=0.3,0.1