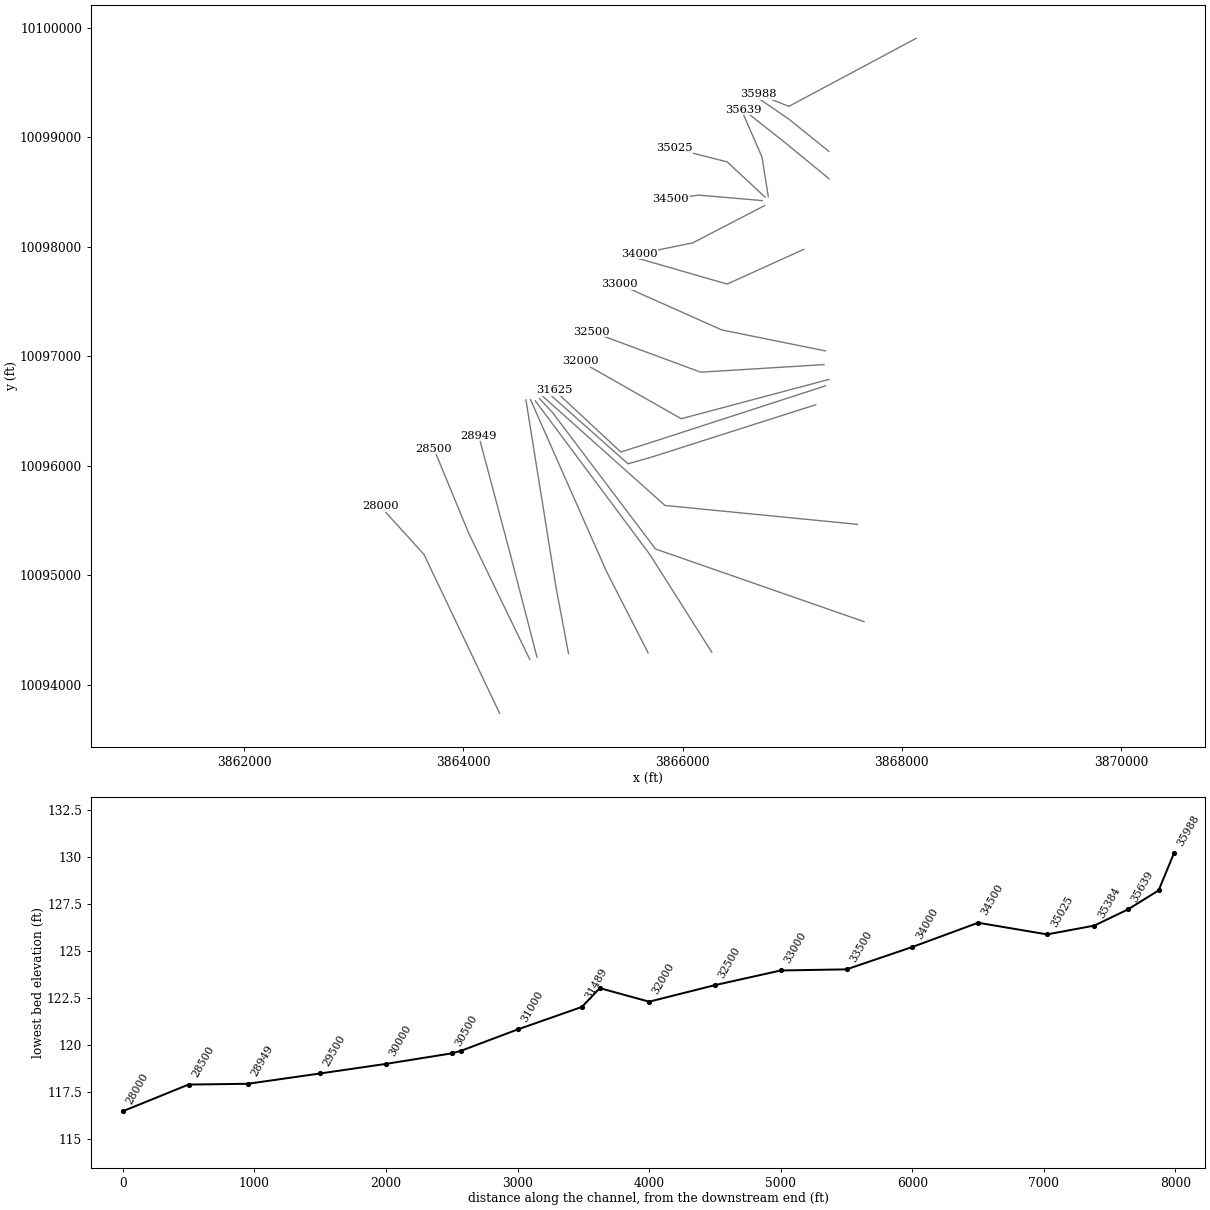
HEC-RAS study CRYSTAL CREEK.prj: CRYSTAL CREEK Base Level Engineering

--- CRYSTAL CREEK.g10 (geometry) --- (continued)

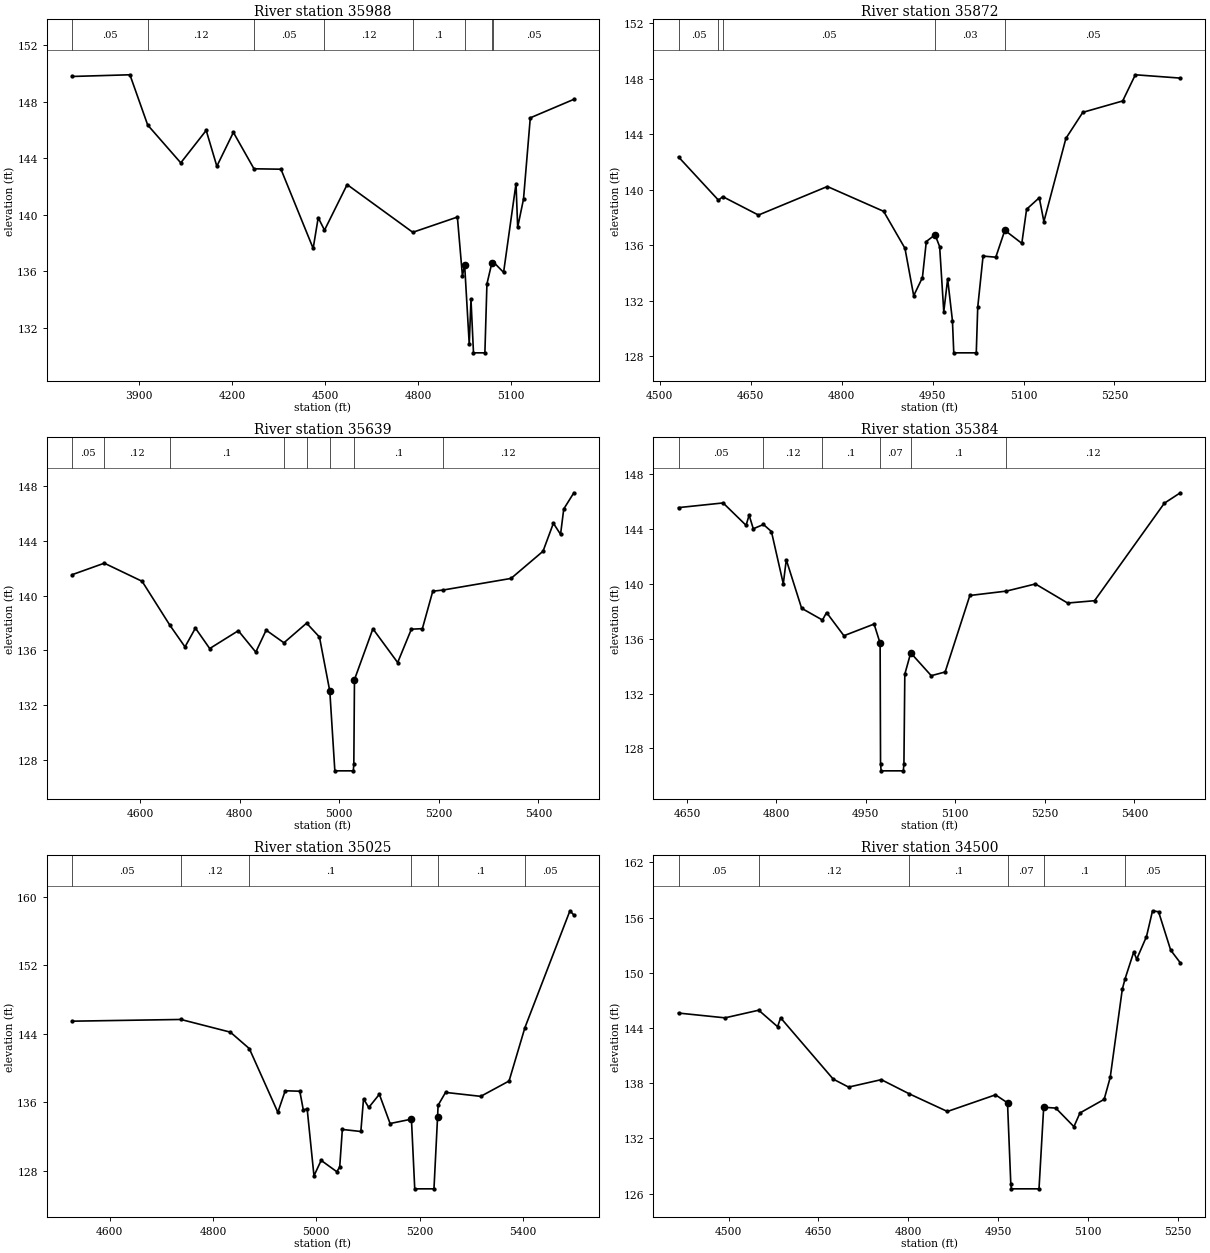
Type RM Length L Ch R = 1 ,35988   ,116,116,116
BEGIN DESCRIPTION:
CRYSTAL CREEK 72.0
END DESCRIPTION:
XS GIS Cut Line= 3
      3868130.13     10099902.81      3866968.87     10099281.75
      3866687.32      10099394.8
#Sta/Elev= 30
  3683.1  149.79  3869.9  149.91  3927.3  146.35  4034.1  143.67  4116.2  145.97
  4150.6  143.43    4204  145.83  4270.5  143.25  4357.6  143.22  4461.6  137.61
  4477.9  139.79  4498.2   138.9  4571.3  142.13  4783.3  138.75  4927.3  139.83
  4943.6  135.66  4950.7  136.45  4965.6  130.82  4971.2     134  4979.3  130.21
  5016.1  130.21  5022.7  135.09  5038.6  136.58    5042  136.68  5076.5  135.91
  5116.6   142.2    5122  139.11  5140.8   141.1  5162.7  146.86  5303.4  148.17
#Mann= 8 ,-1 , 0
  3683.1     .05       0  3927.3     .12       0  4270.5     .05       0
  4498.2     .12       0  4783.3      .1       0  4950.7     .07       0
  5038.6      .1       0    5042     .05       0
Bank Sta=4950.7,5038.6
XS Rating Curve= 0 ,0
Exp/Cntr=0.3,0.1

Type RM Length L Ch R = 1 ,35872   ,233,233,233
BEGIN DESCRIPTION:
Mapping XS 6da51c09
END DESCRIPTION:
XS GIS Cut Line= 3
       3867333.1      10098871.4      3866968.01     10099165.64
      3866672.23     10099368.39
#Sta/Elev= 30
  4531.1  142.37    4597  139.25    4604  139.51  4662.9  138.18  4776.5  140.24
  4869.3  138.45  4904.5  135.78  4918.9  132.36  4933.3  133.67  4939.7  136.27
  4954.1  136.76  4961.7   135.9  4968.5   131.2  4974.9  133.57  4982.8  130.56
    4985  128.24  5022.1  128.24  5024.5  131.53  5033.3  135.22  5054.3  135.14
  5069.2  137.08  5097.2  136.14  5105.1   138.6    5126  139.43  5133.6  137.71
  5169.9  143.71  5197.8  145.59  5263.5  146.41  5284.4   148.3  5358.6  148.06
#Mann= 5 ,-1 , 0
  4531.1     .05       0    4597     .12       0    4604     .05       0
  4954.1     .03       0  5069.2     .05       0
Bank Sta=4954.1,5069.2
XS Rating Curve= 0 ,0
Exp/Cntr=0.3,0.1

Type RM Length L Ch R = 1 ,35639   ,255,255,255
BEGIN DESCRIPTION:
CRYSTAL CREEK 71.0
END DESCRIPTION:
XS GIS Cut Line= 3
      3867336.05     10098620.52       3866921.6     10098960.73
      3866551.68     10099252.44
#Sta/Elev= 30
  4463.8  141.52  4528.5  142.36  4604.4  141.04  4660.3  137.83  4690.5  136.26
  4711.4  137.63  4740.1  136.14  4797.5  137.44  4832.6  135.88  4853.4  137.48
  4889.1  136.56  4934.6  137.99  4960.4  136.98  4981.2  133.03  4991.3  127.23
  5028.4  127.23  5029.4  127.73  5030.7  133.88  5067.7  137.58  5117.4  135.12
  5144.9  137.55    5167  137.59  5187.9  140.32    5208   140.4    5345  141.25
  5409.2  143.23    5430  145.27  5444.4  144.46  5450.8  146.31  5471.1  147.49
#Mann= 8 ,-1 , 0
  4463.8     .05       0  4528.5     .12       0  4660.3      .1       0
  4889.1     .05       0  4934.6      .1       0  4981.2     .07       0
  5030.7      .1       0    5208     .12       0
Bank Sta=4981.2,5030.7
XS Rating Curve= 0 ,0
Exp/Cntr=0.3,0.1

Type RM Length L Ch R = 1 ,35384   ,359,359,359
BEGIN DESCRIPTION:
Mapping XS 0432b14f
END DESCRIPTION:
XS GIS Cut Line= 3
      3866781.04     10098457.31      3866723.74     10098819.29
      3866533.65     10099254.17
#Sta/Elev= 30
    4636  145.54  4710.7  145.88  4749.2  144.25  4754.3  144.99  4761.3     144
  4778.3  144.31  4791.7   143.8  4811.6  139.99  4816.6  141.74  4842.3  138.21
  4877.3  137.35  4884.1   137.9  4913.2  136.21  4963.8  137.06  4973.9  135.66
  4974.6  126.87  4975.6  126.37  5012.8  126.37  5013.8  126.87  5015.3  133.41
  5025.2  134.96  5059.6   133.3  5082.9  133.57  5124.3  139.14  5185.6  139.46
  5234.2  139.98  5288.2  138.59  5333.3  138.76  5450.3  145.86  5477.1  146.62
#Mann= 6 ,-1 , 0
    4636     .05       0  4778.3     .12       0  4877.3      .1       0
  4973.9     .07       0  5025.2      .1       0  5185.6     .12       0
Bank Sta=4973.9,5025.2
XS Rating Curve= 0 ,0
Exp/Cntr=0.3,0.1

Type RM Length L Ch R = 1 ,35025   ,525,525,525
BEGIN DESCRIPTION:
CRYSTAL CREEK 70.0
END DESCRIPTION:
XS GIS Cut Line= 3
      3866751.96     10098452.56      3866406.18     10098774.86
      3865923.17     10098897.35
#Sta/Elev= 30
  4527.3  145.46  4737.9  145.66  4833.6  144.18  4870.3  142.26  4925.5  134.83
  4939.7  137.34    4968  137.29  4974.8  135.09  4982.2  135.24  4995.4  127.42
  5009.3  129.22  5039.5   127.9  5045.2  128.44  5050.3  132.83  5086.1  132.59
  5091.3   136.4  5101.4  135.39  5121.9  136.93  5142.7  133.52    5184  134.03
  5190.4   125.9  5227.6   125.9 5234.54 134.249  5235.6  135.65    5250  137.15
  5318.1  136.69  5372.9  138.48  5403.6  144.71  5490.7  158.34  5498.3  157.84
#Mann= 6 ,-1 , 0
  4527.3     .05       0  4737.9     .12       0  4870.3      .1       0
    5184     .07       0 5234.54      .1       0  5403.6     .05       0
Bank Sta=5184,5234.54
XS Rating Curve= 0 ,0
Exp/Cntr=0.3,0.1

Type RM Length L Ch R = 1 ,34500   ,500,500,500
BEGIN DESCRIPTION:
CRYSTAL CREEK 69.0
END DESCRIPTION:
XS GIS Cut Line= 3
      3866725.19     10098421.67      3866143.84      10098471.7
      3865891.92     10098435.57
#Sta/Elev= 30
  4416.5  145.63  4494.1  145.11  4550.4  145.94  4581.9  144.15    4587  145.11
  4674.8  138.45  4700.5  137.58  4755.1  138.39  4802.1  136.84  4865.5  134.93
  4945.8  136.74  4965.9  135.87  4971.4  127.02  4972.4  126.52  5018.5  126.52
  5026.3  135.39  5046.5   135.3  5076.8  133.28  5086.9  134.77  5127.3  136.25
  5137.4  138.63  5157.6  148.22  5162.1  149.33  5176.6  152.25  5181.7   151.5
    5198  153.95  5208.1  156.75  5218.2  156.64  5238.4  152.47  5254.5  151.09
#Mann= 6 ,-1 , 0
  4416.5     .05       0  4550.4     .12       0  4802.1      .1       0
  4965.9     .07       0  5026.3      .1       0  5162.1     .05       0
Bank Sta=4965.9,5026.3
XS Rating Curve= 0 ,0
Exp/Cntr=0.3,0.1

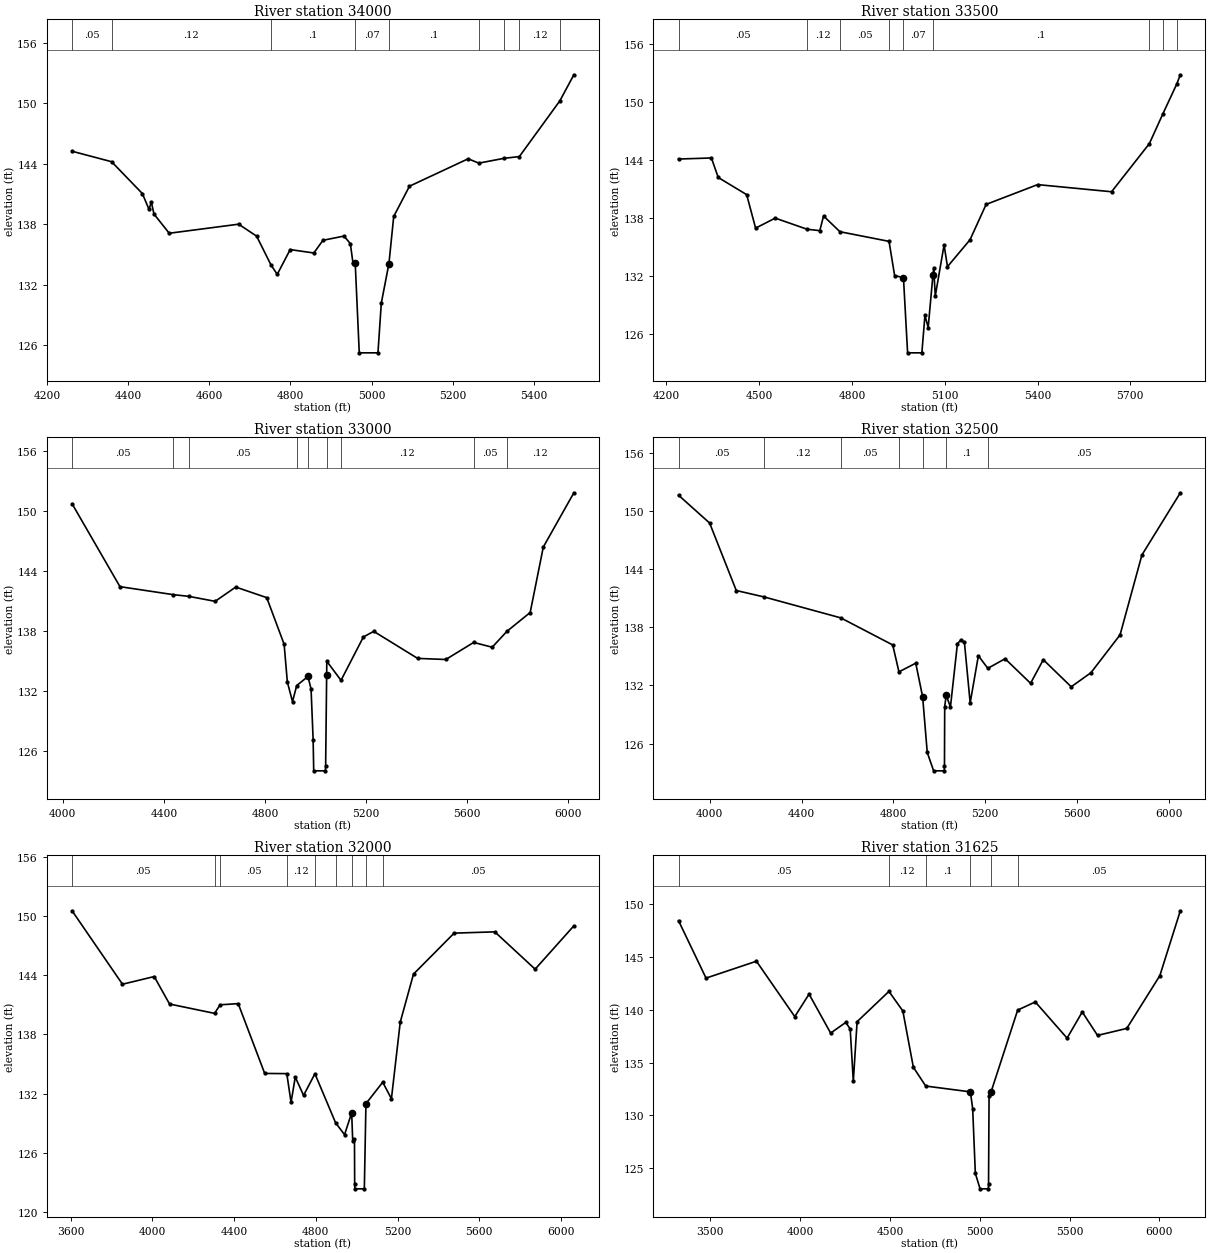
Type RM Length L Ch R = 1 ,34000   ,500,500,500
BEGIN DESCRIPTION:
CRYSTAL CREEK 68.0
END DESCRIPTION:
XS GIS Cut Line= 3
      3866747.11     10098375.76      3866091.44     10098035.28
      3865602.28     10097936.17
#Sta/Elev= 30
  4261.2  145.24  4358.7   144.2  4434.6  141.04    4451  139.47  4456.7  140.21
  4463.2  139.01  4500.9   137.1  4672.2     138  4716.5  136.81    4752  133.95
  4767.4  133.02  4799.3  135.48  4857.6  135.14  4880.1   136.4    4932  136.82
  4947.7  136.07  4954.1  134.17  4959.7  134.16  4969.7  125.23  5015.8  125.23
  5024.1  130.17  5042.9  134.09  5054.7  138.77  5093.6  141.77  5238.3  144.49
  5264.7  144.06  5327.1  144.54  5364.6  144.71  5464.5  150.24  5499.1  152.83
#Mann= 9 ,-1 , 0
  4261.2     .05       0  4358.7     .12       0    4752      .1       0
  4959.7     .07       0  5042.9      .1       0  5264.7     .12       0
  5327.1     .05       0  5364.6     .12       0  5464.5     .05       0
Bank Sta=4959.7,5042.9
XS Rating Curve= 0 ,0
Exp/Cntr=0.3,0.1

Type RM Length L Ch R = 1 ,33500   ,500,500,500
BEGIN DESCRIPTION:
CRYSTAL CREEK 67.0
END DESCRIPTION:
XS GIS Cut Line= 3
      3867104.67     10097976.42      3866405.88     10097659.56
      3865584.71     10097896.33
#Sta/Elev= 30
  4239.7  144.12    4346  144.23    4368  142.21  4459.9  140.43  4488.8  136.96
  4552.2     138  4654.8  136.85  4696.3   136.7  4708.4  138.22  4761.3  136.59
  4920.1  135.59  4938.1  132.05  4966.7  131.83  4980.1  124.04  5026.2  124.04
  5036.1  127.92  5046.6  126.66  5061.9  132.07  5064.4  132.79  5069.6  129.94
    5098  135.22    5109  132.97  5181.9  135.76  5233.9  139.42  5400.4  141.47
  5639.3  140.73  5761.4  145.71  5805.6  148.83  5849.9  151.88  5861.6  152.85
#Mann= 9 ,-1 , 0
  4239.7     .05       0  4654.8     .12       0  4761.3     .05       0
  4920.1      .1       0  4966.7     .07       0  5061.9      .1       0
  5761.4     .12       0  5805.6     .05       0  5849.9     .12       0
Bank Sta=4966.7,5061.9
XS Rating Curve= 0 ,0
Exp/Cntr=0.3,0.1

Type RM Length L Ch R = 1 ,33000   ,500,500,500
BEGIN DESCRIPTION:
CRYSTAL CREEK 66.0
END DESCRIPTION:
XS GIS Cut Line= 3
      3867302.65     10097049.35      3866358.15     10097240.29
      3865425.19     10097656.52
#Sta/Elev= 30
  4036.4  150.75  4225.9  142.44  4436.7  141.64  4497.7  141.47  4602.4  140.97
    4684   142.4  4806.5  141.34  4875.3  136.67  4888.1  132.88  4908.5  130.92
  4925.2  132.53  4969.7  133.44  4981.9  132.18  4990.1  127.12  4992.4  123.98
  5038.6  123.98  5039.6  124.48  5043.6 133.593  5044.2  134.96  5100.4  133.05
    5189   137.4  5229.9  137.96  5403.5  135.25    5515  135.14  5625.2  136.85
  5698.5  136.37  5756.7  137.96  5848.8  139.85  5900.7  146.41  6021.6  151.85
#Mann= 9 ,-1 , 0
  4036.4     .05       0  4436.7     .12       0  4497.7     .05       0
  4925.2      .1       0  4969.7     .07       0  5043.6      .1       0
  5100.4     .12       0  5625.2     .05       0  5756.7     .12       0
Bank Sta=4969.7,5043.6
XS Rating Curve= 0 ,0
Exp/Cntr=0.3,0.1

Type RM Length L Ch R = 1 ,32500   ,500,500,500
BEGIN DESCRIPTION:
CRYSTAL CREEK 65.0
END DESCRIPTION:
XS GIS Cut Line= 3
      3867288.76     10096924.35      3866164.91     10096855.04
      3865171.72     10097222.58
#Sta/Elev= 30
  3864.2   151.6  3999.6  148.73  4115.6  141.78  4238.1  141.11  4570.7  138.96
  4796.9  136.17  4823.9   133.4  4897.1  134.29  4927.1  130.83  4947.2  125.09
    4975   123.2  5021.2   123.2  5022.2   123.7  5023.2  129.82  5029.7  130.99
  5048.2  129.78  5078.6   136.3  5093.7  136.69    5109  136.45  5134.1   130.2
  5169.8  135.06  5210.9  133.76  5286.1  134.75  5397.1  132.22  5452.5  134.65
  5574.1  131.86    5660  133.31  5786.8  137.21  5881.9  145.44  6049.2  151.85
#Mann= 7 ,-1 , 0
  3864.2     .05       0  4238.1     .12       0  4570.7     .05       0
  4823.9      .1       0  4927.1     .07       0  5029.7      .1       0
  5210.9     .05       0
Bank Sta=4927.1,5029.7
XS Rating Curve= 0 ,0
Exp/Cntr=0.3,0.1

Type RM Length L Ch R = 1 ,32000   ,375,375,375
BEGIN DESCRIPTION:
CRYSTAL CREEK 64.0
END DESCRIPTION:
XS GIS Cut Line= 3
      3867333.83     10096788.92      3865987.19     10096430.21
        3865063.     10096955.62
#Sta/Elev= 30
  3606.4  150.56  3853.2   143.1  4008.5  143.88  4083.6  141.09    4304  140.14
  4331.2  141.01  4419.8  141.13  4549.5  134.04  4657.6  134.02  4678.5  131.11
  4699.2  133.67  4739.8  131.81  4795.4  134.01  4896.5  129.03  4940.4  127.82
  4975.3  130.04  4980.5  127.15    4989   127.4    4990  122.82    4991  122.32
  5037.3  122.32  5045.2  130.97  5127.3  133.15  5169.9  131.47  5213.1  139.25
    5278  144.13  5476.9  148.29  5675.9  148.42  5873.5  144.63  6063.1  149.03
#Mann= 9 ,-1 , 0
  3606.4     .05       0    4304     .12       0  4331.2     .05       0
  4657.6     .12       0  4795.4     .05       0  4896.5      .1       0
  4975.3     .07       0  5045.2      .1       0  5127.3     .05       0
Bank Sta=4975.3,5045.2
XS Rating Curve= 0 ,0
Exp/Cntr=0.3,0.1

Type RM Length L Ch R = 1 ,31625   ,136,136,136
BEGIN DESCRIPTION:
Mapping XS 75a4ff48
END DESCRIPTION:
XS GIS Cut Line= 4
      3867303.44     10096730.55      3865730.52     10096220.13
      3865435.38     10096126.38      3864827.76     10096692.34
#Sta/Elev= 30
  3322.8  148.45  3475.9  143.01  3756.5  144.61    3970  139.36  4049.5  141.49
  4169.7   137.8  4253.8  138.81  4278.5  138.19  4295.9  133.22  4316.9  138.88
  4494.2  141.75  4571.5   139.9  4630.2  134.56  4699.1  132.78  4947.7  132.23
  4960.4  130.65  4975.2  124.51  5001.5  123.04  5047.8  123.04  5048.8  123.54
  5051.7  131.87  5063.2  132.25    5211  139.98  5309.1  140.75    5486  137.32
  5570.5   139.8  5655.5  137.58  5818.2  138.24  6002.4  143.24  6116.5  149.39
#Mann= 6 ,-1 , 0
  3322.8     .05       0  4494.2     .12       0  4699.1      .1       0
  4947.7     .07       0  5063.2      .1       0    5211     .05       0
Bank Sta=4947.7,5063.2
XS Rating Curve= 0 ,0
Exp/Cntr=0.3,0.1

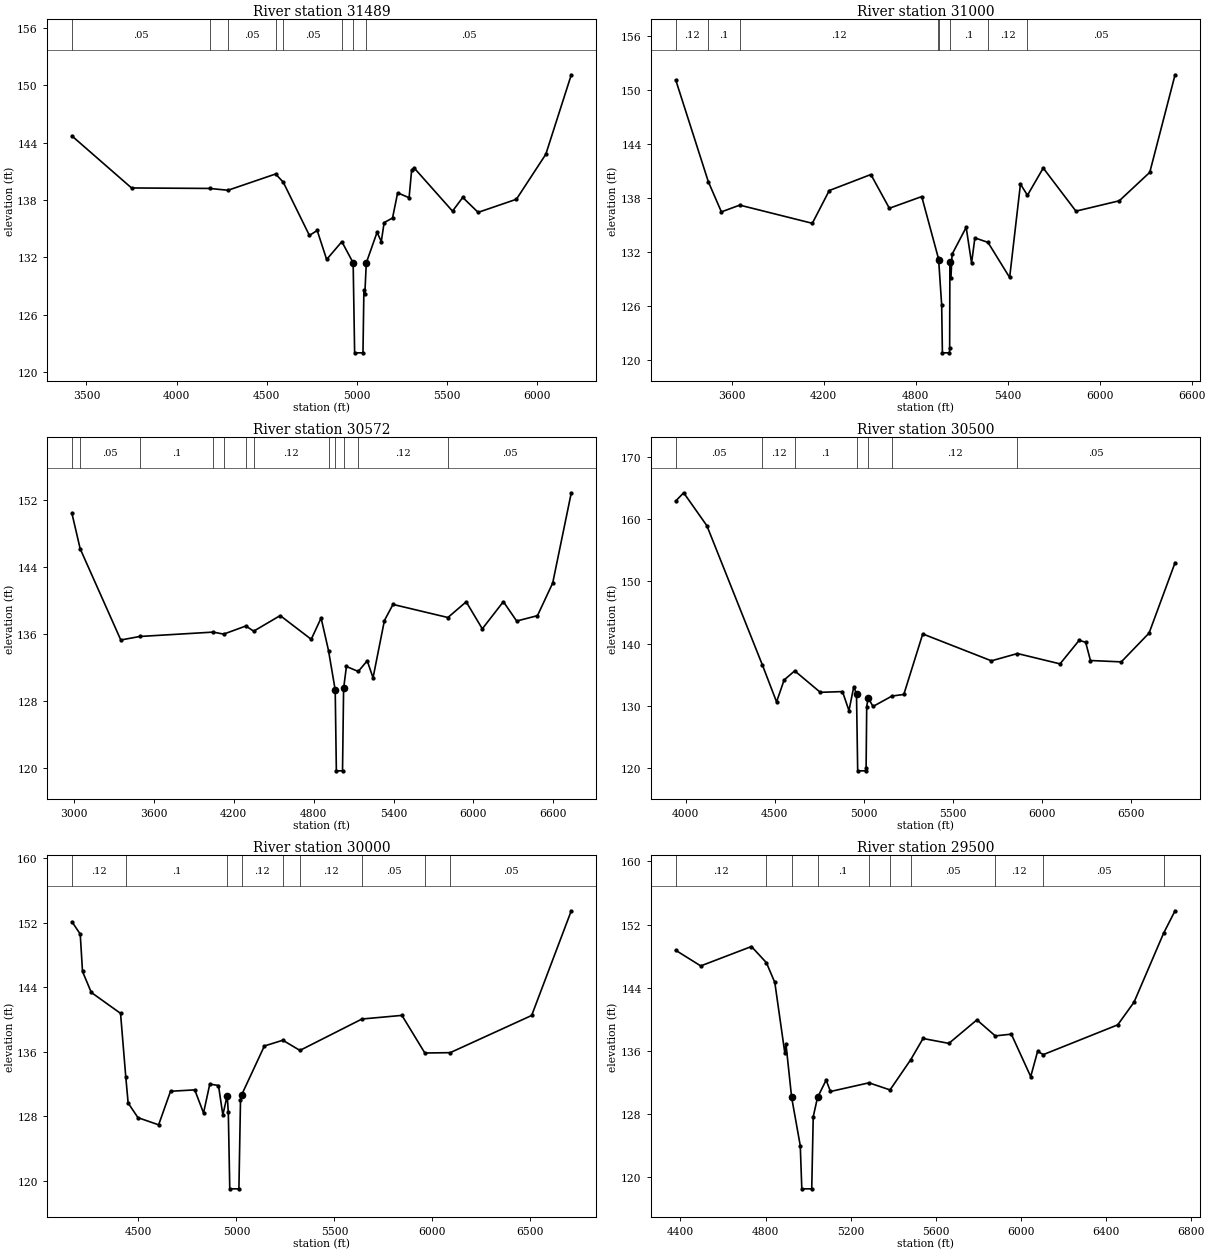
Type RM Length L Ch R = 1 ,31489   ,489,489,489
BEGIN DESCRIPTION:
CRYSTAL CREEK 63.0
END DESCRIPTION:
XS GIS Cut Line= 4
      3867213.99      10096557.8      3865709.69     10096077.77
      3865501.36     10096018.74      3864772.88     10096666.07
#Sta/Elev= 30
  3419.5  144.69  3750.1  139.26  4182.8  139.21  4285.1  139.02  4549.5  140.72
  4592.1  139.85  4736.9   134.3    4780  134.82  4832.5  131.79  4916.7  133.65
  4979.5  131.44  4987.7  122.04    5034  122.04  5039.1  128.59  5044.3  128.18
  5052.4  131.44  5112.2  134.63  5135.6  133.66  5151.3  135.64  5197.9  136.12
  5226.3  138.75  5289.8  138.24    5304  141.13  5318.3  141.34  5530.7  136.84
  5587.5  138.27  5672.8  136.71  5885.2  138.08  6048.3  142.78  6189.6  151.08
#Mann= 8 ,-1 , 0
  3419.5     .05       0  4182.8     .12       0  4285.1     .05       0
  4549.5     .12       0  4592.1     .05       0  4916.7      .1       0
  4979.5     .07       0  5052.4     .05       0
Bank Sta=4979.5,5052.4
XS Rating Curve= 0 ,0
Exp/Cntr=0.3,0.1

Type RM Length L Ch R = 1 ,31000   ,428,428,428
BEGIN DESCRIPTION:
CRYSTAL CREEK 62.0
END DESCRIPTION:
XS GIS Cut Line= 3
      3867594.24     10095466.02       3865838.5     10095638.57
      3864726.22      10096632.7
#Sta/Elev= 30
  3235.8  151.16  3448.4  139.85  3533.6   136.5  3653.4  137.25  4126.5  135.23
    4237  138.87  4508.3  140.65  4628.9   136.9  4839.9   138.2  4948.5  131.35
  4950.4  131.13    4970  126.15  4974.7  120.84    5021  120.84    5022  121.34
  5023.6  130.96  5030.3  129.11  5037.8  131.79  5129.8  134.78  5164.9  130.81
  5186.6  133.61  5271.9  133.11  5413.2  129.21  5483.7  139.59  5529.3  138.34
  5632.2  141.37  5845.4  136.58    6128  137.73  6326.9  140.89  6491.8  151.73
#Mann= 8 ,-1 , 0
  3235.8     .12       0  3448.4      .1       0  3653.4     .12       0
  4948.5      .1       0  4950.4     .07       0  5023.6      .1       0
  5271.9     .12       0  5529.3     .05       0
Bank Sta=4950.4,5023.6
XS Rating Curve= 0 ,0
Exp/Cntr=0.3,0.1

Type RM Length L Ch R = 1 ,30572   ,72,72,72
BEGIN DESCRIPTION:
Mapping XS d79a1941
END DESCRIPTION:
XS GIS Cut Line= 4
      3867654.09     10094577.79      3865752.27     10095240.88
      3864810.38     10096489.23      3864694.05     10096614.25
#Sta/Elev= 30
  2985.9   150.4  3047.5  146.19  3352.6  135.31  3496.2  135.73  4046.2  136.25
  4124.8  136.01  4291.8  136.98  4350.1  136.36  4549.3  138.22  4782.3  135.39
  4856.4  137.93    4912  134.05  4962.3  129.35  4970.9  119.71  5017.2  119.71
  5025.3  129.53  5046.5  132.15  5135.4  131.56  5202.6  132.83  5246.3   130.8
  5331.7  137.63  5396.2  139.55  5808.3  137.99  5945.7  139.86  6066.5  136.64
  6224.7  139.88  6324.6  137.57  6480.7  138.21    6595   142.1  6734.6  152.86
#Mann= 12 ,-1 , 0
  2985.9     .12       0  3047.5     .05       0  3496.2      .1       0
  4046.2     .05       0  4124.8     .12       0  4291.8     .05       0
  4350.1     .12       0    4912      .1       0  4962.3     .07       0
  5025.3      .1       0  5135.4     .12       0  5808.3     .05       0
Bank Sta=4962.3,5025.3
XS Rating Curve= 0 ,0
Exp/Cntr=0.3,0.1

Type RM Length L Ch R = 1 ,30500   ,500,500,500
BEGIN DESCRIPTION:
CRYSTAL CREEK 61.0
END DESCRIPTION:
XS GIS Cut Line= 3
      3866266.14     10094297.35      3865701.28      10095189.7
      3864655.88     10096593.39
#Sta/Elev= 30
  3943.9  162.91  3988.6  164.23  4119.1  158.94  4431.3  136.55  4510.7  130.64
  4553.1  134.16  4612.6  135.63  4756.5  132.18  4881.1   132.3  4917.6  129.24
  4944.7   133.1  4959.9  131.89  4966.6  119.57  5012.9  119.57  5013.9  120.07
  5017.3   129.9  5025.6  131.29  5052.7  129.91  5159.1  131.58  5225.8  131.84
  5332.2  141.56    5718  137.24  5864.5  138.41  6103.8  136.75  6211.2  140.53
  6247.7  140.22  6274.7  137.29  6447.9  137.07  6604.3   141.7  6750.2     153
#Mann= 7 ,-1 , 0
  3943.9     .05       0  4431.3     .12       0  4612.6      .1       0
  4959.9     .07       0  5025.6      .1       0  5159.1     .12       0
  5864.5     .05       0
Bank Sta=4959.9,5025.6
XS Rating Curve= 0 ,0
Exp/Cntr=0.3,0.1

Type RM Length L Ch R = 1 ,30000   ,500,500,500
BEGIN DESCRIPTION:
CRYSTAL CREEK 60.0
END DESCRIPTION:
XS GIS Cut Line= 3
      3865684.51     10094293.06      3865302.71      10095040.6
      3864612.24     10096603.58
#Sta/Elev= 30
  4160.6   152.1  4202.9  150.57  4214.5  145.94  4259.4  143.34  4408.6  140.75
  4435.5  132.81  4447.4  129.64  4497.4  127.83  4602.9  126.94  4663.7   131.1
  4787.2  131.27  4832.1  128.41    4864  131.99  4908.4  131.81  4930.6  128.17
  4952.9  130.57  4958.5  128.49    4966  119.01  5012.6  119.01  5020.7  129.96
  5026.1  130.63  5142.6  136.71  5236.7  137.42  5323.9  136.16  5640.5  140.05
  5844.4   140.5  5961.4  135.84  6090.8  135.88  6506.5  140.49  6708.7  153.46
#Mann= 9 ,-1 , 0
  4160.6     .12       0  4435.5      .1       0  4952.9     .07       0
  5026.1     .12       0  5236.7     .05       0  5323.9     .12       0
  5640.5     .05       0  5961.4     .12       0  6090.8     .05       0
Bank Sta=4952.9,5026.1
XS Rating Curve= 0 ,0
Exp/Cntr=0.3,0.1

Type RM Length L Ch R = 1 ,29500   ,551,551,551
BEGIN DESCRIPTION:
CRYSTAL CREEK 59.0
END DESCRIPTION:
XS GIS Cut Line= 3
      3864958.88     10094285.43      3864843.35     10094896.91
      3864569.99     10096601.43
#Sta/Elev= 30
  4377.7  148.74  4495.4  146.76  4733.9  149.22  4804.2  147.17  4843.8  144.66
  4891.1  135.67  4896.2  136.87  4922.8  130.11  4963.5  123.97  4970.8   118.5
  5017.4   118.5  5024.5  127.65  5044.7  130.08  5085.2  132.29  5105.5  130.84
  5286.7  131.94  5385.7  131.04  5483.2  134.88    5541  137.56  5662.5  136.94
  5794.2  139.92  5880.7  137.89  5956.2  138.11  6047.4  132.73  6079.8  135.92
    6107  135.52  6456.6  139.29  6533.5  142.17  6672.5  150.91  6726.3  153.75
#Mann= 10 ,-1 , 0
  4377.7     .12       0  4804.2      .1       0  4922.8     .07       0
  5044.7      .1       0  5286.7     .05       0  5385.7     .12       0
  5483.2     .05       0  5880.7     .12       0    6107     .05       0
  6672.5     .12       0
Bank Sta=4922.8,5044.7
XS Rating Curve= 0 ,0
Exp/Cntr=0.3,0.1

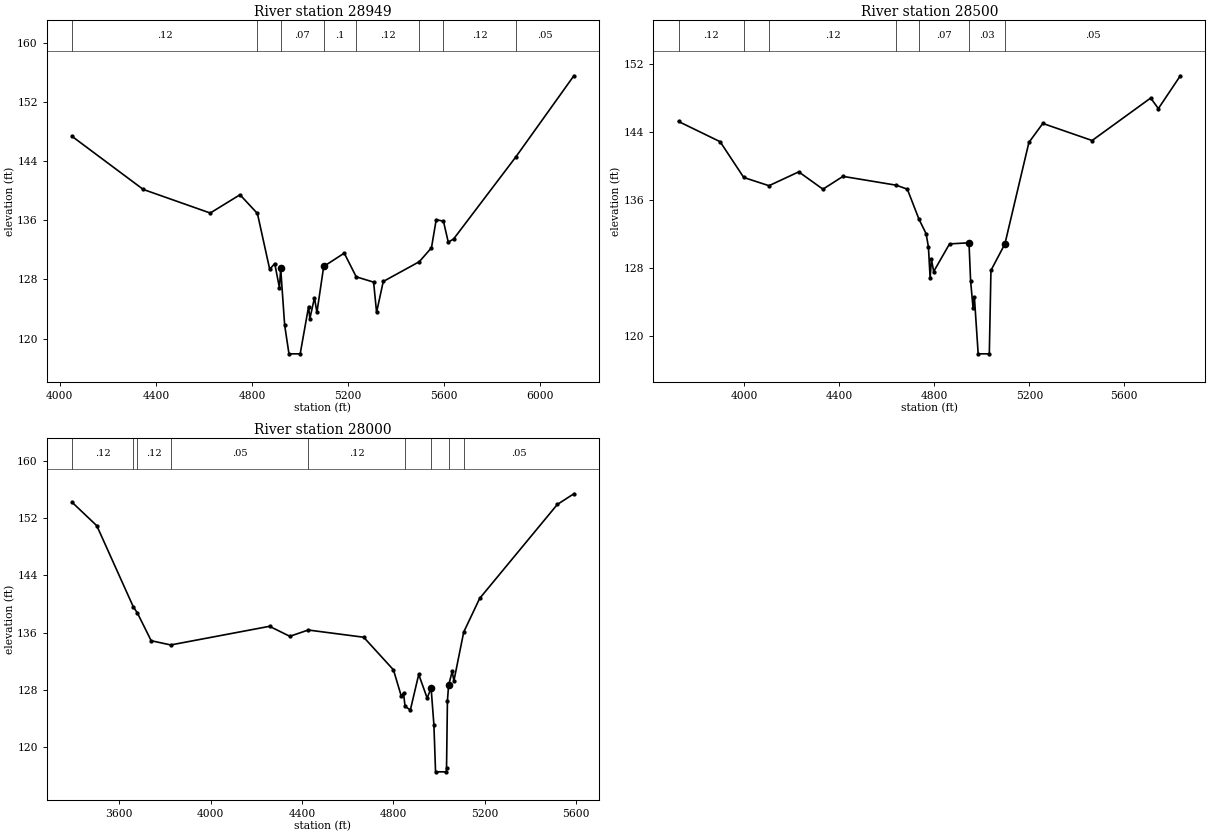
Type RM Length L Ch R = 1 ,28949   ,449,449,449
BEGIN DESCRIPTION:
CRYSTAL CREEK 58.0
END DESCRIPTION:
XS GIS Cut Line= 3
      3864670.68     10094254.21      3864432.46     10095172.83
      3864139.43     10096275.04
#Sta/Elev= 30
    4051  147.34  4347.3  140.17  4626.3  136.98  4750.2  139.45  4822.8  136.92
    4874  129.37  4894.9  130.15  4914.6  126.86  4919.7   129.5  4936.2  121.84
  4954.2  117.95  5000.9  117.95  5035.9  124.34  5041.1  122.69  5060.3  125.52
  5070.6  123.56 5098.87 129.762  5184.4  131.56  5234.2  128.36  5306.6  127.64
    5319  123.56  5346.8  127.73  5496.8   130.4  5547.6  132.28  5567.3  136.09
  5597.5  135.87  5617.5  133.04  5639.7  133.47  5899.7   144.6  6140.5  155.53
#Mann= 8 ,-1 , 0
    4051     .12       0  4822.8      .1       0  4919.7     .07       0
 5098.87      .1       0  5234.2     .12       0  5496.8     .05       0
  5597.5     .12       0  5899.7     .05       0
Bank Sta=4919.7,5098.87
XS Rating Curve= 0 ,0
Exp/Cntr=0.3,0.1

Type RM Length L Ch R = 1 ,28500   ,500,500,500
BEGIN DESCRIPTION:
CRYSTAL CREEK 57.0
END DESCRIPTION:
XS GIS Cut Line= 3
      3864604.72     10094233.35      3864048.67     10095383.82
      3863729.89     10096156.55
#Sta/Elev= 30
  3722.2  145.26  3897.4  142.88  3996.9  138.67  4103.2   137.7  4228.5  139.33
  4330.5  137.29  4414.9   138.8  4639.4  137.76    4686  137.29    4735  133.76
  4764.9  132.06  4774.8   130.5    4782  126.83  4787.5  129.03    4797   127.6
  4863.7  130.85  4945.7  130.98  4952.5   126.5  4962.7  123.33  4968.3  124.63
  4984.4  117.91  5031.3  117.91  5038.2  127.73  5096.9  130.84    5198  142.79
  5256.6  145.03  5464.3  143.02    5711  148.02  5743.4  146.78  5835.9  150.64
#Mann= 7 ,-1 , 0
  3722.2     .12       0  3996.9      .1       0  4103.2     .12       0
  4639.4      .1       0    4735     .07       0  4945.7     .03       0
  5096.9     .05       0
Bank Sta=4945.7,5096.9
XS Rating Curve= 0 ,0
Exp/Cntr=0.3,0.1

Type RM Length L Ch R = 1 ,28000   ,606,606,606
BEGIN DESCRIPTION:
CRYSTAL CREEK 56.0
END DESCRIPTION:
XS GIS Cut Line= 3
      3864330.42     10093740.29      3863639.84     10095191.23
      3863243.61     10095629.19
#Sta/Elev= 30
  3393.1  154.26  3501.5  150.97  3661.4   139.6    3679  138.76  3739.6  134.86
  3825.3  134.27  4257.8  136.88  4346.7  135.48  4427.4  136.36  4670.2  135.35
  4800.5  130.78  4834.7  127.11  4844.8  127.52  4851.3  125.66  4874.6  125.16
  4911.2  130.14  4948.2  126.82  4965.4  128.24  4977.7  123.08  4984.9  116.49
    5032  116.49    5033  116.99  5036.9  126.41  5041.9 128.597  5057.8  130.55
  5065.3  129.24  5108.2  136.07  5178.1  140.79  5518.1  153.95  5590.6  155.45
#Mann= 9 ,-1 , 0
  3393.1     .12       0  3661.4      .1       0    3679     .12       0
  3825.3     .05       0  4427.4     .12       0  4851.3      .1       0
  4965.4     .07       0  5041.9      .1       0  5108.2     .05       0
Bank Sta=4965.4,5041.9
XS Rating Curve= 0 ,0
Exp/Cntr=0.3,0.1