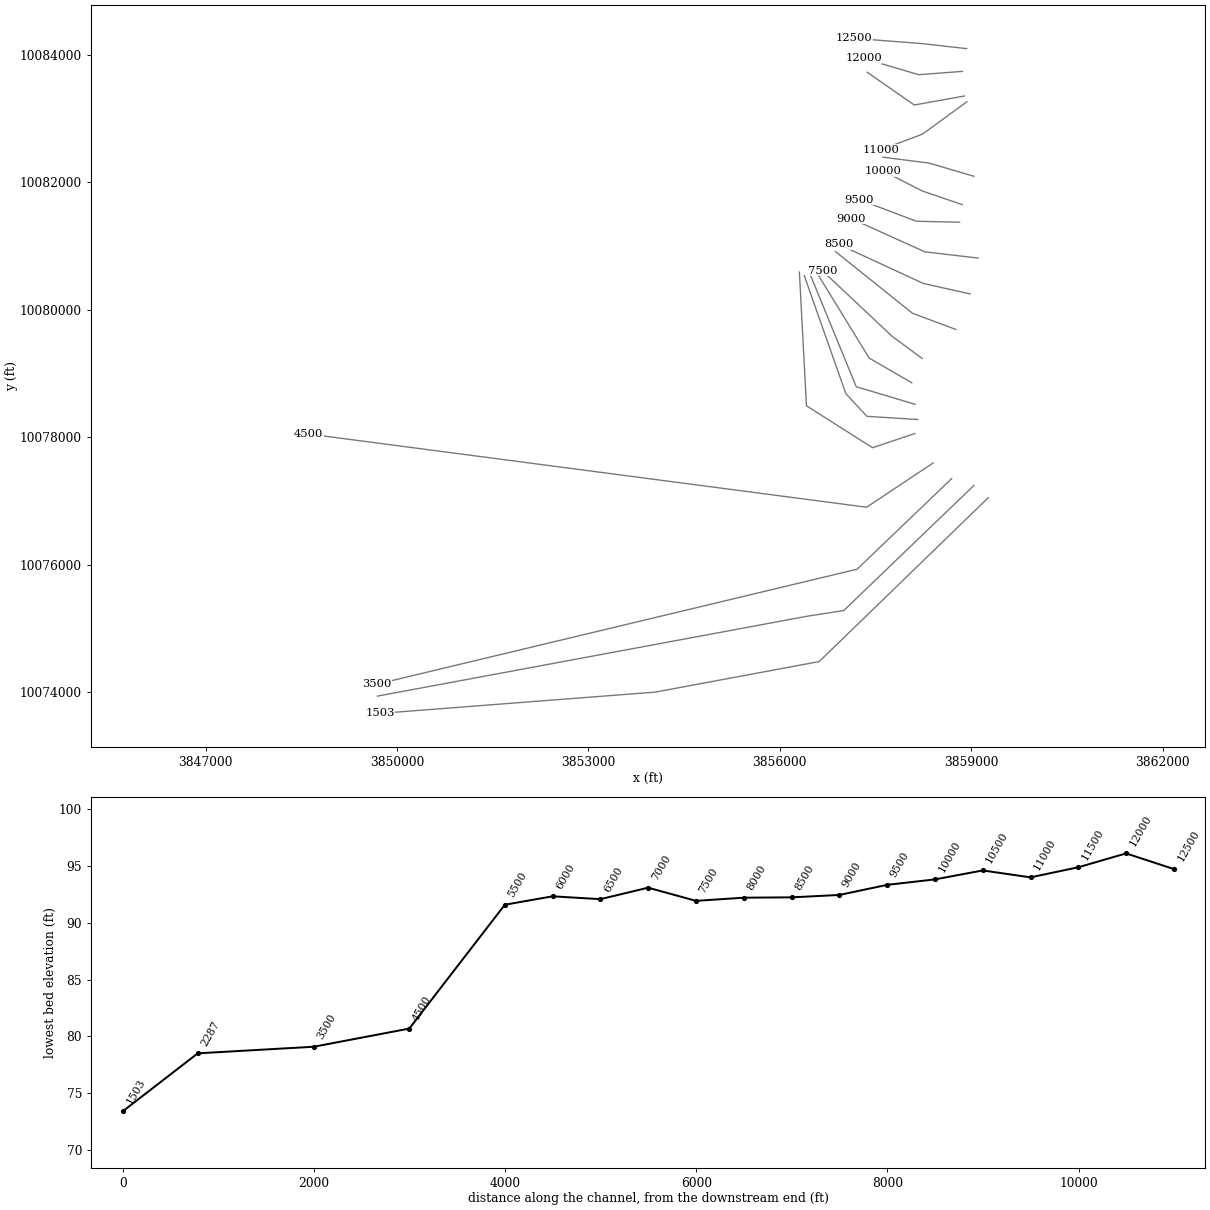
HEC-RAS study CRYSTAL CREEK.prj: CRYSTAL CREEK Base Level Engineering

--- CRYSTAL CREEK.g10 (geometry) --- (continued)

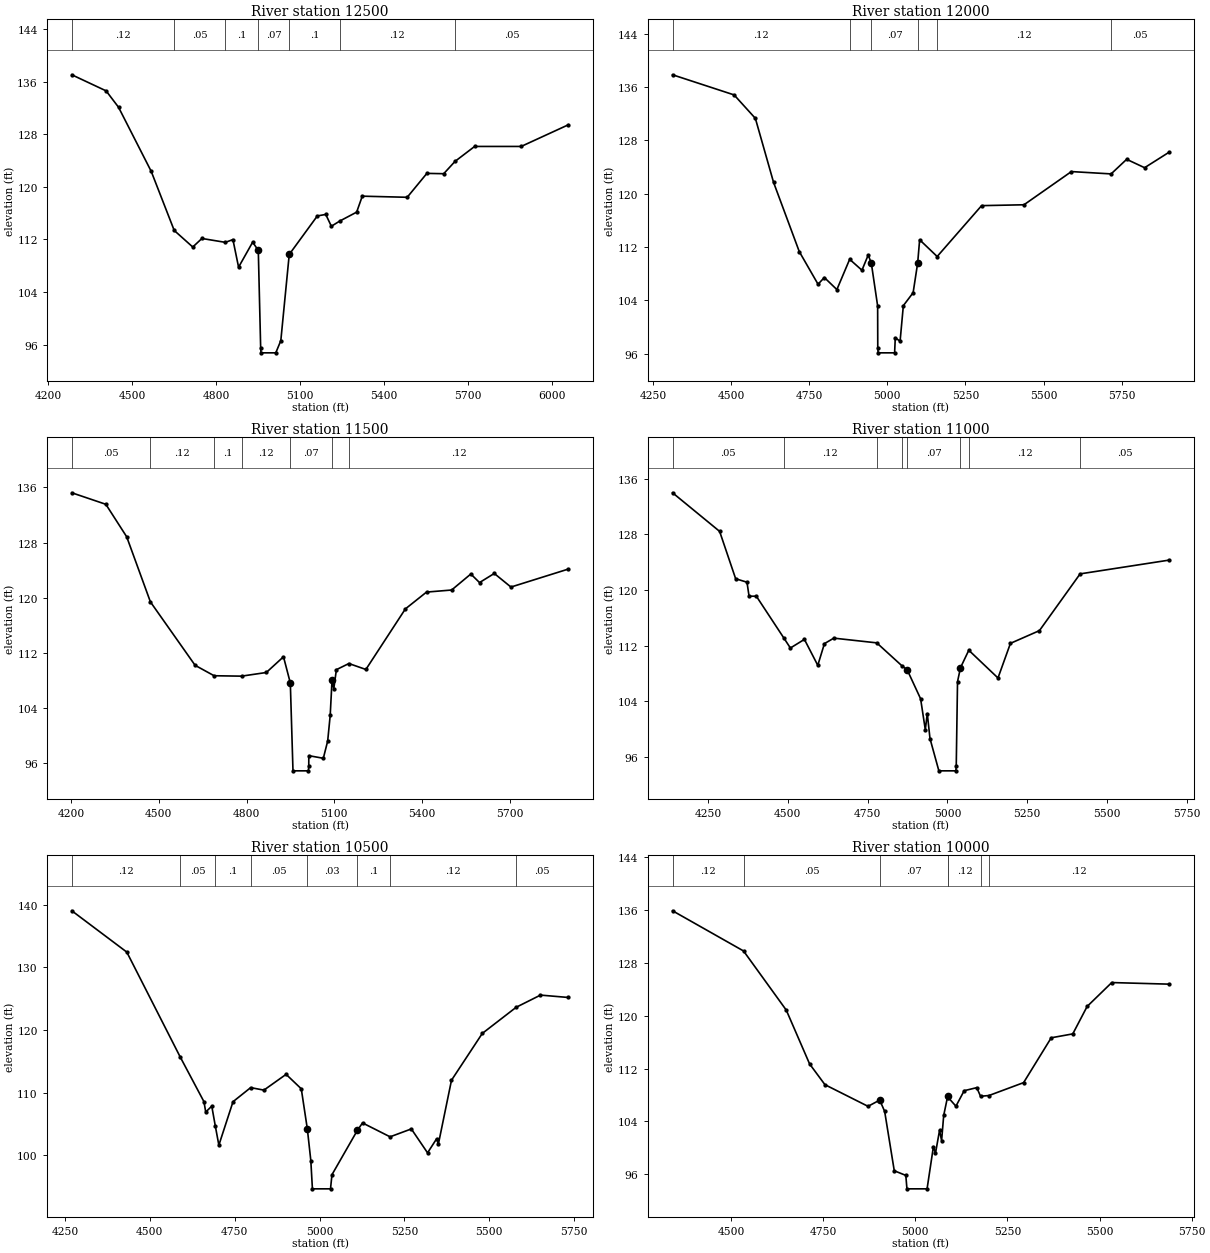
Type RM Length L Ch R = 1 ,12500   ,500,500,500
BEGIN DESCRIPTION:
CRYSTAL CREEK 25.0
END DESCRIPTION:
XS GIS Cut Line= 3
      3858929.59     10084097.55      3858218.27     10084177.53
      3857164.01       10084259.
#Sta/Elev= 30
  4284.2  137.07  4406.7  134.62    4451  132.13  4567.7  122.37  4649.9  113.37
  4716.1  110.85  4748.8  112.15  4832.5  111.56  4859.5  111.98  4879.7  107.78
    4930  111.59  4950.1  110.33  4958.6   95.44  4959.8   94.74  5012.5   94.74
  5030.5   96.59  5060.6  109.72  5160.9  115.58    5191  115.81    5211  114.01
  5240.9   114.8  5301.3  116.16  5321.4  118.59  5481.8  118.42  5552.1  122.06
  5612.2  122.01  5652.7  123.89  5722.6  126.16  5888.8  126.16  6057.4  129.46
#Mann= 7 ,-1 , 0
  4284.2     .12       0  4649.9     .05       0  4832.5      .1       0
  4950.1     .07       0  5060.6      .1       0  5240.9     .12       0
  5652.7     .05       0
Bank Sta=4950.1,5060.6
XS Rating Curve= 0 ,0
Exp/Cntr=0.3,0.1

Type RM Length L Ch R = 1 ,12000   ,500,500,500
BEGIN DESCRIPTION:
CRYSTAL CREEK 24.0
END DESCRIPTION:
XS GIS Cut Line= 3
      3858861.96     10083740.77      3858177.03     10083688.75
      3857312.63     10083944.71
#Sta/Elev= 30
  4313.1  137.83    4510  134.81    4578  131.29  4636.2  121.69  4718.4  111.31
  4778.5  106.41  4798.6  107.42  4838.7  105.61  4879.6  110.15  4918.9  108.51
    4939   110.8    4949  109.54  4969.1  103.15  4969.5   96.82  4970.7   96.12
  5023.4   96.12  5025.5   98.38  5040.9   97.86  5051.3   103.2  5082.6  105.14
  5097.2  109.62  5103.4  113.08  5159.5  110.57  5301.6   118.2  5437.2  118.33
  5588.9  123.31  5715.9  122.96  5765.6  125.15    5823  123.89  5901.5  126.22
#Mann= 6 ,-1 , 0
  4313.1     .12       0  4879.6      .1       0    4949     .07       0
  5097.2      .1       0  5159.5     .12       0  5715.9     .05       0
Bank Sta=4949,5097.2
XS Rating Curve= 0 ,0
Exp/Cntr=0.3,0.1

Type RM Length L Ch R = 1 ,11500   ,500,500,500
BEGIN DESCRIPTION:
CRYSTAL CREEK 23.0
END DESCRIPTION:
XS GIS Cut Line= 3
      3858892.26     10083354.48      3858108.25     10083213.41
      3857370.08      10083726.9
#Sta/Elev= 30
  4203.4  135.22  4319.6  133.55  4390.8  128.84  4471.8   119.4  4624.5   110.2
  4689.3  108.69  4782.9  108.63  4867.6  109.16  4926.3  111.44  4949.6  107.64
  4958.7    94.9  5011.4    94.9  5012.6    95.6  5012.7    97.1  5062.3   96.72
  5077.2   99.23  5085.8  102.95    5092  108.02  5098.1  106.82  5106.9  109.57
  5149.6  110.46  5207.6   109.6  5342.5  118.38  5414.7  120.82  5500.5  121.12
    5566  123.44  5595.7   122.2  5646.1  123.52    5703  121.55  5899.2  124.16
#Mann= 7 ,-1 , 0
  4203.4     .05       0  4471.8     .12       0  4689.3      .1       0
  4782.9     .12       0  4949.6     .07       0    5092     .12       0
  5149.6     .12       0
Bank Sta=4949.6,5092
XS Rating Curve= 0 ,0
Exp/Cntr=0.3,0.1

Type RM Length L Ch R = 1 ,11000   ,500,500,500
BEGIN DESCRIPTION:
CRYSTAL CREEK 22.0
END DESCRIPTION:
XS GIS Cut Line= 3
      3858931.36     10083263.33      3858236.11     10082755.79
      3857585.84     10082512.46
#Sta/Elev= 30
  4139.2  133.99  4286.6  128.44  4336.8  121.63  4372.3  121.13  4378.8  119.12
  4401.6  119.12  4487.4  113.13  4508.2  111.67  4552.1  112.91    4594  109.18
  4614.8   112.3  4644.2  113.09  4778.7  112.41  4858.3  109.08    4874  108.53
    4916  104.37  4930.7   99.93  4936.9  102.24  4945.4   98.65  4973.2   94.01
  5026.4   94.01  5027.6   94.71  5031.6  106.83  5040.8  108.83  5066.9  111.35
  5158.3  107.36  5197.3  112.34  5288.1  114.17  5415.5  122.33  5694.3  124.31
#Mann= 8 ,-1 , 0
  4139.2     .05       0  4487.4     .12       0  4778.7      .1       0
  4858.3     .05       0    4874     .07       0  5040.8      .1       0
  5066.9     .12       0  5415.5     .05       0
Bank Sta=4874,5040.8
XS Rating Curve= 0 ,0
Exp/Cntr=0.3,0.1

Type RM Length L Ch R = 1 ,10500   ,500,500,500
BEGIN DESCRIPTION:
CRYSTAL CREEK 21.0
END DESCRIPTION:
XS GIS Cut Line= 3
      3859043.15      10082094.6      3858343.53     10082301.95
      3857616.29     10082395.28
#Sta/Elev= 30
  4270.3  139.04  4432.3  132.44  4589.1  115.74  4659.6  108.54  4664.8  106.89
  4682.6  107.83  4693.2  104.61  4703.5   101.6  4745.2  108.54  4797.2  110.79
  4836.2  110.39  4901.6  112.91  4946.3   110.6  4964.2  104.17  4974.4   99.14
  4979.1   94.62  5032.4   94.62  5036.7   96.88  5111.3  103.94  5126.7  105.15
  5207.9  102.93  5270.5  104.19  5318.3  100.37    5345  102.62  5350.1  101.75
  5388.8  111.97  5479.6  119.45  5579.5  123.63    5651  125.57  5733.2  125.19
#Mann= 8 ,-1 , 0
  4270.3     .12       0  4589.1     .05       0  4693.2      .1       0
  4797.2     .05       0  4964.2     .03       0  5111.3      .1       0
  5207.9     .12       0  5579.5     .05       0
Bank Sta=4964.2,5111.3
XS Rating Curve= 0 ,0
Exp/Cntr=0.3,0.1

Type RM Length L Ch R = 1 ,10000   ,500,500,500
BEGIN DESCRIPTION:
CRYSTAL CREEK 20.0
END DESCRIPTION:
XS GIS Cut Line= 3
      3858859.83     10081651.28      3858236.71     10081863.58
      3857622.75     10082176.06
#Sta/Elev= 30
  4341.7  135.82  4534.3  129.75  4650.2  120.82  4713.5  112.69  4755.1  109.56
    4872  106.29  4903.7  107.23  4917.1  105.53  4943.2   96.56  4974.5   95.86
  4977.6   93.83  5032.2   93.83  5049.4  100.21    5055    99.2    5066  102.66
  5071.6  101.11  5077.3  104.92  5088.3  107.86  5090.3  107.57  5110.5  106.31
  5132.8  108.65    5167  109.11  5177.2  107.81    5200  107.92  5294.1  109.87
    5369  116.64  5427.5  117.23  5466.4  121.37  5533.2  124.98  5688.9  124.74
#Mann= 7 ,-1 , 0
  4341.7     .12       0  4534.3     .05       0  4903.7     .07       0
  5088.3     .05       0  5090.3     .12       0  5177.2      .1       0
    5200     .12       0
Bank Sta=4903.7,5088.3
XS Rating Curve= 0 ,0
Exp/Cntr=0.3,0.1

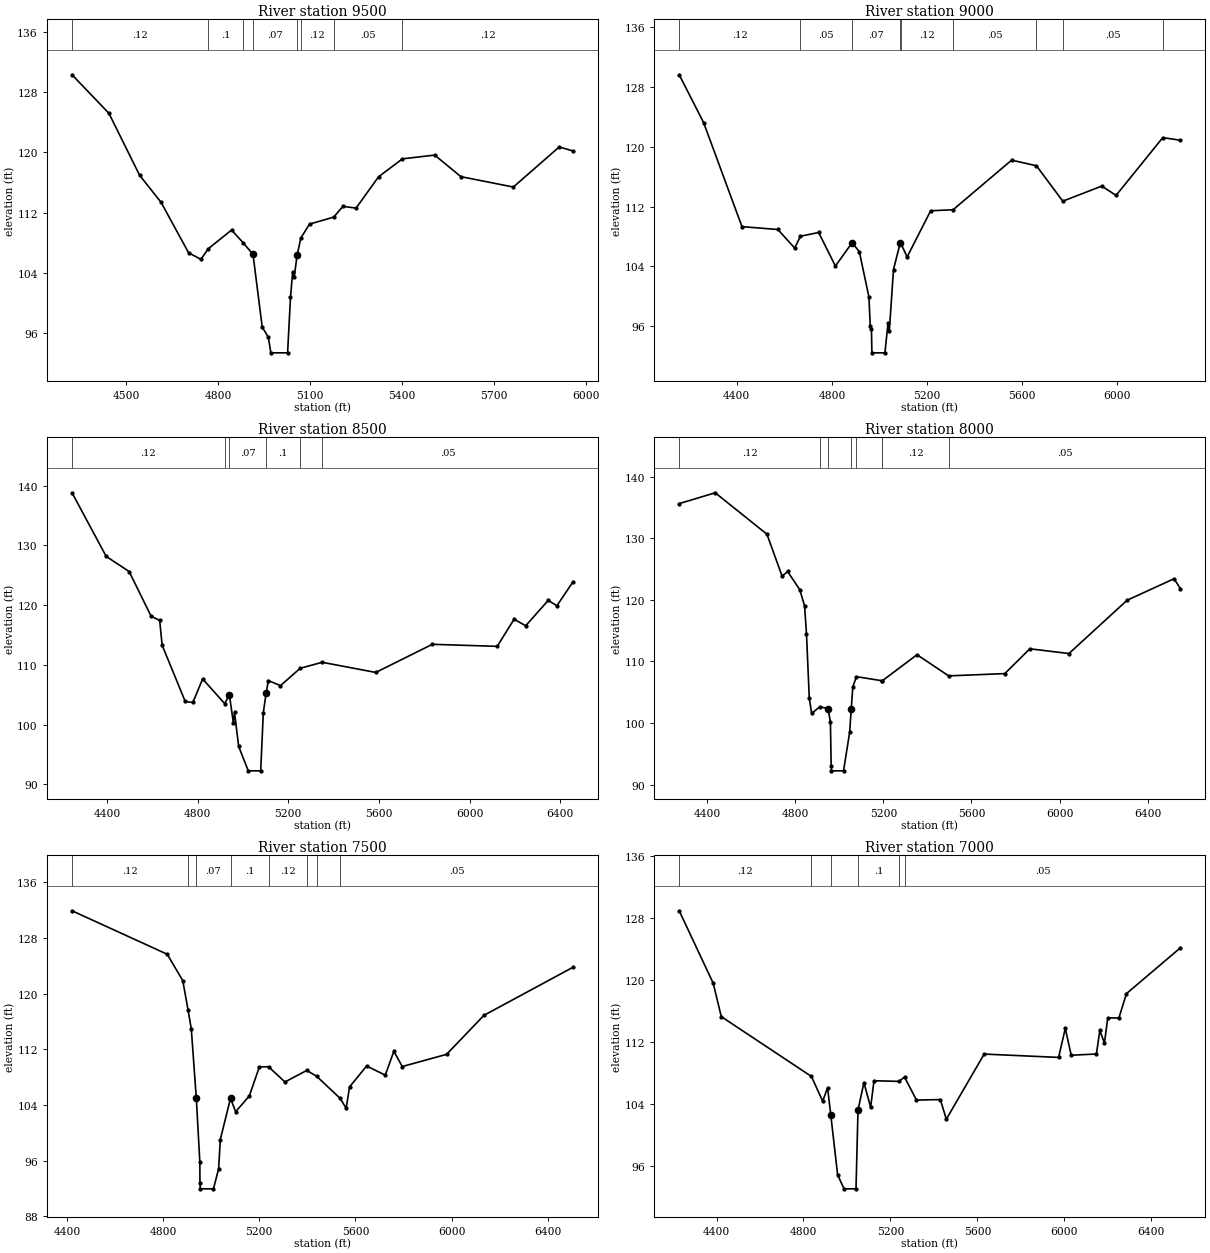
Type RM Length L Ch R = 1 ,9500    ,500,500,500
BEGIN DESCRIPTION:
CRYSTAL CREEK 19.0
END DESCRIPTION:
XS GIS Cut Line= 3
      3858818.17     10081375.23      3858141.73     10081390.18
      3857245.27      10081729.4
#Sta/Elev= 30
  4323.4  130.33  4443.7  125.21  4543.8  116.97  4613.8  113.37  4703.8  106.65
  4743.8  105.79  4768.4  107.21  4843.8  109.68  4881.6     108  4913.9  106.44
  4943.9   96.78  4963.9   95.43  4972.1   93.35  5026.7   93.35  5036.2  100.71
  5043.2  104.11  5048.6   103.5  5057.6  106.31    5070  108.62  5098.2  110.47
  5177.1   111.4  5207.3  112.83  5250.1   112.6  5323.5  116.76  5401.5  119.15
  5506.7  119.65  5592.2  116.78  5763.3   115.4    5913  120.73  5958.5  120.19
#Mann= 8 ,-1 , 0
  4323.4     .12       0  4768.4      .1       0  4881.6     .05       0
  4913.9     .07       0  5057.6      .1       0    5070     .12       0
  5177.1     .05       0  5401.5     .12       0
Bank Sta=4913.9,5057.6
XS Rating Curve= 0 ,0
Exp/Cntr=0.3,0.1

Type RM Length L Ch R = 1 ,9000    ,500,500,500
BEGIN DESCRIPTION:
CRYSTAL CREEK 18.0
END DESCRIPTION:
XS GIS Cut Line= 3
      3859109.87     10080812.73      3858273.76     10080910.52
      3857121.56     10081431.95
#Sta/Elev= 30
  4158.2  129.59  4260.9  123.19    4422  109.31    4573  108.93  4643.5  106.45
  4667.7  108.03  4744.2  108.53  4814.7  104.05  4885.1  107.17  4915.3  105.96
  4955.6   99.92  4961.2   96.06  4966.2   95.68  4968.1   92.46  5022.8   92.46
  5035.8    96.4  5041.3   95.38  5058.9  103.58  5087.5  107.19    5089  107.11
  5116.3  105.27    5215  111.43  5309.4  111.57  5555.3  118.19  5659.8  117.44
  5770.5  112.71  5934.6  114.73  5994.4  113.48  6190.8   121.2  6264.7  120.85
#Mann= 9 ,-1 , 0
  4158.2     .12       0  4667.7     .05       0  4885.1     .07       0
  5087.5     .05       0    5089     .12       0  5309.4     .05       0
  5659.8     .12       0  5770.5     .05       0  6190.8     .12       0
Bank Sta=4885.1,5087.5
XS Rating Curve= 0 ,0
Exp/Cntr=0.3,0.1

Type RM Length L Ch R = 1 ,8500    ,500,500,500
BEGIN DESCRIPTION:
CRYSTAL CREEK 17.0
END DESCRIPTION:
XS GIS Cut Line= 3
      3858984.88     10080250.23      3858249.58     10080414.83
      3856927.81     10081026.17
#Sta/Elev= 30
  4246.5  138.82  4397.2  128.16  4498.3  125.63  4595.3  118.14  4632.9  117.45
  4643.9  113.28  4745.6  103.87  4779.1   103.7  4822.5  107.64  4919.9   103.5
  4940.3  105.02  4957.8  100.31  4962.9  102.05  4981.3   96.33  5023.7   92.25
  5078.4   92.25    5090     102  5102.4  105.27  5112.1  107.37  5165.7  106.52
  5252.4  109.42  5349.6  110.43  5585.8  108.73  5835.2  113.44  6121.4   113.1
  6195.7  117.64  6247.1  116.55  6346.1  120.79  6384.6   119.9  6456.3  123.95
#Mann= 6 ,-1 , 0
  4246.5     .12       0  4919.9      .1       0  4940.3     .07       0
  5102.4      .1       0  5252.4     .12       0  5349.6     .05       0
Bank Sta=4940.3,5102.4
XS Rating Curve= 0 ,0
Exp/Cntr=0.3,0.1

Type RM Length L Ch R = 1 ,8000    ,500,500,500
BEGIN DESCRIPTION:
CRYSTAL CREEK 16.0
END DESCRIPTION:
XS GIS Cut Line= 3
      3858760.96     10079692.92      3858080.32     10079946.95
      3856872.08     10080915.46
#Sta/Elev= 30
  4273.5  135.64  4436.9   137.4  4671.7  130.67  4740.6  123.84  4765.6  124.61
  4820.9  121.65  4842.5  119.03  4851.2   114.5  4863.9  104.05  4874.5  101.55
  4911.5  102.62  4949.3  102.34  4959.9  100.12  4963.3   93.02  4964.6   92.22
  5019.4   92.22  5047.3    98.5  5054.4  102.32  5061.7  105.88    5078  107.52
  5192.4  106.87  5196.2  106.87    5353  111.09  5496.5  107.65  5751.5  108.02
  5865.1  112.05  6042.8  111.28  6306.8  119.94  6519.7  123.43  6548.5  121.84
#Mann= 8 ,-1 , 0
  4273.5     .12       0  4911.5      .1       0  4949.3     .07       0
  5054.4      .1       0    5078     .12       0  5192.4      .1       0
  5196.2     .12       0  5496.5     .05       0
Bank Sta=4949.3,5054.4
XS Rating Curve= 0 ,0
Exp/Cntr=0.3,0.1

Type RM Length L Ch R = 1 ,7500    ,500,500,500
BEGIN DESCRIPTION:
CRYSTAL CREEK 15.0
END DESCRIPTION:
XS GIS Cut Line= 3
      3858229.64     10079239.83      3857763.83     10079583.38
      3856667.16     10080614.82
#Sta/Elev= 30
  4421.2  131.93    4817  125.68  4881.8  121.89  4903.4  117.73  4917.3  114.91
  4938.1  104.95  4952.7   95.83  4953.3   92.74  4954.6   91.94  5009.4   91.94
    5031   94.84  5037.8   99.02  5080.3  104.95  5101.8  103.03  5158.4  105.29
  5200.5  109.49  5238.7  109.49  5306.9  107.31  5397.6  108.97  5439.2  108.11
  5535.5  104.98  5561.4  103.54  5575.5   106.6  5646.4  109.61    5724  108.29
  5759.7  111.72  5794.8  109.53  5978.9  111.28  6134.3  116.89  6505.5  123.82
#Mann= 8 ,-1 , 0
  4421.2     .12       0  4903.4      .1       0  4938.1     .07       0
  5080.3      .1       0  5238.7     .12       0  5397.6     .05       0
  5439.2     .12       0  5535.5     .05       0
Bank Sta=4938.1,5080.3
XS Rating Curve= 0 ,0
Exp/Cntr=0.3,0.1

Type RM Length L Ch R = 1 ,7000    ,500,500,500
BEGIN DESCRIPTION:
CRYSTAL CREEK 14.0
END DESCRIPTION:
XS GIS Cut Line= 3
      3858068.24     10078857.85      3857400.76     10079244.74
      3856599.44     10080552.34
#Sta/Elev= 30
  4228.5  128.96  4384.7  119.62    4422  115.31  4836.8  107.59  4888.3   104.4
  4910.9  106.14  4925.6  102.64  4957.1    94.9  4986.8    93.1  5041.6    93.1
  5050.9  103.28  5078.1   106.8    5109  103.62  5124.4  107.04  5239.1  106.96
  5264.9  107.51  5319.8  104.55  5429.6  104.61  5457.1  102.08  5631.2  110.48
  5973.5  110.05  6004.3  113.79  6031.6  110.33  6147.6  110.49  6163.1  113.54
  6184.4   111.9  6199.8  115.16  6250.6  115.12  6285.8  118.28  6533.6  124.18
#Mann= 6 ,-1 , 0
  4228.5     .12       0  4836.8      .1       0  4925.6     .07       0
  5050.9      .1       0  5239.1     .12       0  5264.9     .05       0
Bank Sta=4925.6,5050.9
XS Rating Curve= 0 ,0
Exp/Cntr=0.3,0.1

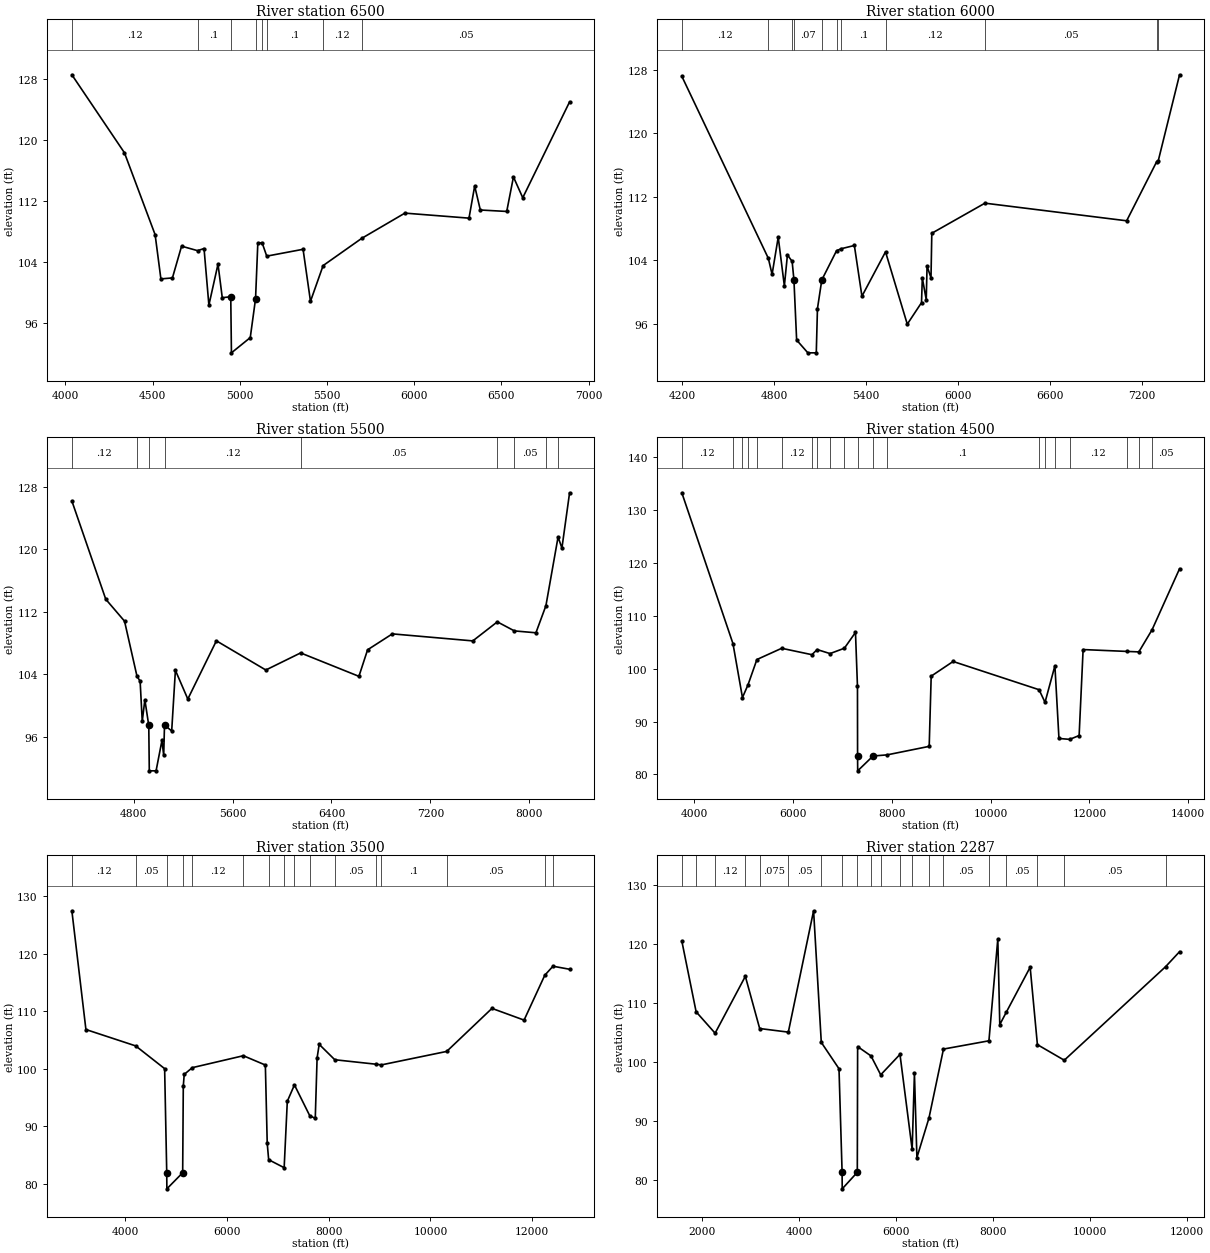
Type RM Length L Ch R = 1 ,6500    ,500,500,500
BEGIN DESCRIPTION:
CRYSTAL CREEK 13.0
END DESCRIPTION:
XS GIS Cut Line= 3
      3858120.28     10078519.33       3857198.5     10078795.26
      3856480.96     10080544.41
#Sta/Elev= 30
  4037.8  128.61  4339.1  118.37    4515  107.61  4548.1   101.8  4614.2  101.93
  4666.6   106.1  4758.4  105.51  4795.4  105.79  4823.2   98.36  4875.4  103.74
  4899.9   99.33  4948.5   99.46  4952.4   92.09  5060.3   94.09  5090.6   99.18
  5103.6  106.48    5128  106.56  5154.8  104.79    5363  105.69  5405.5   98.86
  5477.9  103.55  5698.8  107.12  5946.6  110.44  6314.1  109.78  6346.6     114
    6379  110.85  6530.3  110.66  6568.8  115.19  6622.2  112.46  6890.6  125.05
#Mann= 8 ,-1 , 0
  4037.8     .12       0  4758.4      .1       0  4948.5     .07       0
  5090.6      .1       0    5128     .12       0  5154.8      .1       0
  5477.9     .12       0  5698.8     .05       0
Bank Sta=4948.5,5090.6
XS Rating Curve= 0 ,0
Exp/Cntr=0.3,0.1

Type RM Length L Ch R = 1 ,6000    ,500,500,500
BEGIN DESCRIPTION:
CRYSTAL CREEK 12.0
END DESCRIPTION:
XS GIS Cut Line= 4
      3858165.84     10078280.61       3857365.4     10078330.62
      3857035.66     10078686.64      3856383.99     10080536.76
#Sta/Elev= 30
    4198  127.17  4762.8  104.24  4787.1  102.22  4827.2  106.91  4867.3  100.77
  4887.3  104.67    4918  103.86  4929.7  101.54  4947.4   93.95  5020.7   92.34
  5075.6   92.34  5083.3   97.91  5111.6  101.52  5207.9   105.2  5238.1  105.45
  5324.2  105.86  5373.6   99.47  5527.6  105.06  5669.6   95.95  5762.5   98.66
  5767.8  101.76  5793.4   99.03  5798.7  103.27  5824.4  101.78  5829.7   107.4
  6176.5  111.19  7101.5  108.97  7296.9  116.39  7308.2  116.56  7446.8  127.36
#Mann= 11 ,-1 , 0
    4198     .12       0  4762.8     .05       0    4918      .1       0
  4929.7     .07       0  5111.6      .1       0  5207.9     .12       0
  5238.1      .1       0  5527.6     .12       0  6176.5     .05       0
  7296.9     .12       0  7308.2     .05       0
Bank Sta=4929.7,5111.6
XS Rating Curve= 0 ,0
Exp/Cntr=0.3,0.1

Type RM Length L Ch R = 1 ,5500    ,1000,1000,1000
BEGIN DESCRIPTION:
CRYSTAL CREEK 11.0
END DESCRIPTION:
XS GIS Cut Line= 4
      3858117.81     10078061.06      3857453.96     10077838.73
      3856418.47     10078495.78      3856307.36     10080592.98
#Sta/Elev= 30
  4299.9  126.18  4574.1  113.59    4726  110.78  4826.8  103.72  4852.2  103.08
  4869.3   97.95  4890.4  100.71  4922.1   97.41  4926.3    91.6  4981.2    91.6
  5028.7   95.49  5042.8   93.58 5049.34  97.467  5107.5   96.71  5137.5  104.48
  5237.9   100.8  5469.1  108.26  5869.1  104.52  6150.6  106.71  6622.2  103.71
  6692.3  107.11  6892.6  109.15  7543.5  108.25  7741.9  110.69  7880.2  109.53
  8054.2  109.29    8135  112.76  8233.3  121.56  8264.5  120.15  8326.5  127.23
#Mann= 9 ,-1 , 0
  4299.9     .12       0  4826.8     .05       0  4922.1     .03       0
 5049.34     .12       0  6150.6     .05       0  7741.9      .1       0
  7880.2     .05       0    8135     .12       0  8233.3     .05       0
Bank Sta=4922.1,5049.34
XS Rating Curve= 0 ,0
Exp/Cntr=0.3,0.1

Type RM Length L Ch R = 1 ,4500    ,1000,1000,1000
BEGIN DESCRIPTION:
CRYSTAL CREEK 9.0
END DESCRIPTION:
XS GIS Cut Line= 3
      3858404.61     10077599.96      3857361.16     10076905.35
      3848611.82     10078053.87
#Sta/Elev= 30
  3746.5  133.17    4782   104.7    4974   94.52  5086.3   96.92  5266.6   101.7
  5768.6  103.82  6380.6  102.61  6486.5  103.58  6747.2  102.82  7037.4  103.83
  7262.6  106.81  7302.9   96.61    7305   83.49  7307.3   80.69  7618.4   83.49
    7901    83.7  8755.3   85.31  8795.6   98.56  9239.4  101.33 10979.7      96
 11100.7   93.62 11300.6  100.52 11382.6    86.8 11600.6   86.63 11791.1   87.35
 11871.8  103.58 12753.7  103.23 13000.5  103.14 13268.8  107.33 13824.4  118.83
#Mann= 20 ,-1 , 0
  3746.5     .12       0    4782     .05       0    4974      .1       0
  5086.3     .12       0  5266.6     .05       0  5768.6     .12       0
  6380.6     .12       0  6486.5      .1       0  6747.2     .12       0
  7037.4     .05       0    7305     .03       0  7618.4     .05       0
    7901      .1       0 10979.7      .1       0 11100.7     .12       0
 11300.6     .05       0 11600.6     .12       0 12753.7      .1       0
 13000.5     .12       0 13268.8     .05       0
Bank Sta=7305,7618.4
XS Rating Curve= 0 ,0
Exp/Cntr=0.3,0.1

Type RM Length L Ch R = 1 ,3500    ,1213,1213,1213
BEGIN DESCRIPTION:
CRYSTAL CREEK 7.0
END DESCRIPTION:
XS GIS Cut Line= 3
      3858694.86      10077354.9      3857211.52     10075932.96
      3849687.12     10074130.41
#Sta/Elev= 30
  2945.2  127.49  3221.6  106.82  4200.7  103.97  4770.4  100.01  4811.8   81.89
  4814.1   79.09  5125.2   81.89  5137.5   96.97  5155.6   99.01  5313.8  100.18
  6318.9  102.26  6751.9  100.64  6788.7   87.01  6817.1   84.16  7121.8   82.77
  7183.8   94.33  7324.1   97.18  7625.7   91.81  7733.8   91.36  7769.9  101.87
    7811  104.24  8118.2  101.56  8932.4  100.78  9032.9  100.66 10319.8  103.01
 11210.1   110.5 11841.9  108.46 12249.5  116.27 12410.6  117.84 12737.3  117.31
#Mann= 16 ,-1 , 0
  2945.2     .12       0  4200.7     .05       0  4811.8     .03       0
  5125.2    .075       0  5313.8     .12       0  6318.9      .1       0
  6817.1     .05       0  7121.8      .1       0  7324.1     .05       0
  7625.7      .1       0  8118.2     .05       0  8932.4     .12       0
  9032.9      .1       0 10319.8     .05       0 12249.5    .075       0
 12410.6     .05       0
Bank Sta=4811.8,5125.2
XS Rating Curve= 0 ,0
Exp/Cntr=0.3,0.1

Type RM Length L Ch R = 1 ,2287    ,784,784,784
BEGIN DESCRIPTION:
CRYSTAL CREEK 5.0
END DESCRIPTION:
XS GIS Cut Line= 4
      3859043.22      10077246.9       3857003.3      10075285.1
      3856419.85     10075194.01      3849694.03      10073942.9
#Sta/Elev= 30
  1579.3  120.47  1874.1  108.49  2265.4  104.87  2888.8   114.5  3184.3  105.66
  3775.1  105.05  4295.9   125.6  4454.8  103.31  4819.8   98.85  4883.8   81.31
  4886.1   78.51  5197.2   81.31  5203.9   102.6  5479.3  101.02  5679.8   97.82
  6077.1  101.28  6328.2    85.2  6375.2   98.06  6426.1    83.8  6674.9   90.51
  6973.8  102.18    7911  103.58  8094.2  120.84  8134.9  106.33    8269  108.42
  8761.1  116.04  8910.5  102.93  9464.5  100.29 11553.3  116.13 11841.2  118.67
#Mann= 20 ,-1 , 0
  1579.3     .12       0  1874.1     .05       0  2265.4     .12       0
  2888.8     .05       0  3184.3    .075       0  3775.1     .05       0
  4454.8     .05       0  4883.8     .03       0  5197.2     .05       0
  5479.3    .075       0  5679.8    .075       0  6077.1     .05       0
  6328.2      .1       0  6674.9     .12       0  6973.8     .05       0
    7911    .075       0    8269     .05       0  8910.5      .1       0
  9464.5     .05       0 11553.3     .05       0
Bank Sta=4883.8,5197.2
XS Rating Curve= 0 ,0
Exp/Cntr=0.3,0.1

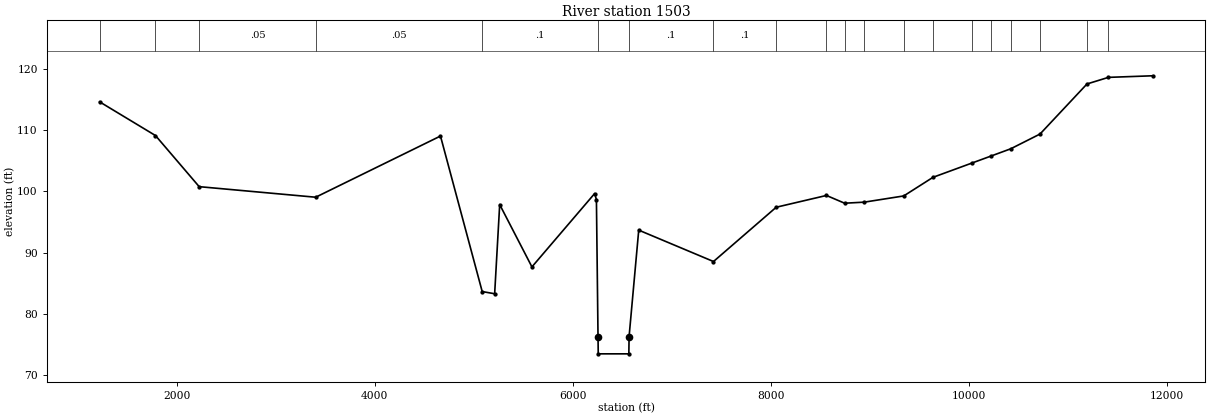
Type RM Length L Ch R = 1 ,1503    ,1003,1003,1003
BEGIN DESCRIPTION:
CRYSTAL CREEK 3.0
END DESCRIPTION:
XS GIS Cut Line= 4
      3859268.92     10077055.94      3856617.86      10074484.7
      3854048.22     10074005.41      3849735.69     10073672.07
#Sta/Elev= 30
  1222.5  114.68  1786.4  109.16  2227.5  100.79  3403.7   99.06  4663.7  109.08
  5084.9   83.61  5210.7   83.25  5261.5   97.86    5587   87.65    6220   99.66
  6238.1   98.67  6254.3   76.21  6256.5   73.41  6565.5   73.41  6567.8   76.21
  6665.3   93.67  7420.1   88.53  8053.4   97.42  8560.4   99.35  8743.9   98.08
  8941.2   98.25  9340.7   99.27  9636.2  102.32 10026.3  104.64   10218  105.78
 10420.9  106.99 10716.9  109.41   11191  117.61 11407.4  118.69   11855  118.95
#Mann= 20 ,-1 , 0
  1222.5     .12       0  1786.4    .075       0  2227.5     .05       0
  3403.7     .05       0  5084.9      .1       0  6254.3     .03       0
  6565.5      .1       0  7420.1      .1       0  8053.4     .05       0
  8560.4    .075       0  8743.9     .05       0  8941.2    .075       0
  9340.7     .05       0  9636.2      .1       0 10026.3     .05       0
   10218    .075       0 10420.9     .12       0 10716.9    .075       0
   11191    .075       0 11407.4     .05       0
Bank Sta=6254.3,6567.8
XS Rating Curve= 0 ,0
Exp/Cntr=0.3,0.1