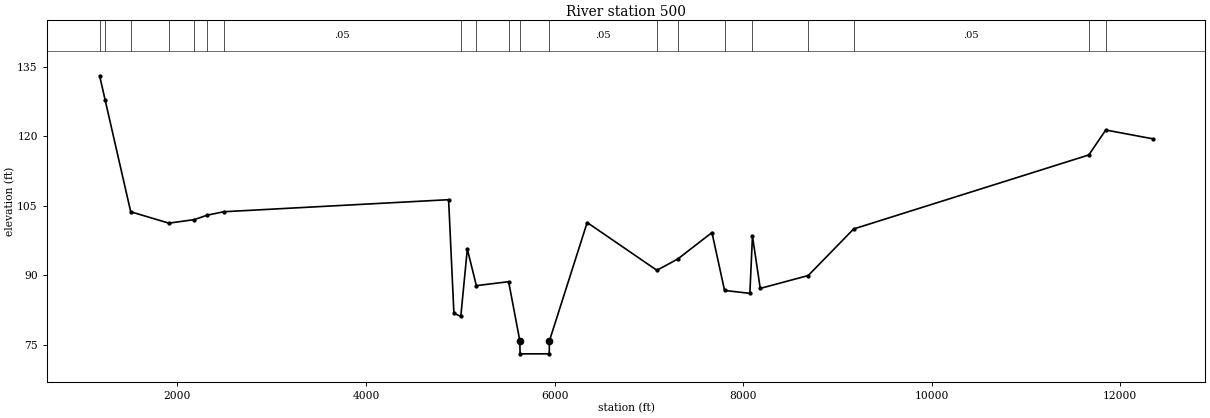
HEC-RAS study CRYSTAL CREEK.prj: CRYSTAL CREEK Base Level Engineering

--- CRYSTAL CREEK.g10 (geometry) --- (continued)

Type RM Length L Ch R = 1 ,500     ,0,0,0
BEGIN DESCRIPTION:
CRYSTAL CREEK 1.0
END DESCRIPTION:
XS GIS Cut Line= 4
       3859513.1     10076829.13      3856993.52     10073950.03
      3854235.72     10073442.91      3849694.01     10073422.07
#Sta/Elev= 30
  1174.1  133.08  1232.9   127.8  1503.8  103.71  1908.8  101.25  2179.2  102.02
  2314.4  102.97  2491.4  103.72    4876  106.32  4932.2   81.81  5005.4   81.11
  5074.5   95.66  5170.4   87.76  5512.7   88.61  5631.8   75.83  5634.1   73.03
  5943.3   73.03  5945.5   75.83  6345.9  101.39  7085.6   91.07  7305.4   93.49
  7669.7   99.22  7803.4   86.72  8071.9   86.09  8099.3   98.46  8181.9   87.16
  8691.1   89.94  9172.8     100 11667.5  115.98 11847.1  121.37 12345.8  119.47
#Mann= 20 ,-1 , 0
  1174.1    .075       0  1232.9     .05       0  1503.8      .1       0
  1908.8     .05       0  2179.2      .1       0  2314.4     .12       0
  2491.4     .05       0  5005.4      .1       0  5170.4     .12       0
  5512.7      .1       0  5634.1     .03       0  5943.3     .05       0
  7085.6     .05       0  7305.4      .1       0  7803.4     .05       0
  8099.3      .1       0  8691.1     .05       0  9172.8     .05       0
 11667.5    .075       0 11847.1     .05       0
Bank Sta=5631.8,5945.5
XS Rating Curve= 0 ,0
Exp/Cntr=0.3,0.1