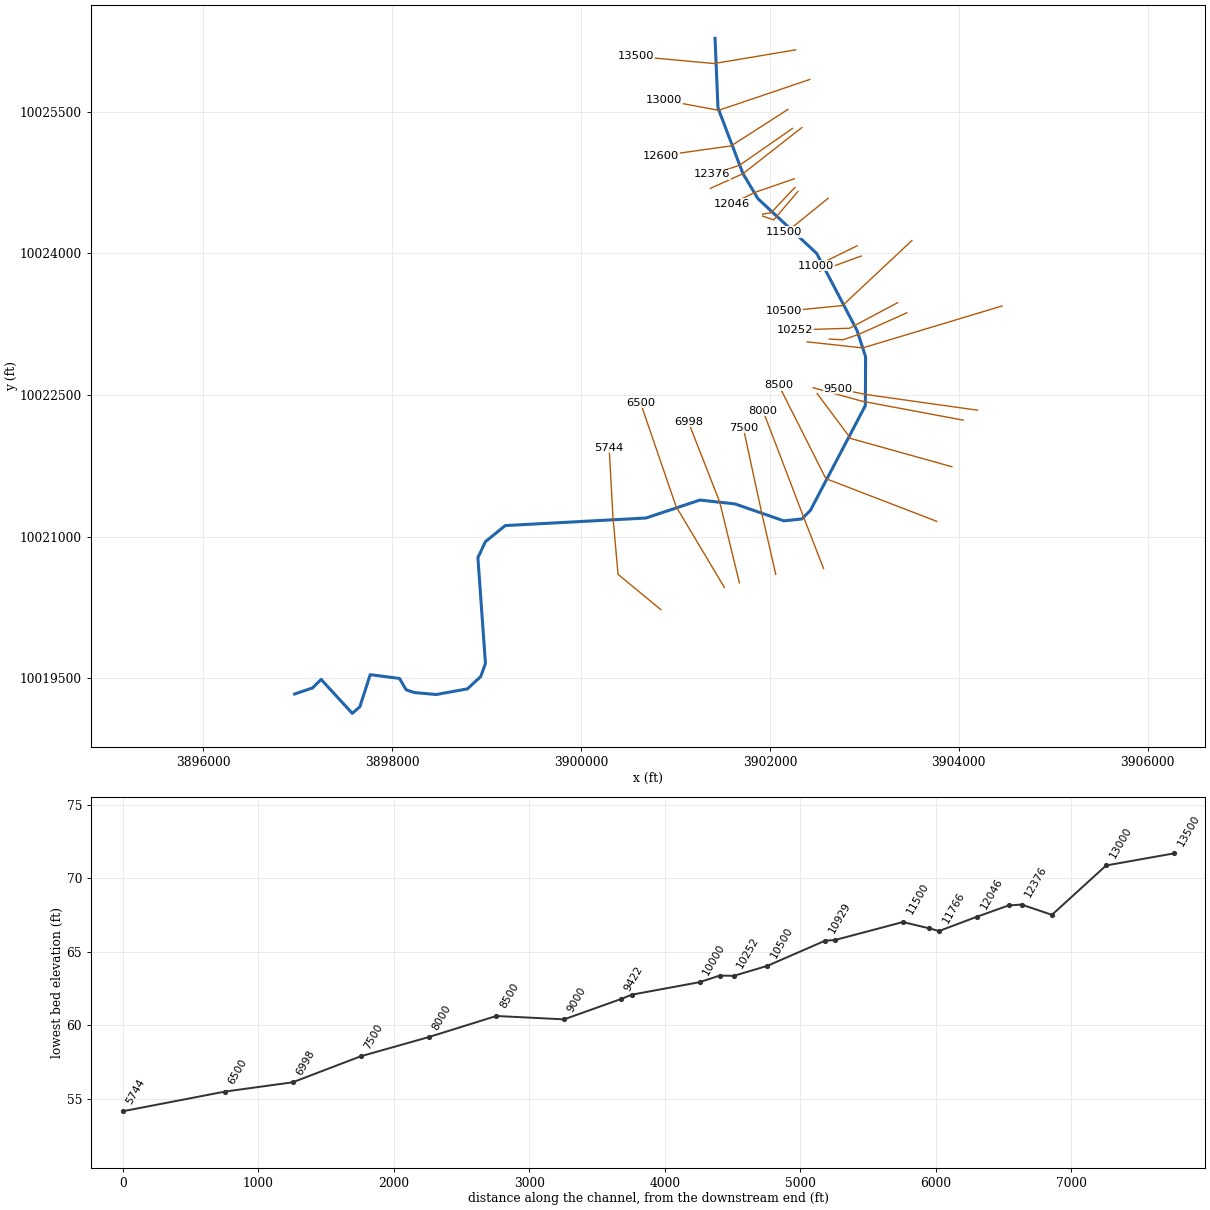
--- Crystal Creek 001.prj (project) ---

Proj Title=Crystal Creek 001 Base Level Engineering
Current Plan=p01
Default Exp/Contr=0.3,0.1
English Units
Geom File=g01
Flow File=f01
Flow File=f02
Plan File=p01
Y Axis Title=Elevation
X Axis Title(PF)=Main Channel Distance
X Axis Title(XS)=Station
BEGIN DESCRIPTION:
Crystal Creek 001
END DESCRIPTION:
DSS File=dss
DSS Export Rating Curves= 0
DSS Export Rating Curve Sorted= 0
DSS Export Volume Flow Curves= 0
DXF OffsetX= 0
DXF OffsetY= 0
DXF ScaleX= 1
DXF ScaleY= 10

--- Crystal Creek 001.p01 (plan) ---

Plan Title=Multiple Run
Program Version=4.10
Short Identifier=Multiple Run
Geom File=g01
Flow File=f01
Subcritical Flow
K Sum by GR= 0
Std Step Tol= 0.01
Critical Tol= 0.01
Num of Std Step Trials= 20
Max Error Tol= 0.3
Flow Tol Ratio= 0.001
Split Flow NTrial= 30
Split Flow Tol= 0.02
Split Flow Ratio= 0.02
Log Output Level= 0
Friction Slope Method= 1
Unsteady Friction Slope Method= 2
Unsteady Bridges Friction Slope Method= 1
Parabolic Critical Depth
Global Vel Dist= 1 , 1 , 1
Global Log Level= 0
CheckData=True
Encroach Param=-1 ,0,0, 0
BEGIN DESCRIPTION:
Multiple Run
END DESCRIPTION:
Computation Interval=1HOUR
Output Interval=1HOUR
Run HTab= 0
Run UNet= 0
Run PostProcess= 0
Run WQNet= 0
UNET Theta= 1
UNET Theta Warmup= 1
UNET ZTol= 0.02
UNET ZSATol= 0.05
UNET MxIter= 20
UNET MaxInSteps= 0
UNET DtIC= 0
UNET DtMin= 0
UNET MaxCRTS= 20
UNET WFStab= 2
UNET SFStab= 1
UNET WFX= 1
UNET SFX= 1
UNET DSS MLevel= 4
UNET DZMax Abort= 100
UNET Convert EG Bridges= 0
UNET Use Existing IB Tables=-1
UNET Froude Reduction=False
UNET Froude Limit= 1
UNET Froude Power= 10
UNET Time Slicing=0,0, 5
UNET Junction Losses=0
Instantaneous Interval=1HOUR
DSS File=dss
Write IC File= 0
Write IC File at Sim End=0
Echo Input=False
Echo Parameters=False
Echo Output=False
Write Detailed= 0
WQ AD Non Conservative
WQ ULTIMATE=-1
WQ Max Comp Step=1HOUR
WQ Output Interval=15MIN
WQ Output Selected Increments= 0
WQ Output face flow=0
WQ Output face velocity=0
WQ Output face area=0
WQ Output face dispersion=0
WQ Output cell volume=0
WQ Output cell surface area=0
WQ Output cell continuity=0
WQ Output cumulative cell continuity=0
WQ Output face conc=0
WQ Output face dconc_dx=0
WQ Output face courant=0
WQ Output face peclet=0
WQ Output face adv mass=0
WQ Output face disp mass=0
WQ Output cell mass=0
WQ Output cell source sink temp=0
WQ Output cell source sink nsm=0
WQ Output MaxMinRange=-1
WQ Daily Max Min Mean=-1
WQ Daily Range=0
WQ Daily Time=0
WQ Create Restart=0
WQ Fixed Restart=0
WQ System Summary=0
WQ Use Fixed Temperature=0
Sorting and Armoring Iterations= 10
XS Update Threshold= 0.02
Hydraulics Update Threshold= 0.02
Energy Slope Method= 1
Volume Change Method= 0
XS Weighting Method= 0
Number of US Weighted Cross Sections= 1
Number of DS Weighted Cross Sections= 1
Upstream XS Weight=0.25
Main XS Weight=0.5
Downstream XS Weight=0.25
Number of DS XS's Weighted with US Boundary= 1
Upstream Boundary Weight= 1
Weight of XSs Associated with US Boundary= 0
Number of US XS's Weighted with DS Boundary= 1
Downstream Boundary Weight= 0.5
Weight of XSs Associated with DS Boundary= 0.5
Sediment Output Level= 4
Mass or Volume Output= 0
Output Increment Type= 1
Profile and TS Output Increment= 10
XS Output Flag= 0
XS Output Increment= 10
Disregard all LS=0
Disregard all Conn=0
Disregard all Breaches=0
Disregard all Pumps=0

--- Crystal Creek 001.f01 (steady flow) ---

Flow Title=Multiple
Program Version=4.10
Number of Profiles= 7
Profile Names=10-year,25-year,50-year,1pct_min,100-year,1pct_plu,500-year
River Rch & RM=Crystal Creek 00,Reach-1         ,13500
     567     734     964     416    1255    3790    2196
River Rch & RM=Crystal Creek 00,Reach-1         ,5744
     667     870    1144     495    1494    4512    2625
Boundary for River Rch & Prof#=Crystal Creek 00,Reach-1         , 1
Up Type= 0
Dn Type= 3
Dn Slope=0.003
Boundary for River Rch & Prof#=Crystal Creek 00,Reach-1         , 2
Up Type= 0
Dn Type= 3
Dn Slope=0.003
Boundary for River Rch & Prof#=Crystal Creek 00,Reach-1         , 3
Up Type= 0
Dn Type= 3
Dn Slope=0.003
Boundary for River Rch & Prof#=Crystal Creek 00,Reach-1         , 4
Up Type= 0
Dn Type= 3
Dn Slope=0.003
Boundary for River Rch & Prof#=Crystal Creek 00,Reach-1         , 5
Up Type= 0
Dn Type= 3
Dn Slope=0.003
Boundary for River Rch & Prof#=Crystal Creek 00,Reach-1         , 6
Up Type= 0
Dn Type= 3
Dn Slope=0.003
Boundary for River Rch & Prof#=Crystal Creek 00,Reach-1         , 7
Up Type= 0
Dn Type= 3
Dn Slope=0.003
DSS Import GetInterval= 0
DSS Import GetPeak= 0
DSS Import FillOption= 0

--- Crystal Creek 001.f02 (steady flow) ---

Flow Title=Orig_BLE_Flow
Program Version=4.10
Number of Profiles= 7
Profile Names=10-year,25-year,50-year,1pct_min,100-year,1pct_plu,500-year
River Rch & RM=Crystal Creek 00,Reach-1         ,13500
     567     720     838     320     965    2916    1277
River Rch & RM=Crystal Creek 00,Reach-1         ,5744
     667     853     995     380    1149    3469    1526
Boundary for River Rch & Prof#=Crystal Creek 00,Reach-1         , 1
Up Type= 0
Dn Type= 3
Dn Slope=0.003
Boundary for River Rch & Prof#=Crystal Creek 00,Reach-1         , 2
Up Type= 0
Dn Type= 3
Dn Slope=0.003
Boundary for River Rch & Prof#=Crystal Creek 00,Reach-1         , 3
Up Type= 0
Dn Type= 3
Dn Slope=0.003
Boundary for River Rch & Prof#=Crystal Creek 00,Reach-1         , 4
Up Type= 0
Dn Type= 3
Dn Slope=0.003
Boundary for River Rch & Prof#=Crystal Creek 00,Reach-1         , 5
Up Type= 0
Dn Type= 3
Dn Slope=0.003
Boundary for River Rch & Prof#=Crystal Creek 00,Reach-1         , 6
Up Type= 0
Dn Type= 3
Dn Slope=0.003
Boundary for River Rch & Prof#=Crystal Creek 00,Reach-1         , 7
Up Type= 0
Dn Type= 3
Dn Slope=0.003
DSS Import GetInterval= 0
DSS Import GetPeak= 0
DSS Import FillOption= 0

--- Crystal Creek 001.g01 (geometry) ---

Geom Title=Existing Conditions
Program Version=4.10

River Reach=Crystal Creek 00,Reach-1
Reach XY= 30
      3901419.17     10026279.36      3901450.15     10025542.84
       3901714.8     10024845.33      3901872.92     10024581.02
       3902494.9     10024000.73      3902923.16     10023182.65
      3903013.02      10022905.7      3903010.54     10022388.19
      3902428.24     10021276.86      3902338.24     10021186.86
      3902148.24     10021166.86      3901628.24     10021346.86
      3901258.24     10021386.86      3900688.24     10021196.86
      3899198.24     10021116.86      3898988.24     10020946.86
      3898908.24     10020776.86      3898988.24     10019656.86
      3898938.24     10019516.86      3898798.24     10019386.86
      3898468.24     10019326.86      3898238.24     10019346.86
      3898148.24     10019376.86      3898078.24     10019496.86
      3897768.24     10019536.86      3897658.24     10019196.86
      3897578.24     10019126.86      3897248.24     10019486.86
      3897158.24     10019396.86      3896968.24     10019332.05

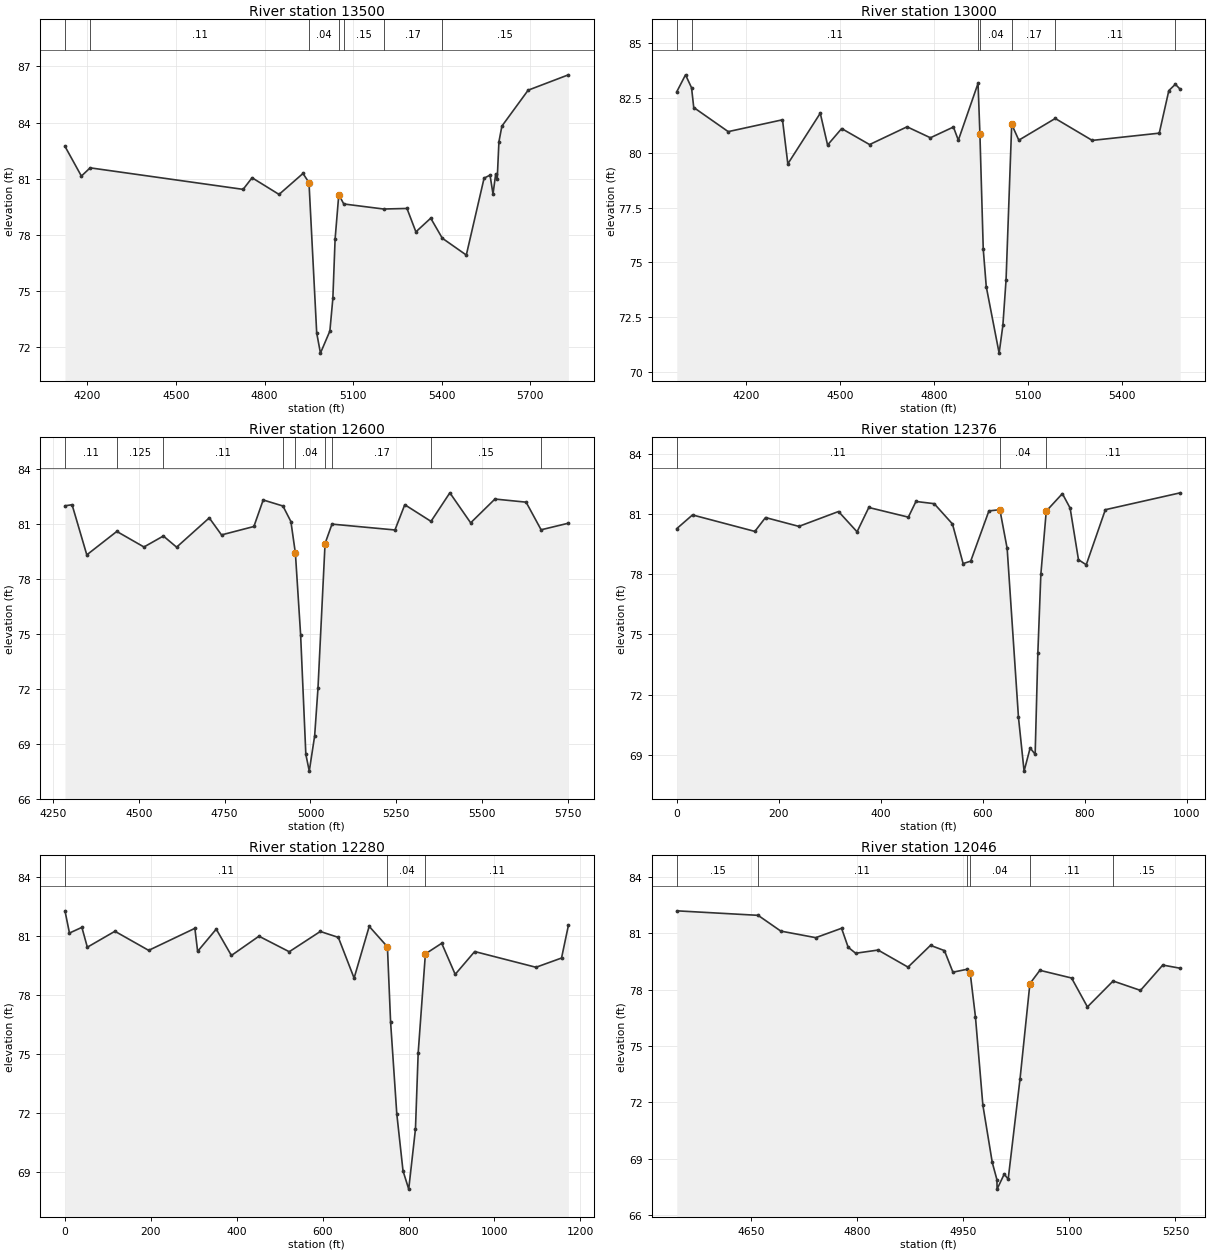
Type RM Length L Ch R = 1 ,13500   ,500,500,500
BEGIN DESCRIPTION:
Crystal Creek 001 27.0
END DESCRIPTION:
XS GIS Cut Line= 3
      3902272.72     10026157.23       3901408.7     10026012.29
      3900583.58     10026088.24
#Sta/Elev= 30
  4123.9   82.73  4179.5   81.14  4209.2   81.58  4727.1   80.43  4757.5   81.05
  4848.8   80.16  4929.9   81.28  4950.2   80.79  4976.3   72.76    4989   71.68
  5020.9   72.86    5031    74.6  5038.6   77.77  5051.1   80.15  5067.9   79.65
  5202.9   79.38    5282   79.41  5312.2   78.16  5362.4   78.89  5401.6   77.82
  5482.9   76.92  5543.1   81.03  5563.2   81.19  5573.3   80.18  5582.5   81.26
  5587.6   80.99  5593.3   82.97  5603.4   83.81  5692.3   85.73  5828.6   86.55
#Mann= 7 ,-1 , 0
  4123.9    .125       0  4209.2     .11       0  4950.2     .04       0
  5051.1     .11       0  5067.9     .15       0  5202.9     .17       0
  5401.6     .15       0
#XS Ineff= 2 , 0
       0                  5051.1       0   80.15
Permanent Ineff=
       F       F
Bank Sta=4950.2,5051.1
XS Rating Curve= 0 ,0
Exp/Cntr=0.3,0.1

Type RM Length L Ch R = 1 ,13000   ,400,400,400
BEGIN DESCRIPTION:
Crystal Creek 001 26.0
END DESCRIPTION:
XS GIS Cut Line= 3
      3902423.06     10025843.67      3901457.17      10025516.8
      3900882.07     10025623.97
#Sta/Elev= 30
  3980.3   82.78  4008.1   83.55  4027.3   82.96  4034.3   82.06  4144.2   80.96
  4317.2    81.5  4334.2   79.49  4437.6    81.8  4460.9   80.35  4505.8    81.1
  4594.8   80.37  4714.2   81.18  4788.7   80.68    4862   81.17  4877.7   80.57
  4940.5   83.16  4946.5   80.83  4957.1    75.6  4966.7   73.89  5007.7   70.86
  5019.6   72.12  5029.8    74.2  5047.8   81.29  5070.5   80.57  5186.6   81.56
  5304.5   80.56  5518.1   80.89  5548.6   82.83  5569.4   83.12    5585   82.89
#Mann= 7 ,-1 , 0
  3980.3    .125       0  4027.3     .11       0  4940.5     .08       0
  4946.5     .04       0  5047.8     .17       0  5186.6     .11       0
  5569.4     .15       0
Bank Sta=4946.5,5047.8
XS Rating Curve= 0 ,0
Exp/Cntr=0.3,0.1

Type RM Length L Ch R = 1 ,12600   ,224,224,224
BEGIN DESCRIPTION:
Crystal Creek 001 25.0
END DESCRIPTION:
XS GIS Cut Line= 3
      3902191.33     10025526.62      3901589.91     10025139.76
      3900845.88     10025035.47
#Sta/Elev= 30
  4284.9      82  4305.6   82.06  4348.5   79.32  4435.9    80.6    4515   79.75
  4571.5   80.35  4610.1   79.74  4705.2   81.34  4740.9   80.41  4835.2   80.87
  4862.3   82.32  4919.8   81.99    4943   81.14  4956.1   79.41  4971.3   74.95
  4986.5   68.42  4996.5    67.5  5012.2   69.43  5021.9   72.04  5042.5   79.94
  5062.7      81  5246.1   80.68  5274.7   82.06  5351.1   81.15    5406   82.71
  5466.6   81.07  5537.3   82.37  5628.1    82.2  5671.8   80.69  5751.3   81.05
#Mann= 9 ,-1 , 0
  4284.9     .11       0  4435.9    .125       0  4571.5     .11       0
  4919.8     .11       0  4956.1     .04       0  5042.5     .11       0
  5062.7     .17       0  5351.1     .15       0  5671.8     .11       0
Bank Sta=4956.1,5042.5
XS Rating Curve= 0 ,0
Exp/Cntr=0.3,0.1

Type RM Length L Ch R = 1 ,12376   ,96,96,96
XS GIS Cut Line= 3
      3902238.28     10025323.59       3901677.1      10024933.7
      3901388.49     10024837.67
#Sta/Elev= 30
       0   80.27    30.8   80.95   153.1   80.13     174   80.82   239.5   80.38
   317.2   81.12   353.6   80.11   376.6   81.32   454.2   80.84   469.1   81.62
   504.9   81.51   540.7    80.5   561.6   78.53   576.5   78.65   612.2   81.15
   633.7   81.21     648   79.28   670.2   70.87   681.2    68.2   693.1   69.35
   702.9   69.04   708.2   74.08   714.1      78   724.7   81.14   756.3   82.01
   771.5   81.29   787.9   78.72   803.1   78.47   840.6   81.21   987.5   82.05
#Mann= 3 , 0 , 0
       0     .11       0   633.7     .04       0   724.7     .11       0
Bank Sta=633.7,724.7
XS Rating Curve= 0 ,0
Exp/Cntr=0.3,0.1

Type RM Length L Ch R = 1 ,12280   ,234,234,234
XS GIS Cut Line= 3
      3902338.84     10025334.32       3901714.8     10024845.33
      3901369.07     10024689.15
#Sta/Elev= 30
       0   82.29    10.5   81.16    39.4   81.45    52.1   80.44   116.3   81.25
   194.9   80.28   302.5    81.4   308.9   80.23   352.2   81.36   387.5   80.02
   451.7      81   522.2   80.21   594.5   81.24   636.5   80.94   673.2   78.87
   708.4    81.5   750.8   80.46   758.2   76.63   772.6   71.97   787.1   69.07
   800.4   68.14   816.1    71.2   822.4   75.06   839.2    80.1   877.2   80.64
   908.6   79.06     954   80.22  1096.7   79.42  1156.2   79.89  1172.2   81.55
#Mann= 3 , 0 , 0
       0     .11       0   750.8     .04       0   839.2     .11       0
Bank Sta=750.8,839.2
XS Rating Curve= 0 ,0
Exp/Cntr=0.3,0.1

Type RM Length L Ch R = 1 ,12046   ,279,279,279
BEGIN DESCRIPTION:
Mapping XS cb780087
END DESCRIPTION:
XS GIS Cut Line= 3
       3902256.8     10024790.79      3901838.97      10024646.5
       3901597.5     10024526.69
#Sta/Elev= 30
  4545.2    82.2  4660.1   81.96  4692.2   81.12  4741.6   80.77  4778.1   81.27
  4787.4   80.26    4798   79.94  4829.7   80.11    4872    79.2  4903.8   80.36
  4923.5   80.08  4935.5   78.93  4954.7   79.08  4959.9   78.89  4967.3   76.56
  4977.8   71.85  4991.1   68.79  4997.7   67.87  4997.9   67.37    5008   68.17
  5013.6    67.9  5030.4   73.26  5044.3   78.32  5058.4   79.03  5103.2   78.62
  5125.6   77.08  5161.9   78.46  5200.6   77.96  5232.1   79.31  5256.8   79.14
#Mann= 6 ,-1 , 0
  4545.2     .15       0  4660.1     .11       0  4954.7     .11       0
  4959.9     .04       0  5044.3     .11       0  5161.9     .15       0
Bank Sta=4959.9,5044.3
XS Rating Curve= 0 ,0
Exp/Cntr=0.3,0.1

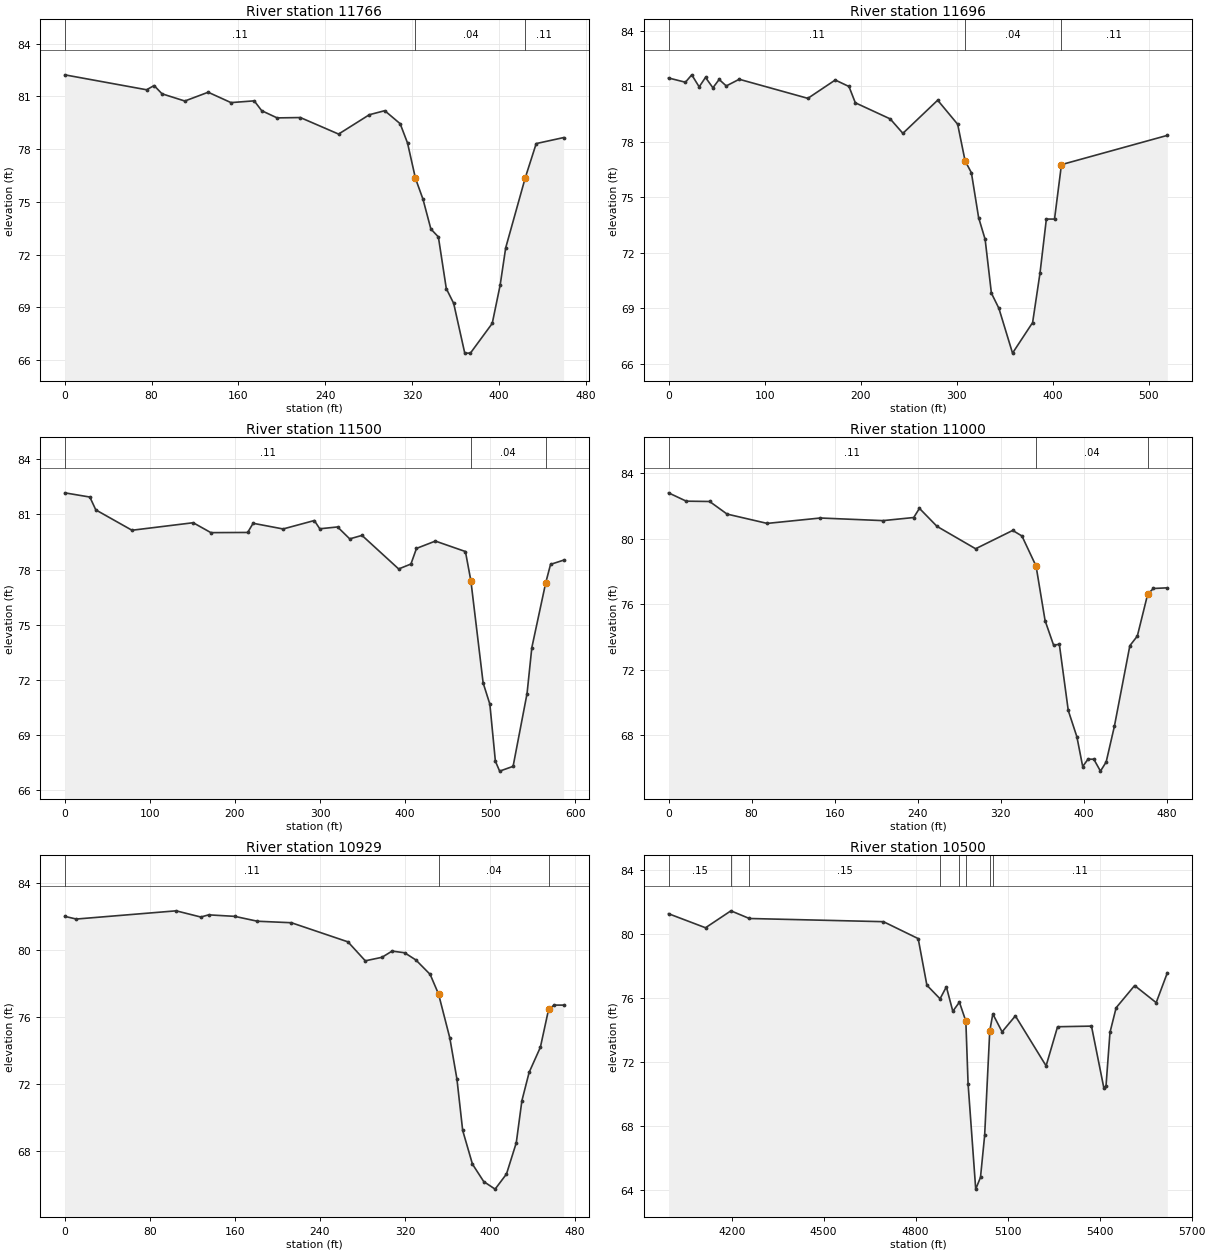
Type RM Length L Ch R = 1 ,11766   ,71,71,71
XS GIS Cut Line= 3
      3902265.28     10024700.22      3902012.44     10024431.83
      3901923.06     10024416.72
#Sta/Elev= 30
       0   82.23    75.4   81.38    82.3   81.62    89.6   81.15   110.6   80.74
   132.1   81.24   153.1   80.65   174.5   80.75   181.4   80.19   195.6   79.78
     217    79.8   252.2   78.86   280.5   79.96   294.7   80.19   308.9   79.45
   315.7   78.35     323   76.34   329.9   75.16   337.2   73.46   344.1   73.01
   351.4   70.07   358.2   69.23   368.4    66.4   373.6    66.4   393.7   68.09
     401   70.27   406.1   72.39   424.1   76.37   434.2   78.32   459.4   78.66
#Mann= 3 , 0 , 0
       0     .11       0     323     .04       0   424.1     .11       0
Bank Sta=323,424.1
XS Rating Curve= 0 ,0
Exp/Cntr=0.3,0.1

Type RM Length L Ch R = 1 ,11696   ,196,196,196
XS GIS Cut Line= 3
      3902296.53     10024656.81      3902039.63      10024354.9
      3901923.27     10024396.75
#Sta/Elev= 30
       0   81.44    17.6   81.21    24.2   81.61    31.9   80.96    38.5   81.47
    46.2   80.91    52.7   81.36    60.1   81.01    73.6   81.37     145   80.34
   173.5   81.33   187.8   80.98   194.4    80.1   230.7   79.23   243.9   78.45
   280.1   80.24   300.9   78.94   308.6   76.97   315.2   76.32   322.7    73.9
   329.5   72.72     336   69.82   343.8      69     358   66.58   378.9   68.23
   386.6   70.91   393.2   73.82   401.7   73.82   408.9   76.76   519.1   78.34
#Mann= 3 , 0 , 0
       0     .11       0   308.6     .04       0   408.9     .11       0
Bank Sta=308.6,408.9
XS Rating Curve= 0 ,0
Exp/Cntr=0.3,0.1

Type RM Length L Ch R = 1 ,11500   ,500,500,500
XS GIS Cut Line= 3
      3902616.23     10024584.22      3902215.54      10024259.8
      3902153.32     10024226.81
#Sta/Elev= 30
       0   82.18    29.5   81.95    36.5   81.25      79   80.14   150.9   80.55
   171.7   80.01   214.9   80.02   221.3   80.52   256.5   80.21   293.2   80.67
   299.6   80.22   320.5   80.32   334.8   79.67   349.2   79.86   392.3   78.03
   406.7    78.3   413.2   79.15   435.4   79.55   470.7   78.98   477.1   77.39
   491.5   71.82   499.4   70.66   505.9   67.55   510.9   67.01   526.7   67.27
   543.1   71.24   548.7   73.74     565   77.27   570.7   78.28     586   78.51
#Mann= 3 , 0 , 0
       0     .11       0   477.1     .04       0     565     .11       0
Bank Sta=477.1,565
XS Rating Curve= 0 ,0
Exp/Cntr=0.3,0.1

Type RM Length L Ch R = 1 ,11000   ,74,74,74
XS GIS Cut Line= 3
      3902923.02     10024081.26      3902558.67     10023901.51
      3902490.67     10023869.37
#Sta/Elev= 30
       0   82.81    17.1    82.3    39.6   82.28    56.4   81.51      95   80.94
   146.2   81.27   206.5   81.11   236.1    81.3   241.6   81.86   258.5   80.76
   295.7   79.39   331.4   80.51   340.3   80.17   353.9   78.33   362.6   74.99
   370.8   73.49   376.3   73.55   384.9    69.5   393.2   67.89   398.8   66.07
   403.9   66.52   409.5   66.52   415.9   65.79   421.4   66.35   429.3   68.53
   444.2   73.46   451.4   74.05   461.4   76.62   466.9   76.96   480.3      77
#Mann= 3 , 0 , 0
       0     .11       0   353.9     .04       0   461.4     .11       0
Bank Sta=353.9,461.4
XS Rating Curve= 0 ,0
Exp/Cntr=0.3,0.1

Type RM Length L Ch R = 1 ,10929   ,426,426,426
XS GIS Cut Line= 2
      3902968.06     10023973.26      3902527.44     10023812.11
#Sta/Elev= 30
       0      82    10.9   81.84   104.8   82.33     128   81.96   135.4   82.09
   159.9      82   181.2   81.71   213.2   81.62   266.4   80.48   282.7   79.35
   298.4   79.56   307.9   79.93   319.7   79.83   330.3    79.4   343.7   78.54
   351.6   77.37   362.2   74.75   368.9    72.3   374.3   69.24   383.5   67.23
   394.1   66.19   404.8   65.74   415.5   66.64   424.7    68.5     430   71.01
   436.8    72.7   447.4    74.2   455.2   76.48   460.5   76.71   469.2   76.71
#Mann= 3 , 0 , 0
       0     .11       0   351.6     .04       0   455.2     .11       0
Bank Sta=351.6,455.2
XS Rating Curve= 0 ,0
Exp/Cntr=0.3,0.1

Type RM Length L Ch R = 1 ,10500   ,248,248,248
BEGIN DESCRIPTION:
Crystal Creek 001 21.0
END DESCRIPTION:
XS GIS Cut Line= 3
      3903502.99     10024136.62      3902769.24      10023448.4
      3902151.65     10023386.27
#Sta/Elev= 30
    3994   81.28  4114.7    80.4  4197.5   81.46  4257.6   80.98  4694.9   80.78
  4808.2   79.72  4836.6    76.8  4879.5   75.95  4900.1    76.7  4921.1   75.17
  4942.6   75.74  4963.6   74.55  4970.9   70.63  4995.8   64.03  5011.4   64.77
  5024.9   67.39  5041.6   73.94  5051.6      75  5081.8   73.88  5125.1   74.88
  5225.3   71.75  5262.7    74.2  5373.3   74.24  5413.5   70.38  5420.7   70.49
  5433.6   73.84  5453.7   75.39    5514   76.78  5584.3   75.71  5620.7   77.58
#Mann= 8 ,-1 , 0
    3994     .15       0  4197.5    .125       0  4257.6     .15       0
  4879.5     .11       0  4942.6     .11       0  4963.6     .04       0
  5041.6     .11       0  5051.6     .11       0
#XS Ineff= 2 , 0
       0                  5051.6       0      75
Permanent Ineff=
       F       F
Bank Sta=4963.6,5041.6
XS Rating Curve= 0 ,0
Exp/Cntr=0.3,0.1

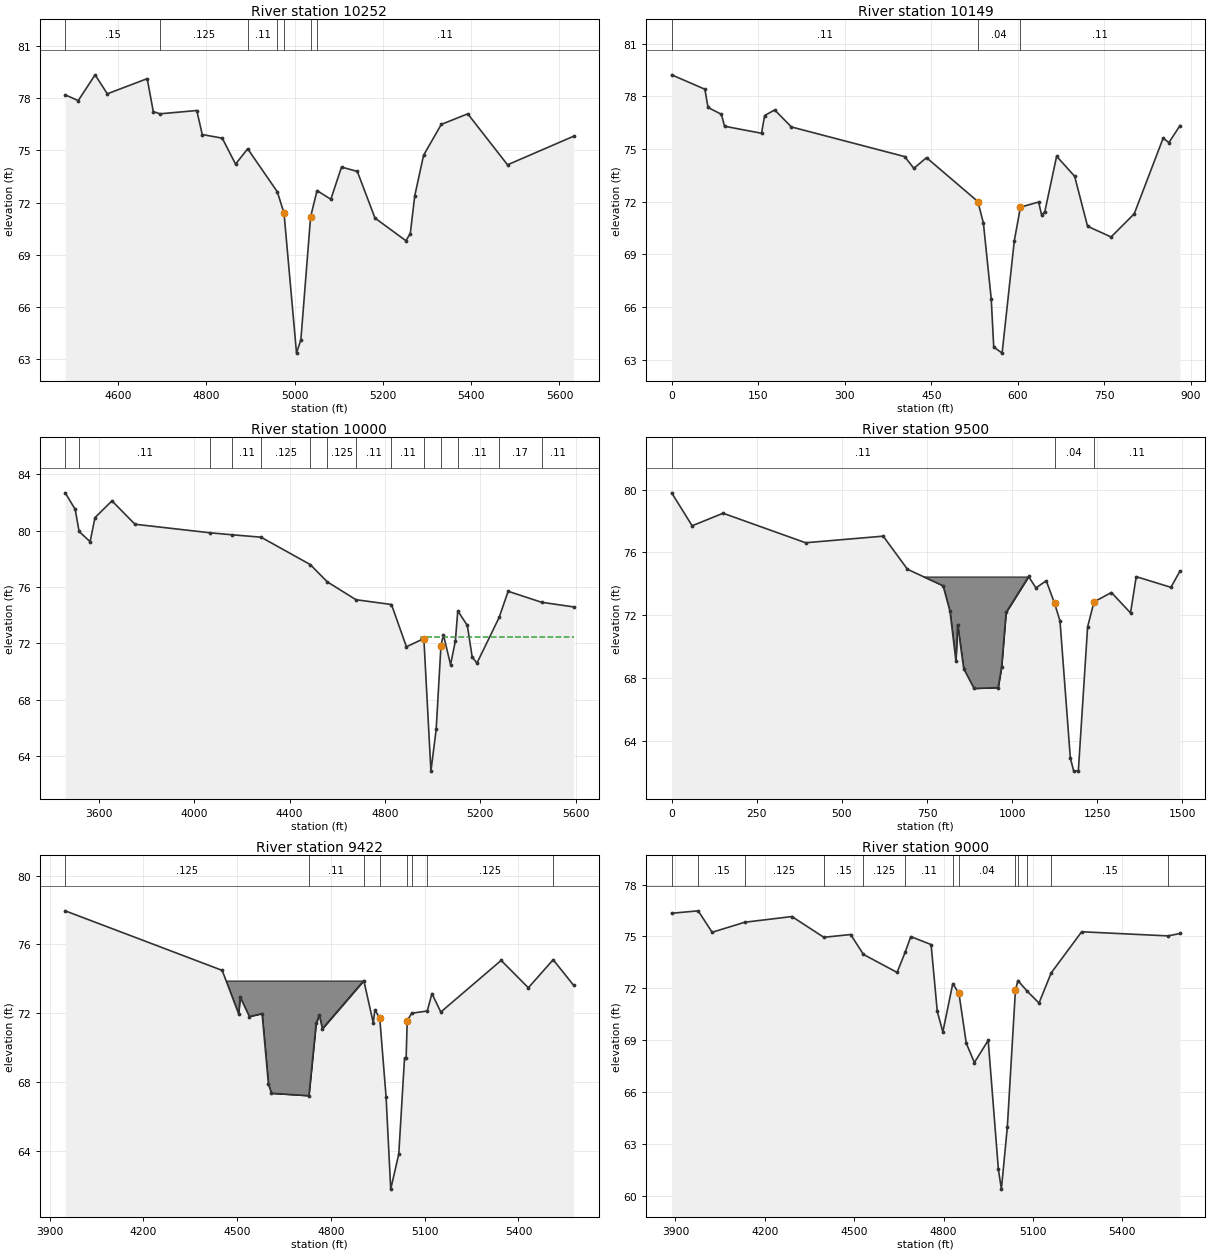
Type RM Length L Ch R = 1 ,10252   ,103,103,103
BEGIN DESCRIPTION:
Mapping XS e8cfc439
END DESCRIPTION:
XS GIS Cut Line= 3
      3903351.69     10023478.45      3902843.92     10023207.64
      3902268.39     10023189.41
#Sta/Elev= 30
  4480.6   78.19  4510.1   77.86  4548.3   79.34    4576   78.25  4666.3   79.12
  4680.1   77.23  4695.3    77.1  4778.6   77.29    4791   75.91  4836.3    75.7
  4866.4   74.21  4893.9   75.09    4961   72.62  4976.2   71.39  5004.5   63.35
  5014.4   64.13  5036.4   71.18    5051   72.69  5082.2   72.19  5106.4   74.04
  5142.2   73.79  5182.2   71.11  5252.2   69.81  5262.2   70.22  5272.3   72.39
  5292.3   74.72  5332.3   76.49  5392.3    77.1  5482.4   74.17  5631.9   75.81
#Mann= 7 ,-1 , 0
  4480.6     .15       0  4695.3    .125       0  4893.9     .11       0
    4961     .11       0  4976.2     .04       0  5036.4     .11       0
    5051     .11       0
#XS Ineff= 2 , 0
       0                    5051       0   72.69
Permanent Ineff=
       F       F
Bank Sta=4976.2,5036.4
XS Rating Curve= 0 ,0
Exp/Cntr=0.3,0.1

Type RM Length L Ch R = 1 ,10149   ,149,149,149
XS GIS Cut Line= 4
       3903450.7      10023371.7      3902940.28     10023142.53
      3902773.61     10023085.24       3902628.7     10023092.87
#Sta/Elev= 30
       0   79.23    57.5   78.41      63   77.37    86.2   76.98    91.6    76.3
   155.7    75.9   161.1   76.91   178.5   77.23   207.5   76.26   403.8   74.57
   419.7    73.9   441.6   74.51   530.6   72.01   540.2   70.78   553.8   66.45
   558.1   63.72   572.6   63.37   593.8   69.78   604.4   71.69   635.9   71.98
   641.1   71.24   646.7   71.44   667.1   74.59   698.3   73.45   720.7    70.6
   761.5   69.99   801.6   71.31   851.7   75.62   861.7   75.37   880.9   76.34
#Mann= 3 , 0 , 0
       0     .11       0   530.6     .04       0   604.4     .11       0
Bank Sta=530.6,604.4
XS Rating Curve= 0 ,0
Exp/Cntr=0.3,0.1

Type RM Length L Ch R = 1 ,10000   ,500,500,500
BEGIN DESCRIPTION:
Crystal Creek 001 20.0
END DESCRIPTION:
XS GIS Cut Line= 3
      3904457.84     10023443.45      3902982.69     10022999.18
      3902395.27     10023063.24
#Sta/Elev= 30
  3459.4   82.68  3501.2   81.51  3517.6   79.94  3563.8   79.21  3584.3   80.92
  3655.5   82.11  3751.8   80.45  4067.9   79.84  4160.1    79.7  4280.6   79.53
  4486.6   77.59  4558.3   76.36  4678.9   75.09  4827.5   74.75  4890.2   71.75
  4963.3   72.33  4992.9   62.92  5014.9   65.88    5035   71.82  5045.1   72.61
  5075.3   70.48  5095.4   72.16  5105.5    74.3  5145.7   73.26  5165.8   71.03
  5185.9   70.59  5278.9   73.83  5316.7   75.69  5456.7   74.91  5590.9   74.58
#Mann= 14 ,-1 , 0
  3459.4    .125       0  3517.6     .11       0  4067.9    .125       0
  4160.1     .11       0  4280.6    .125       0  4486.6     .11       0
  4558.3    .125       0  4678.9     .11       0  4827.5     .11       0
  4963.3     .04       0    5035     .11       0  5105.5     .11       0
  5278.9     .17       0  5456.7     .11       0
#XS Ineff= 3 ,-1
  4952.8  4868.1   72.41  5045.1  5105.5   72.61  5105.5  5316.7    74.3
Permanent Ineff=
       F       F       F
Bank Sta=4963.3,5035
XS Rating Curve= 0 ,0
Exp/Cntr=0.3,0.1

Type RM Length L Ch R = 1 ,9500    ,78,78,78
XS GIS Cut Line= 3
       3904197.4     10022339.28      3903022.98     10022504.74
      3902720.62     10022564.93
#Sta/Elev= 30
       0    79.8    60.1    77.7     151    78.5   393.4   76.62   621.4   77.04
   692.6   74.93   797.3   73.88   817.5   72.25   834.9   69.11     840   71.41
   857.9   68.59   888.2   67.34   958.9   67.39     969   68.68   982.3   72.18
  1048.5   74.47    1070   73.74  1100.3    74.2  1124.7   72.76  1140.7   71.64
    1171   62.91    1181   62.07  1194.6   62.09  1221.8   71.26  1240.6   72.85
  1291.7   73.45  1347.9   72.15  1364.6   74.46  1466.5   73.78  1493.2   74.82
#Mann= 3 , 0 , 0
       0     .11       0  1124.7     .04       0  1240.6     .11       0
#Block Obstruct= 2 , 0
       0  1048.5   74.47               0
Bank Sta=1124.7,1240.6
XS Rating Curve= 0 ,0
Exp/Cntr=0.3,0.1

Type RM Length L Ch R = 1 ,9422    ,422,422,422
BEGIN DESCRIPTION:
Mapping XS c27095f7
END DESCRIPTION:
XS GIS Cut Line= 3
      3904047.03     10022233.68      3902976.74      10022434.2
      3902458.49     10022577.44
#Sta/Elev= 30
  3949.7   77.95    4452   74.49  4504.5   71.97  4509.6   72.94    4539   71.81
  4579.7   71.98    4600   67.88  4609.7   67.35  4729.5   67.21  4752.6   71.41
  4762.8    71.9  4772.6    71.1  4905.2    73.9  4935.4   71.45  4940.5   72.18
  4956.1   71.74  4976.4   67.16  4991.3   61.78  5017.1   63.82  5035.5   69.39
  5040.6   69.39  5044.1   71.56  5058.2      72  5108.2   72.13  5123.2   73.14
  5151.6   72.07  5344.7   75.07  5431.7   73.48  5511.1   75.11  5576.3   73.63
#Mann= 8 ,-1 , 0
  3949.7    .125       0  4729.5     .11       0  4905.2     .11       0
  4956.1     .04       0  5044.1     .11       0  5058.2     .11       0
  5108.2    .125       0  5511.1     .11       0
#Block Obstruct= 2 , 0
       0  4905.2    73.9               0
Bank Sta=4956.1,5044.1
XS Rating Curve= 0 ,0
Exp/Cntr=0.3,0.1

Type RM Length L Ch R = 1 ,9000    ,500,500,500
BEGIN DESCRIPTION:
Crystal Creek 001 18.0
END DESCRIPTION:
XS GIS Cut Line= 3
      3903926.52     10021740.33      3902854.95     10022039.68
      3902500.26     10022515.65
#Sta/Elev= 30
  3887.4   76.34  3976.4   76.48  4023.2   75.24  4132.7   75.82    4291   76.15
  4398.1   74.95  4488.2   75.11    4531   73.96    4644   72.92  4671.7   74.11
    4690   74.99  4758.2   74.53  4778.9   70.66  4797.6   69.48  4830.9   72.27
  4851.6   71.71  4876.3   68.82  4903.5   67.71  4949.8   68.99    4984   61.53
  4994.1   60.39  5014.1   63.99  5041.2   71.89  5049.6   72.45  5080.2   71.84
  5120.4   71.15  5161.2   72.89  5263.6   75.27  5553.5   75.03  5593.6   75.17
#Mann= 13 ,-1 , 0
  3887.4    .125       0  3976.4     .15       0  4132.7    .125       0
  4398.1     .15       0    4531    .125       0  4671.7     .11       0
  4830.9     .11       0  4851.6     .04       0  5041.2     .11       0
  5049.6     .11       0  5080.2    .125       0  5161.2     .15       0
  5553.5     .11       0
#XS Ineff= 2 , 0
       0  4830.9   72.27  5049.6       0   72.45
Permanent Ineff=
       F       F
Bank Sta=4851.6,5041.2
XS Rating Curve= 0 ,0
Exp/Cntr=0.3,0.1

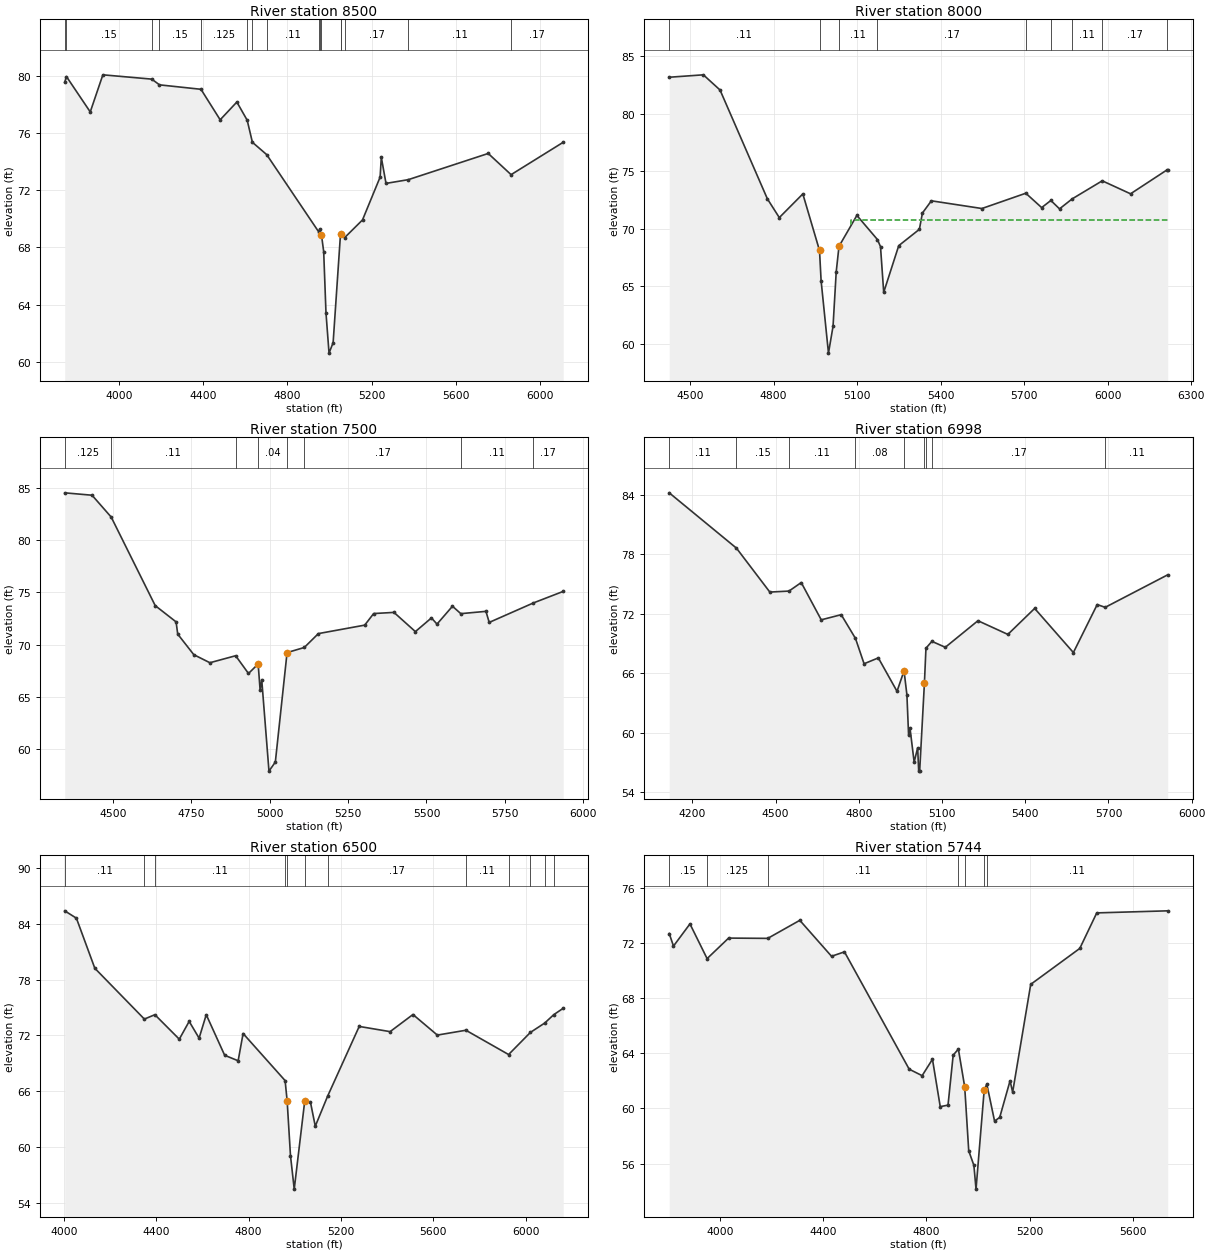
Type RM Length L Ch R = 1 ,8500    ,500,500,500
BEGIN DESCRIPTION:
Crystal Creek 001 17.0
END DESCRIPTION:
XS GIS Cut Line= 3
      3903765.12     10021162.19      3902592.58     10021614.07
      3902093.21     10022604.95
#Sta/Elev= 30
  3743.4   79.53  3751.6   79.93  3864.6   77.46  3924.5   80.05  4156.5   79.75
  4193.3   79.35  4390.2   79.04  4481.3   76.91  4560.5   78.15  4609.6   76.88
  4634.3   75.34  4702.1   74.48  4949.8   69.07  4953.4   69.28  4962.2   68.87
  4972.7   67.71  4983.6   63.43  4998.1   60.62  5017.5   61.35  5052.6   68.94
  5053.4   68.94  5071.9   68.68    5157   69.92  5240.6   72.91  5246.2   74.29
  5268.5   72.47  5374.1   72.73  5753.7   74.56  5862.3   73.08  6109.6   75.34
#Mann= 16 ,-1 , 0
  3743.4    .125       0  3751.6     .15       0  4156.5    .125       0
  4193.3     .15       0  4390.2    .125       0  4609.6     .15       0
  4634.3    .125       0  4702.1     .11       0  4949.8     .17       0
  4953.4     .12       0  4962.2     .04       0  5052.6     .12       0
  5053.4     .11       0  5071.9     .17       0  5374.1     .11       0
  5862.3     .17       0
#XS Ineff= 2 , 0
       0  4953.4   69.28  5052.6       0   68.94
Permanent Ineff=
       F       F
Bank Sta=4962.2,5052.6
XS Rating Curve= 0 ,0
Exp/Cntr=0.3,0.1

Type RM Length L Ch R = 1 ,8000    ,500,500,500
BEGIN DESCRIPTION:
Crystal Creek 001 16.0
END DESCRIPTION:
XS GIS Cut Line= 3
       3902567.2     10020662.17      3902360.03     10021198.66
      3901926.58     10022334.03
#Sta/Elev= 30
  4424.9   83.18  4547.5   83.39  4607.4   82.07  4777.5    72.6  4820.3   70.97
  4904.8   73.03  4964.7   68.11  4970.4   65.49  4996.9   59.18  5013.3   61.51
  5024.7   66.25  5034.7   68.47  5098.9   71.16  5172.8   69.06  5183.8   68.44
  5195.3   64.47  5249.3   68.53  5323.4   69.95  5334.4   71.37  5366.5   72.43
    5548   71.76  5705.7   73.09  5762.6   71.84  5795.7   72.46  5826.8   71.73
  5872.3    72.6  5980.2   74.17  6081.9   73.04  6212.9   75.12  6215.3   75.12
#Mann= 9 ,-1 , 0
  4424.9     .11       0  4964.7     .04       0  5034.7     .11       0
  5172.8     .17       0  5705.7     .11       0  5795.7     .17       0
  5872.3     .11       0  5980.2     .17       0  6212.9     .11       0
#XS Ineff= 2 , 0
       0                  5079.5       0   70.75
Permanent Ineff=
       F       F
Bank Sta=4964.7,5034.7
XS Rating Curve= 0 ,0
Exp/Cntr=0.3,0.1

Type RM Length L Ch R = 1 ,7500    ,502,502,502
BEGIN DESCRIPTION:
Crystal Creek 001 15.0
END DESCRIPTION:
XS GIS Cut Line= 3
      3902061.98      10020599.7      3901916.34     10021236.86
      3901718.23     10022151.76
#Sta/Elev= 30
  4346.4   84.53  4433.6    84.3  4494.6   82.21    4635   73.73  4701.6   72.17
  4706.8      71  4758.1   69.03  4809.4   68.26  4891.5   68.93  4932.5   67.23
  4963.3   68.14  4969.6   65.63  4974.7   66.64  4997.8   57.88  5018.1   58.75
  5055.5   69.23  5110.4   69.72  5155.4   71.05  5303.1   71.86  5331.7   72.97
  5396.4   73.08  5464.7   71.24  5515.9   72.55  5533.7   71.96    5583   73.67
  5609.6   72.96  5689.8   73.18  5700.1   72.12  5841.4   73.99  5936.1   75.09
#Mann= 8 ,-1 , 0
  4346.4    .125       0  4494.6     .11       0  4891.5     .11       0
  4963.3     .04       0  5055.5     .11       0  5110.4     .17       0
  5609.6     .11       0  5841.4     .17       0
#XS Ineff= 2 , 0
       0  4974.7   66.64               0
Permanent Ineff=
       F       F
Bank Sta=4963.3,5055.5
XS Rating Curve= 0 ,0
Exp/Cntr=0.3,0.1

Type RM Length L Ch R = 1 ,6998    ,498,498,498
BEGIN DESCRIPTION:
Crystal Creek 001 14.0
END DESCRIPTION:
XS GIS Cut Line= 3
      3901677.41     10020508.69      3901468.24     10021366.86
      3901135.58     10022217.75
#Sta/Elev= 30
  4116.7   84.18  4359.1    78.6  4479.4   74.17  4548.4   74.27  4592.6   75.13
  4664.7   71.37  4736.7   71.89  4788.2   69.49  4819.1   66.94  4870.5   67.53
  4937.9   64.16  4963.2   66.23  4973.5   63.81  4979.6   59.74  4984.7   60.44
  4999.6   57.02  5012.3   58.47    5016   56.11  5019.5   56.11  5036.7   65.03
  5042.2   68.51  5063.7    69.2  5111.9    68.6  5229.6   71.28  5337.4    69.9
    5434   72.52  5573.6   68.07  5659.5   72.91  5688.3   72.63  5913.6   75.91
#Mann= 9 ,-1 , 0
  4116.7     .11       0  4359.1     .15       0  4548.4     .11       0
  4788.2     .08       0  4963.2     .04       0  5036.7     .08       0
  5042.2     .11       0  5063.7     .17       0  5688.3     .11       0
#XS Ineff= 2 , 0
       0  4963.2   66.23               0
Permanent Ineff=
       F       F
Bank Sta=4963.2,5036.7
XS Rating Curve= 0 ,0
Exp/Cntr=0.3,0.1

Type RM Length L Ch R = 1 ,6500    ,756,756,756
BEGIN DESCRIPTION:
Crystal Creek 001 13.0
END DESCRIPTION:
XS GIS Cut Line= 3
      3901517.84      10020461.1      3901007.47     10021316.86
      3900629.91     10022416.77
#Sta/Elev= 30
  4003.6   85.38  4054.2   84.59    4134   79.21  4348.6   73.75  4394.2   74.22
  4499.9   71.59  4542.7    73.5  4585.7    71.7  4616.7   74.22  4696.5   69.86
  4754.9   69.27  4776.3    72.2  4958.3   67.14  4967.1   64.97  4981.6   59.07
  4997.8   55.48  5043.2   64.92  5067.9   64.85    5089   62.24  5142.3   65.46
  5279.3   72.96  5413.1    72.4  5512.1   74.24  5617.7   72.03  5741.4   72.55
  5926.4   69.94    6021   72.32  6082.7   73.32  6121.9   74.22  6162.9   74.91
#Mann= 12 ,-1 , 0
  4003.6     .11       0  4348.6     .15       0  4394.2     .11       0
  4958.3     .08       0  4967.1     .04       0  5043.2     .08       0
  5142.3     .17       0  5741.4     .11       0  5926.4     .17       0
    6021     .15       0  6082.7     .17       0  6121.9     .11       0
#XS Ineff= 2 , 0
       0                  5043.2       0   64.92
Permanent Ineff=
       F       F
Bank Sta=4967.1,5043.2
XS Rating Curve= 0 ,0
Exp/Cntr=0.3,0.1

Type RM Length L Ch R = 1 ,5744    ,166,166,166
BEGIN DESCRIPTION:
Crystal Creek 001 12.0
END DESCRIPTION:
XS GIS Cut Line= 4
      3900845.75     10020225.64      3900392.24     10020599.78
      3900338.24     10021206.86      3900297.76     10021941.45
#Sta/Elev= 30
  3802.6    72.7  3819.2   71.79    3883    73.4  3949.5   70.88  4032.9   72.37
  4184.7   72.35    4309   73.66    4432   71.05  4482.2   71.37  4733.2   62.85
  4783.4   62.38  4823.5   63.57  4853.6   60.13  4883.8   60.24  4903.8   63.87
  4923.9   64.31  4948.5   61.57  4964.1   56.92  4984.1   55.87  4992.4   54.14
  5024.2   61.36  5034.3   61.76  5064.3   59.08  5084.3   59.35  5124.4   62.01
  5134.4   61.18  5204.5   69.01  5394.8   71.62  5460.6    74.2  5735.7   74.35
#Mann= 7 ,-1 , 0
  3802.6     .15       0  3949.5    .125       0  4184.7     .11       0
  4923.9     .11       0  4948.5     .04       0  5024.2     .11       0
  5034.3     .11       0
#XS Ineff= 3 ,-1
  4923.9  4662.9   64.31  5034.3  5124.4   61.76  5124.4  5144.4   62.01
Permanent Ineff=
       F       F       F
Bank Sta=4948.5,5024.2
XS Rating Curve= 0 ,0
Exp/Cntr=0.3,0.1