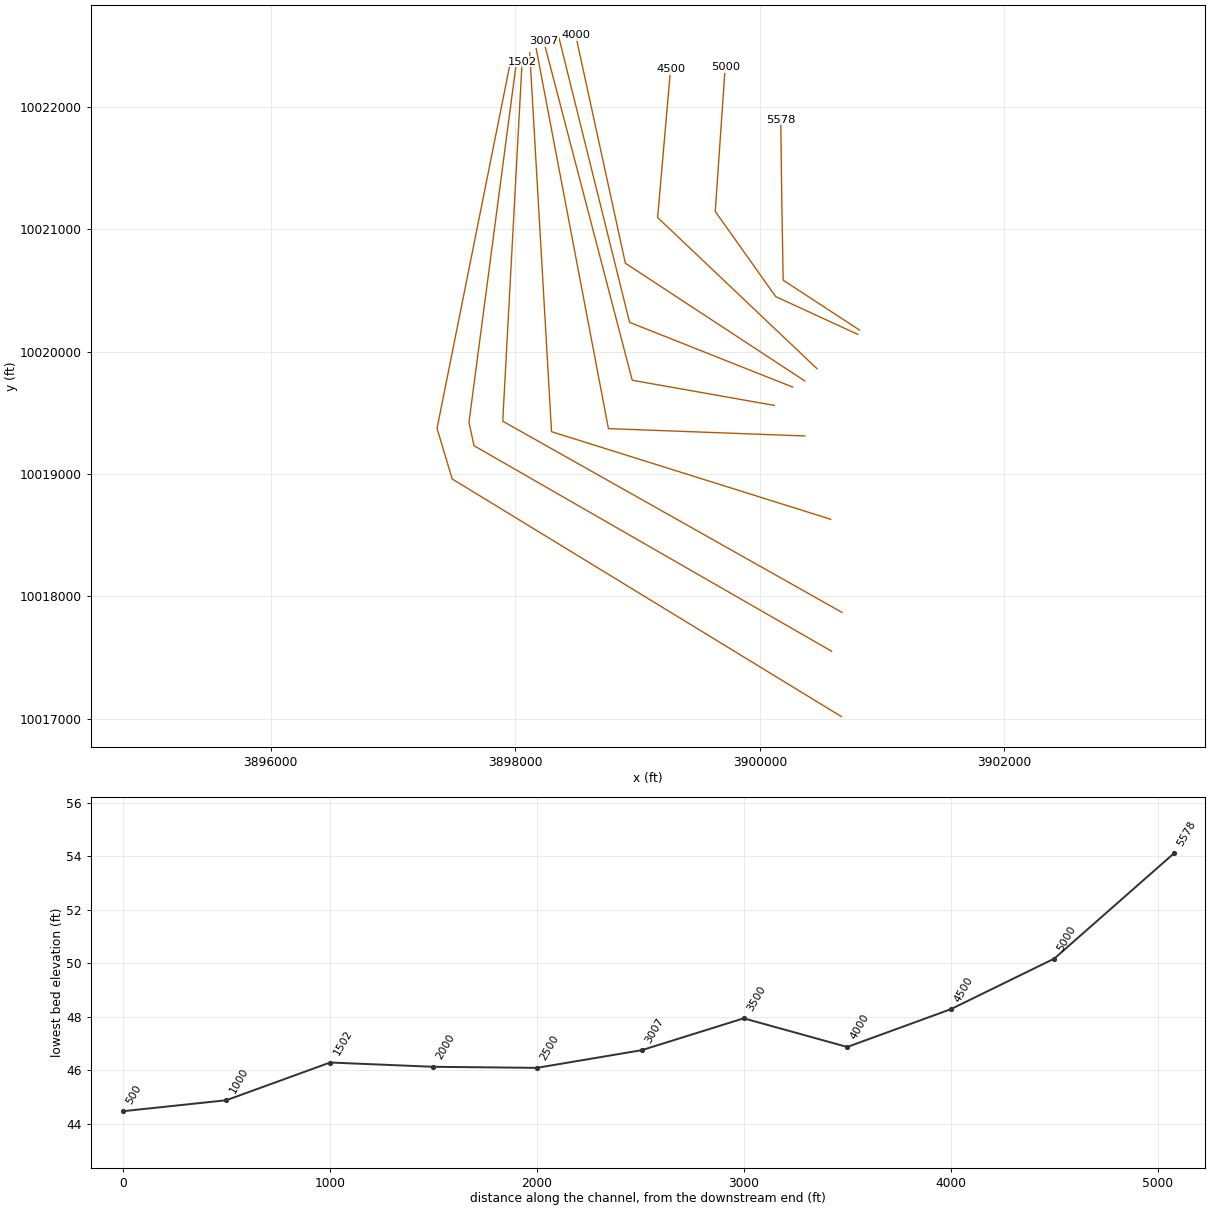
HEC-RAS study Crystal Creek 001.prj: Crystal Creek 001 Base Level Engineering

--- Crystal Creek 001.g01 (geometry) --- (continued)

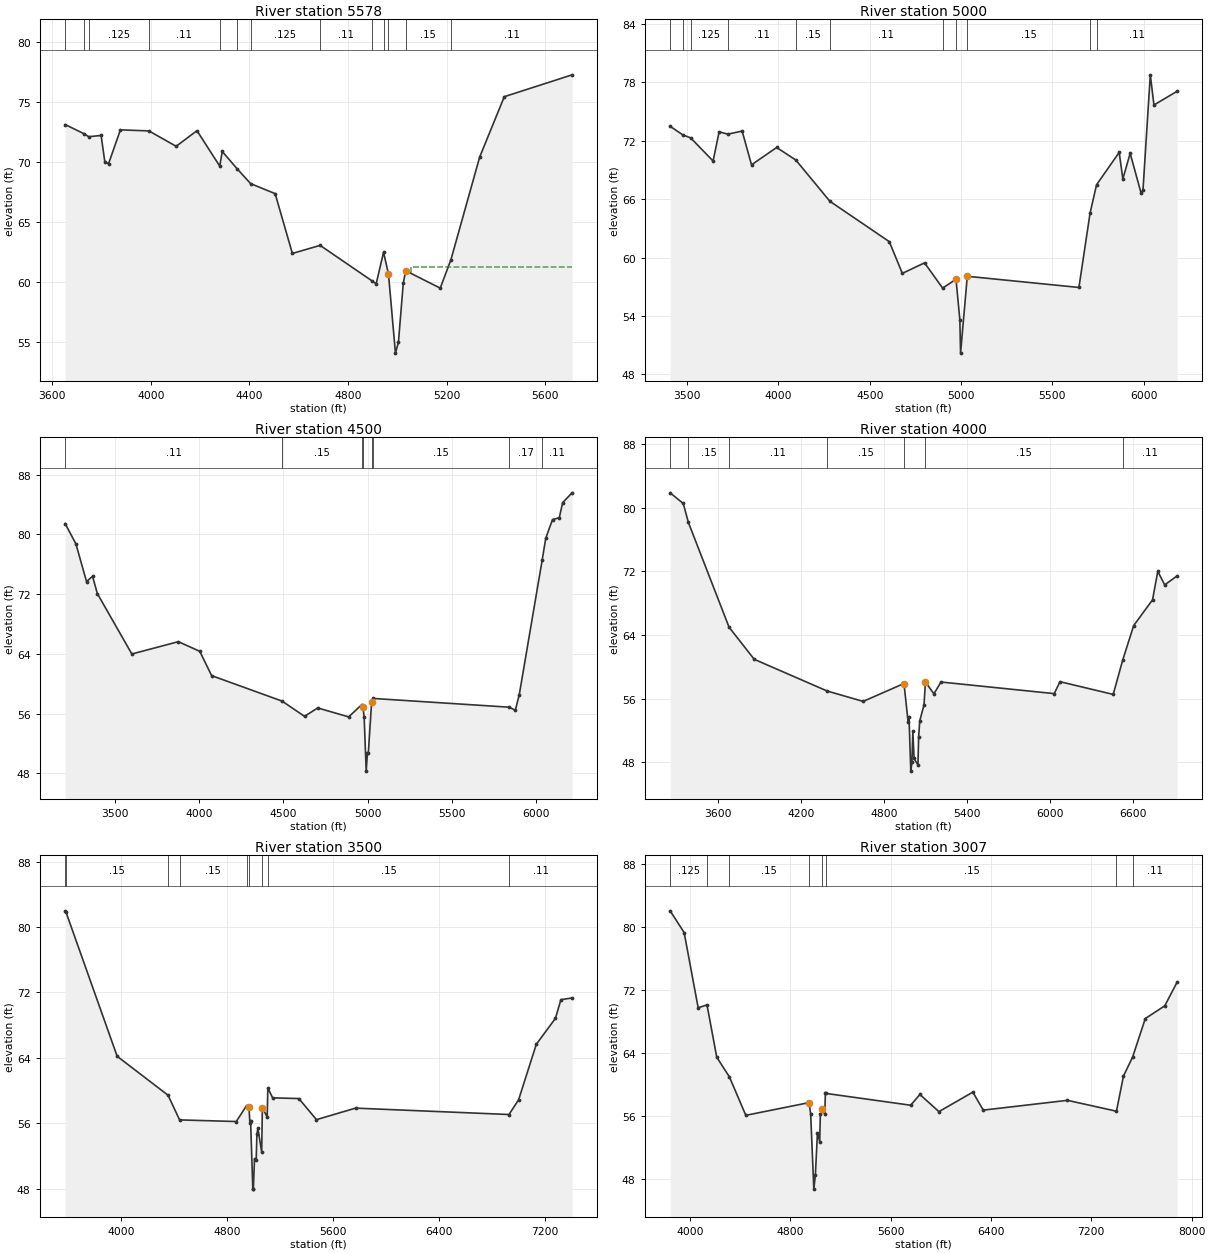
Type RM Length L Ch R = 1 ,5578    ,578,578,578
BEGIN DESCRIPTION:
Crystal Creek 001 11.0
END DESCRIPTION:
XS GIS Cut Line= 4
       3900815.5     10020176.52      3900191.34     10020584.56
       3900180.6     10021186.86      3900171.36      10021896.3
#Sta/Elev= 30
  3651.9   73.13  3730.2   72.35  3747.1   72.12  3797.9   72.22    3813   70.02
  3828.1   69.87  3876.2   72.69    3992    72.6  4102.5   71.32  4186.9   72.62
  4279.4   69.67  4289.5   70.89  4351.1   69.42  4404.7   68.21  4504.1   67.38
  4574.1    62.4  4686.8   63.07  4896.4   60.13  4914.2   59.87  4944.2    62.5
  4964.2   60.68  4992.4    54.1  5004.6   55.01  5024.2   59.93  5034.2   60.96
  5174.2   59.51  5217.8   61.89  5334.2   70.42  5434.2   75.45  5709.5   77.27
#Mann= 13 ,-1 , 0
  3651.9    .125       0  3730.2     .15       0  3747.1    .125       0
    3992     .11       0  4279.4    .125       0  4351.1     .15       0
  4404.7    .125       0  4686.8     .11       0  4896.4     .15       0
  4944.2     .12       0  4964.2     .04       0  5034.2     .15       0
  5217.8     .11       0
#XS Ineff= 2 , 0
       0  4944.2    62.5  5054.2       0   61.28
Permanent Ineff=
       F       F
Bank Sta=4964.2,5034.2
XS Rating Curve= 0 ,0
Exp/Cntr=0.3,0.1

Type RM Length L Ch R = 1 ,5000    ,500,500,500
BEGIN DESCRIPTION:
Crystal Creek 001 10.0
END DESCRIPTION:
XS GIS Cut Line= 4
      3900801.52     10020141.38      3900129.86     10020450.65
      3899635.87     10021146.86      3899717.27     10022327.66
#Sta/Elev= 30
  3406.9   73.49  3476.8    72.6  3519.1    72.3  3642.1   69.92  3675.2   72.92
  3723.5   72.68  3801.2      73  3852.6   69.53  3990.4   71.31  4095.3   70.02
  4281.8   65.78  4607.2   61.63  4678.6   58.37  4800.3   59.45  4899.4   56.85
  4972.6   57.77  4993.5   53.62  4997.6   50.17  5034.3   58.07  5645.7   56.92
  5707.1    64.6  5742.4   67.48  5866.3   70.81  5886.3   68.07  5926.4   70.71
  5986.5    66.6  5996.6   66.94  6036.7   78.78  6056.7   75.68  6183.6   77.09
#Mann= 11 ,-1 , 0
  3406.9    .125       0  3476.8     .11       0  3519.1    .125       0
  3723.5     .11       0  4095.3     .15       0  4281.8     .11       0
  4899.4     .15       0  4972.6     .09       0  5034.3     .15       0
  5707.1     .17       0  5742.4     .11       0
#XS Ineff= 2 , 0
       0  4800.3   59.45               0
Permanent Ineff=
       F       F
Bank Sta=4972.6,5034.3
XS Rating Curve= 0 ,0
Exp/Cntr=0.3,0.1

Type RM Length L Ch R = 1 ,4500    ,500,500,500
BEGIN DESCRIPTION:
Crystal Creek 001 9.0
END DESCRIPTION:
XS GIS Cut Line= 3
      3900467.84     10019861.08      3899164.87     10021096.86
      3899270.23     10022307.08
#Sta/Elev= 30
  3204.2   81.46  3267.9   78.75  3331.4   73.68    3367    74.4  3395.3   72.08
  3600.4   63.98  3876.3   65.63  4003.6   64.34  4074.1   61.08  4492.9   57.66
  4625.8   55.62  4703.9   56.75  4887.6   55.55  4965.6   57.19  4972.5    56.9
  4979.8   55.53  4991.9   48.28  4999.4    50.7  5004.6    50.7  5024.3   57.61
  5034.3   58.02  5840.7   56.85  5877.5   56.44  5900.9   58.53  6037.4   76.63
  6058.2    79.5  6098.3      82  6138.5   82.24  6158.6   84.27  6214.8   85.58
#Mann= 8 ,-1 , 0
  3204.2     .11       0  4492.9     .15       0  4965.6     .12       0
  4972.5     .09       0  5024.3     .12       0  5034.3     .15       0
  5840.7     .17       0  6037.4     .11       0
Bank Sta=4972.5,5024.3
XS Rating Curve= 0 ,0
Exp/Cntr=0.3,0.1

Type RM Length L Ch R = 1 ,4000    ,500,500,500
BEGIN DESCRIPTION:
Crystal Creek 001 8.0
END DESCRIPTION:
XS GIS Cut Line= 3
      3900367.82     10019761.09      3898900.93     10020723.34
      3898494.63     10022587.64
#Sta/Elev= 30
  3254.4   81.88  3349.3   80.54  3386.1   78.16  3680.2   64.97  3861.7   60.94
  4388.3   56.95  4648.4   55.64  4943.7   57.89  4973.9      53  4979.9   53.68
  4992.9   46.87    5001   47.97  5007.6   51.89  5016.6   48.46  5044.5   47.65
  5049.6   51.18  5057.6    53.2  5088.3   55.19  5098.6   58.07  5159.9    56.6
  5211.1   58.08  6028.8   56.62  6070.8   58.12  6455.1   56.52  6523.2   60.81
    6603   65.18  6739.2   68.42    6777      72  6827.1    70.3  6916.8   71.43
#Mann= 7 ,-1 , 0
  3254.4    .125       0  3386.1     .15       0  3680.2     .11       0
  4388.3     .15       0  4943.7     .09       0  5098.6     .15       0
  6523.2     .11       0
#XS Ineff= 2 , 0
       0  4943.7   57.89  5098.6       0   58.07
Permanent Ineff=
       F       F
Bank Sta=4943.7,5098.6
XS Rating Curve= 0 ,0
Exp/Cntr=0.3,0.1

Type RM Length L Ch R = 1 ,3500    ,493,493,493
BEGIN DESCRIPTION:
Crystal Creek 001 7.0
END DESCRIPTION:
XS GIS Cut Line= 3
      3900267.83     10019711.08      3898935.65     10020240.01
      3898358.85     10022563.24
#Sta/Elev= 30
  3580.2   81.99  3586.2   81.85    3973   64.19    4357   59.43  4444.2   56.41
    4872   56.21  4950.3   58.17  4968.1   57.96  4974.6   56.05    4980   56.33
  4996.9   47.94    5001   47.94  5009.7   51.67  5022.5   51.53  5027.6   54.63
  5035.2   55.39  5063.8   52.47    5069   57.92  5105.2   56.76  5110.3   60.32
  5146.5   59.11  5344.3   59.02  5477.4   56.44  5772.1   57.85  6930.8   57.07
  7003.2   58.87  7136.9   65.66  7281.4   68.84  7322.6   71.12  7407.3   71.33
#Mann= 9 ,-1 , 0
  3580.2    .125       0  3586.2     .15       0    4357     .11       0
  4444.2     .15       0  4950.3     .12       0  4968.1     .09       0
    5069     .12       0  5110.3     .15       0  6930.8     .11       0
Bank Sta=4968.1,5069
XS Rating Curve= 0 ,0
Exp/Cntr=0.3,0.1

Type RM Length L Ch R = 1 ,3007    ,507,507,507
BEGIN DESCRIPTION:
Crystal Creek 001 6.0
END DESCRIPTION:
XS GIS Cut Line= 3
      3900117.81     10019561.08      3898957.21     10019766.59
      3898233.99     10022536.68
#Sta/Elev= 30
  3842.7   82.01  3954.4   79.26  4066.1   69.73  4136.5   70.09  4214.4   63.46
  4315.6   60.96  4445.9    56.1  4949.6   57.71  4962.9   56.31  4988.2   46.75
  5000.4   48.52    5017   53.88  5034.9   52.78  5040.1    56.3    5057   56.95
  5075.3   56.26  5080.5   58.99    5088   58.87  5759.8   57.38  5833.8   58.74
  5985.3   56.57  6255.9   59.04  6338.6   56.76  7010.3      58  7400.6   56.62
  7456.6   61.08  7529.6   63.49  7630.5   68.36  7785.5   69.97  7884.3   72.98
#Mann= 8 ,-1 , 0
  3842.7    .125       0  4136.5     .11       0  4315.6     .15       0
  4949.6     .09       0    5057     .12       0    5088     .15       0
  7400.6     .17       0  7529.6     .11       0
Bank Sta=4949.6,5057
XS Rating Curve= 0 ,0
Exp/Cntr=0.3,0.1

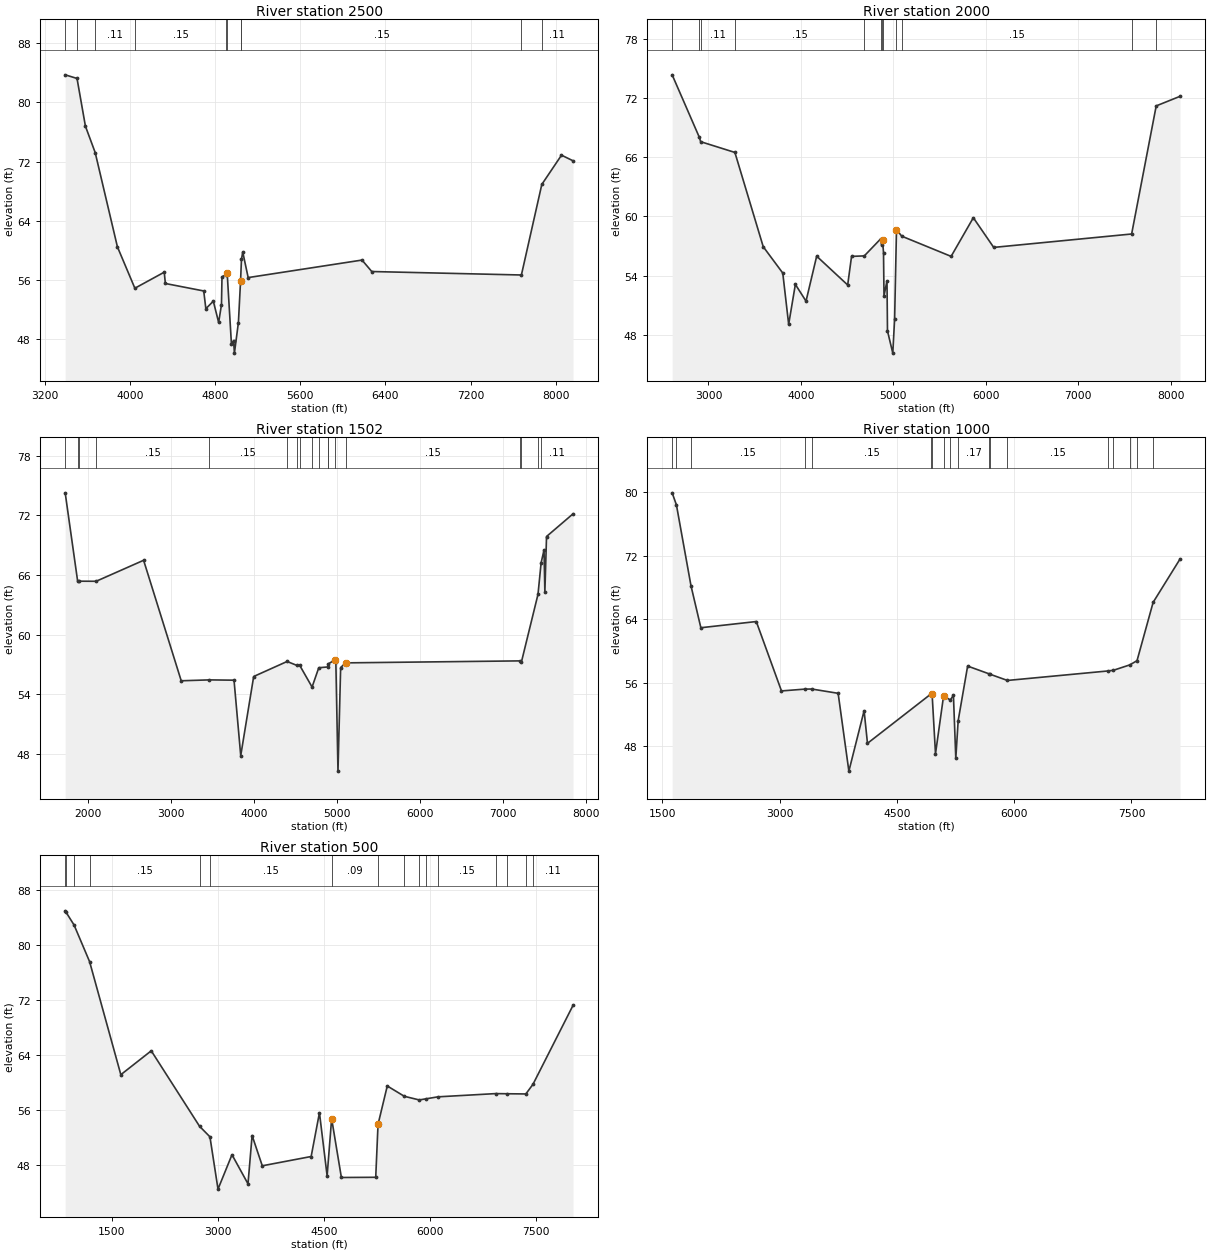
Type RM Length L Ch R = 1 ,2500    ,500,500,500
BEGIN DESCRIPTION:
Crystal Creek 001 5.0
END DESCRIPTION:
XS GIS Cut Line= 3
      3900367.87     10019311.07      3898762.59     10019371.22
      3898171.71     10022478.03
#Sta/Elev= 30
  3393.6   83.74  3504.8   83.25  3583.7   76.79  3675.4   73.22    3884   60.47
  4047.9   54.87  4323.8   57.04  4334.3   55.51  4694.5    54.5  4714.5    52.1
  4784.6   53.12  4834.6   50.24  4861.1   52.63  4866.1   56.41  4904.7   56.72
  4914.7   56.94  4954.7   47.31  4974.7   47.79  4982.7   46.09  5020.2   50.23
  5040.6   55.91  5048.9   58.78  5060.9   59.77  5111.8   56.31  6180.9   58.68
  6272.3   57.13  7677.5   56.66  7869.1   68.91    8054   72.87  8162.5   72.11
#Mann= 10 ,-1 , 0
  3393.6     .11       0  3504.8     .15       0  3675.4     .11       0
  4047.9     .15       0  4904.7     .12       0  4914.7     .09       0
  5040.6     .12       0  5048.9     .15       0  7677.5     .17       0
  7869.1     .11       0
Bank Sta=4914.7,5040.6
XS Rating Curve= 0 ,0
Exp/Cntr=0.3,0.1

Type RM Length L Ch R = 1 ,2000    ,498,498,498
BEGIN DESCRIPTION:
Crystal Creek 001 4.0
END DESCRIPTION:
XS GIS Cut Line= 3
      3900579.72     10018630.12      3898297.51     10019346.02
      3898119.27     10022443.44
#Sta/Elev= 30
  2607.3   74.35  2900.6   68.03  2915.8   67.57    3286   66.48  3592.6   56.92
    3804   54.25  3867.8   49.05  3940.3    53.1  4055.6    51.4  4170.8   55.96
  4506.2   53.04  4548.1   55.94  4686.2   55.99  4861.5    57.7    4873   57.08
  4883.5   57.56  4893.9   56.32  4899.2   51.94  4931.6   53.47  4936.8   48.38
  4994.3   46.13  5014.2   49.63  5034.3   58.66  5090.9   57.99  5625.2   55.94
  5865.6   59.86    6086   56.85  7578.2   58.21  7844.1    71.2  8101.7   72.17
#Mann= 12 ,-1 , 0
  2607.3     .11       0  2900.6     .17       0  2915.8     .11       0
    3286     .15       0  4686.2     .11       0  4861.5     .11       0
    4873     .08       0  4883.5     .06       0  5034.3     .11       0
  5090.9     .15       0  7578.2     .17       0  7844.1     .11       0
Bank Sta=4883.5,5034.3
XS Rating Curve= 0 ,0
Exp/Cntr=0.3,0.1

Type RM Length L Ch R = 1 ,1502    ,502,502,502
BEGIN DESCRIPTION:
Crystal Creek 001 3.0
END DESCRIPTION:
XS GIS Cut Line= 3
      3900671.99     10017868.72      3897898.62     10019431.85
      3898056.77     10022370.55
#Sta/Elev= 30
  1721.3   74.26  1871.8   65.37  1888.7   65.38  2094.6   65.37  2667.3   67.48
    3121   55.37  3459.5   55.46  3758.1   55.43    3839   47.85  3995.1    55.8
  4398.4   57.31  4511.9   56.93    4549   56.94  4699.6   54.74  4780.3   56.68
  4887.4   56.76    4896   57.07  4974.2   57.47  4986.4   57.28  5012.1   46.29
  5044.3    56.7  5104.4   57.17  7207.2   57.37  7223.6   57.21    7425   64.06
  7462.5   67.22  7497.8   68.52  7507.8   64.27  7527.9   69.87  7847.8   72.15
#Mann= 18 ,-1 , 0
  1721.3     .17       0  1871.8     .15       0  1888.7     .11       0
  2094.6     .15       0  3459.5     .15       0  4398.4     .17       0
  4511.9     .15       0    4549     .17       0  4699.6     .11       0
  4780.3     .17       0  4887.4     .11       0    4896     .15       0
  4974.2     .06       0  5104.4     .15       0  7207.2     .11       0
  7223.6     .15       0    7425     .17       0  7462.5     .11       0
#XS Ineff= 2 , 0
       0  4974.2   57.47  5104.4       0   57.17
Permanent Ineff=
       F       F
Bank Sta=4974.2,5104.4
XS Rating Curve= 0 ,0
Exp/Cntr=0.3,0.1

Type RM Length L Ch R = 1 ,1000    ,500,500,500
BEGIN DESCRIPTION:
Crystal Creek 001 2.0
END DESCRIPTION:
XS GIS Cut Line= 4
      3900587.55     10017551.18      3897663.18     10019231.81
      3897622.63     10019423.44      3898004.68     10022323.61
#Sta/Elev= 30
  1627.1   79.93  1681.7   78.41  1868.2   68.21  1994.1   62.94  2702.9   63.72
  3024.9   54.98  3325.2   55.21  3412.1   55.22  3749.5   54.68  3886.8   44.88
  4081.5   52.49  4124.7   48.38  4936.9    54.6  4951.3   54.55  4994.4   47.07
  5097.3   54.32  5184.5   53.85  5223.7   54.44    5254   46.48  5284.3   51.23
  5405.3   58.11  5683.2   57.12  5690.3   57.09  5914.1    56.3  7193.9   57.49
  7269.3   57.58  7478.8   58.26  7571.3   58.79  7777.4   66.14  8121.1   71.59
#Mann= 18 ,-1 , 0
  1627.1     .17       0  1681.7     .11       0  1868.2     .15       0
  3325.2     .11       0  3412.1     .15       0  4936.9     .12       0
  4951.3     .09       0  5097.3     .17       0  5184.5     .15       0
  5284.3     .17       0  5683.2     .15       0  5690.3     .11       0
  5914.1     .15       0  7193.9     .17       0  7269.3     .15       0
  7478.8     .11       0  7571.3     .15       0  7777.4     .11       0
Bank Sta=4951.3,5097.3
XS Rating Curve= 0 ,0
Exp/Cntr=0.3,0.1

Type RM Length L Ch R = 1 ,500     ,0,0,0
BEGIN DESCRIPTION:
Crystal Creek 001 1.0
END DESCRIPTION:
XS GIS Cut Line= 4
      3900666.57     10017017.31      3897485.08     10018959.83
      3897361.55     10019373.55      3897955.04       10022337.
#Sta/Elev= 30
   840.6   84.91   848.4   84.78   966.7   82.84  1185.6   77.53  1627.5    61.1
  2057.6   64.57  2740.8    53.6  2887.6   52.07  3001.6   44.47  3199.3   49.47
  3425.7   45.24  3483.8   52.26  3627.7   47.86  4318.9   49.21  4436.1   55.57
  4544.6    46.4  4608.5   54.71  4746.3   46.16    5232   46.19  5264.5   53.87
  5395.2   59.46  5636.2   57.96  5847.1   57.43    5942   57.59  6110.9   57.88
    6927   58.35  7082.5   58.33  7354.9    58.3    7456   59.71  8022.3   71.18
#Mann= 16 ,-1 , 0
   840.6     .17       0   848.4     .11       0   966.7     .11       0
  1185.6     .15       0  2740.8     .11       0  2887.6     .15       0
  4608.5     .09       0  5264.5     .17       0  5636.2     .15       0
  5847.1     .11       0    5942     .15       0  6110.9     .15       0
    6927     .17       0  7082.5     .15       0  7354.9     .15       0
    7456     .11       0
#XS Ineff= 2 , 0
       0  4608.5   54.71  5264.5       0   53.87
Permanent Ineff=
       F       F
Bank Sta=4608.5,5264.5
XS Rating Curve= 0 ,0
Exp/Cntr=0.3,0.1

Chan Stop Cuts=-1
Use User Specified Reach Order=0
Composite Channel Slope=5