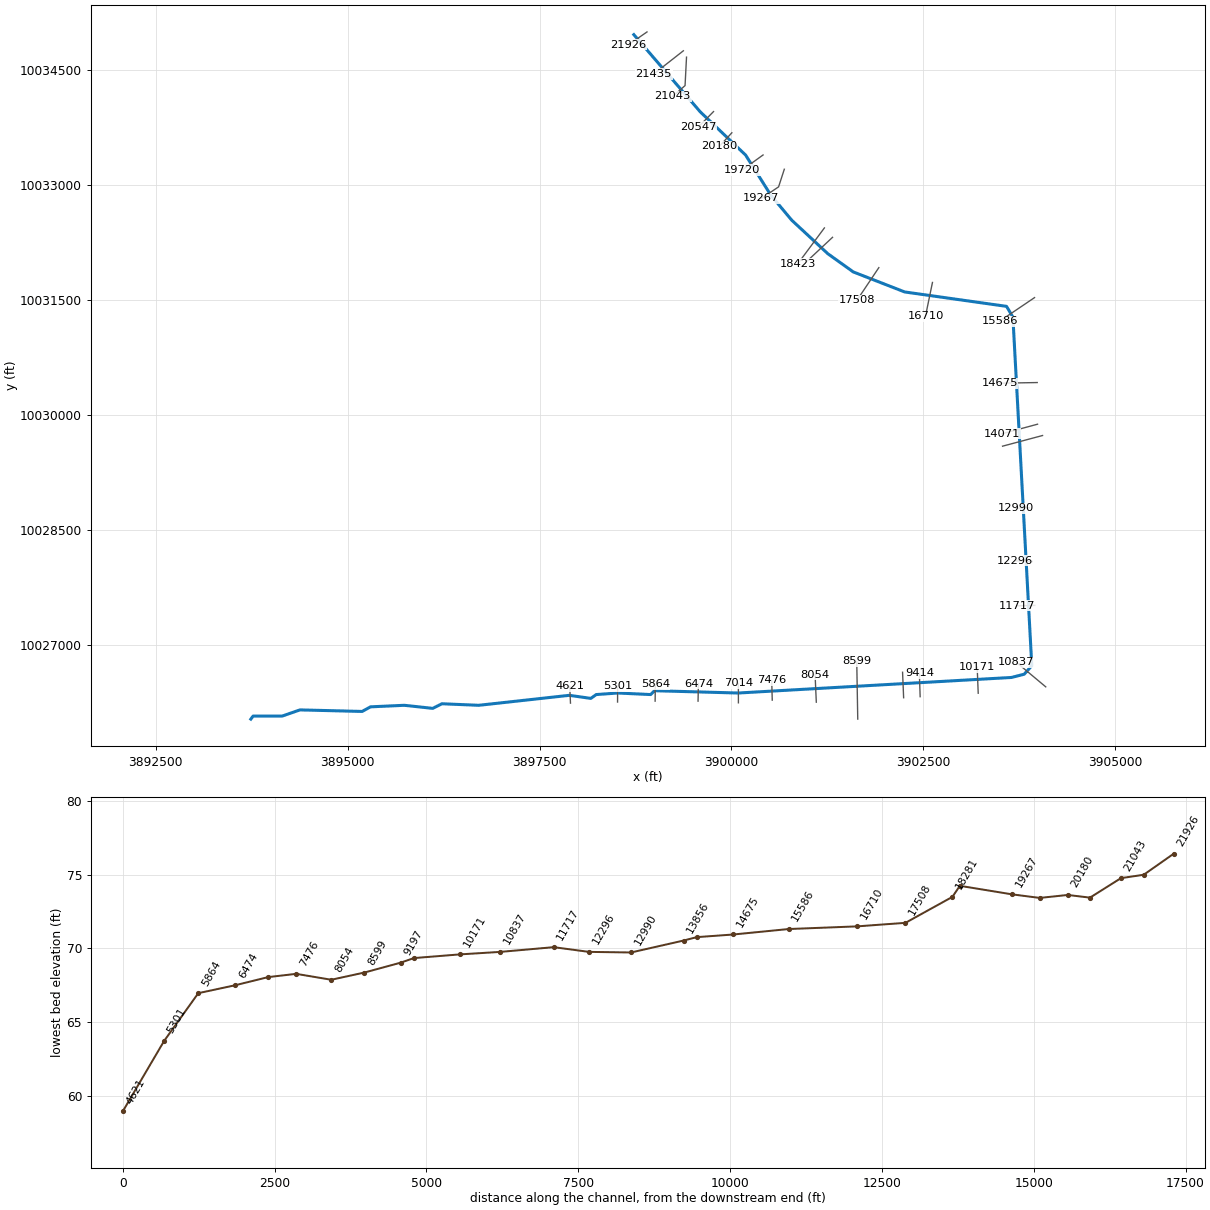
--- Crystal Creek 002.prj (project) ---

Proj Title=Crystal Creek 002 Base Level Engineering
Current Plan=p01
Default Exp/Contr=0.3,0.1
English Units
Geom File=g01
Flow File=f01
Flow File=f02
Plan File=p01
Y Axis Title=Elevation
X Axis Title(PF)=Main Channel Distance
X Axis Title(XS)=Station
BEGIN DESCRIPTION:
Crystal Creek 002
END DESCRIPTION:
DSS Export Rating Curves= 0
DSS Export Rating Curve Sorted= 0
DSS Export Volume Flow Curves= 0
DXF OffsetX= 0
DXF OffsetY= 0
DXF ScaleX= 1
DXF ScaleY= 10

--- Crystal Creek 002.p01 (plan) ---

Plan Title=Multiple Run
Program Version=4.10
Short Identifier=Multiple
Geom File=g01
Flow File=f01
Subcritical Flow
K Sum by GR= 0
Std Step Tol= 0.01
Critical Tol= 0.01
Num of Std Step Trials= 20
Max Error Tol= 0.3
Flow Tol Ratio= 0.001
Split Flow NTrial= 30
Split Flow Tol= 0.02
Split Flow Ratio= 0.02
Log Output Level= 0
Friction Slope Method= 1
Unsteady Friction Slope Method= 2
Unsteady Bridges Friction Slope Method= 1
Parabolic Critical Depth
Global Vel Dist= 1 , 1 , 1
Global Log Level= 0
CheckData=True
Encroach Param=-1 ,0,0, 0
BEGIN DESCRIPTION:
Multiple Run
END DESCRIPTION:
Computation Interval=1HOUR
Output Interval=1HOUR
Run HTab= 0
Run UNet= 0
Run PostProcess= 0
Run WQNet= 0
UNET Theta= 1
UNET Theta Warmup= 1
UNET ZTol= 0.02
UNET ZSATol= 0.05
UNET MxIter= 20
UNET MaxInSteps= 0
UNET DtIC= 0
UNET DtMin= 0
UNET MaxCRTS= 20
UNET WFStab= 2
UNET SFStab= 1
UNET WFX= 1
UNET SFX= 1
UNET DSS MLevel= 4
UNET DZMax Abort= 100
UNET Convert EG Bridges= 0
UNET Use Existing IB Tables=-1
UNET Froude Reduction=False
UNET Froude Limit= 1
UNET Froude Power= 10
UNET Time Slicing=0,0, 5
UNET Junction Losses=0
Instantaneous Interval=1HOUR
Write IC File= 0
Write IC File at Sim End=0
Echo Input=False
Echo Parameters=False
Echo Output=False
Write Detailed= 0
WQ AD Non Conservative
WQ ULTIMATE=-1
WQ Max Comp Step=1HOUR
WQ Output Interval=15MIN
WQ Output Selected Increments= 0
WQ Output face flow=0
WQ Output face velocity=0
WQ Output face area=0
WQ Output face dispersion=0
WQ Output cell volume=0
WQ Output cell surface area=0
WQ Output cell continuity=0
WQ Output cumulative cell continuity=0
WQ Output face conc=0
WQ Output face dconc_dx=0
WQ Output face courant=0
WQ Output face peclet=0
WQ Output face adv mass=0
WQ Output face disp mass=0
WQ Output cell mass=0
WQ Output cell source sink temp=0
WQ Output cell source sink nsm=0
WQ Output MaxMinRange=-1
WQ Daily Max Min Mean=-1
WQ Daily Range=0
WQ Daily Time=0
WQ Create Restart=0
WQ Fixed Restart=0
WQ System Summary=0
WQ Use Fixed Temperature=0
Sorting and Armoring Iterations= 10
XS Update Threshold= 0.02
Hydraulics Update Threshold= 0.02
Energy Slope Method= 1
Volume Change Method= 0
XS Weighting Method= 0
Number of US Weighted Cross Sections= 1
Number of DS Weighted Cross Sections= 1
Upstream XS Weight=0.25
Main XS Weight=0.5
Downstream XS Weight=0.25
Number of DS XS's Weighted with US Boundary= 1
Upstream Boundary Weight= 1
Weight of XSs Associated with US Boundary= 0
Number of US XS's Weighted with DS Boundary= 1
Downstream Boundary Weight= 0.5
Weight of XSs Associated with DS Boundary= 0.5
Sediment Output Level= 4
Mass or Volume Output= 0
Output Increment Type= 1
Profile and TS Output Increment= 10
XS Output Flag= 0
XS Output Increment= 10
Disregard all LS=0
Disregard all Conn=0
Disregard all Breaches=0
Disregard all Pumps=0

--- Crystal Creek 002.f01 (steady flow) ---

Flow Title=Multiple
Program Version=4.10
Number of Profiles= 7
Profile Names=10-year,25-year,50-year,1pct_min,100-year,1pct_plu,500-year
River Rch & RM=Crystal Creek 00,Reach-1         ,21926
     832    1098    1455     633    1911    5771    3404
River Rch & RM=Crystal Creek 00,Reach-1         ,19720
    1024    1363    1818     794    2399    7245    4315
River Rch & RM=Crystal Creek 00,Reach-1         ,18423
    1334    1784    2387    1045    3155    9528    5700
River Rch & RM=Crystal Creek 00,Reach-1         ,8599
    1586    2144    2892    1276    3852   11633    7064
Boundary for River Rch & Prof#=Crystal Creek 00,Reach-1         , 1
Up Type= 0
Dn Type= 3
Dn Slope=0.004
Boundary for River Rch & Prof#=Crystal Creek 00,Reach-1         , 2
Up Type= 0
Dn Type= 3
Dn Slope=0.004
Boundary for River Rch & Prof#=Crystal Creek 00,Reach-1         , 3
Up Type= 0
Dn Type= 3
Dn Slope=0.004
Boundary for River Rch & Prof#=Crystal Creek 00,Reach-1         , 4
Up Type= 0
Dn Type= 3
Dn Slope=0.004
Boundary for River Rch & Prof#=Crystal Creek 00,Reach-1         , 5
Up Type= 0
Dn Type= 3
Dn Slope=0.004
Boundary for River Rch & Prof#=Crystal Creek 00,Reach-1         , 6
Up Type= 0
Dn Type= 3
Dn Slope=0.004
Boundary for River Rch & Prof#=Crystal Creek 00,Reach-1         , 7
Up Type= 0
Dn Type= 3
Dn Slope=0.004
DSS Import GetInterval= 0
DSS Import GetPeak= 0
DSS Import FillOption= 0

--- Crystal Creek 002.f02 (steady flow) ---

Flow Title=Orig_BLE_Flow
Program Version=4.10
Number of Profiles= 7
Profile Names=10-year,25-year,50-year,1pct_min,100-year,1pct_plu,500-year
River Rch & RM=Crystal Creek 00,Reach-1         ,21926
     832    1076    1265     487    1470    4439    1979
River Rch & RM=Crystal Creek 00,Reach-1         ,19720
    1024    1336    1581     611    1845    5571    2509
River Rch & RM=Crystal Creek 00,Reach-1         ,18423
    1334    1749    2076     804    2427    7330    3314
River Rch & RM=Crystal Creek 00,Reach-1         ,8599
    1586    2102    2515     981    2963    8948    4107
Boundary for River Rch & Prof#=Crystal Creek 00,Reach-1         , 1
Up Type= 0
Dn Type= 3
Dn Slope=0.004
Boundary for River Rch & Prof#=Crystal Creek 00,Reach-1         , 2
Up Type= 0
Dn Type= 3
Dn Slope=0.004
Boundary for River Rch & Prof#=Crystal Creek 00,Reach-1         , 3
Up Type= 0
Dn Type= 3
Dn Slope=0.004
Boundary for River Rch & Prof#=Crystal Creek 00,Reach-1         , 4
Up Type= 0
Dn Type= 3
Dn Slope=0.004
Boundary for River Rch & Prof#=Crystal Creek 00,Reach-1         , 5
Up Type= 0
Dn Type= 3
Dn Slope=0.004
Boundary for River Rch & Prof#=Crystal Creek 00,Reach-1         , 6
Up Type= 0
Dn Type= 3
Dn Slope=0.004
Boundary for River Rch & Prof#=Crystal Creek 00,Reach-1         , 7
Up Type= 0
Dn Type= 3
Dn Slope=0.004
DSS Import GetInterval= 0
DSS Import GetPeak= 0
DSS Import FillOption= 0

--- Crystal Creek 002.g01 (geometry) ---

Geom Title=Existing Conditions
Program Version=4.10

River Reach=Crystal Creek 00,Reach-1
Reach XY= 30
      3898728.51     10034954.72      3899594.34     10033948.85
      3900184.79     10033386.27      3900514.96     10032861.46
      3900785.88     10032537.43      3901255.12     10032101.58
      3901587.57     10031863.52      3902257.41     10031602.58
      3903584.68     10031414.68      3903667.55     10031274.53
      3903913.89     10026733.04      3903814.47     10026621.72
      3903647.78     10026579.48      3900088.24     10026376.86
      3898998.24     10026406.86      3898948.24     10026356.86
      3898518.24     10026376.86      3898238.24     10026356.86
      3898168.24     10026306.86      3897888.24     10026346.86
      3896708.24     10026216.86      3896228.24     10026236.86
      3896108.24     10026176.86      3895738.24     10026216.86
      3895298.24     10026196.86      3895188.24     10026136.86
      3894378.24     10026156.86      3894148.24     10026076.86
      3893768.24     10026076.86      3893738.24     10026036.86

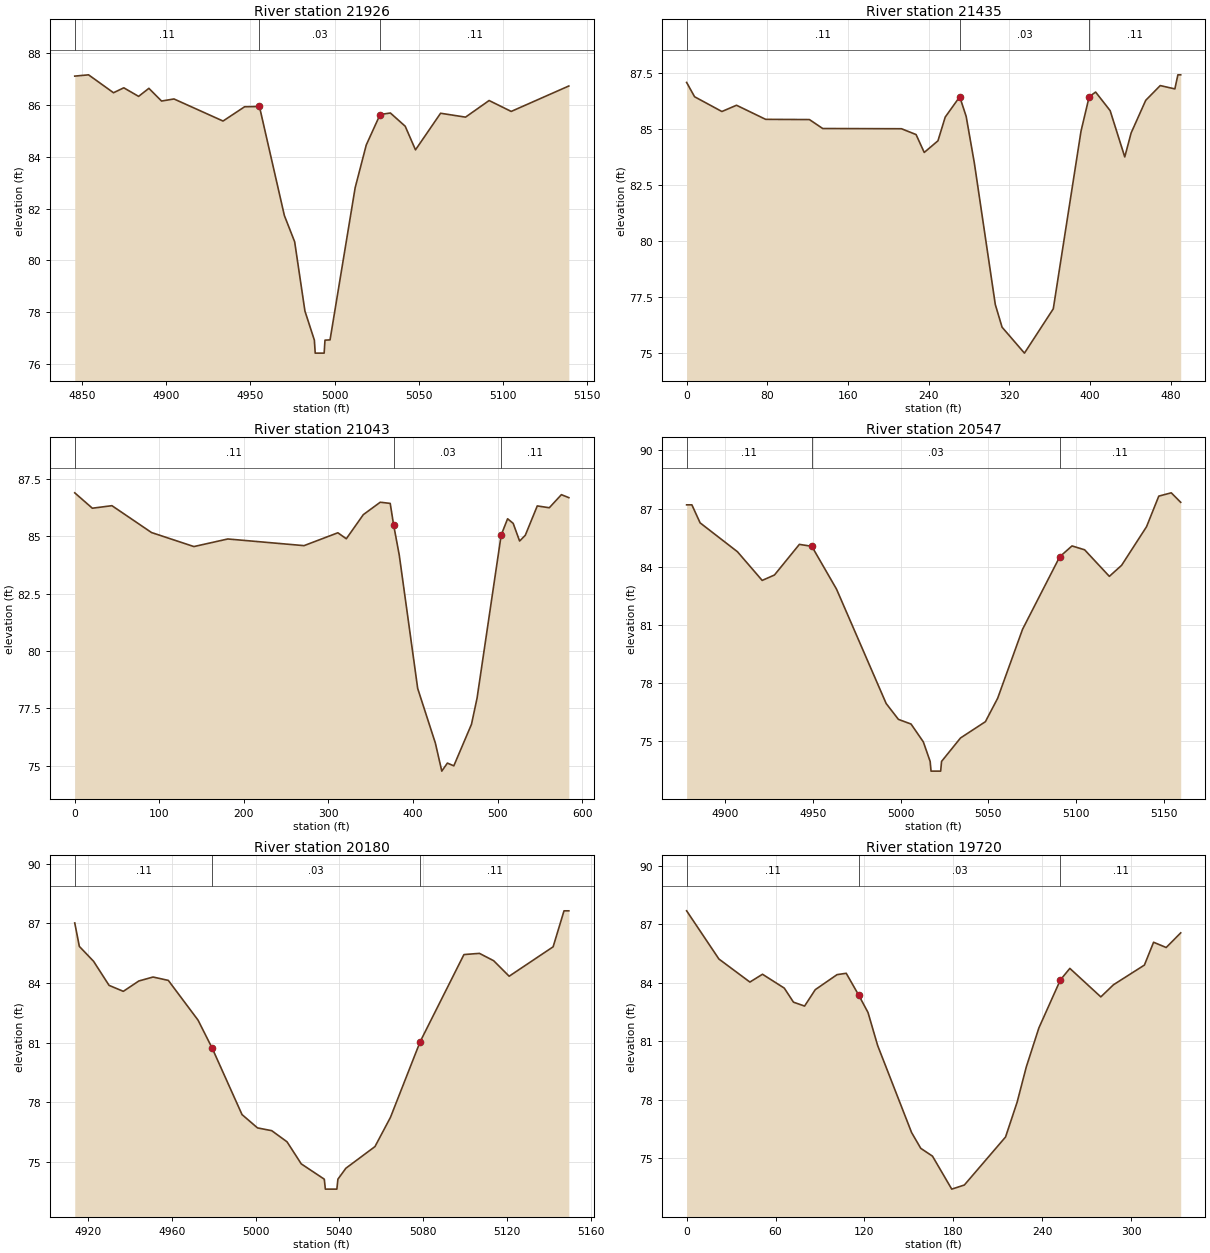
Type RM Length L Ch R = 1 ,21926   ,495,495,495
BEGIN DESCRIPTION:
Crystal Creek 002 35.0
END DESCRIPTION:
XS GIS Cut Line= 2
      3898900.24     10034990.24      3898658.94     10034823.68
#Sta/Elev= 30
  4845.8    87.1    4854   87.15  4868.8   86.46  4874.9   86.65  4883.7   86.32
  4889.8   86.63  4897.3   86.14  4904.7   86.22  4933.8   85.37  4946.6   85.92
  4955.4   85.93  4970.2   81.73  4976.3   80.72  4982.4   78.05    4988   76.93
  4988.5   76.43  4993.8   76.43  4994.3   76.93  4997.3   76.94  5012.2    82.8
  5018.8   84.45    5027   85.62  5033.1   85.68  5041.9   85.17    5048   84.26
  5062.9   85.67  5077.7   85.52  5091.7   86.16  5104.8   85.74    5139   86.72
#Mann= 3 , 0 , 0
  4845.8     .11       0  4955.4     .03       0    5027     .11       0
#XS Ineff= 2 , 0
       0                  5033.1       0   85.68
Permanent Ineff=
       F       F
Bank Sta=4955.4,5027
XS Rating Curve= 0 ,0
Exp/Cntr=0.3,0.1

Type RM Length L Ch R = 1 ,21435   ,375,375,375
XS GIS Cut Line= 2
      3899374.08     10034744.81      3898988.37     10034442.42
#Sta/Elev= 30
       0    87.1     7.9   86.46      35    85.8    49.5   86.08    78.4   85.45
   121.8   85.44     135   85.04   213.1   85.03   227.6   84.77   235.7   83.97
   249.3   84.49   256.5   85.55   270.9   86.46   277.3   85.58   285.4    83.5
   306.2   77.17   312.9   76.16   335.1      75   363.7   76.98   391.2   84.92
   399.3   86.46   405.7   86.67   420.1   85.84   434.6   83.77   440.9   84.84
   455.4    86.3   469.8   86.96   484.3   86.81   487.3   87.44   490.1   87.44
#Mann= 3 , 0 , 0
       0     .11       0   270.9     .03       0   399.3     .11       0
Bank Sta=270.9,399.3
XS Rating Curve= 0 ,0
Exp/Cntr=0.3,0.1

Type RM Length L Ch R = 1 ,21043   ,509,509,509
XS GIS Cut Line= 3
      3899415.02      10034661.8      3899395.98     10034291.37
      3899235.61     10034150.76
#Sta/Elev= 30
       0   86.89    20.8   86.22      44   86.33    90.8   85.16   140.9   84.55
     181   84.88   271.1   84.59   311.1   85.15   321.1   84.89   341.2   85.94
   361.2   86.48     373   86.43     377    85.5   383.7   84.18   405.5   78.37
   426.4   75.99     434   74.77   440.6   75.12   448.2      75   469.1   76.81
   475.7   77.95   504.2   85.05   511.8   85.76   518.4   85.56     526   84.79
   532.7   85.04   546.9   86.32   561.1   86.24   575.4   86.81   584.2   86.68
#Mann= 3 , 0 , 0
       0     .11       0     377     .03       0   504.2     .11       0
Bank Sta=377,504.2
XS Rating Curve= 0 ,0
Exp/Cntr=0.3,0.1

Type RM Length L Ch R = 1 ,20547   ,367,367,367
BEGIN DESCRIPTION:
Crystal Creek 002 32.0
END DESCRIPTION:
XS GIS Cut Line= 2
      3899767.03     10033952.79      3899569.13     10033752.18
#Sta/Elev= 30
    4878   87.19    4881   87.19  4885.7   86.26    4907   84.77  4921.1   83.29
  4928.1   83.57  4942.3   85.15  4949.4   85.05  4963.5   82.84  4991.8   76.94
  4998.8   76.12    5006   75.88    5013   74.96  5016.9   73.95  5017.4   73.45
  5022.9   73.45  5023.4   73.95  5034.2   75.16  5048.4      76  5055.4   77.21
  5069.6   80.77  5090.8   84.51  5097.8   85.07    5105   84.87  5119.1    83.5
  5126.1   84.07  5140.3   86.06  5147.3   87.64  5154.4   87.81  5159.8   87.32
#Mann= 3 , 0 , 0
    4878     .11       0  4949.4     .03       0  5090.8     .11       0
#XS Ineff= 2 , 0
       0  4942.3   85.15  5097.8       0   85.07
Permanent Ineff=
       F       F
Bank Sta=4949.4,5090.8
XS Rating Curve= 0 ,0
Exp/Cntr=0.3,0.1

Type RM Length L Ch R = 1 ,20180   ,460,460,460
BEGIN DESCRIPTION:
Crystal Creek 002 31.0
END DESCRIPTION:
XS GIS Cut Line= 2
      3900005.68     10033676.25      3899845.72     10033502.73
#Sta/Elev= 30
  4913.6   87.02  4915.8   85.84  4922.6   85.09    4930   83.88  4936.8   83.58
  4944.2    84.1    4951    84.3  4958.3   84.13  4972.5   82.13  4979.3   80.71
  4993.5   77.38  5000.9   76.71  5007.7   76.57    5015   76.01  5021.8    74.9
  5032.8   74.13  5033.3   73.63  5038.8   73.63  5039.3   74.13  5043.1   74.68
    5057   75.77  5064.4   77.24  5078.6   81.05  5099.5   85.43  5106.9   85.49
  5113.7   85.12  5121.1   84.34  5142.1   85.82  5147.3   87.63  5149.6   87.63
#Mann= 3 , 0 , 0
  4913.6     .11       0  4979.3     .03       0  5078.6     .11       0
#XS Ineff= 2 , 0
       0    4951    84.3  5106.9       0   85.49
Permanent Ineff=
       F       F
Bank Sta=4979.3,5078.6
XS Rating Curve= 0 ,0
Exp/Cntr=0.3,0.1

Type RM Length L Ch R = 1 ,19720   ,453,453,453
XS GIS Cut Line= 2
       3900412.4     10033387.47      3900141.21     10033191.87
#Sta/Elev= 30
       0   87.69    21.8   85.22    42.7   84.04    51.2   84.44    65.9   83.73
    72.1   83.01    79.6   82.81    86.8   83.65   101.5   84.42   107.7   84.49
   116.2   83.36   122.4   82.48   128.9   80.79   151.8   76.33     158   75.52
   165.9   75.12   178.9   73.43   187.4   73.64   215.2    76.1     223   77.88
   229.2   79.69   237.7   81.69   252.2   84.15   258.6   84.74   279.5   83.28
     288    83.9   308.9   84.91   315.1   86.08   323.6   85.81   333.4   86.56
#Mann= 3 , 0 , 0
       0     .11       0   116.2     .03       0   252.2     .11       0
Bank Sta=116.2,252.2
XS Rating Curve= 0 ,0
Exp/Cntr=0.3,0.1

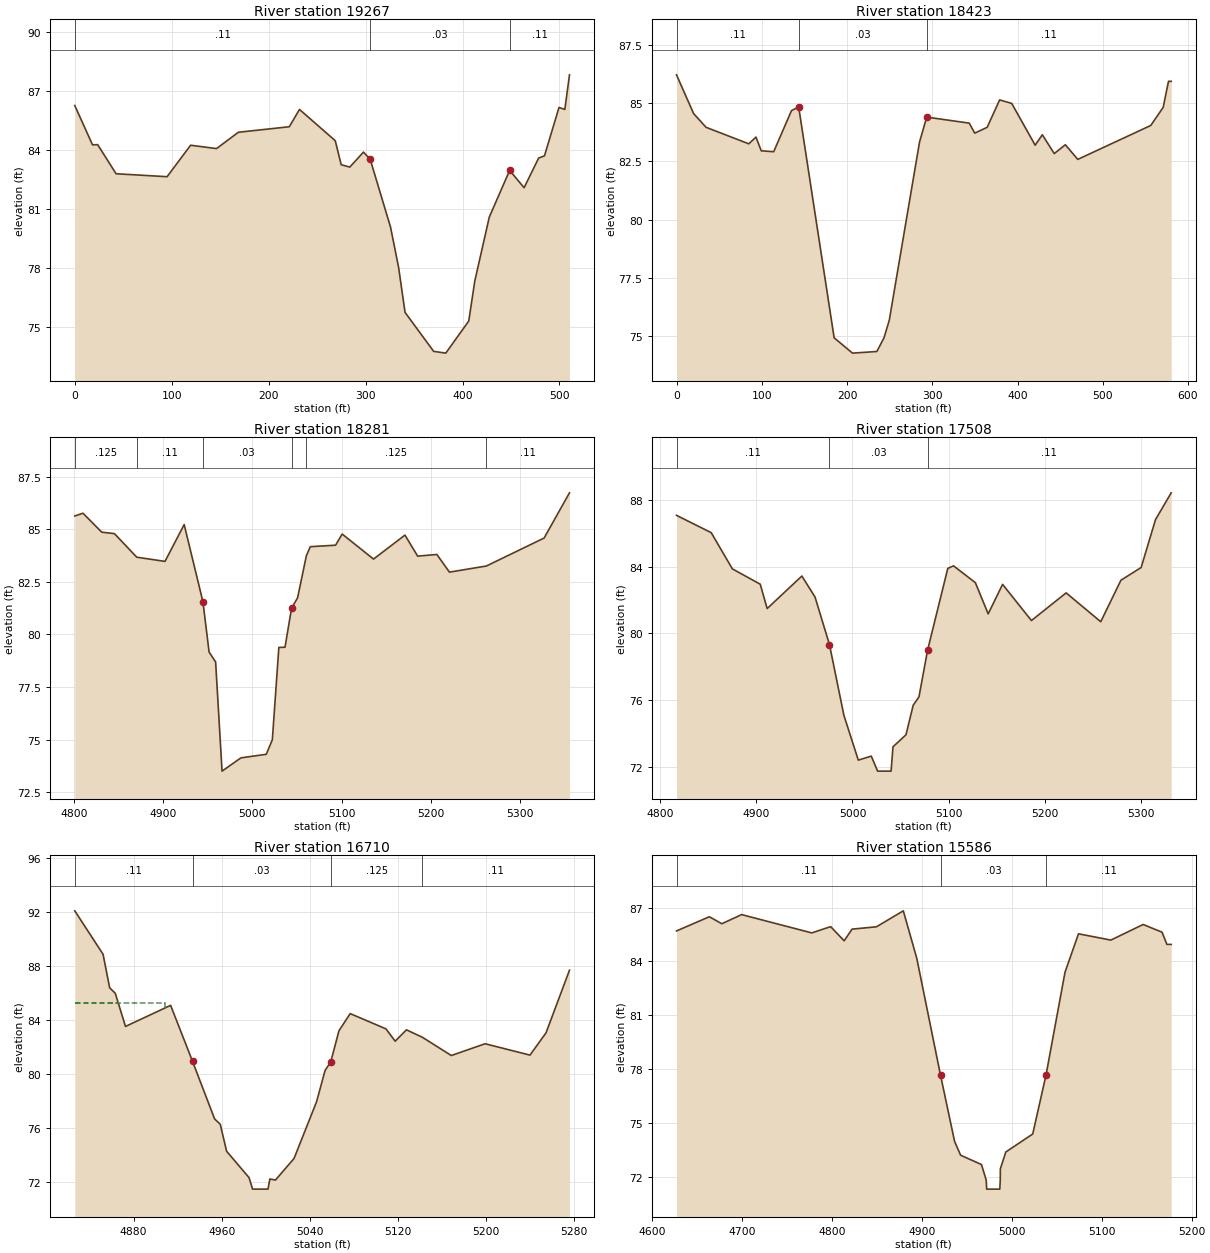
Type RM Length L Ch R = 1 ,19267   ,863,863,863
XS GIS Cut Line= 3
      3900689.14     10033201.58      3900614.65     10032972.08
      3900390.71     10032820.76
#Sta/Elev= 30
       0   86.26    18.3   84.26    23.6   84.27    42.6   82.79    95.2   82.64
   119.5   84.24   146.2   84.07   168.8    84.9   221.3   85.18   231.8   86.06
   268.7   84.47   274.8   83.25   283.7   83.13   297.8   83.89   304.7   83.53
   325.7   80.08     334   78.04   340.7   75.74   370.2   73.76   382.7   73.67
   406.4    75.3   412.6   77.33   427.6   80.59   448.6   82.96   463.5   82.08
   478.5   83.59   484.5    83.7   499.5   86.16   505.5   86.06   510.3   87.82
#Mann= 3 , 0 , 0
       0     .11       0   304.7     .03       0   448.6     .11       0
Bank Sta=304.7,448.6
XS Rating Curve= 0 ,0
Exp/Cntr=0.3,0.1

Type RM Length L Ch R = 1 ,18423   ,123,123,123
XS GIS Cut Line= 2
       3901211.5     10032436.74      3900865.44      10031970.9
#Sta/Elev= 30
       0   86.23    20.1   84.56    34.7   83.97    84.8   83.26    93.2   83.55
    99.4   82.96     114   82.92   134.9   84.69   143.3   84.85   184.9   74.91
   206.4   74.25     235   74.32   243.4   74.91   249.6   75.67   285.1   83.34
   293.5   84.41   343.4   84.15   349.8   83.72   364.4   83.97     379   85.15
   393.2      85   420.7    83.2   429.1   83.65   443.1   82.84   456.1   83.22
   470.7   82.59   556.3   84.05   570.9   84.83   577.1   85.95   580.3   85.95
#Mann= 3 , 0 , 0
       0     .11       0   143.3     .03       0   293.5     .11       0
Bank Sta=143.3,293.5
XS Rating Curve= 0 ,0
Exp/Cntr=0.3,0.1

Type RM Length L Ch R = 1 ,18281   ,773,773,773
BEGIN DESCRIPTION:
Crystal Creek 002 27.0
END DESCRIPTION:
XS GIS Cut Line= 2
      3901317.43     10032314.37        3900913.     10031935.89
#Sta/Elev= 30
  4801.2   85.63  4810.4   85.76  4831.4   84.86  4845.6   84.79  4870.6   83.67
  4902.2   83.47  4923.7   85.22  4944.7   81.55  4951.6   79.16  4958.9   78.69
  4966.1    73.5  4987.2   74.13  5015.6    74.3  5022.4   74.99  5029.7   79.38
  5036.6   79.39  5043.9   81.24  5050.7   81.74  5060.5   83.74  5064.9   84.17
  5093.2   84.24  5100.6   84.77  5135.7   83.58  5170.9   84.72  5185.1   83.72
  5206.6    83.8  5220.7   82.96    5262   83.25  5326.7   84.58  5355.1   86.73
#Mann= 6 ,-1 , 0
  4801.2    .125       0  4870.6     .11       0  4944.7     .03       0
  5043.9     .11       0  5060.5    .125       0    5262     .11       0
#XS Ineff= 2 , 0
       0  4923.7   85.22  5100.6       0   84.77
Permanent Ineff=
       F       F
Bank Sta=4944.7,5043.9
XS Rating Curve= 0 ,0
Exp/Cntr=0.3,0.1

Type RM Length L Ch R = 1 ,17508   ,798,798,798
BEGIN DESCRIPTION:
Crystal Creek 002 26.0
END DESCRIPTION:
XS GIS Cut Line= 2
       3901920.7     10031919.37      3901634.25     10031491.87
#Sta/Elev= 30
    4817   87.08  4853.1   86.04  4875.1   83.87  4904.1   82.95  4911.3   81.49
  4947.4   83.44  4961.1   82.18  4976.1   79.33  4991.1   75.09  5006.1    72.4
  5019.6   72.64  5026.2   71.74  5040.2   71.74  5042.2    73.2  5055.7   73.92
  5063.2   75.69  5069.2   76.19  5078.2      79  5099.2    83.9  5105.2   84.05
  5127.9   83.04  5141.2   81.17  5156.2   82.94  5186.2   80.77  5222.3   82.43
  5258.3    80.7  5279.3   83.19  5300.3   83.95  5315.3   86.83  5331.6   88.43
#Mann= 3 , 0 , 0
    4817     .11       0  4976.1     .03       0  5078.2     .11       0
#XS Ineff= 2 , 0
       0  4947.4   83.44  5105.2       0   84.05
Permanent Ineff=
       F       F
Bank Sta=4976.1,5078.2
XS Rating Curve= 0 ,0
Exp/Cntr=0.3,0.1

Type RM Length L Ch R = 1 ,16710   ,1124,1124,1124
BEGIN DESCRIPTION:
Crystal Creek 002 25.0
END DESCRIPTION:
XS GIS Cut Line= 2
      3902619.48      10031726.2      3902528.39     10031285.93
#Sta/Elev= 30
  4826.5   92.08  4852.2   88.87  4858.2   86.39  4863.3   85.98  4872.6   83.53
  4913.6   85.09 4933.52   80.95  4953.6   76.69  4958.7    76.3  4964.5    74.3
  4984.9   72.35  4988.1    71.5  5002.1    71.5  5003.8   72.25  5008.9   72.17
  5025.8   73.77  5046.2   77.95    5054   80.28  5059.1    80.9  5066.6   83.21
  5076.8   84.48  5109.3   83.35  5117.7   82.44  5127.9   83.28  5142.4   82.73
  5168.7   81.38  5199.4   82.25  5240.2   81.41  5254.8   83.06  5276.1   87.69
#Mann= 4 ,-1 , 0
  4826.5     .11       0 4933.52     .03       0  5059.1    .125       0
  5142.4     .11       0
#XS Ineff= 2 , 0
       0  4908.5   85.25  5076.8       0   84.48
Permanent Ineff=
       F       F
Bank Sta=4933.52,5059.1
XS Rating Curve= 0 ,0
Exp/Cntr=0.3,0.1

Type RM Length L Ch R = 1 ,15586   ,911,911,911
BEGIN DESCRIPTION:
Crystal Creek 002 24.0
END DESCRIPTION:
XS GIS Cut Line= 2
      3903949.57     10031528.88      3903493.88     10031220.74
#Sta/Elev= 30
  4627.1    85.7  4663.6   86.49  4677.5    86.1  4699.5   86.61  4777.5   85.59
  4798.5   85.94  4813.5   85.15  4822.3    85.8  4849.4   85.93  4879.3   86.82
  4894.3   84.17  4920.777.65705  4936.3   73.98    4943   73.21  4966.2   72.69
  4971.5   71.82    4972   71.32  4986.6   71.32  4987.1   71.82  4987.2   72.45
  4993.3   73.39  5023.2   74.39  5038.1    77.7  5059.1    83.4  5074.1   85.54
  5110.1   85.19    5146   86.06    5167   85.63  5172.4   84.95  5177.2   84.95
#Mann= 3 , 0 , 0
  4627.1     .11       0  4920.7     .03       0  5038.1     .11       0
Bank Sta=4920.7,5038.1
XS Rating Curve= 0 ,0
Exp/Cntr=0.3,0.1

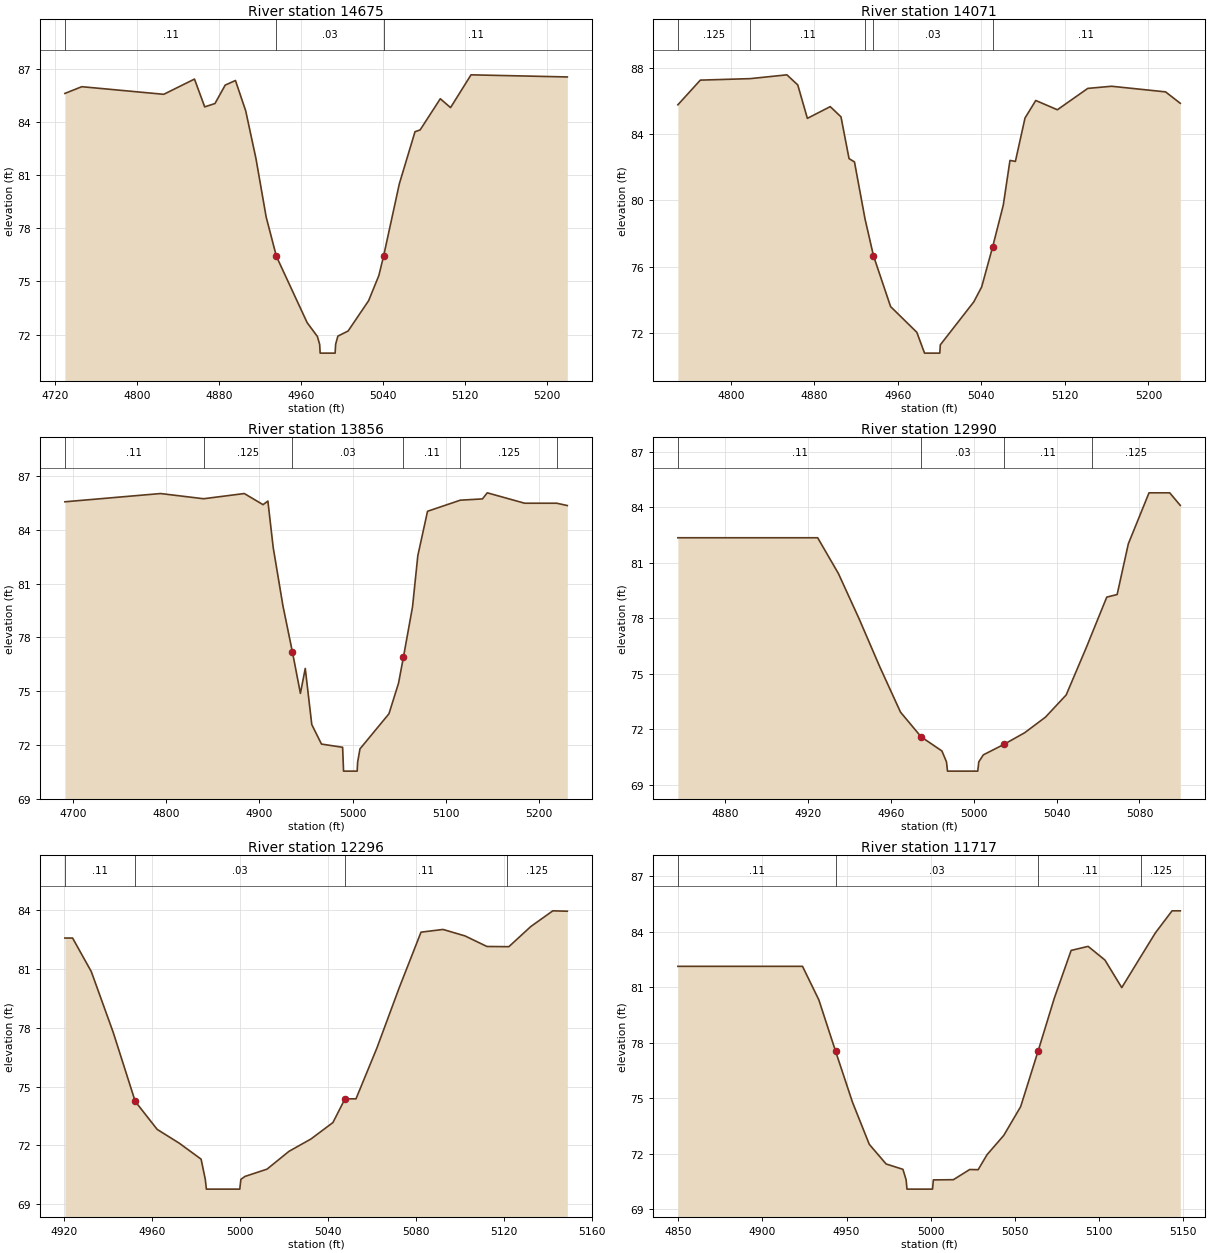
Type RM Length L Ch R = 1 ,14675   ,604,604,604
BEGIN DESCRIPTION:
Crystal Creek 002 23.0
END DESCRIPTION:
XS GIS Cut Line= 2
       3903984.3     10030422.12      3903493.88     10030413.44
#Sta/Elev= 30
  4729.7   85.61  4746.2   85.99  4826.2   85.56  4856.2   86.42  4866.2   84.85
  4876.2   85.04  4886.2   86.08  4896.2   86.34  4906.2   84.63  4916.2   81.94
  4926.2   78.63  4936.2   76.41  4966.2   72.67  4976.2   71.89  4978.4   71.45
  4978.9   70.95  4993.5   70.95    4994   71.45  4996.2   71.91  5006.2    72.2
  5026.2   73.91  5036.2   75.33  5040.976.44853  5056.2   80.51  5071.5   83.45
  5076.5   83.55  5096.2   85.31  5106.2   84.81  5126.2   86.66  5220.2   86.54
#Mann= 3 , 0 , 0
  4729.7     .11       0  4936.2     .03       0  5040.9     .11       0
Bank Sta=4936.2,5040.9
XS Rating Curve= 0 ,0
Exp/Cntr=0.3,0.1

Type RM Length L Ch R = 1 ,14071   ,215,215,215
BEGIN DESCRIPTION:
Crystal Creek 002 22.0
END DESCRIPTION:
XS GIS Cut Line= 2
      3903988.64     10029879.58       3903524.3     10029753.73
#Sta/Elev= 30
  4749.4   85.77  4770.9   87.26  4818.7   87.35  4853.8   87.58  4864.2   86.97
  4873.4   84.95  4895.3   85.66  4905.6   85.04  4913.3   82.52  4918.5   82.32
  4928.6   78.88  4936.7   76.65  4953.1   73.58  4978.2   72.03  4985.6   70.77
  5000.2   70.77  5000.7   71.27  5032.8   73.87  5040.3   74.77  5050.7   77.16
    5061   79.71  5067.4   82.41  5072.6   82.35  5081.8   84.97  5092.1   86.03
  5112.8   85.47  5141.9   86.76  5164.7   86.89  5216.4   86.55  5230.5   85.86
#Mann= 5 ,-1 , 0
  4749.4    .125       0  4818.7     .11       0  4928.6    .125       0
  4936.7     .03       0  5050.7     .11       0
Bank Sta=4936.7,5050.7
XS Rating Curve= 0 ,0
Exp/Cntr=0.3,0.1

Type RM Length L Ch R = 1 ,13856   ,866,866,866
BEGIN DESCRIPTION:
Crystal Creek 002 21.0
END DESCRIPTION:
XS GIS Cut Line= 2
      3904053.81     10029732.03      3903532.91     10029593.13
#Sta/Elev= 30
  4691.3   85.57  4793.9   86.03  4840.1   85.74  4883.8   86.03  4903.9   85.41
  4909.1   85.61  4914.8   83.02  4925.2   79.78  4935.5   77.17    4944   74.88
  4949.2   76.27  4956.2   73.14  4966.6   72.05  4989.3   71.87  4990.3   70.54
  5004.9   70.54  5005.4   71.04  5007.9   71.78    5039   73.74  5049.3   75.45
 5054.5876.91011  5064.3   79.71    5070   82.57  5080.4   85.04  5115.6   85.66
  5139.3   85.73  5144.5   86.07  5184.6   85.49    5219   85.49  5230.4   85.36
#Mann= 6 ,-1 , 0
  4691.3     .11       0  4840.1    .125       0  4935.5     .03       0
 5054.58     .11       0  5115.6    .125       0    5219     .11       0
Bank Sta=4935.5,5054.58
XS Rating Curve= 0 ,0
Exp/Cntr=0.3,0.1

Type RM Length L Ch R = 1 ,12990   ,694,694,694
BEGIN DESCRIPTION:
Crystal Creek 002 20.0
END DESCRIPTION:
XS GIS Cut Line= 2
      3903882.82     10028789.58      3903702.77     10028785.34
#Sta/Elev= 26
  4857.1   82.35  4919.6   82.35  4924.6   82.35  4934.6   80.42  4944.6   77.97
  4954.6   75.37  4964.6   72.92  4974.6   71.58  4984.6   70.82  4986.8   70.23
  4987.3   69.73  5001.9   69.73  5002.4   70.23  5004.6   70.61  5014.6   71.18
  5024.6   71.81  5034.6   72.65  5044.6   73.85  5054.6   76.49  5057.3   77.24
  5064.2   79.14  5069.2   79.28  5074.6   82.02  5084.6   84.78  5094.6   84.78
  5099.7    84.1
#Mann= 4 ,-1 , 0
  4857.1     .11       0  4974.6     .03       0  5014.6     .11       0
  5057.3    .125       0
Bank Sta=4974.6,5014.6
XS Rating Curve= 0 ,0
Exp/Cntr=0.3,0.1

Type RM Length L Ch R = 1 ,12296   ,579,579,579
BEGIN DESCRIPTION:
Crystal Creek 002 19.0
END DESCRIPTION:
XS GIS Cut Line= 2
       3903919.8     10028091.25      3903691.26     10028099.87
#Sta/Elev= 30
  4920.2   82.59  4923.7   82.59  4932.2   80.88  4942.2   77.77  4952.2   74.25
  4962.2   72.82  4972.2   72.12  4982.2    71.3  4984.1   70.27  4984.6   69.77
  4999.8   69.77  5000.3   70.27  5002.2   70.42  5012.2   70.79  5022.2    71.7
  5032.2   72.33  5042.2   73.17  5047.7   74.38  5052.7   74.38  5062.2   76.97
  5072.3   80.03  5082.3   82.89  5092.3   83.03  5102.3    82.7  5112.3   82.16
  5121.4   82.15  5122.3   82.15  5132.3   83.18  5142.3   83.98  5148.9   83.96
#Mann= 4 ,-1 , 0
  4920.2     .11       0  4952.2     .03       0  5047.7     .11       0
  5121.4    .125       0
Bank Sta=4952.2,5047.7
XS Rating Curve= 0 ,0
Exp/Cntr=0.3,0.1

Type RM Length L Ch R = 1 ,11717   ,880,880,880
BEGIN DESCRIPTION:
Crystal Creek 002 18.0
END DESCRIPTION:
XS GIS Cut Line= 2
      3903952.26      10027518.6      3903723.02     10027513.27
#Sta/Elev= 30
  4849.7   82.13  4919.1   82.13  4923.8   82.13  4933.5   80.32  4943.5   77.53
  4953.5   74.79  4963.5   72.51  4973.5   71.45  4983.5   71.16  4985.4   70.59
  4985.9   70.09  5001.1   70.09  5001.6   70.59  5003.5   70.59  5013.5    70.6
  5023.2   71.15  5028.2   71.14  5033.5   71.95  5043.5      73  5053.5   74.55
 5063.89   77.56  5073.5   80.41  5083.5   82.99  5093.6   83.21  5103.6   82.47
  5113.6   80.98    5125   82.67  5133.6   83.94  5143.5   85.13  5148.4   85.13
#Mann= 4 ,-1 , 0
  4849.7     .11       0  4943.5     .03       0 5063.89     .11       0
    5125    .125       0
Bank Sta=4943.5,5063.89
XS Rating Curve= 0 ,0
Exp/Cntr=0.3,0.1

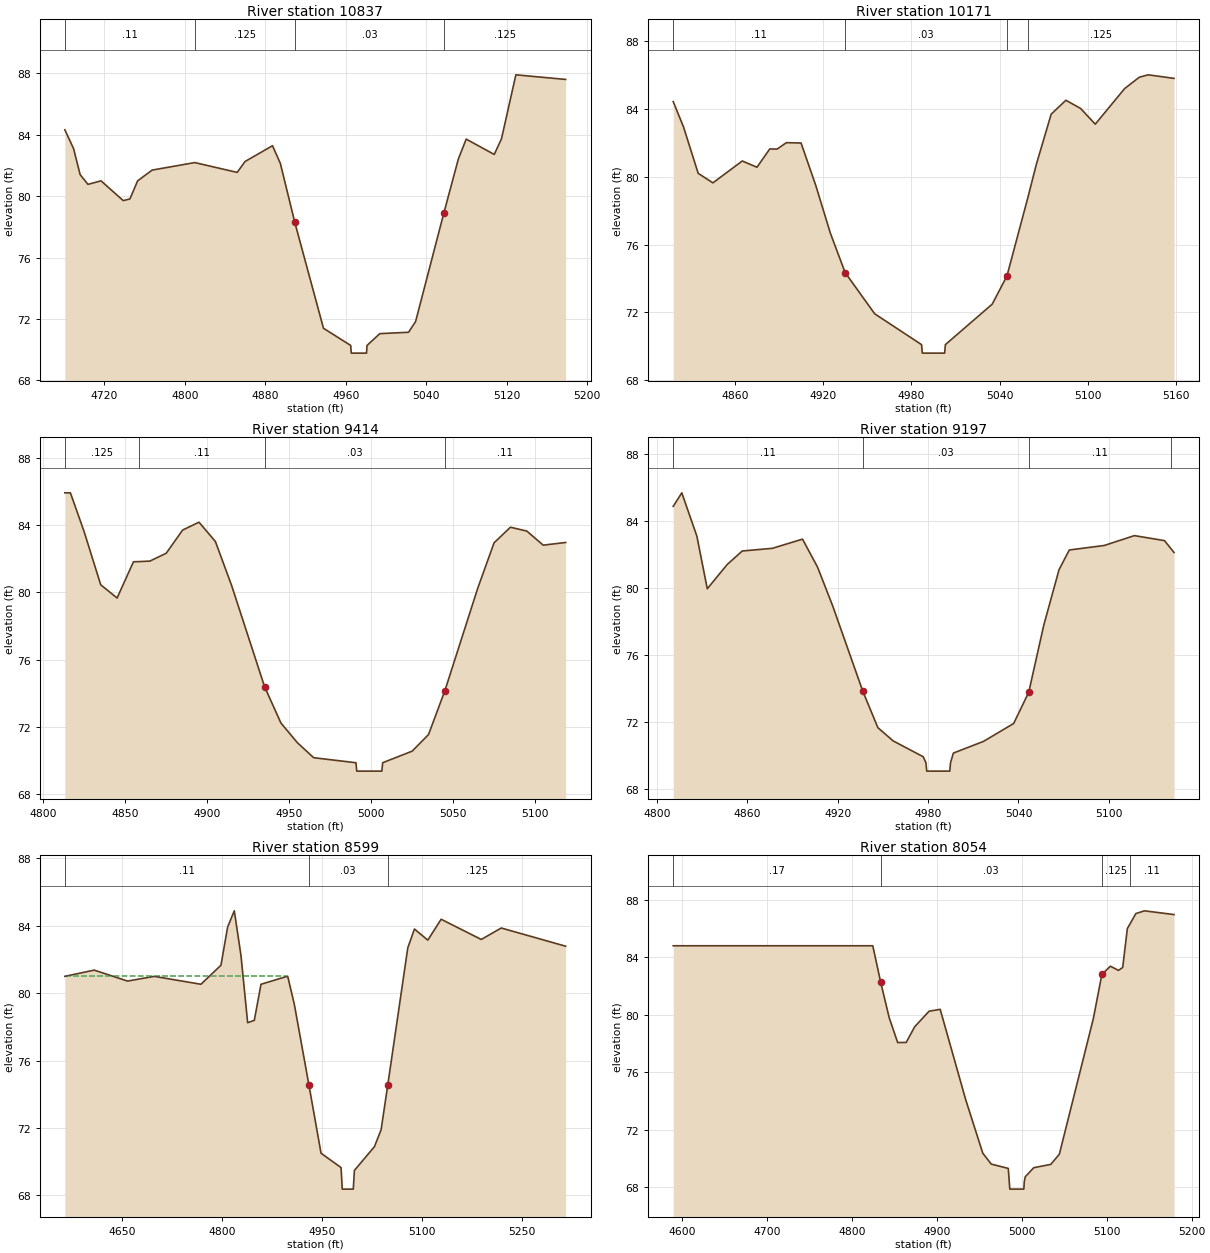
Type RM Length L Ch R = 1 ,10837   ,666,666,666
BEGIN DESCRIPTION:
Crystal Creek 002 17.0
END DESCRIPTION:
XS GIS Cut Line= 2
      3904095.51     10026457.16      3903713.39     10026776.52
#Sta/Elev= 30
  4680.6   84.33  4689.3    83.1  4695.8   81.41  4703.6   80.77  4716.6      81
  4738.7   79.71  4745.3   79.82    4753      81  4767.4    81.7  4809.8   82.19
    4852   81.55  4859.8   82.26  4887.1   83.29  4894.9   82.14  4909.2   78.31
  4937.8   71.39  4964.9   70.27  4965.4   69.77  4980.6   69.77  4981.1   70.27
  4993.8   71.04  5022.4   71.13  5029.4   71.83  5057.6   78.93  5071.9   82.42
  5079.7   83.72  5107.6   82.72  5114.8   83.74  5129.1   87.91  5178.6   87.61
#Mann= 4 ,-1 , 0
  4680.6     .11       0  4809.8    .125       0  4909.2     .03       0
  5057.6    .125       0
#XS Ineff= 2 , 0
       0  4887.1   83.29               0
Permanent Ineff=
       F       F
Bank Sta=4909.2,5057.6
XS Rating Curve= 0 ,0
Exp/Cntr=0.3,0.1

Type RM Length L Ch R = 1 ,10171   ,757,757,757
BEGIN DESCRIPTION:
Crystal Creek 002 16.0
END DESCRIPTION:
XS GIS Cut Line= 2
      3903215.58     10026374.12       3903202.2     10026714.65
#Sta/Elev= 30
  4817.9   84.43  4824.9   82.94  4834.9    80.2  4844.9   79.64  4864.9   80.93
  4874.9   80.56  4883.6   81.64  4888.6   81.63  4894.9   82.01  4904.9   81.99
  4914.9   79.49  4924.9   76.66  4934.9   74.35    4955   71.92  4986.9    70.1
  4987.4    69.6  5002.6    69.6  5003.1    70.1    5035   72.49    5045   74.15
  5059.3   78.79    5065   80.73  5075.1   83.69  5085.1   84.51  5095.1   84.03
  5105.1    83.1  5125.1    85.2  5135.1   85.87  5141.2   86.01  5158.7    85.8
#Mann= 4 ,-1 , 0
  4817.9     .11       0  4934.9     .03       0    5045     .11       0
  5059.3    .125       0
#XS Ineff= 2 , 0
       0  4904.9   81.99               0
Permanent Ineff=
       F       F
Bank Sta=4934.9,5045
XS Rating Curve= 0 ,0
Exp/Cntr=0.3,0.1

Type RM Length L Ch R = 1 ,9414    ,217,217,217
BEGIN DESCRIPTION:
Crystal Creek 002 15.0
END DESCRIPTION:
XS GIS Cut Line= 2
      3902459.15     10026329.23      3902448.73     10026634.75
#Sta/Elev= 30
  4813.3   85.94  4816.7   85.94  4825.1   83.62  4835.2   80.46  4845.2   79.67
  4855.2   81.83  4858.5   81.84  4865.2   81.87  4875.2   82.34  4885.2   83.72
  4895.2   84.19  4905.2   83.04  4915.2   80.39  4935.2   74.39  4945.2   72.22
  4955.2   71.05  4965.2   70.15    4991   69.85  4991.5   69.35  5006.8   69.35
  5007.3   69.85  5025.3   70.54  5035.3   71.53  5045.3   74.15  5065.3   80.24
  5075.3   82.96  5085.3   83.89  5095.3   83.66  5105.3   82.82    5119   82.98
#Mann= 4 ,-1 , 0
  4813.3    .125       0  4858.5     .11       0  4935.2     .03       0
  5045.3     .11       0
#XS Ineff= 2 , 0
       0  4895.2   84.19               0
Permanent Ineff=
       F       F
Bank Sta=4935.2,5045.3
XS Rating Curve= 0 ,0
Exp/Cntr=0.3,0.1

Type RM Length L Ch R = 1 ,9197    ,598,598,598
BEGIN DESCRIPTION:
Crystal Creek 002 14.0
END DESCRIPTION:
XS GIS Cut Line= 2
      3902243.87     10026315.34      3902230.04     10026647.35
#Sta/Elev= 30
  4810.9   84.88  4816.6   85.69  4826.6    83.1  4833.5   79.95  4846.7    81.4
  4856.7   82.21  4876.7   82.37  4896.7   82.92  4906.7   81.24  4916.7   78.93
  4936.7   73.82  4946.7   71.64  4956.8   70.85  4976.8    69.9  4978.6   69.54
  4979.1   69.04  4994.4   69.04  4994.9   69.54  4996.8   70.12  5016.8   70.82
  5036.8   71.89  5046.8   73.76  5056.8   77.78  5066.9   81.09  5073.7   82.27
  5096.9   82.54  5116.9   83.13  5136.9   82.83  5141.5   82.31  5143.2   82.12
#Mann= 4 ,-1 , 0
  4810.9     .11       0  4936.7     .03       0  5046.8     .11       0
  5141.5    .125       0
#XS Ineff= 2 , 0
       0  4896.7   82.92               0
Permanent Ineff=
       F       F
Bank Sta=4936.7,5046.8
XS Rating Curve= 0 ,0
Exp/Cntr=0.3,0.1

Type RM Length L Ch R = 1 ,8599    ,545,545,545
BEGIN DESCRIPTION:
Crystal Creek 002 13.0
END DESCRIPTION:
XS GIS Cut Line= 2
      3901646.06     10026037.11        3901633.      10026787.6
#Sta/Elev= 30
  4564.6      81  4608.6   81.37  4658.6   80.72  4698.6      81  4768.6   80.53
  4798.6   81.66  4808.6   83.93  4818.6   84.89  4828.6   82.24  4838.6   78.25
  4848.6   78.39  4858.6   80.53  4898.6   81.01  4908.6   79.33 4930.3374.57442
  4948.6    70.5  4978.6   69.65  4980.4   68.37  4996.9   68.37  4998.6   69.48
  5028.6   70.89  5038.6   71.89  5048.6   74.55  5078.6   82.69  5088.6   83.81
  5108.6   83.15  5128.6   84.39  5188.7   83.19  5218.7   83.87  5315.2   82.79
#Mann= 3 , 0 , 0
  4564.6     .11       0 4930.33     .03       0  5048.6    .125       0
#XS Ineff= 2 , 0
       0  4898.6   81.01               0
Permanent Ineff=
       F       F
Bank Sta=4930.33,5048.6
XS Rating Curve= 0 ,0
Exp/Cntr=0.3,0.1

Type RM Length L Ch R = 1 ,8054    ,578,578,578
BEGIN DESCRIPTION:
Crystal Creek 002 12.0
END DESCRIPTION:
XS GIS Cut Line= 2
      3901106.07     10026257.54      3901090.14     10026615.89
#Sta/Elev= 30
    4590    84.8  4824.8    84.8    4834   82.29  4844.1    79.8  4854.1   78.07
  4864.1   78.08  4874.1   79.17    4891   80.25  4904.1   80.38  4934.1    74.1
  4954.2   70.38  4964.2   69.62  4984.2   69.32    4986   67.88  5002.5   67.88
    5003   68.38  5004.2   68.74  5014.2   69.37  5034.2    69.6  5044.3   70.31
  5084.3   79.74  5094.3   82.81  5104.3   83.38  5113.8   83.09  5118.8   83.29
  5124.3      86  5127.7   86.35  5134.3   87.04  5144.4   87.23  5179.2   86.97
#Mann= 4 ,-1 , 0
    4590     .17       0    4834     .03       0  5094.3    .125       0
  5127.7     .11       0
#XS Ineff= 2 , 0
       0  4904.1   80.38               0
Permanent Ineff=
       F       F
Bank Sta=4834,5094.3
XS Rating Curve= 0 ,0
Exp/Cntr=0.3,0.1

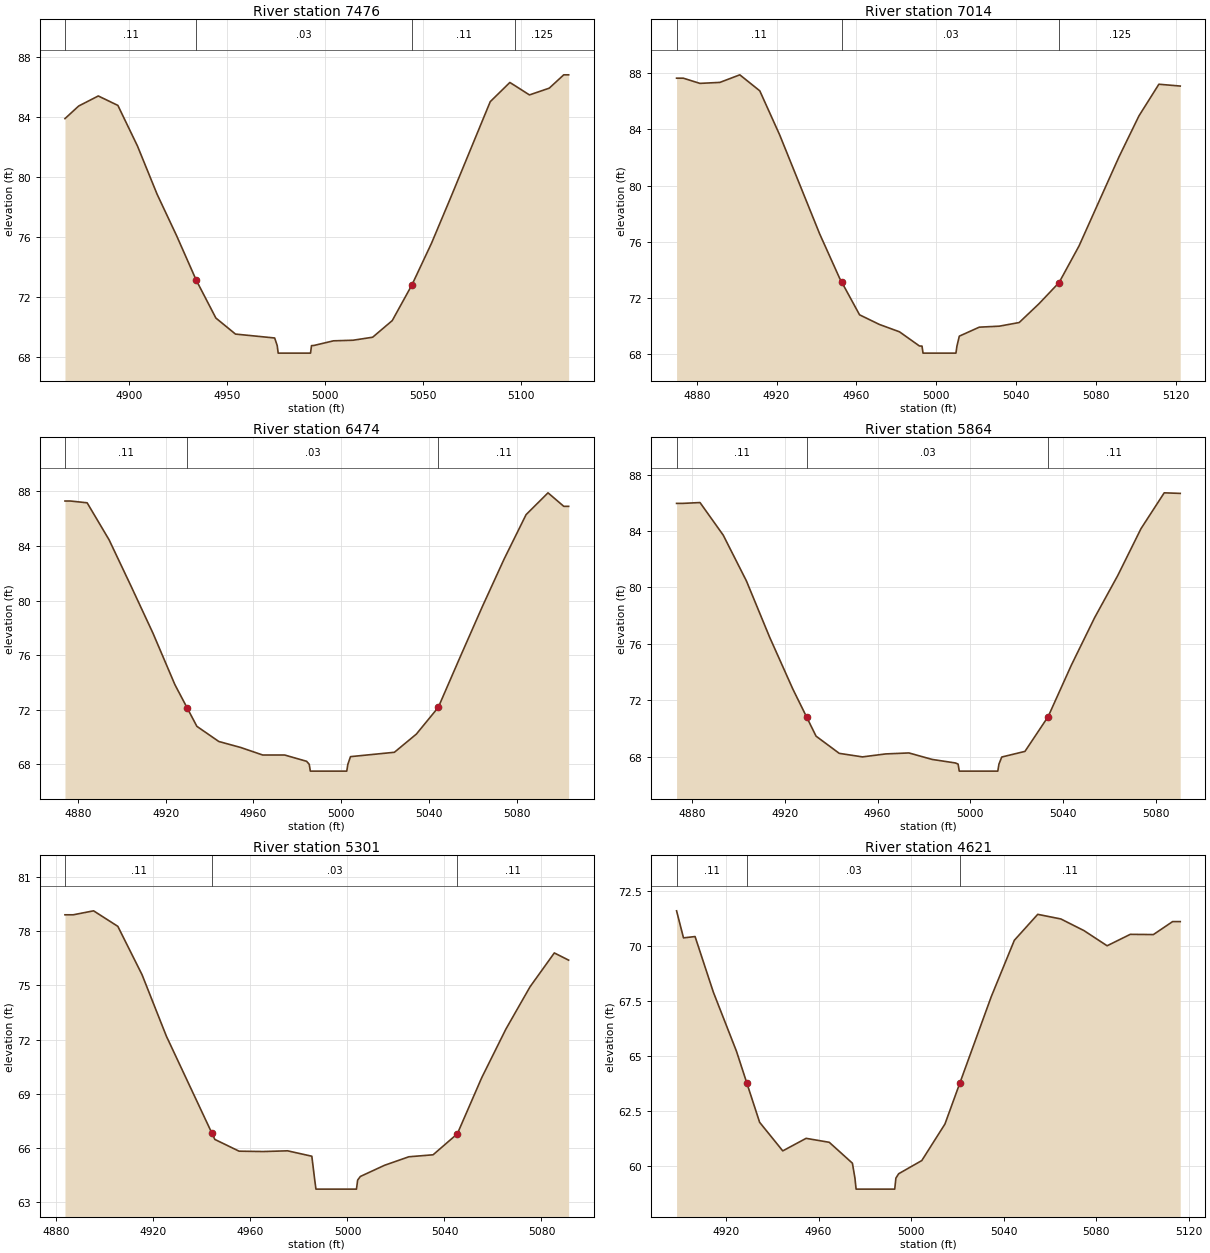
Type RM Length L Ch R = 1 ,7476    ,462,462,462
BEGIN DESCRIPTION:
Crystal Creek 002 11.0
END DESCRIPTION:
XS GIS Cut Line= 2
      3900532.06     10026284.11      3900525.12     10026541.02
#Sta/Elev= 30
  4867.2   83.92  4874.2   84.76  4884.2   85.43  4894.2    84.8  4904.2   82.09
  4914.2   78.88  4924.2    76.1  4934.2   73.14  4944.2   70.62  4954.2   69.55
  4974.2   69.29  4975.5   68.78    4976   68.28  4992.5   68.28    4993   68.78
  4994.2   68.79  5004.2    69.1  5014.2   69.14  5024.2   69.34  5034.2   70.45
  5044.2   72.82  5054.2    75.6  5064.2   78.71  5084.2   85.05  5094.2   86.33
  5096.9   86.11  5104.2    85.5  5114.3   85.95  5121.7   86.84  5124.2   86.84
#Mann= 4 ,-1 , 0
  4867.2     .11       0  4934.2     .03       0  5044.2     .11       0
  5096.9    .125       0
Bank Sta=4934.2,5044.2
XS Rating Curve= 0 ,0
Exp/Cntr=0.3,0.1

Type RM Length L Ch R = 1 ,7014    ,540,540,540
BEGIN DESCRIPTION:
Crystal Creek 002 10.0
END DESCRIPTION:
XS GIS Cut Line= 2
      3900091.09     10026249.35      3900090.58     10026501.75
#Sta/Elev= 29
  4869.9   87.65  4873.3   87.65  4881.6   87.28  4891.6   87.35  4901.6   87.89
  4911.6   86.75  4921.6    83.6  4941.6   76.56  4951.6    73.4  4952.773.11288
  4961.6   70.79  4971.6    70.1  4981.6   69.58  4991.6   68.57  4992.9   68.56
  4993.4   68.06  5009.9   68.06  5010.4   68.56  5011.6   69.27  5021.6   69.91
  5031.6   69.98  5041.6   70.24  5051.6   71.59  5061.6   73.09  5071.6    75.7
  5091.6   82.04  5101.6   84.96  5111.6   87.22  5122.3   87.09
#Mann= 3 , 0 , 0
  4869.9     .11       0  4952.7     .03       0  5061.6    .125       0
Bank Sta=4952.7,5061.6
XS Rating Curve= 0 ,0
Exp/Cntr=0.3,0.1

Type RM Length L Ch R = 1 ,6474    ,610,610,610
BEGIN DESCRIPTION:
Crystal Creek 002 9.0
END DESCRIPTION:
XS GIS Cut Line= 2
      3899565.33     10026270.99      3899569.74     10026500.44
#Sta/Elev= 29
  4874.1   87.29  4876.6   87.29  4884.2   87.16  4894.2   84.45  4904.2   81.06
  4914.2   77.61  4924.2   73.84  4929.972.10159  4934.2   70.79  4944.2   69.68
  4954.2   69.24  4964.2   68.69  4974.2   68.69  4984.2   68.23  4985.4   68.01
  4985.9   67.51  5002.5   67.51    5003   68.01  5004.2   68.57  5024.2   68.89
  5034.2   70.22  5044.2   72.18  5054.2   75.88  5064.2   79.53  5074.2   83.04
  5084.2   86.29  5094.2   87.89  5101.4    86.9  5103.6    86.9
#Mann= 3 , 0 , 0
  4874.1     .11       0  4929.9     .03       0  5044.2     .11       0
Bank Sta=4929.9,5044.2
XS Rating Curve= 0 ,0
Exp/Cntr=0.3,0.1

Type RM Length L Ch R = 1 ,5864    ,563,563,563
BEGIN DESCRIPTION:
Crystal Creek 002 8.0
END DESCRIPTION:
XS GIS Cut Line= 2
      3899006.07     10026271.01      3899008.52     10026487.99
#Sta/Elev= 28
  4873.4   85.96  4875.9   85.96  4883.5   86.02  4893.5   83.71  4903.5   80.46
  4913.5   76.47  4923.5   72.79  4929.5  70.786  4933.5   69.45  4943.5   68.23
  4953.5   67.98  4963.5   68.19  4973.5   68.26  4983.5    67.8  4993.5   67.55
  4994.7   67.47  4995.2   66.97  5011.8   66.97  5012.3   67.47  5013.5   67.97
  5023.5   68.37  5033.5   70.84  5043.5   74.49  5053.5   77.85  5063.5   80.85
  5073.5   84.17  5083.5   86.71  5090.4   86.67
#Mann= 3 , 0 , 0
  4873.4     .11       0  4929.5     .03       0  5033.5     .11       0
Bank Sta=4929.5,5033.5
XS Rating Curve= 0 ,0
Exp/Cntr=0.3,0.1

Type RM Length L Ch R = 1 ,5301    ,680,680,680
BEGIN DESCRIPTION:
Crystal Creek 002 7.0
END DESCRIPTION:
XS GIS Cut Line= 2
      3898516.48     10026259.27      3898517.65     10026466.97
#Sta/Elev= 26
  4883.5   78.91  4886.9   78.91  4895.3   79.13  4905.3   78.27  4915.3   75.59
  4925.3    72.2  4944.166.82312  4945.3   66.48  4955.3   65.83  4965.3   65.81
  4975.3   65.85  4985.3   65.55  4986.5   64.23    4987   63.73  5003.7   63.73
  5004.2   64.23  5005.3   64.43  5015.3   65.05  5025.3   65.52  5035.3   65.63
  5045.3   66.79  5055.3   69.88  5065.3   72.58  5075.3   74.93  5085.3    76.8
  5091.2    76.4
#Mann= 3 , 0 , 0
  4883.5     .11       0  4944.1     .03       0  5045.3     .11       0
Bank Sta=4944.1,5045.3
XS Rating Curve= 0 ,0
Exp/Cntr=0.3,0.1

Type RM Length L Ch R = 1 ,4621    ,924,924,924
BEGIN DESCRIPTION:
Crystal Creek 002 6.0
END DESCRIPTION:
XS GIS Cut Line= 2
      3897903.08     10026245.17      3897893.53     10026462.66
#Sta/Elev= 29
  4898.6   71.62  4901.6   70.39  4906.6   70.45  4914.5   67.92  4924.5   65.23
  4928.963.80883  4934.5      62  4944.5    60.7  4954.6   61.27  4964.6   61.09
  4974.6   60.14  4975.7   59.46  4976.2   58.96  4992.9   58.96  4993.4   59.46
  4994.6   59.66  5004.6   60.26  5014.6   61.92  5021.163.80175  5034.6   67.71
  5044.6   70.28  5054.7   71.46  5064.7   71.25  5074.7   70.72  5084.7   70.03
  5094.7   70.55  5104.7   70.54    5113   71.13  5116.3   71.13
#Mann= 3 , 0 , 0
  4898.6     .11       0  4928.9     .03       0  5021.1     .11       0
Bank Sta=4928.9,5021.1
XS Rating Curve= 0 ,0
Exp/Cntr=0.3,0.1