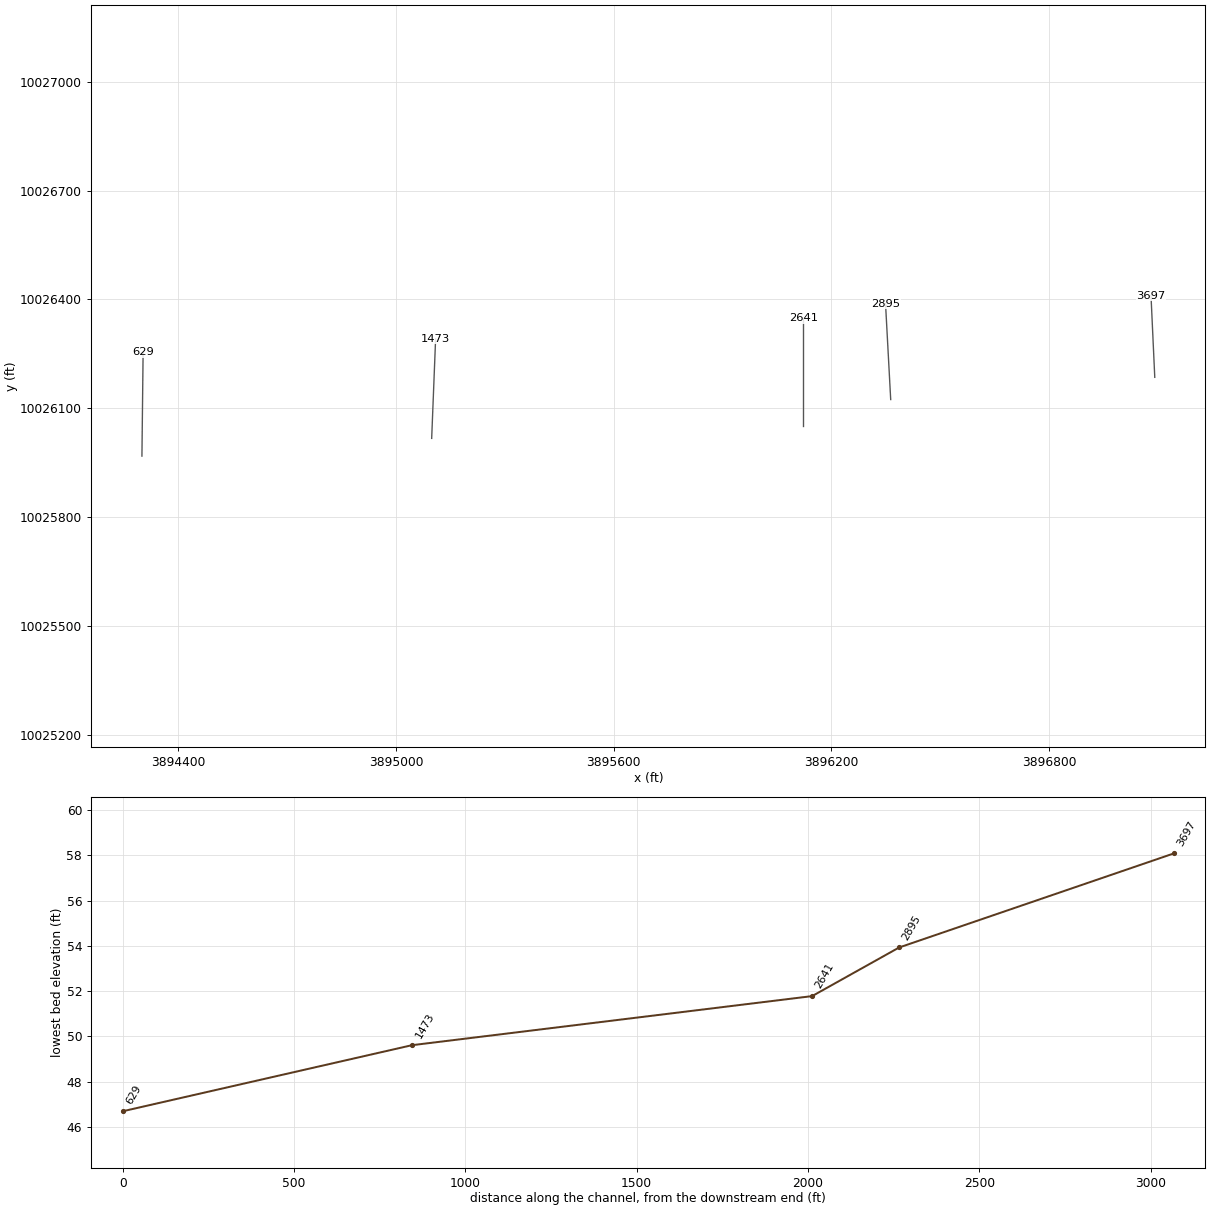
HEC-RAS study Crystal Creek 002.prj: Crystal Creek 002 Base Level Engineering

--- Crystal Creek 002.g01 (geometry) --- (continued)

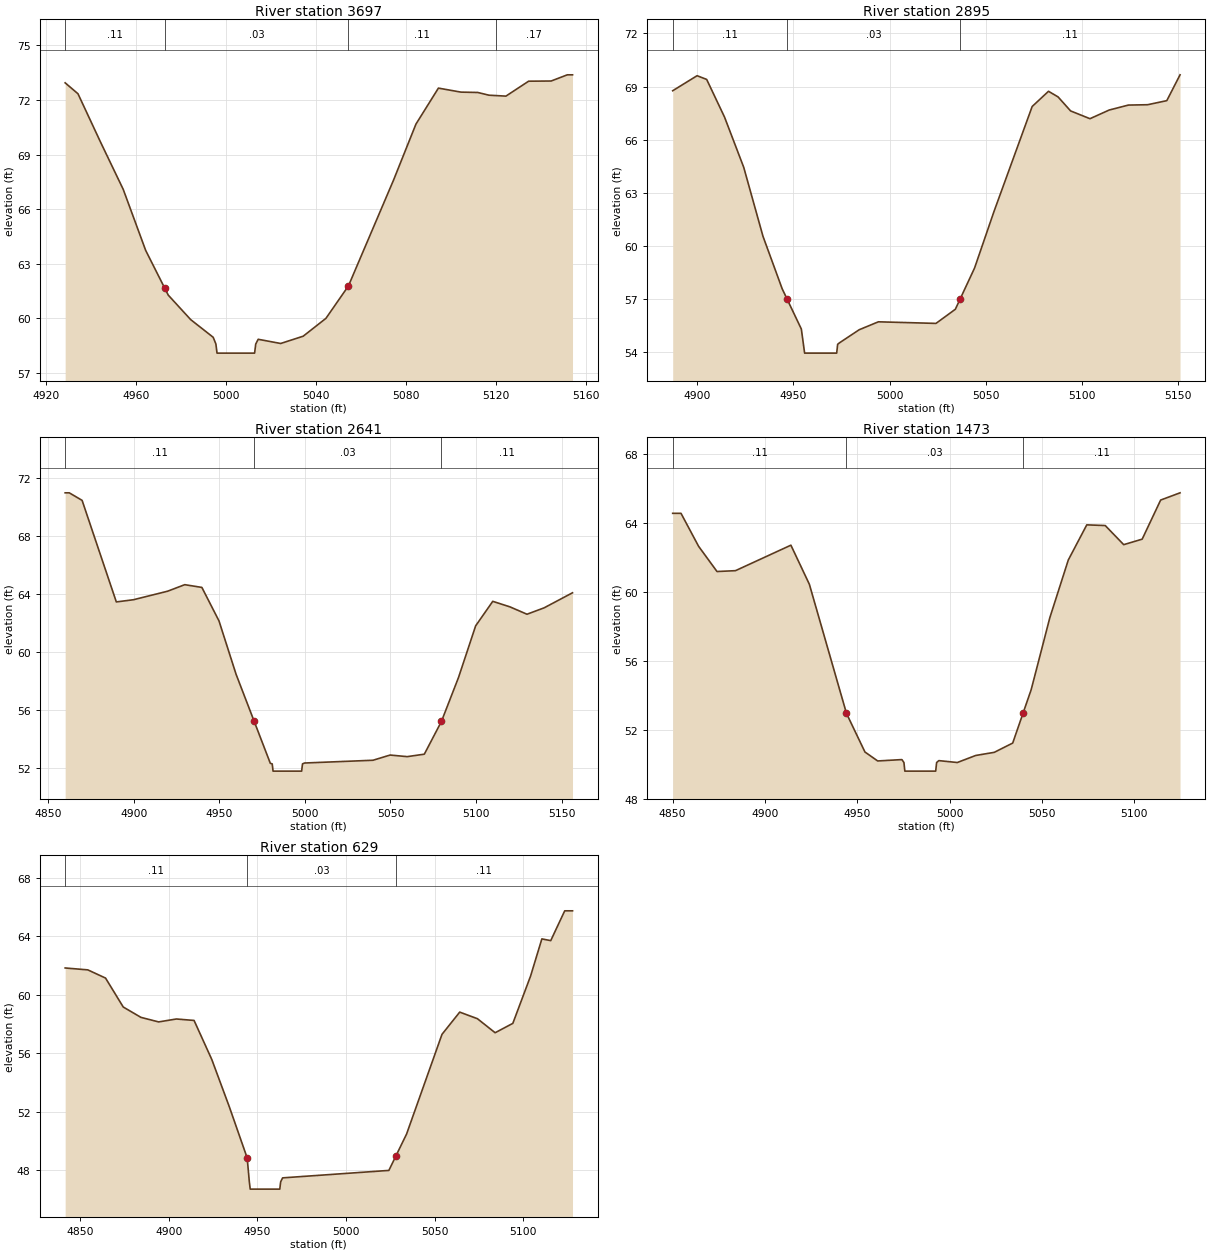
Type RM Length L Ch R = 1 ,3697    ,802,802,802
BEGIN DESCRIPTION:
Crystal Creek 002 5.0
END DESCRIPTION:
XS GIS Cut Line= 2
      3897091.44     10026185.34      3897081.03      10026410.6
#Sta/Elev= 30
  4928.4   72.94  4934.1   72.34  4944.1   69.69  4954.2   67.09  4964.2   63.73
  4972.7 61.6475  4974.2   61.28  4984.2   59.93  4994.2   58.96  4995.4   58.59
  4995.9   58.09  5012.6   58.09  5013.1   58.59  5014.2   58.85  5024.2   58.62
  5034.2   59.02  5044.3      60  5054.3   61.78  5074.3   67.58  5084.3   70.67
  5094.3   72.65  5104.3   72.43  5111.8   72.41  5116.8   72.26  5119.9   72.24
  5124.3   72.21  5134.4   73.03  5144.4   73.04  5151.6   73.38  5153.9   73.38
#Mann= 4 ,-1 , 0
  4928.4     .11       0  4972.7     .03       0  5054.3     .11       0
  5119.9     .17       0
Bank Sta=4972.7,5054.3
XS Rating Curve= 0 ,0
Exp/Cntr=0.3,0.1

Type RM Length L Ch R = 1 ,2895    ,254,254,254
BEGIN DESCRIPTION:
Crystal Creek 002 4.0
END DESCRIPTION:
XS GIS Cut Line= 2
      3896363.58     10026124.13      3896349.35     10026387.94
#Sta/Elev= 30
  4887.1   68.76  4899.8   69.61  4904.8    69.4  4914.1   67.27  4924.1   64.43
  4934.1   60.54  4944.1   57.57 4946.5457.01369  4954.1   55.29  4955.8   53.93
  4972.5   53.93    4973   54.43  4974.2   54.53  4984.2   55.25  4994.2    55.7
  5024.2   55.61  5034.3   56.41 5036.8657.00649  5044.3   58.74  5054.3    61.9
  5074.3   67.87  5082.8   68.73  5087.8   68.41  5094.3   67.62  5104.4   67.18
  5114.4   67.67  5124.4   67.95  5134.4   67.97  5144.4    68.2  5151.3   69.66
#Mann= 3 , 0 , 0
  4887.1     .11       0 4946.54     .03       0 5036.86     .11       0
Bank Sta=4946.54,5036.86
XS Rating Curve= 0 ,0
Exp/Cntr=0.3,0.1

Type RM Length L Ch R = 1 ,2641    ,1168,1168,1168
BEGIN DESCRIPTION:
Crystal Creek 002 3.0
END DESCRIPTION:
XS GIS Cut Line= 2
      3896122.69     10026051.22      3896122.69     10026347.72
#Sta/Elev= 29
  4859.9   70.99  4862.3   70.99  4869.8   70.47  4889.8   63.46  4899.8   63.61
  4919.8    64.2  4929.8   64.65  4939.8   64.46  4949.8   62.15  4959.8   58.46
 4970.3355.22721  4979.8   52.32  4980.9   52.28  4981.4   51.78  4998.1   51.78
  4998.6   52.28  4999.8   52.34  5039.8   52.53  5049.8   52.89  5059.8   52.78
  5069.8   52.95  5079.8   55.21  5089.8   58.25  5099.8   61.81  5109.8    63.5
  5119.8   63.12  5129.8   62.61  5139.8   63.05  5156.4   64.09
#Mann= 3 , 0 , 0
  4859.9     .11       0 4970.33     .03       0  5079.8     .11       0
Bank Sta=4970.33,5079.8
XS Rating Curve= 0 ,0
Exp/Cntr=0.3,0.1

Type RM Length L Ch R = 1 ,1473    ,844,844,844
BEGIN DESCRIPTION:
Crystal Creek 002 2.0
END DESCRIPTION:
XS GIS Cut Line= 2
      3895098.39     10026017.08      3895109.24     10026291.57
#Sta/Elev= 30
  4850.1   64.58  4854.6   64.58  4864.1   62.67  4874.1    61.2  4884.1   61.25
  4914.1   62.73  4924.1   60.46  4944.2   52.96  4954.2   50.72  4961.1    50.2
  4974.2   50.28  4975.3   50.11  4975.8   49.61  4992.5   49.61    4993   50.11
  4994.2   50.22  5004.2   50.11  5014.2   50.52  5024.2    50.7  5034.2   51.24
  5039.953.00691  5044.2   54.34  5054.3   58.52  5064.3   61.87  5074.3   63.91
  5084.3   63.87  5094.3   62.76  5104.3   63.08  5114.3   65.35  5124.8   65.77
#Mann= 3 , 0 , 0
  4850.1     .11       0  4944.2     .03       0  5039.9     .11       0
Bank Sta=4944.2,5039.9
XS Rating Curve= 0 ,0
Exp/Cntr=0.3,0.1

Type RM Length L Ch R = 1 ,629     ,0,0,0
BEGIN DESCRIPTION:
Crystal Creek 002 1.0
END DESCRIPTION:
XS GIS Cut Line= 2
      3894299.78     10025968.27      3894303.03     10026254.75
#Sta/Elev= 29
  4841.4   61.82  4854.2   61.69  4864.2   61.13  4874.2   59.15  4884.2   58.44
  4894.2   58.13  4904.2   58.33  4914.2   58.23  4924.2   55.56  4934.2   52.29
  4944.2   48.82  4945.4   47.19  4945.9   46.69  4962.6   46.69  4963.1   47.19
  4964.2   47.46  5024.2   47.97 5028.1248.94606  5034.2   50.46  5054.2   57.28
  5064.2    58.8  5074.2   58.35  5084.2   57.39  5094.2   58.03  5104.2   61.26
  5110.6   63.81  5115.6   63.69  5123.5   65.73  5127.9   65.73
#Mann= 3 , 0 , 0
  4841.4     .11       0  4944.2     .03       0 5028.12     .11       0
Bank Sta=4944.2,5028.12
XS Rating Curve= 0 ,0
Exp/Cntr=0.3,0.1

Chan Stop Cuts=-1
Use User Specified Reach Order=0
Composite Channel Slope=5

--- Crystal Creek 002.g10 (geometry) ---

Geom Title=Existing Conditions
Program Version=4.10

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
River Reach=Crystal Creek 00,Reach-1

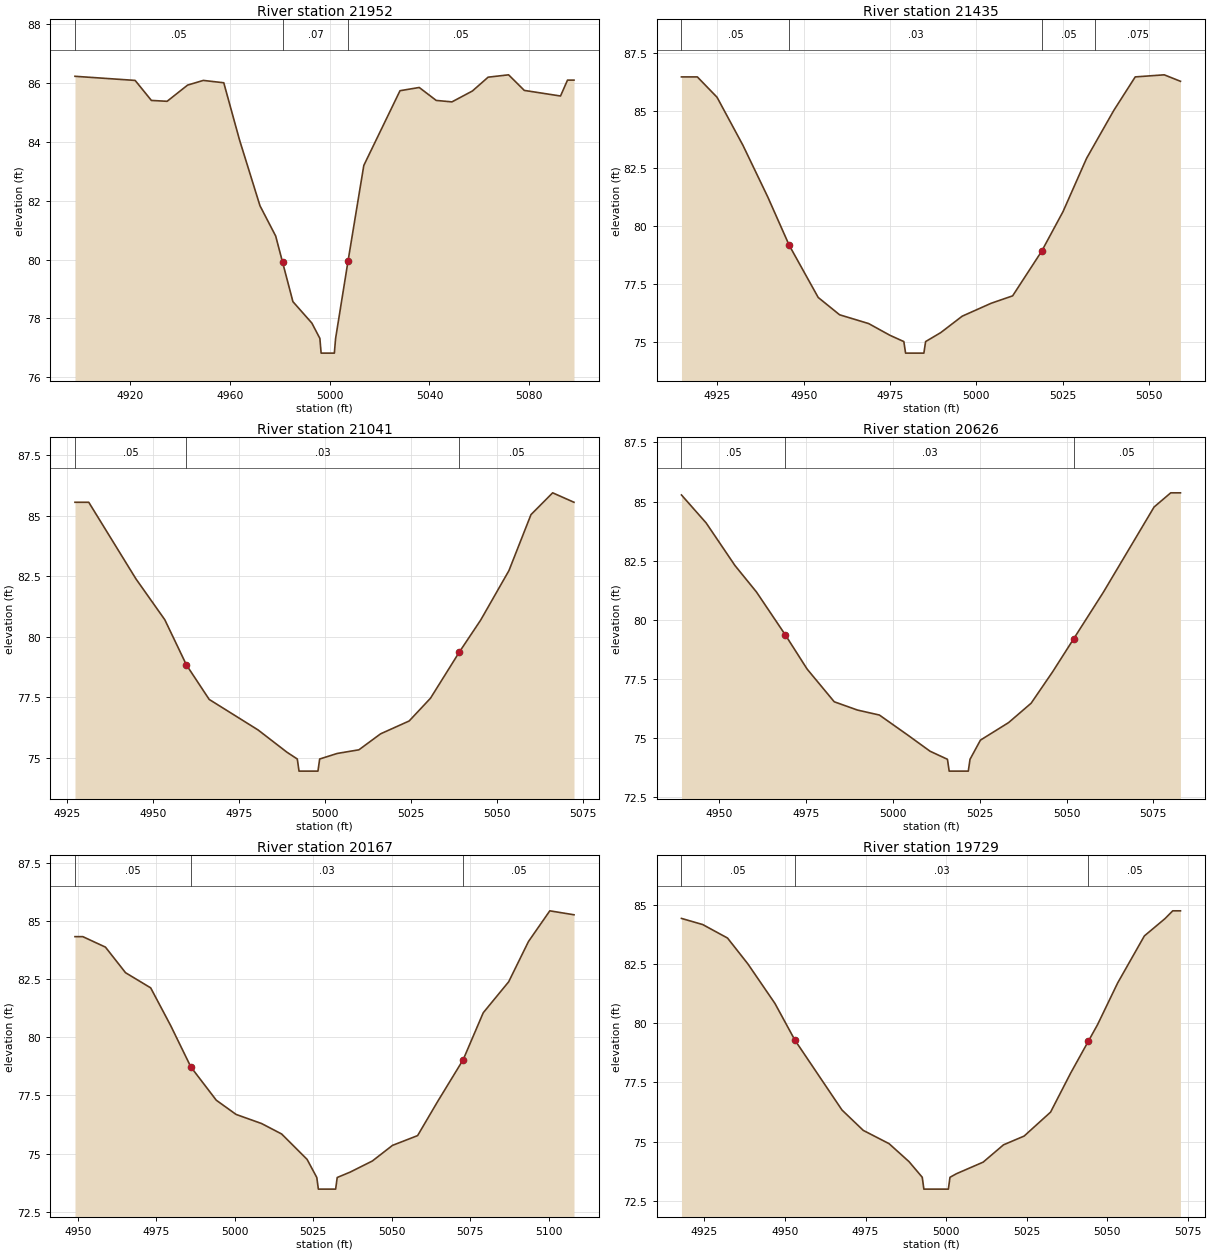
Type RM Length L Ch R = 1 ,21952   ,517,517,517
BEGIN DESCRIPTION:
Crystal Creek 002 35.0
END DESCRIPTION:
XS GIS Cut Line= 2
      3898836.88     10034984.96      3898678.79     10034862.61
#Sta/Elev= 30
    4898   86.23  4922.1   86.09  4928.6   85.41  4934.9   85.38  4943.1   85.93
  4949.4   86.09  4957.6   86.01  4963.9   84.07  4972.1   81.83  4978.4    80.8
 4981.17  79.905  4985.3   78.57  4992.9   77.84  4996.1   77.32  4996.6   76.82
  5001.9   76.82  5002.4   77.32  5007.4   79.96  5013.7    83.2  5028.2   85.74
  5035.9   85.85  5042.7   85.41    5049   85.36  5057.2   85.73  5063.5    86.2
  5071.7   86.28    5078   85.75  5092.5   85.56  5095.3    86.1  5097.9    86.1
#Mann= 3 , 0 , 0
    4898     .05       0 4981.17     .07       0  5007.4     .05       0
Bank Sta=4981.17,5007.4
XS Rating Curve= 0 ,0
Exp/Cntr=0.3,0.1

Type RM Length L Ch R = 1 ,21435   ,394,394,394
BEGIN DESCRIPTION:
Crystal Creek 002 34.0
END DESCRIPTION:
XS GIS Cut Line= 2
      3899162.13     10034581.52      3899045.99     10034495.54
#Sta/Elev= 26
  4914.6   86.46  4919.2   86.46  4924.9   85.58  4932.4    83.5  4939.6   81.26
  4945.8   79.17  4954.2   76.91  4960.4   76.16  4968.8   75.78    4975   75.27
    4979      75  4979.5    74.5  4984.8    74.5  4985.3      75  4989.7   75.39
  4995.9    76.1  5004.3   76.66  5010.5   76.98  5018.9   78.91  5025.1   80.63
  5031.9   82.93  5034.4   83.59  5039.8   85.01    5046   86.46  5054.4   86.55
  5059.1   86.27
#Mann= 4 ,-1 , 0
  4914.6     .05       0  4945.8     .03       0  5018.9     .05       0
  5034.4    .075       0
Bank Sta=4945.8,5018.9
XS Rating Curve= 0 ,0
Exp/Cntr=0.3,0.1

Type RM Length L Ch R = 1 ,21041   ,415,415,415
BEGIN DESCRIPTION:
Crystal Creek 002 33.0
END DESCRIPTION:
XS GIS Cut Line= 2
      3899409.18     10034275.09      3899292.64     10034188.81
#Sta/Elev= 23
  4927.3   85.56  4931.3   85.56    4945    82.4  4953.4   80.71  4959.7   78.84
  4966.3   77.42  4980.5   76.16  4988.9   75.24  4991.9   74.96  4992.4   74.46
  4997.9   74.46  4998.4   74.96  5003.5   75.19  5009.8   75.34  5016.1      76
  5024.4   76.53  5030.6   77.47    5039   79.38  5045.2    80.7  5053.4   82.74
  5059.8   85.05  5066.1   85.95  5072.3   85.56
#Mann= 3 , 0 , 0
  4927.3     .05       0  4959.7     .03       0    5039     .05       0
Bank Sta=4959.7,5039
XS Rating Curve= 0 ,0
Exp/Cntr=0.3,0.1

Type RM Length L Ch R = 1 ,20626   ,459,459,459
BEGIN DESCRIPTION:
Crystal Creek 002 32.0
END DESCRIPTION:
XS GIS Cut Line= 2
      3899672.94     10033956.98       3899558.4     10033870.21
#Sta/Elev= 24
  4939.1   85.28  4946.2    84.1  4954.5    82.3  4960.7   81.18    4969   79.37
  4975.3   77.92  4983.1   76.54  4989.8   76.19  4996.1   75.98  5004.4   75.12
  5010.7   74.45  5015.7   74.11  5016.2   73.61  5021.7   73.61  5022.2   74.11
  5025.2   74.92  5033.3   75.66  5039.8   76.48    5046   77.81 5052.04    79.2
  5060.6   81.17  5075.2   84.77    5080   85.37  5082.8   85.37
#Mann= 3 , 0 , 0
  4939.1     .05       0    4969     .03       0 5052.04     .05       0
Bank Sta=4969,5052.04
XS Rating Curve= 0 ,0
Exp/Cntr=0.3,0.1

Type RM Length L Ch R = 1 ,20167   ,438,438,438
BEGIN DESCRIPTION:
Crystal Creek 002 31.0
END DESCRIPTION:
XS GIS Cut Line= 2
      3899996.79     10033634.98       3899871.8     10033536.86
#Sta/Elev= 27
  4949.1   84.32  4951.6   84.32  4958.8   83.87  4965.2   82.77  4973.2   82.12
  4979.6   80.49    4986   78.72  4994.1   77.29  5000.4   76.68  5008.5   76.29
  5014.9   75.84    5023   74.75  5026.1   73.97  5026.6   73.47  5032.1   73.47
  5032.6   73.97  5036.7    74.2  5043.8   74.68  5050.2   75.35  5058.2   75.77
  5064.6   77.24  5072.7   79.03  5079.1   81.05  5087.2   82.38  5093.5   84.11
  5100.3   85.43    5108   85.26
#Mann= 3 , 0 , 0
  4949.1     .05       0    4986     .03       0  5072.7     .05       0
Bank Sta=4986,5072.7
XS Rating Curve= 0 ,0
Exp/Cntr=0.3,0.1

Type RM Length L Ch R = 1 ,19729   ,651,651,651
BEGIN DESCRIPTION:
Crystal Creek 002 30.0
END DESCRIPTION:
XS GIS Cut Line= 2
      3900323.18      10033335.5      3900198.87     10033243.25
#Sta/Elev= 27
  4917.9   84.42  4924.5   84.16  4932.2   83.59  4938.5    82.5  4946.9   80.83
  4953.1   79.28  4967.7   76.33  4974.3   75.47  4982.3   74.91  4988.5   74.15
  4992.6   73.49  4993.1   72.99  5000.7   72.99  5001.2   73.49  5003.2   73.64
  5011.5   74.13  5017.8   74.86  5024.2   75.23  5032.4   76.24  5038.6   77.88
 5044.16  79.244    5047   79.94  5053.2   81.69  5061.5   83.68  5067.9   84.41
  5070.3   84.74  5072.7   84.74
#Mann= 3 , 0 , 0
  4917.9     .05       0  4953.1     .03       0 5044.16     .05       0
Bank Sta=4953.1,5044.16
XS Rating Curve= 0 ,0
Exp/Cntr=0.3,0.1

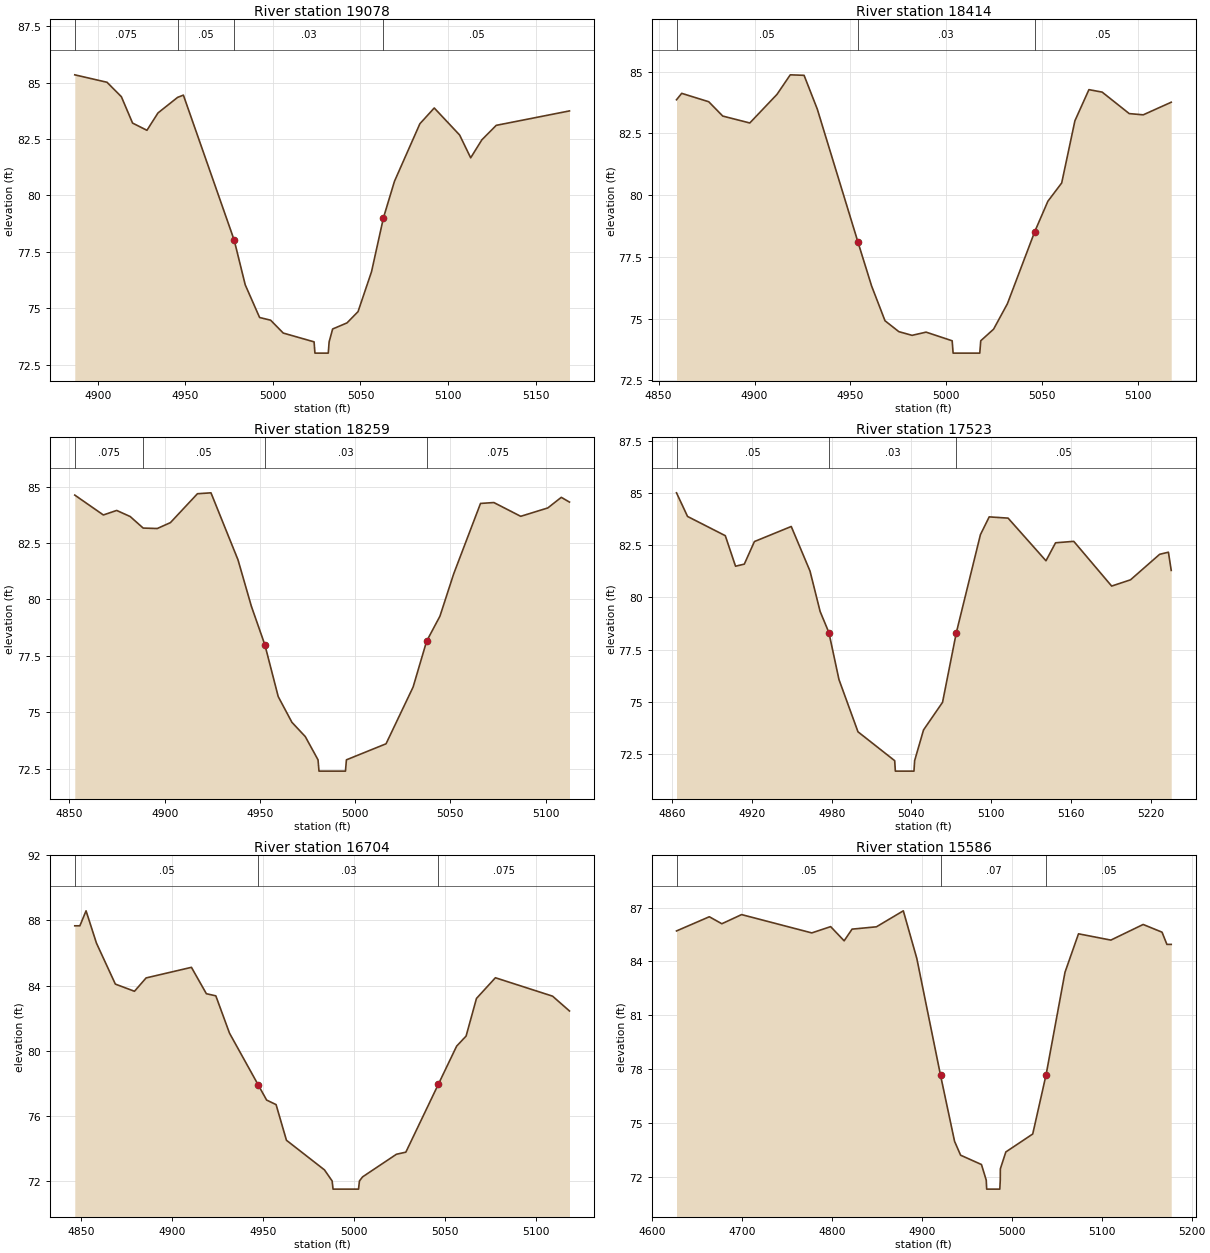
Type RM Length L Ch R = 1 ,19078   ,664,664,664
BEGIN DESCRIPTION:
Crystal Creek 002 29.0
END DESCRIPTION:
XS GIS Cut Line= 2
      3900702.24     10032813.64      3900478.21     10032641.71
#Sta/Elev= 30
  4886.9   85.35  4905.3   85.02  4913.5   84.38  4919.9   83.21  4928.1   82.89
  4934.4   83.66  4945.6   84.35  4948.9   84.45  4977.9   78.02  4984.2   76.04
  4992.4   74.59  4998.7   74.47  5005.9    73.9  5023.5   73.51    5024   73.01
  5031.6   73.01  5032.1   73.51  5034.1   74.08  5042.3   74.35  5048.6   74.85
  5056.3   76.62  5063.1   79.01  5069.4   80.63  5083.9   83.18  5092.1   83.88
  5106.6   82.68  5112.9   81.67  5119.3   82.47  5127.5   83.11  5169.3   83.75
#Mann= 4 ,-1 , 0
  4886.9    .075       0  4945.6     .05       0  4977.9     .03       0
  5063.1     .05       0
Bank Sta=4977.9,5063.1
XS Rating Curve= 0 ,0
Exp/Cntr=0.3,0.1

Type RM Length L Ch R = 1 ,18414   ,155,155,155
BEGIN DESCRIPTION:
Crystal Creek 002 28.0
END DESCRIPTION:
XS GIS Cut Line= 2
      3901176.18     10032366.58      3900989.53     10032188.61
#Sta/Elev= 30
  4859.3   83.86    4862   84.12  4876.1   83.78  4883.4    83.2  4897.5   82.92
  4911.7   84.08  4918.6   84.87  4925.8   84.85  4932.7   83.48  4953.8   78.12
    4961   76.32    4968   74.91  4975.2   74.47  4982.1   74.32  4989.4   74.45
    5003    74.1  5003.5    73.6  5017.4    73.6  5017.9    74.1  5024.6   74.57
  5031.8    75.6    5046   78.51  5052.9   79.75  5060.1   80.49    5067   83.01
  5074.3   84.27  5081.2   84.17  5095.3    83.3  5102.6   83.25  5117.2   83.76
#Mann= 3 , 0 , 0
  4859.3     .05       0  4953.8     .03       0    5046     .05       0
Bank Sta=4953.8,5046
XS Rating Curve= 0 ,0
Exp/Cntr=0.3,0.1

Type RM Length L Ch R = 1 ,18259   ,736,736,736
BEGIN DESCRIPTION:
Crystal Creek 002 27.0
END DESCRIPTION:
XS GIS Cut Line= 2
      3901293.35     10032266.74      3901107.56     10032085.28
#Sta/Elev= 30
  4852.8   84.62  4867.8   83.74  4874.8   83.94  4881.9   83.67  4888.7   83.16
  4896.1   83.14    4903    83.4  4917.2   84.68  4924.3   84.72  4938.5   81.75
  4945.5    79.7  4952.6   77.99  4959.6    75.7  4966.8   74.56  4973.8   73.93
  4980.5    72.9    4981    72.4  4994.9    72.4  4995.4    72.9  5016.2   73.61
  5030.4   76.12  5037.5   78.15  5044.5   79.26  5051.7   81.13  5065.8   84.25
  5072.8   84.29  5086.9   83.68  5101.1   84.05  5108.2   84.52  5112.5   84.31
#Mann= 4 ,-1 , 0
  4852.8    .075       0  4888.7     .05       0  4952.6     .03       0
  5037.5    .075       0
Bank Sta=4952.6,5037.5
XS Rating Curve= 0 ,0
Exp/Cntr=0.3,0.1

Type RM Length L Ch R = 1 ,17523   ,819,819,819
BEGIN DESCRIPTION:
Crystal Creek 002 26.0
END DESCRIPTION:
XS GIS Cut Line= 2
      3901894.93     10031876.14      3901650.64     10031595.46
#Sta/Elev= 30
  4863.3      85  4871.6   83.87    4900   82.95  4907.7   81.49  4914.3   81.59
  4921.9   82.67  4949.6   83.39  4963.7   81.26  4971.3   79.33  4977.9   78.32
  4985.5   76.07  4999.8   73.57  5027.4   72.19  5027.9   71.69  5041.9   71.69
  5042.4   72.19  5049.1   73.66  5063.4   74.98 5073.75  78.308  5091.9      83
  5098.5   83.85  5112.7   83.79  5141.2   81.75  5148.4   82.61  5162.1   82.68
  5190.6   80.54  5204.8   80.84  5226.7   82.06  5233.3   82.16  5235.4   81.29
#Mann= 3 , 0 , 0
  4863.3     .05       0  4977.9     .03       0 5073.75     .05       0
Bank Sta=4977.9,5073.75
XS Rating Curve= 0 ,0
Exp/Cntr=0.3,0.1

Type RM Length L Ch R = 1 ,16704   ,1118,1118,1118
BEGIN DESCRIPTION:
Crystal Creek 002 25.0
END DESCRIPTION:
XS GIS Cut Line= 2
      3902634.49     10031702.47      3902556.38     10031442.14
#Sta/Elev= 30
  4846.5   87.67  4849.3   87.67  4852.7   88.59  4858.4   86.61  4868.8   84.09
  4879.3   83.65  4885.7   84.47  4910.6   85.12  4918.8    83.5    4924   83.37
  4931.5   81.08 4947.32  77.893  4951.9   76.97  4957.1   76.69  4962.8    74.5
  4983.7   72.68  4987.9      72  4988.4    71.5  5002.4    71.5  5002.9      72
  5004.6   72.25  5023.2   73.64  5028.4   73.77  5046.3   77.95  5056.3   80.28
  5061.5    80.9  5067.2   83.21  5077.6   84.48    5109   83.35  5118.3   82.44
#Mann= 3 , 0 , 0
  4846.5     .05       0 4947.32     .03       0  5046.3    .075       0
Bank Sta=4947.32,5046.3
XS Rating Curve= 0 ,0
Exp/Cntr=0.3,0.1

Type RM Length L Ch R = 1 ,15586   ,911,911,911
BEGIN DESCRIPTION:
Crystal Creek 002 24.0
END DESCRIPTION:
XS GIS Cut Line= 2
      3903949.57     10031528.88      3903493.88     10031220.74
#Sta/Elev= 30
  4627.1    85.7  4663.6   86.49  4677.5    86.1  4699.5   86.61  4777.5   85.59
  4798.5   85.94  4813.5   85.15  4822.3    85.8  4849.4   85.93  4879.3   86.82
  4894.3   84.17  4920.7  77.657  4936.3   73.98    4943   73.21  4966.2   72.69
  4971.5   71.82    4972   71.32  4986.6   71.32  4987.1   71.82  4987.2   72.45
  4993.3   73.39  5023.2   74.39  5038.1    77.7  5059.1    83.4  5074.1   85.54
  5110.1   85.19    5146   86.06    5167   85.63  5172.4   84.95  5177.2   84.95
#Mann= 3 , 0 , 0
  4627.1     .05       0  4920.7     .07       0  5038.1     .05       0
Bank Sta=4920.7,5038.1
XS Rating Curve= 0 ,0
Exp/Cntr=0.3,0.1

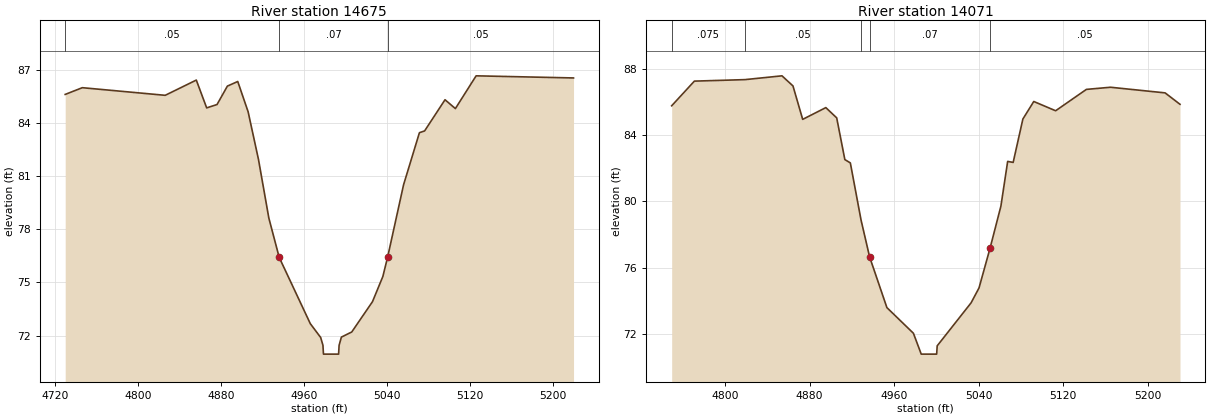
Type RM Length L Ch R = 1 ,14675   ,604,604,604
BEGIN DESCRIPTION:
Crystal Creek 002 23.0
END DESCRIPTION:
XS GIS Cut Line= 2
       3903984.3     10030422.12      3903493.88     10030413.44
#Sta/Elev= 30
  4729.7   85.61  4746.2   85.99  4826.2   85.56  4856.2   86.42  4866.2   84.85
  4876.2   85.04  4886.2   86.08  4896.2   86.34  4906.2   84.63  4916.2   81.94
  4926.2   78.63  4936.2   76.41  4966.2   72.67  4976.2   71.89  4978.4   71.45
  4978.9   70.95  4993.5   70.95    4994   71.45  4996.2   71.91  5006.2    72.2
  5026.2   73.91  5036.2   75.33  5040.9  76.449  5056.2   80.51  5071.5   83.45
  5076.5   83.55  5096.2   85.31  5106.2   84.81  5126.2   86.66  5220.2   86.54
#Mann= 3 , 0 , 0
  4729.7     .05       0  4936.2     .07       0  5040.9     .05       0
Bank Sta=4936.2,5040.9
XS Rating Curve= 0 ,0
Exp/Cntr=0.3,0.1

Type RM Length L Ch R = 1 ,14071   ,215,215,215
BEGIN DESCRIPTION:
Crystal Creek 002 22.0
END DESCRIPTION:
XS GIS Cut Line= 2
      3903988.64     10029879.58       3903524.3     10029753.73
#Sta/Elev= 30
  4749.4   85.77  4770.9   87.26  4818.7   87.35  4853.8   87.58  4864.2   86.97
  4873.4   84.95  4895.3   85.66  4905.6   85.04  4913.3   82.52  4918.5   82.32
  4928.6   78.88  4936.7   76.65  4953.1   73.58  4978.2   72.03  4985.6   70.77
  5000.2   70.77  5000.7   71.27  5032.8   73.87  5040.3   74.77  5050.7   77.16
    5061   79.71  5067.4   82.41  5072.6   82.35  5081.8   84.97  5092.1   86.03
  5112.8   85.47  5141.9   86.76  5164.7   86.89  5216.4   86.55  5230.5   85.86
#Mann= 5 ,-1 , 0
  4749.4    .075       0  4818.7     .05       0  4928.6    .075       0
  4936.7     .07       0  5050.7     .05       0
Bank Sta=4936.7,5050.7
XS Rating Curve= 0 ,0
Exp/Cntr=0.3,0.1