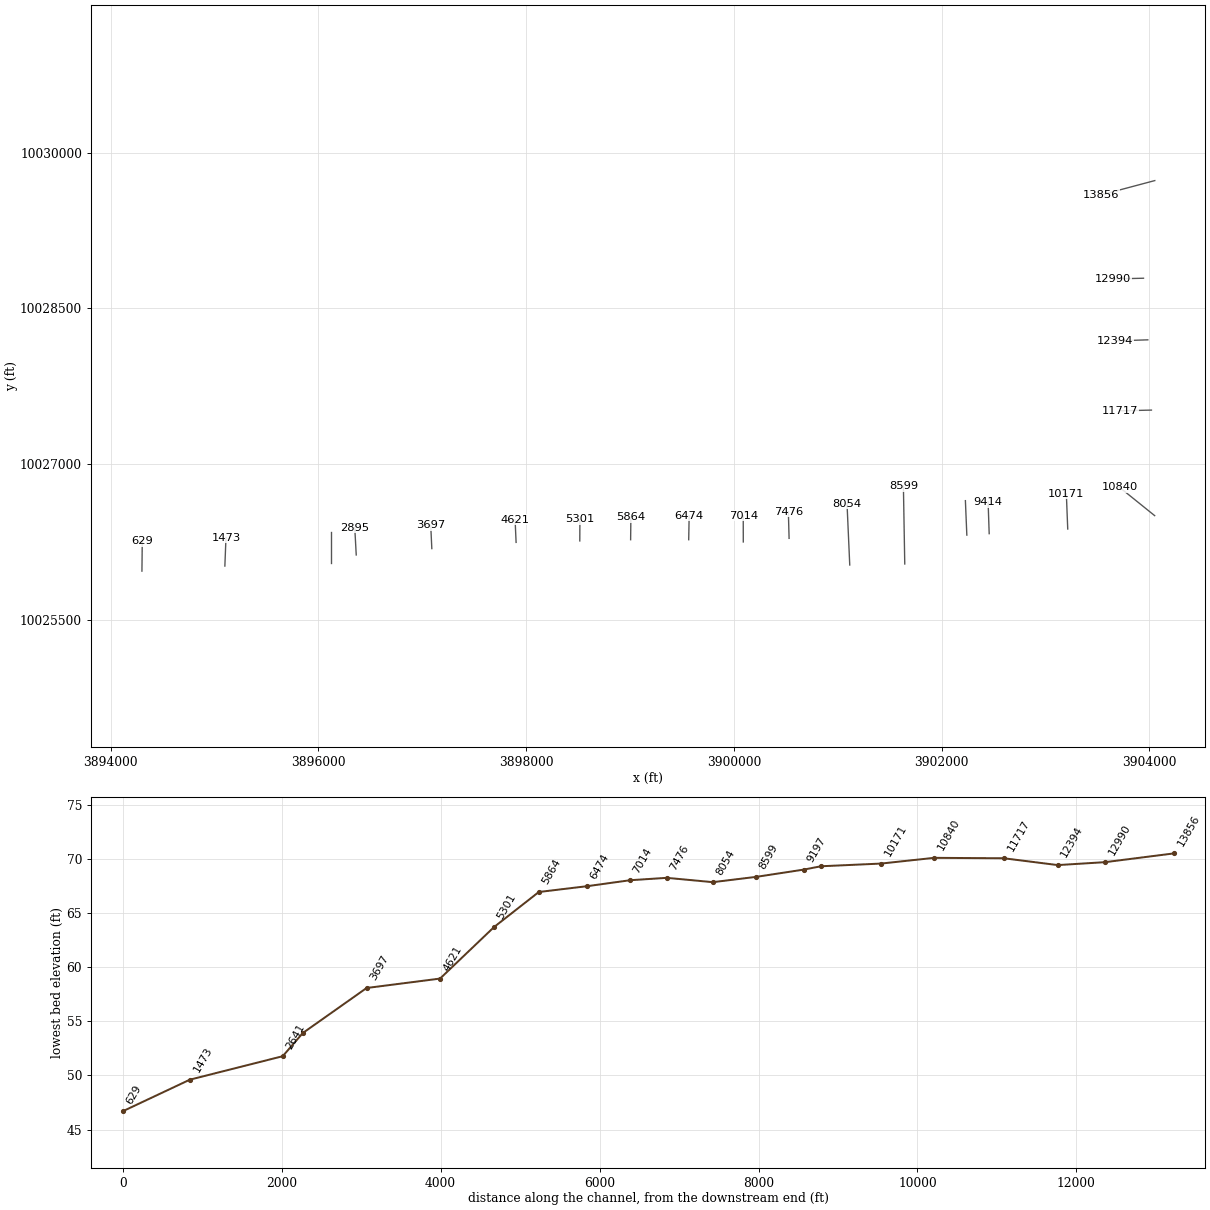
HEC-RAS study Crystal Creek 002.prj: Crystal Creek 002 Base Level Engineering

--- Crystal Creek 002.g10 (geometry) --- (continued)

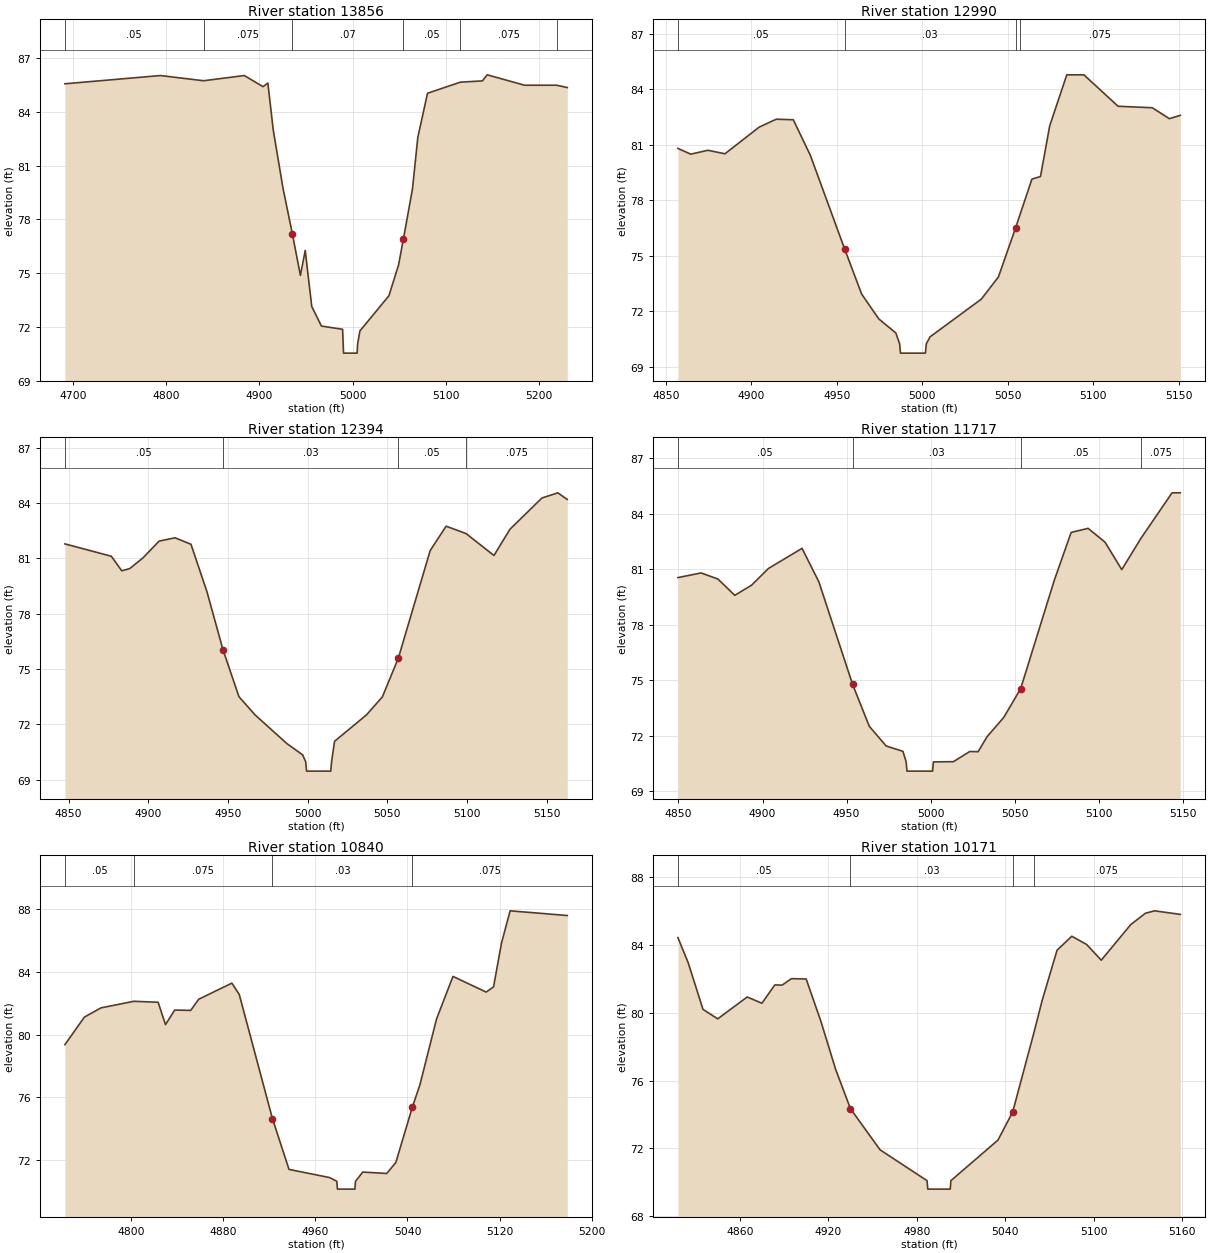
Type RM Length L Ch R = 1 ,13856   ,866,866,866
BEGIN DESCRIPTION:
Crystal Creek 002 21.0
END DESCRIPTION:
XS GIS Cut Line= 2
      3904053.81     10029732.03      3903532.91     10029593.13
#Sta/Elev= 30
  4691.3   85.57  4793.9   86.03  4840.1   85.74  4883.8   86.03  4903.9   85.41
  4909.1   85.61  4914.8   83.02  4925.2   79.78  4935.5   77.17    4944   74.88
  4949.2   76.27  4956.2   73.14  4966.6   72.05  4989.3   71.87  4990.3   70.54
  5004.9   70.54  5005.4   71.04  5007.9   71.78    5039   73.74  5049.3   75.45
 5054.58   76.91  5064.3   79.71    5070   82.57  5080.4   85.04  5115.6   85.66
  5139.3   85.73  5144.5   86.07  5184.6   85.49    5219   85.49  5230.4   85.36
#Mann= 6 ,-1 , 0
  4691.3     .05       0  4840.1    .075       0  4935.5     .07       0
 5054.58     .05       0  5115.6    .075       0    5219     .05       0
Bank Sta=4935.5,5054.58
XS Rating Curve= 0 ,0
Exp/Cntr=0.3,0.1

Type RM Length L Ch R = 1 ,12990   ,596,596,596
BEGIN DESCRIPTION:
Crystal Creek 002 20.0
END DESCRIPTION:
XS GIS Cut Line= 2
       3903945.3     10028791.05      3903651.48     10028784.14
#Sta/Elev= 30
  4857.1    80.8  4864.6   80.49  4874.6    80.7  4884.6   80.51  4904.6   81.95
  4914.6   82.38  4924.6   82.35  4934.6   80.42  4954.6   75.37  4964.6   72.92
  4974.6   71.58  4984.6   70.82  4986.8   70.23  4987.3   69.73  5001.9   69.73
  5002.4   70.23  5004.6   70.61  5034.6   72.65  5044.6   73.85  5054.6   76.49
  5057.3   77.24  5064.2   79.14  5069.2   79.28  5074.6   82.02  5084.6   84.78
  5094.6   84.78  5114.6   83.08  5134.6      83  5144.6   82.41    5151   82.59
#Mann= 4 ,-1 , 0
  4857.1     .05       0  4954.6     .03       0  5054.6     .05       0
  5057.3    .075       0
Bank Sta=4954.6,5054.6
XS Rating Curve= 0 ,0
Exp/Cntr=0.3,0.1

Type RM Length L Ch R = 1 ,12394   ,677,677,677
BEGIN DESCRIPTION:
Crystal Creek 002 19.0
END DESCRIPTION:
XS GIS Cut Line= 2
      3903986.95      10028197.3      3903671.92     10028186.91
#Sta/Elev= 30
  4847.7   81.79  4876.8   81.12  4883.4   80.33  4888.4   80.45  4896.8   81.04
  4906.8   81.94  4916.8   82.12  4926.8   81.77  4936.8    79.2  4946.9   76.04
  4956.9    73.5  4966.9   72.52  4986.9   70.96  4996.9   70.34  4998.8   69.96
  4999.3   69.46  5014.5   69.46    5015   69.96  5016.9   71.08  5036.9   72.51
  5046.9   73.49  5056.9   75.59  5076.9   81.43  5086.9   82.75  5099.4   82.35
  5116.9   81.16    5127   82.59    5147   84.28    5157   84.56  5162.9    84.2
#Mann= 4 ,-1 , 0
  4847.7     .05       0  4946.9     .03       0  5056.9     .05       0
  5099.4    .075       0
Bank Sta=4946.9,5056.9
XS Rating Curve= 0 ,0
Exp/Cntr=0.3,0.1

Type RM Length L Ch R = 1 ,11717   ,877,877,877
BEGIN DESCRIPTION:
Crystal Creek 002 18.0
END DESCRIPTION:
XS GIS Cut Line= 2
      3904021.64     10027520.21      3903723.02     10027513.27
#Sta/Elev= 30
  4849.7   80.55  4863.5    80.8  4873.5   80.47  4883.5   79.59  4893.5   80.14
  4903.5   81.04  4923.5   82.13  4933.5   80.32  4953.5   74.79  4963.5   72.51
  4973.5   71.45  4983.5   71.16  4985.4   70.59  4985.9   70.09  5001.1   70.09
  5001.6   70.59  5013.5    70.6  5023.2   71.15  5028.2   71.14  5033.5   71.95
  5043.5      73  5053.5   74.55  5073.5   80.41  5083.5   82.99  5093.6   83.21
  5103.6   82.47  5113.6   80.98    5125   82.67  5143.5   85.13  5148.4   85.13
#Mann= 4 ,-1 , 0
  4849.7     .05       0  4953.5     .03       0  5053.5     .05       0
    5125    .075       0
Bank Sta=4953.5,5053.5
XS Rating Curve= 0 ,0
Exp/Cntr=0.3,0.1

Type RM Length L Ch R = 1 ,10840   ,669,669,669
BEGIN DESCRIPTION:
Crystal Creek 002 17.0
END DESCRIPTION:
XS GIS Cut Line= 2
      3904052.87     10026502.88      3903713.43     10026776.51
#Sta/Elev= 30
  4742.7   79.36  4759.6   81.12    4774   81.71  4802.5   82.13  4823.6   82.07
    4830   80.64    4838   81.57  4851.9   81.55  4858.8   82.26  4887.6   83.29
    4894   82.57  4922.8   74.64  4937.2   71.39  4972.4   70.87  4978.7   70.63
  4979.2   70.13  4994.4   70.13  4994.9   70.63  5001.2   71.22    5022   71.13
  5029.9   71.83  5044.3   75.38  5050.8   76.79  5065.2   80.99  5079.5   83.72
  5108.3   82.72  5114.7   83.05  5121.6   85.84  5129.1   87.91  5178.7   87.61
#Mann= 4 ,-1 , 0
  4742.7     .05       0  4802.5    .075       0  4922.8     .03       0
  5044.3    .075       0
Bank Sta=4922.8,5044.3
XS Rating Curve= 0 ,0
Exp/Cntr=0.3,0.1

Type RM Length L Ch R = 1 ,10171   ,757,757,757
BEGIN DESCRIPTION:
Crystal Creek 002 16.0
END DESCRIPTION:
XS GIS Cut Line= 2
      3903215.58     10026374.12       3903202.2     10026714.65
#Sta/Elev= 30
  4817.9   84.43  4824.9   82.94  4834.9    80.2  4844.9   79.64  4864.9   80.93
  4874.9   80.56  4883.6   81.64  4888.6   81.63  4894.9   82.01  4904.9   81.99
  4914.9   79.49  4924.9   76.66  4934.9   74.35    4955   71.92  4986.9    70.1
  4987.4    69.6  5002.6    69.6  5003.1    70.1    5035   72.49    5045   74.15
  5059.3   78.79    5065   80.73  5075.1   83.69  5085.1   84.51  5095.1   84.03
  5105.1    83.1  5125.1    85.2  5135.1   85.87  5141.2   86.01  5158.7    85.8
#Mann= 4 ,-1 , 0
  4817.9     .05       0  4934.9     .03       0    5045     .05       0
  5059.3    .075       0
Bank Sta=4934.9,5045
XS Rating Curve= 0 ,0
Exp/Cntr=0.3,0.1

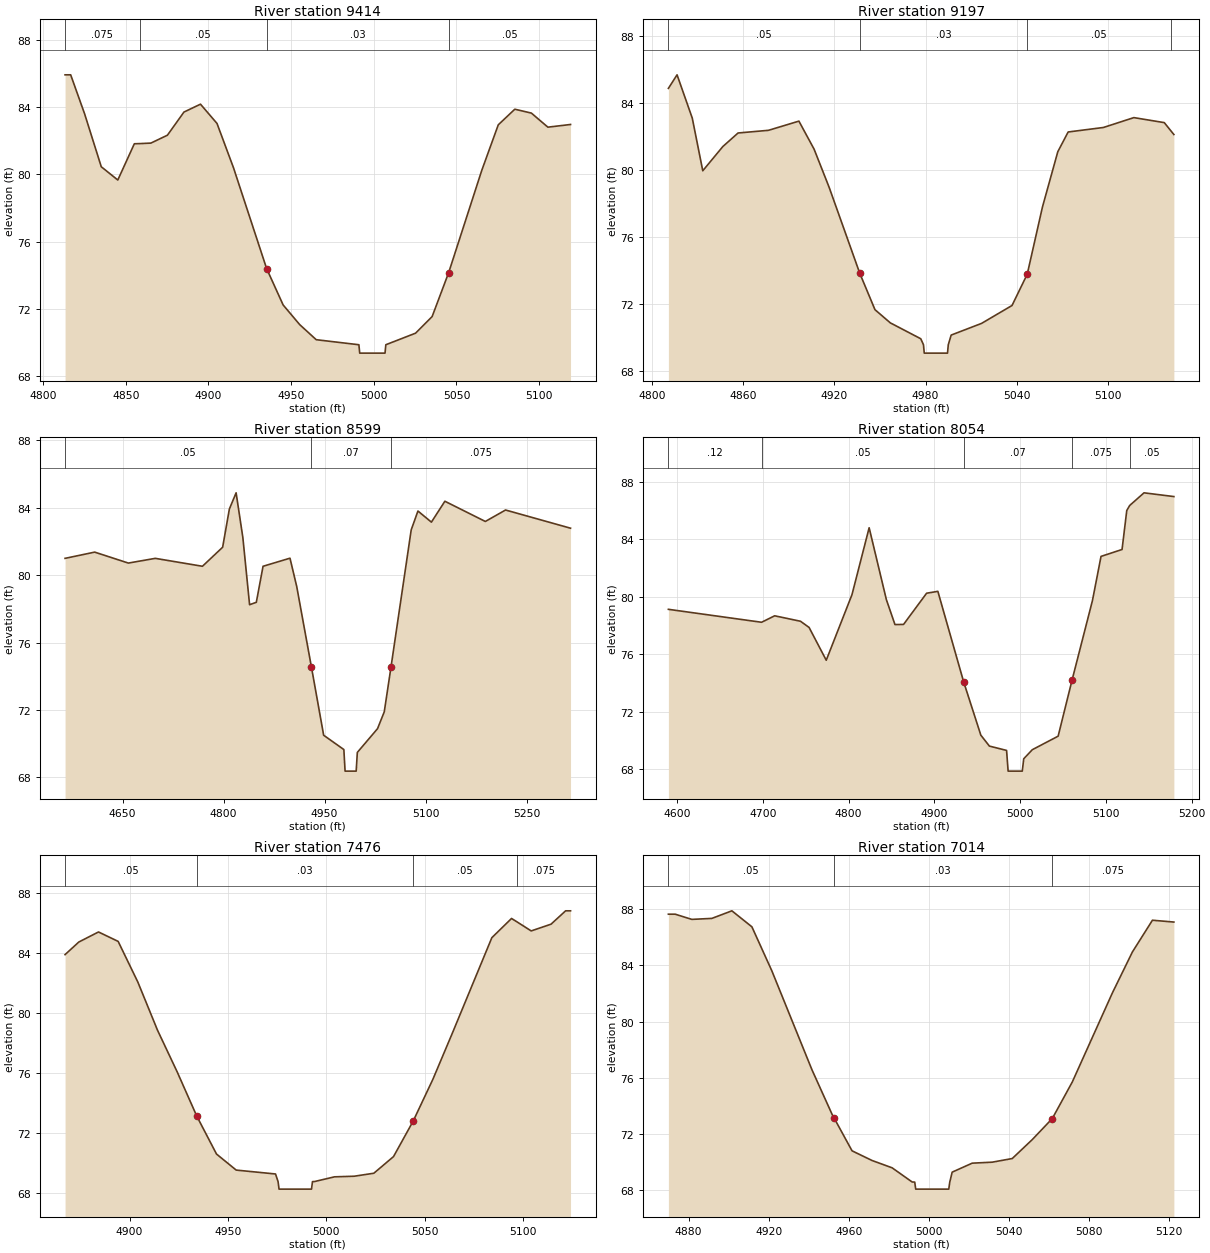
Type RM Length L Ch R = 1 ,9414    ,217,217,217
BEGIN DESCRIPTION:
Crystal Creek 002 15.0
END DESCRIPTION:
XS GIS Cut Line= 2
      3902459.15     10026329.23      3902448.73     10026634.75
#Sta/Elev= 30
  4813.3   85.94  4816.7   85.94  4825.1   83.62  4835.2   80.46  4845.2   79.67
  4855.2   81.83  4858.5   81.84  4865.2   81.87  4875.2   82.34  4885.2   83.72
  4895.2   84.19  4905.2   83.04  4915.2   80.39  4935.2   74.39  4945.2   72.22
  4955.2   71.05  4965.2   70.15    4991   69.85  4991.5   69.35  5006.8   69.35
  5007.3   69.85  5025.3   70.54  5035.3   71.53  5045.3   74.15  5065.3   80.24
  5075.3   82.96  5085.3   83.89  5095.3   83.66  5105.3   82.82    5119   82.98
#Mann= 4 ,-1 , 0
  4813.3    .075       0  4858.5     .05       0  4935.2     .03       0
  5045.3     .05       0
Bank Sta=4935.2,5045.3
XS Rating Curve= 0 ,0
Exp/Cntr=0.3,0.1

Type RM Length L Ch R = 1 ,9197    ,598,598,598
BEGIN DESCRIPTION:
Crystal Creek 002 14.0
END DESCRIPTION:
XS GIS Cut Line= 2
      3902243.87     10026315.34      3902230.04     10026647.35
#Sta/Elev= 30
  4810.9   84.88  4816.6   85.69  4826.6    83.1  4833.5   79.95  4846.7    81.4
  4856.7   82.21  4876.7   82.37  4896.7   82.92  4906.7   81.24  4916.7   78.93
  4936.7   73.82  4946.7   71.64  4956.8   70.85  4976.8    69.9  4978.6   69.54
  4979.1   69.04  4994.4   69.04  4994.9   69.54  4996.8   70.12  5016.8   70.82
  5036.8   71.89  5046.8   73.76  5056.8   77.78  5066.9   81.09  5073.7   82.27
  5096.9   82.54  5116.9   83.13  5136.9   82.83  5141.5   82.31  5143.2   82.12
#Mann= 4 ,-1 , 0
  4810.9     .05       0  4936.7     .03       0  5046.8     .05       0
  5141.5    .075       0
Bank Sta=4936.7,5046.8
XS Rating Curve= 0 ,0
Exp/Cntr=0.3,0.1

Type RM Length L Ch R = 1 ,8599    ,545,545,545
BEGIN DESCRIPTION:
Crystal Creek 002 13.0
END DESCRIPTION:
XS GIS Cut Line= 2
      3901646.06     10026037.11        3901633.      10026787.6
#Sta/Elev= 30
  4564.6      81  4608.6   81.37  4658.6   80.72  4698.6      81  4768.6   80.53
  4798.6   81.66  4808.6   83.93  4818.6   84.89  4828.6   82.24  4838.6   78.25
  4848.6   78.39  4858.6   80.53  4898.6   81.01  4908.6   79.33 4930.33  74.574
  4948.6    70.5  4978.6   69.65  4980.4   68.37  4996.9   68.37  4998.6   69.48
  5028.6   70.89  5038.6   71.89  5048.6   74.55  5078.6   82.69  5088.6   83.81
  5108.6   83.15  5128.6   84.39  5188.7   83.19  5218.7   83.87  5315.2   82.79
#Mann= 3 , 0 , 0
  4564.6     .05       0 4930.33     .07       0  5048.6    .075       0
Bank Sta=4930.33,5048.6
XS Rating Curve= 0 ,0
Exp/Cntr=0.3,0.1

Type RM Length L Ch R = 1 ,8054    ,578,578,578
BEGIN DESCRIPTION:
Crystal Creek 002 12.0
END DESCRIPTION:
XS GIS Cut Line= 2
       3901116.3     10026027.27      3901090.14     10026615.89
#Sta/Elev= 30
    4590   79.13  4698.6   78.23  4713.9   78.68    4744    78.3    4754   77.87
    4774   75.59    4804   80.15    4824    84.8  4844.1    79.8  4854.1   78.07
  4864.1   78.08    4891   80.25  4904.1   80.38  4934.1    74.1  4954.2   70.38
  4964.2   69.62  4984.2   69.32    4986   67.88  5002.5   67.88  5004.2   68.74
  5014.2   69.37  5044.3   70.31  5060.6  74.226  5084.3   79.74  5094.3   82.81
  5118.8   83.29  5124.3      86  5127.7   86.35  5144.4   87.23  5179.2   86.97
#Mann= 5 ,-1 , 0
    4590     .12       0  4698.6     .05       0  4934.1     .07       0
  5060.6    .075       0  5127.7     .05       0
Bank Sta=4934.1,5060.6
XS Rating Curve= 0 ,0
Exp/Cntr=0.3,0.1

Type RM Length L Ch R = 1 ,7476    ,462,462,462
BEGIN DESCRIPTION:
Crystal Creek 002 11.0
END DESCRIPTION:
XS GIS Cut Line= 2
      3900532.06     10026284.11      3900525.12     10026541.02
#Sta/Elev= 30
  4867.2   83.92  4874.2   84.76  4884.2   85.43  4894.2    84.8  4904.2   82.09
  4914.2   78.88  4924.2    76.1  4934.2   73.14  4944.2   70.62  4954.2   69.55
  4974.2   69.29  4975.5   68.78    4976   68.28  4992.5   68.28    4993   68.78
  4994.2   68.79  5004.2    69.1  5014.2   69.14  5024.2   69.34  5034.2   70.45
  5044.2   72.82  5054.2    75.6  5064.2   78.71  5084.2   85.05  5094.2   86.33
  5096.9   86.11  5104.2    85.5  5114.3   85.95  5121.7   86.84  5124.2   86.84
#Mann= 4 ,-1 , 0
  4867.2     .05       0  4934.2     .03       0  5044.2     .05       0
  5096.9    .075       0
Bank Sta=4934.2,5044.2
XS Rating Curve= 0 ,0
Exp/Cntr=0.3,0.1

Type RM Length L Ch R = 1 ,7014    ,540,540,540
BEGIN DESCRIPTION:
Crystal Creek 002 10.0
END DESCRIPTION:
XS GIS Cut Line= 2
      3900091.09     10026249.35      3900090.58     10026501.75
#Sta/Elev= 29
  4869.9   87.65  4873.3   87.65  4881.6   87.28  4891.6   87.35  4901.6   87.89
  4911.6   86.75  4921.6    83.6  4941.6   76.56  4951.6    73.4  4952.7  73.113
  4961.6   70.79  4971.6    70.1  4981.6   69.58  4991.6   68.57  4992.9   68.56
  4993.4   68.06  5009.9   68.06  5010.4   68.56  5011.6   69.27  5021.6   69.91
  5031.6   69.98  5041.6   70.24  5051.6   71.59  5061.6   73.09  5071.6    75.7
  5091.6   82.04  5101.6   84.96  5111.6   87.22  5122.3   87.09
#Mann= 3 , 0 , 0
  4869.9     .05       0  4952.7     .03       0  5061.6    .075       0
Bank Sta=4952.7,5061.6
XS Rating Curve= 0 ,0
Exp/Cntr=0.3,0.1

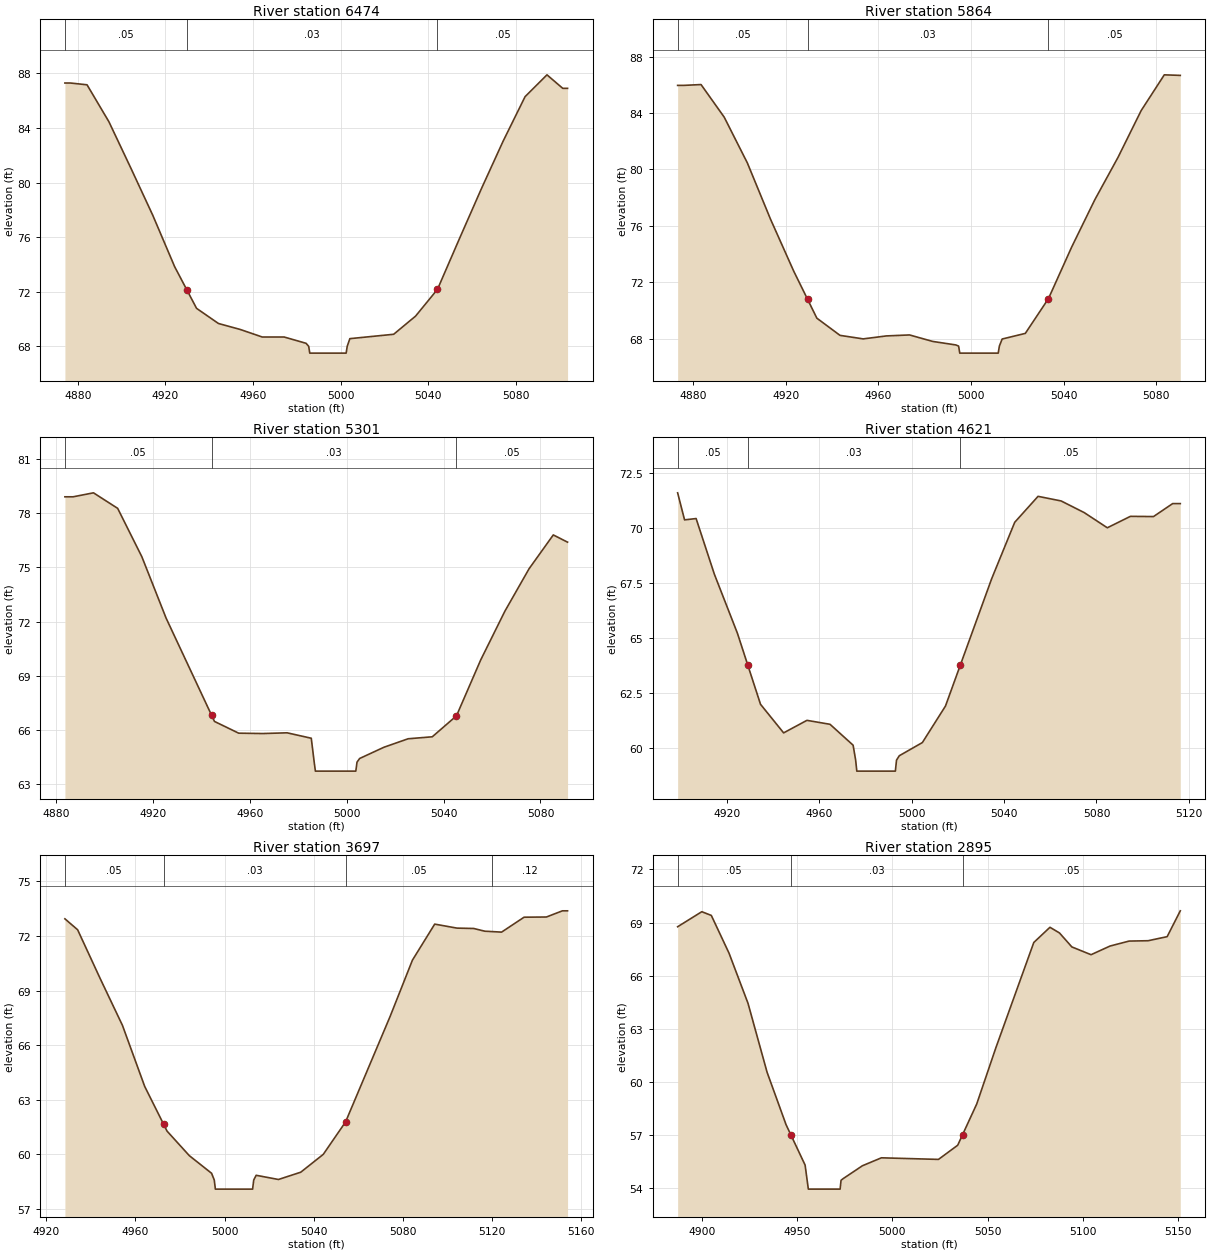
Type RM Length L Ch R = 1 ,6474    ,610,610,610
BEGIN DESCRIPTION:
Crystal Creek 002 9.0
END DESCRIPTION:
XS GIS Cut Line= 2
      3899565.33     10026270.99      3899569.74     10026500.44
#Sta/Elev= 29
  4874.1   87.29  4876.6   87.29  4884.2   87.16  4894.2   84.45  4904.2   81.06
  4914.2   77.61  4924.2   73.84  4929.9  72.102  4934.2   70.79  4944.2   69.68
  4954.2   69.24  4964.2   68.69  4974.2   68.69  4984.2   68.23  4985.4   68.01
  4985.9   67.51  5002.5   67.51    5003   68.01  5004.2   68.57  5024.2   68.89
  5034.2   70.22  5044.2   72.18  5054.2   75.88  5064.2   79.53  5074.2   83.04
  5084.2   86.29  5094.2   87.89  5101.4    86.9  5103.6    86.9
#Mann= 3 , 0 , 0
  4874.1     .05       0  4929.9     .03       0  5044.2     .05       0
Bank Sta=4929.9,5044.2
XS Rating Curve= 0 ,0
Exp/Cntr=0.3,0.1

Type RM Length L Ch R = 1 ,5864    ,563,563,563
BEGIN DESCRIPTION:
Crystal Creek 002 8.0
END DESCRIPTION:
XS GIS Cut Line= 2
      3899006.07     10026271.01      3899008.52     10026487.99
#Sta/Elev= 28
  4873.4   85.96  4875.9   85.96  4883.5   86.02  4893.5   83.71  4903.5   80.46
  4913.5   76.47  4923.5   72.79  4929.5  70.786  4933.5   69.45  4943.5   68.23
  4953.5   67.98  4963.5   68.19  4973.5   68.26  4983.5    67.8  4993.5   67.55
  4994.7   67.47  4995.2   66.97  5011.8   66.97  5012.3   67.47  5013.5   67.97
  5023.5   68.37  5033.5   70.84  5043.5   74.49  5053.5   77.85  5063.5   80.85
  5073.5   84.17  5083.5   86.71  5090.4   86.67
#Mann= 3 , 0 , 0
  4873.4     .05       0  4929.5     .03       0  5033.5     .05       0
Bank Sta=4929.5,5033.5
XS Rating Curve= 0 ,0
Exp/Cntr=0.3,0.1

Type RM Length L Ch R = 1 ,5301    ,680,680,680
BEGIN DESCRIPTION:
Crystal Creek 002 7.0
END DESCRIPTION:
XS GIS Cut Line= 2
      3898516.48     10026259.27      3898517.65     10026466.97
#Sta/Elev= 26
  4883.5   78.91  4886.9   78.91  4895.3   79.13  4905.3   78.27  4915.3   75.59
  4925.3    72.2  4944.1  66.823  4945.3   66.48  4955.3   65.83  4965.3   65.81
  4975.3   65.85  4985.3   65.55  4986.5   64.23    4987   63.73  5003.7   63.73
  5004.2   64.23  5005.3   64.43  5015.3   65.05  5025.3   65.52  5035.3   65.63
  5045.3   66.79  5055.3   69.88  5065.3   72.58  5075.3   74.93  5085.3    76.8
  5091.2    76.4
#Mann= 3 , 0 , 0
  4883.5     .05       0  4944.1     .03       0  5045.3     .05       0
Bank Sta=4944.1,5045.3
XS Rating Curve= 0 ,0
Exp/Cntr=0.3,0.1

Type RM Length L Ch R = 1 ,4621    ,924,924,924
BEGIN DESCRIPTION:
Crystal Creek 002 6.0
END DESCRIPTION:
XS GIS Cut Line= 2
      3897903.08     10026245.17      3897893.53     10026462.66
#Sta/Elev= 29
  4898.6   71.62  4901.6   70.39  4906.6   70.45  4914.5   67.92  4924.5   65.23
  4928.9  63.809  4934.5      62  4944.5    60.7  4954.6   61.27  4964.6   61.09
  4974.6   60.14  4975.7   59.46  4976.2   58.96  4992.9   58.96  4993.4   59.46
  4994.6   59.66  5004.6   60.26  5014.6   61.92  5021.1  63.802  5034.6   67.71
  5044.6   70.28  5054.7   71.46  5064.7   71.25  5074.7   70.72  5084.7   70.03
  5094.7   70.55  5104.7   70.54    5113   71.13  5116.3   71.13
#Mann= 3 , 0 , 0
  4898.6     .05       0  4928.9     .03       0  5021.1     .05       0
Bank Sta=4928.9,5021.1
XS Rating Curve= 0 ,0
Exp/Cntr=0.3,0.1

Type RM Length L Ch R = 1 ,3697    ,802,802,802
BEGIN DESCRIPTION:
Crystal Creek 002 5.0
END DESCRIPTION:
XS GIS Cut Line= 2
      3897091.44     10026185.34      3897081.03      10026410.6
#Sta/Elev= 30
  4928.4   72.94  4934.1   72.34  4944.1   69.69  4954.2   67.09  4964.2   63.73
  4972.7  61.648  4974.2   61.28  4984.2   59.93  4994.2   58.96  4995.4   58.59
  4995.9   58.09  5012.6   58.09  5013.1   58.59  5014.2   58.85  5024.2   58.62
  5034.2   59.02  5044.3      60  5054.3   61.78  5074.3   67.58  5084.3   70.67
  5094.3   72.65  5104.3   72.43  5111.8   72.41  5116.8   72.26  5119.9   72.24
  5124.3   72.21  5134.4   73.03  5144.4   73.04  5151.6   73.38  5153.9   73.38
#Mann= 4 ,-1 , 0
  4928.4     .05       0  4972.7     .03       0  5054.3     .05       0
  5119.9     .12       0
Bank Sta=4972.7,5054.3
XS Rating Curve= 0 ,0
Exp/Cntr=0.3,0.1

Type RM Length L Ch R = 1 ,2895    ,254,254,254
BEGIN DESCRIPTION:
Crystal Creek 002 4.0
END DESCRIPTION:
XS GIS Cut Line= 2
      3896363.58     10026124.13      3896349.35     10026387.94
#Sta/Elev= 30
  4887.1   68.76  4899.8   69.61  4904.8    69.4  4914.1   67.27  4924.1   64.43
  4934.1   60.54  4944.1   57.57 4946.54  57.014  4954.1   55.29  4955.8   53.93
  4972.5   53.93    4973   54.43  4974.2   54.53  4984.2   55.25  4994.2    55.7
  5024.2   55.61  5034.3   56.41 5036.86  57.006  5044.3   58.74  5054.3    61.9
  5074.3   67.87  5082.8   68.73  5087.8   68.41  5094.3   67.62  5104.4   67.18
  5114.4   67.67  5124.4   67.95  5134.4   67.97  5144.4    68.2  5151.3   69.66
#Mann= 3 , 0 , 0
  4887.1     .05       0 4946.54     .03       0 5036.86     .05       0
Bank Sta=4946.54,5036.86
XS Rating Curve= 0 ,0
Exp/Cntr=0.3,0.1

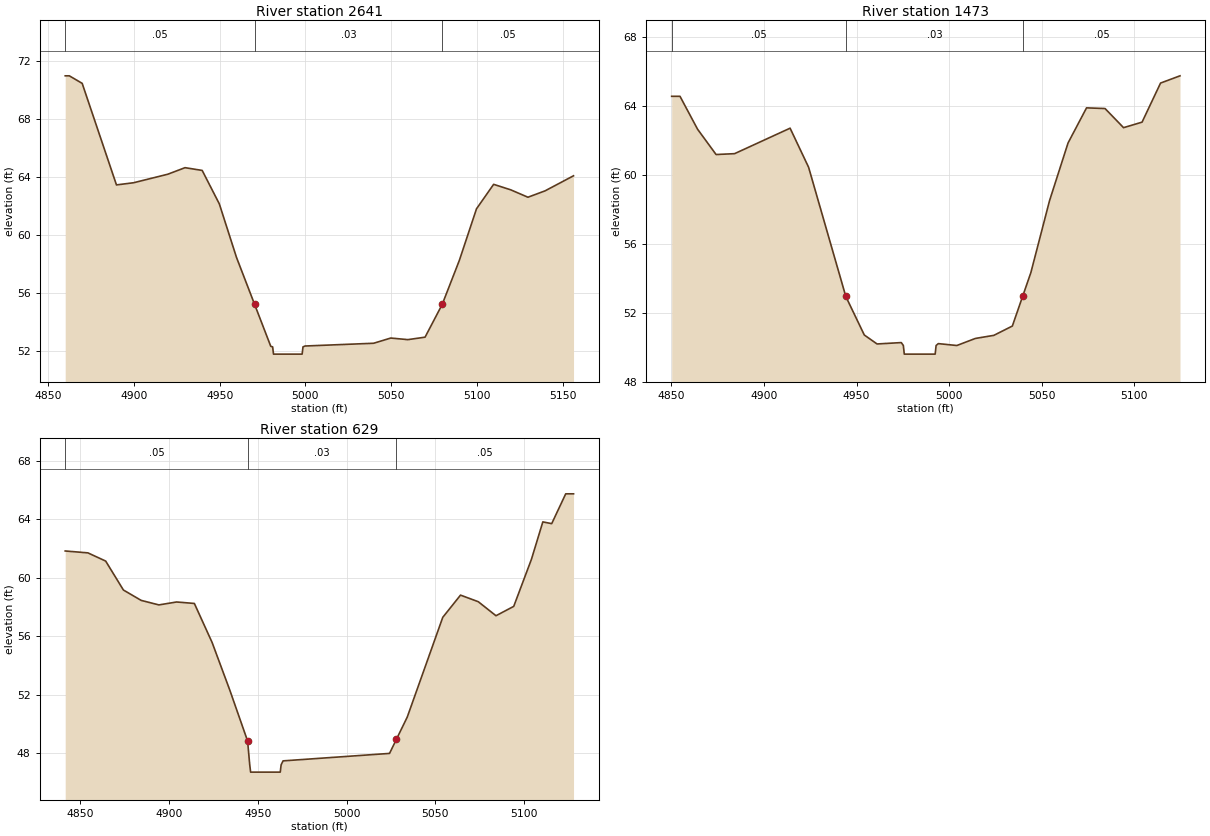
Type RM Length L Ch R = 1 ,2641    ,1168,1168,1168
BEGIN DESCRIPTION:
Crystal Creek 002 3.0
END DESCRIPTION:
XS GIS Cut Line= 2
      3896122.69     10026051.22      3896122.69     10026347.72
#Sta/Elev= 29
  4859.9   70.99  4862.3   70.99  4869.8   70.47  4889.8   63.46  4899.8   63.61
  4919.8    64.2  4929.8   64.65  4939.8   64.46  4949.8   62.15  4959.8   58.46
 4970.33  55.227  4979.8   52.32  4980.9   52.28  4981.4   51.78  4998.1   51.78
  4998.6   52.28  4999.8   52.34  5039.8   52.53  5049.8   52.89  5059.8   52.78
  5069.8   52.95  5079.8   55.21  5089.8   58.25  5099.8   61.81  5109.8    63.5
  5119.8   63.12  5129.8   62.61  5139.8   63.05  5156.4   64.09
#Mann= 3 , 0 , 0
  4859.9     .05       0 4970.33     .03       0  5079.8     .05       0
Bank Sta=4970.33,5079.8
XS Rating Curve= 0 ,0
Exp/Cntr=0.3,0.1

Type RM Length L Ch R = 1 ,1473    ,844,844,844
BEGIN DESCRIPTION:
Crystal Creek 002 2.0
END DESCRIPTION:
XS GIS Cut Line= 2
      3895098.39     10026017.08      3895109.24     10026291.57
#Sta/Elev= 30
  4850.1   64.58  4854.6   64.58  4864.1   62.67  4874.1    61.2  4884.1   61.25
  4914.1   62.73  4924.1   60.46  4944.2   52.96  4954.2   50.72  4961.1    50.2
  4974.2   50.28  4975.3   50.11  4975.8   49.61  4992.5   49.61    4993   50.11
  4994.2   50.22  5004.2   50.11  5014.2   50.52  5024.2    50.7  5034.2   51.24
  5039.9  53.007  5044.2   54.34  5054.3   58.52  5064.3   61.87  5074.3   63.91
  5084.3   63.87  5094.3   62.76  5104.3   63.08  5114.3   65.35  5124.8   65.77
#Mann= 3 , 0 , 0
  4850.1     .05       0  4944.2     .03       0  5039.9     .05       0
Bank Sta=4944.2,5039.9
XS Rating Curve= 0 ,0
Exp/Cntr=0.3,0.1

Type RM Length L Ch R = 1 ,629     ,0,0,0
BEGIN DESCRIPTION:
Crystal Creek 002 1.0
END DESCRIPTION:
XS GIS Cut Line= 2
      3894299.78     10025968.27      3894303.03     10026254.75
#Sta/Elev= 29
  4841.4   61.82  4854.2   61.69  4864.2   61.13  4874.2   59.15  4884.2   58.44
  4894.2   58.13  4904.2   58.33  4914.2   58.23  4924.2   55.56  4934.2   52.29
  4944.2   48.82  4945.4   47.19  4945.9   46.69  4962.6   46.69  4963.1   47.19
  4964.2   47.46  5024.2   47.97 5028.12  48.946  5034.2   50.46  5054.2   57.28
  5064.2    58.8  5074.2   58.35  5084.2   57.39  5094.2   58.03  5104.2   61.26
  5110.6   63.81  5115.6   63.69  5123.5   65.73  5127.9   65.73
#Mann= 3 , 0 , 0
  4841.4     .05       0  4944.2     .03       0 5028.12     .05       0
Bank Sta=4944.2,5028.12
XS Rating Curve= 0 ,0
Exp/Cntr=0.3,0.1