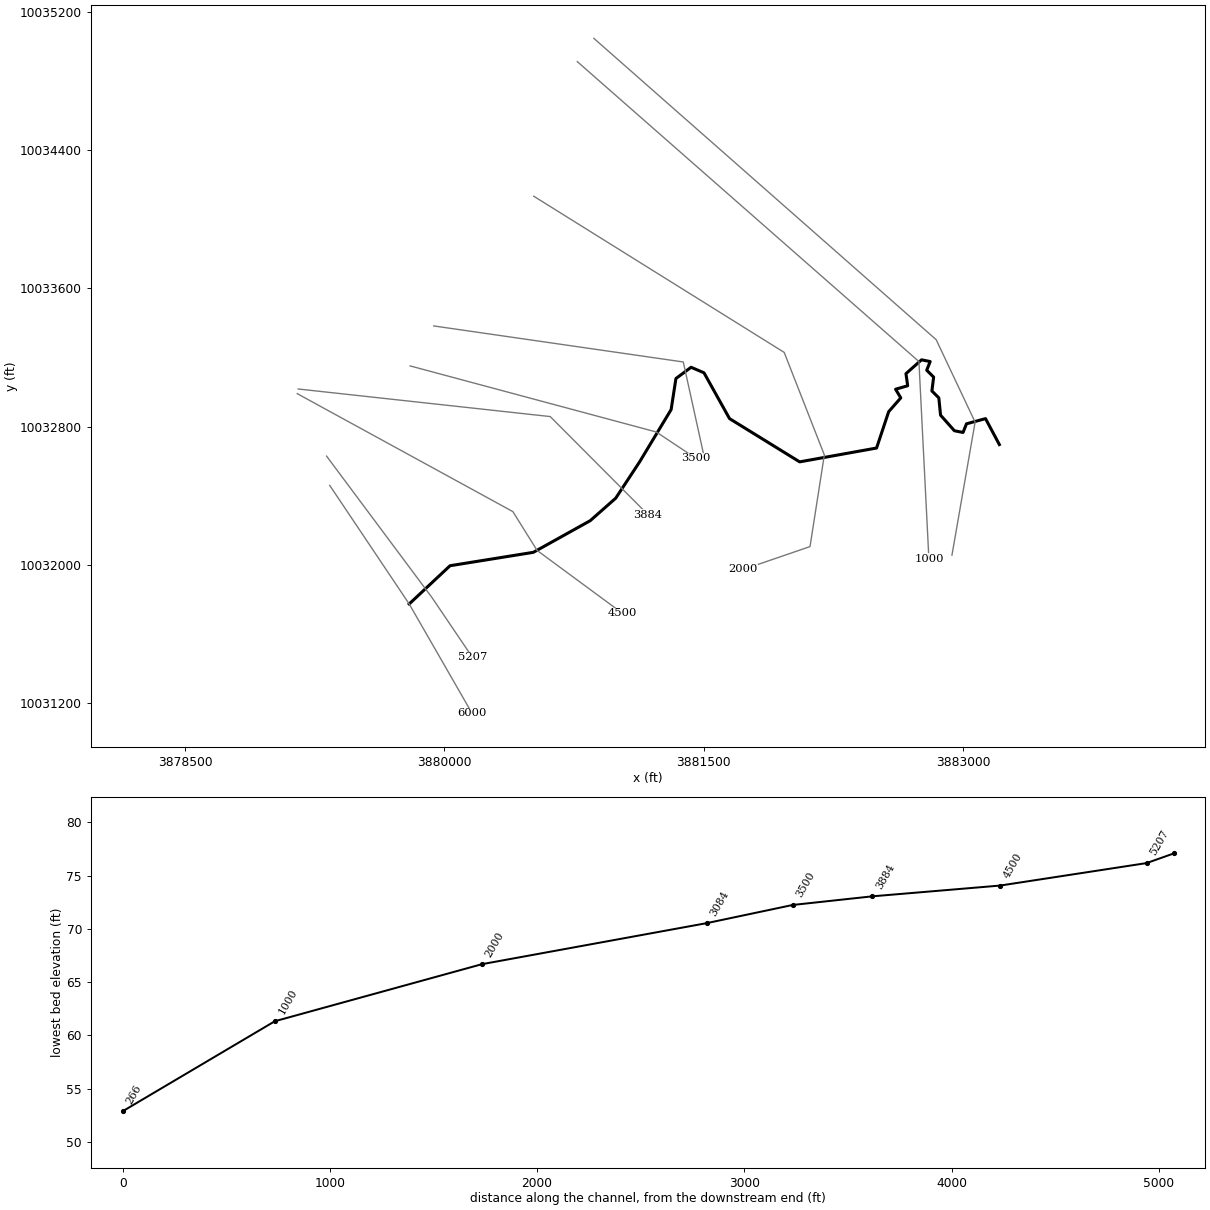
--- Crystal Creek 003.prj (project) ---

Proj Title=Crystal Creek 003 Base Level Engineering
Current Plan=p01
Default Exp/Contr=0.3,0.1
English Units
Geom File=g01
Flow File=f01
Flow File=f02
Plan File=p01
Y Axis Title=Elevation
X Axis Title(PF)=Main Channel Distance
X Axis Title(XS)=Station
BEGIN DESCRIPTION:
Crystal Creek 003
END DESCRIPTION:
DSS File=dss
DSS Export Rating Curves= 0
DSS Export Rating Curve Sorted= 0
DSS Export Volume Flow Curves= 0
DXF OffsetX= 0
DXF OffsetY= 0
DXF ScaleX= 1
DXF ScaleY= 10

--- Crystal Creek 003.p01 (plan) ---

Plan Title=Multiple Run
Program Version=4.10
Short Identifier=Multiple Run
Geom File=g01
Flow File=f01
Subcritical Flow
K Sum by GR= 0
Std Step Tol= 0.01
Critical Tol= 0.01
Num of Std Step Trials= 20
Max Error Tol= 0.3
Flow Tol Ratio= 0.001
Split Flow NTrial= 30
Split Flow Tol= 0.02
Split Flow Ratio= 0.02
Log Output Level= 0
Friction Slope Method= 1
Unsteady Friction Slope Method= 2
Unsteady Bridges Friction Slope Method= 1
Parabolic Critical Depth
Global Vel Dist= 1 , 1 , 1
Global Log Level= 0
CheckData=True
Encroach Param=-1 ,0,0, 0
BEGIN DESCRIPTION:
Multiple Run
END DESCRIPTION:
Computation Interval=1HOUR
Output Interval=1HOUR
Run HTab= 0
Run UNet= 0
Run PostProcess= 0
Run WQNet= 0
UNET Theta= 1
UNET Theta Warmup= 1
UNET ZTol= 0.02
UNET ZSATol= 0.05
UNET MxIter= 20
UNET MaxInSteps= 0
UNET DtIC= 0
UNET DtMin= 0
UNET MaxCRTS= 20
UNET WFStab= 2
UNET SFStab= 1
UNET WFX= 1
UNET SFX= 1
UNET DSS MLevel= 4
UNET DZMax Abort= 100
UNET Convert EG Bridges= 0
UNET Use Existing IB Tables=-1
UNET Froude Reduction=False
UNET Froude Limit= 1
UNET Froude Power= 10
UNET Time Slicing=0,0, 5
UNET Junction Losses=0
Instantaneous Interval=1HOUR
DSS File=dss
Write IC File= 0
Write IC File at Sim End=0
Echo Input=False
Echo Parameters=False
Echo Output=False
Write Detailed= 0
WQ AD Non Conservative
WQ ULTIMATE=-1
WQ Max Comp Step=1HOUR
WQ Output Interval=15MIN
WQ Output Selected Increments= 0
WQ Output face flow=0
WQ Output face velocity=0
WQ Output face area=0
WQ Output face dispersion=0
WQ Output cell volume=0
WQ Output cell surface area=0
WQ Output cell continuity=0
WQ Output cumulative cell continuity=0
WQ Output face conc=0
WQ Output face dconc_dx=0
WQ Output face courant=0
WQ Output face peclet=0
WQ Output face adv mass=0
WQ Output face disp mass=0
WQ Output cell mass=0
WQ Output cell source sink temp=0
WQ Output cell source sink nsm=0
WQ Output MaxMinRange=-1
WQ Daily Max Min Mean=-1
WQ Daily Range=0
WQ Daily Time=0
WQ Create Restart=0
WQ Fixed Restart=0
WQ System Summary=0
WQ Use Fixed Temperature=0
Sorting and Armoring Iterations= 10
XS Update Threshold= 0.02
Hydraulics Update Threshold= 0.02
Energy Slope Method= 1
Volume Change Method= 0
XS Weighting Method= 0
Number of US Weighted Cross Sections= 1
Number of DS Weighted Cross Sections= 1
Upstream XS Weight=0.25
Main XS Weight=0.5
Downstream XS Weight=0.25
Number of DS XS's Weighted with US Boundary= 1
Upstream Boundary Weight= 1
Weight of XSs Associated with US Boundary= 0
Number of US XS's Weighted with DS Boundary= 1
Downstream Boundary Weight= 0.5
Weight of XSs Associated with DS Boundary= 0.5
Sediment Output Level= 4
Mass or Volume Output= 0
Output Increment Type= 1
Profile and TS Output Increment= 10
XS Output Flag= 0
XS Output Increment= 10
Disregard all LS=0
Disregard all Conn=0
Disregard all Breaches=0
Disregard all Pumps=0

--- Crystal Creek 003.f01 (steady flow) ---

Flow Title=Multiple
Program Version=4.10
Number of Profiles= 7
Profile Names=10-year,25-year,50-year,1pct_min,100-year,1pct_plu,500-year
River Rch & RM=Crystal Creek 00,Reach-1         ,6000
     295     360     453     187     566    1709     908
River Rch & RM=Crystal Creek 00,Reach-1         ,5207
     295     360     453     187     566    1709     908
Boundary for River Rch & Prof#=Crystal Creek 00,Reach-1         , 1
Up Type= 0
Dn Type= 3
Dn Slope=0.01
Boundary for River Rch & Prof#=Crystal Creek 00,Reach-1         , 2
Up Type= 0
Dn Type= 3
Dn Slope=0.01
Boundary for River Rch & Prof#=Crystal Creek 00,Reach-1         , 3
Up Type= 0
Dn Type= 3
Dn Slope=0.01
Boundary for River Rch & Prof#=Crystal Creek 00,Reach-1         , 4
Up Type= 0
Dn Type= 3
Dn Slope=0.01
Boundary for River Rch & Prof#=Crystal Creek 00,Reach-1         , 5
Up Type= 0
Dn Type= 3
Dn Slope=0.01
Boundary for River Rch & Prof#=Crystal Creek 00,Reach-1         , 6
Up Type= 0
Dn Type= 3
Dn Slope=0.01
Boundary for River Rch & Prof#=Crystal Creek 00,Reach-1         , 7
Up Type= 0
Dn Type= 3
Dn Slope=0.01
DSS Import GetInterval= 0
DSS Import GetPeak= 0
DSS Import FillOption= 0

--- Crystal Creek 003.f02 (steady flow) ---

Flow Title=Orig_BLE_Flow
Program Version=4.10
Number of Profiles= 7
Profile Names=10-year,25-year,50-year,1pct_min,100-year,1pct_plu,500-year
River Rch & RM=Crystal Creek 00,Reach-1         ,6000
     295     353     394     144     435    1313     528
River Rch & RM=Crystal Creek 00,Reach-1         ,5207
     295     353     394     144     435    1313     528
Boundary for River Rch & Prof#=Crystal Creek 00,Reach-1         , 1
Up Type= 0
Dn Type= 3
Dn Slope=0.01
Boundary for River Rch & Prof#=Crystal Creek 00,Reach-1         , 2
Up Type= 0
Dn Type= 3
Dn Slope=0.01
Boundary for River Rch & Prof#=Crystal Creek 00,Reach-1         , 3
Up Type= 0
Dn Type= 3
Dn Slope=0.01
Boundary for River Rch & Prof#=Crystal Creek 00,Reach-1         , 4
Up Type= 0
Dn Type= 3
Dn Slope=0.01
Boundary for River Rch & Prof#=Crystal Creek 00,Reach-1         , 5
Up Type= 0
Dn Type= 3
Dn Slope=0.01
Boundary for River Rch & Prof#=Crystal Creek 00,Reach-1         , 6
Up Type= 0
Dn Type= 3
Dn Slope=0.01
Boundary for River Rch & Prof#=Crystal Creek 00,Reach-1         , 7
Up Type= 0
Dn Type= 3
Dn Slope=0.01
DSS Import GetInterval= 0
DSS Import GetPeak= 0
DSS Import FillOption= 0

--- Crystal Creek 003.g01 (geometry) ---

Geom Title=Existing Conditions
Program Version=4.10

River Reach=Crystal Creek 00,Reach-1
Reach XY= 30
      3879795.91     10031775.17      3880032.13     10031996.32
      3880513.91     10032073.86      3880842.59     10032256.72
      3880990.15     10032386.86      3881128.24     10032596.86
      3881310.47     10032899.08      3881338.24     10033078.76
      3881425.92     10033143.87      3881500.57     10033111.75
      3881648.24     10032846.86      3882053.52     10032596.86
      3882498.24     10032676.86      3882568.24     10032886.86
      3882638.24     10032966.86      3882608.24     10033016.86
      3882678.24     10033036.86      3882668.24     10033106.86
      3882758.24     10033186.86      3882808.24     10033176.86
      3882788.24     10033126.86      3882828.24     10033086.86
      3882818.24     10033006.86      3882858.24     10032966.86
      3882868.24     10032866.86      3882948.24     10032776.86
      3882998.24     10032766.86      3883018.24     10032816.86
      3883128.24     10032846.86      3883208.24     10032696.86

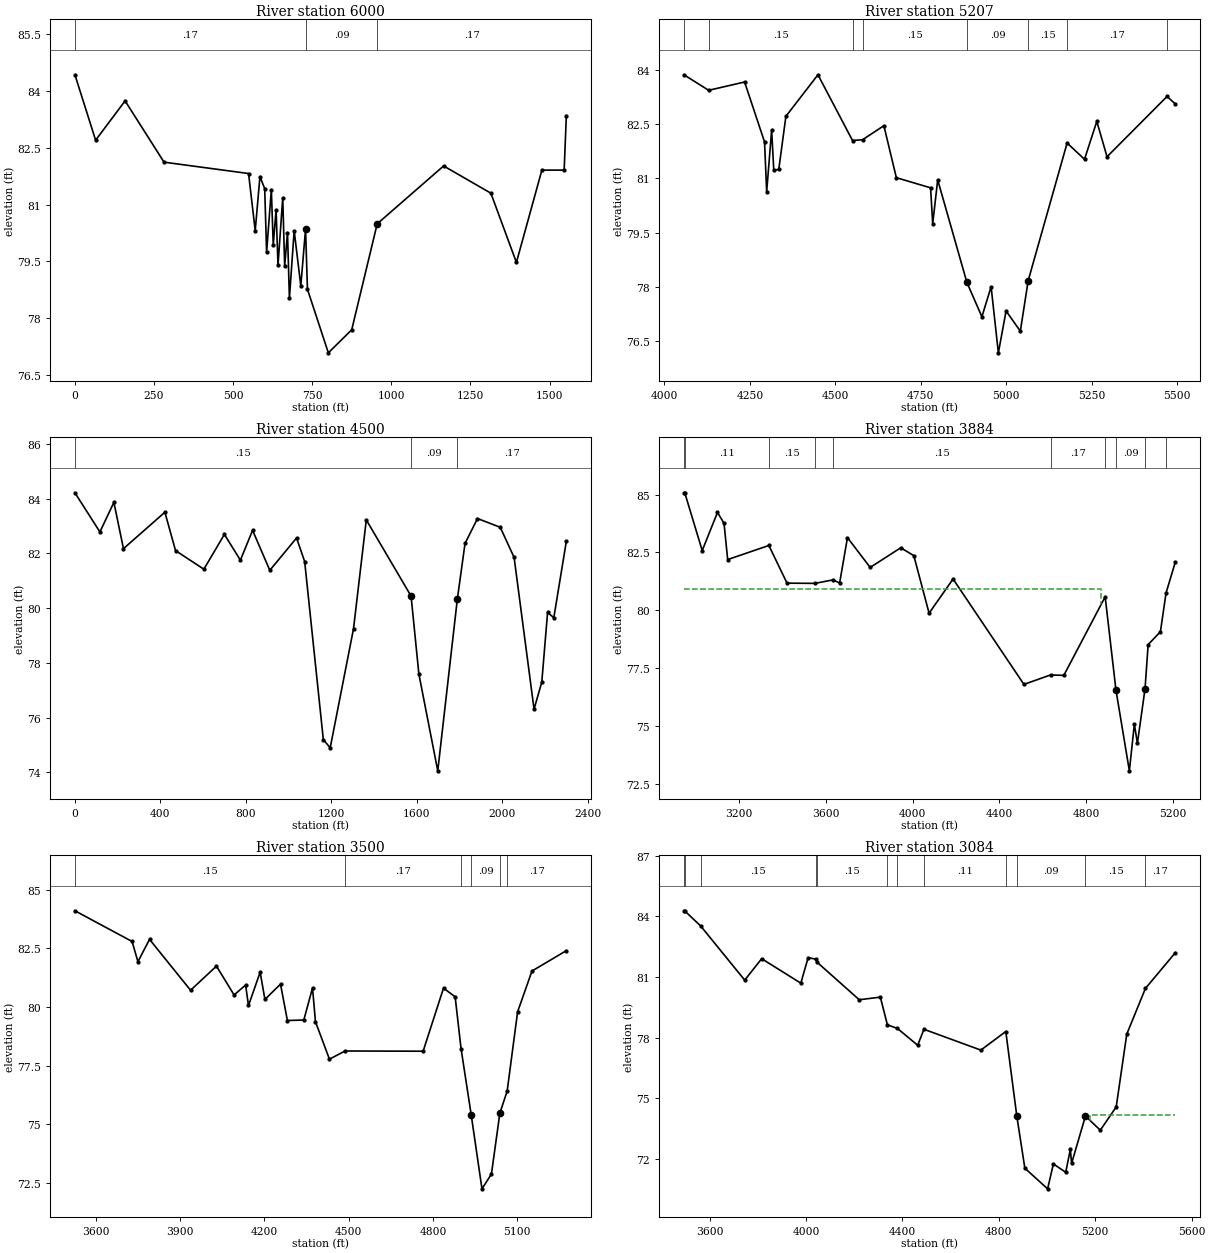
Type RM Length L Ch R = 1 ,6000    ,132,132,132
XS GIS Cut Line= 3
       3879336.6      10032460.7      3879795.98     10031775.28
       3880159.7     10031142.66
#Sta/Elev= 30
       0   84.43    65.4    82.7   158.5   83.74   281.6   82.12   548.7   81.82
   569.7   80.31   584.7   81.74   599.7   81.42   605.7   79.74   620.7   81.39
   626.7   79.93   635.7   80.86   641.7   79.39   656.7   81.18   662.8   79.37
   671.7   80.26   677.8   78.52   692.8   80.31   713.8   78.85   728.8   80.35
   734.8   78.76   800.8   77.08   874.7   77.69   955.2   80.49  1165.1   82.02
  1314.4    81.3  1395.1   79.47  1475.6   81.91    1546   81.91  1552.9   83.35
#Mann= 3 , 0 , 0
       0     .17       0   728.8     .09       0   955.2     .17       0
Bank Sta=728.8,955.2
XS Rating Curve= 0 ,0
Exp/Cntr=0.3,0.1

Type RM Length L Ch R = 1 ,5207    ,707,707,707
BEGIN DESCRIPTION:
Crystal Creek 003 10.0
END DESCRIPTION:
XS GIS Cut Line= 3
      3879318.25     10032630.13      3879927.61     10031812.45
        3880162.     10031466.06
#Sta/Elev= 30
  4057.1   83.87  4129.4   83.44  4234.5   83.67  4292.9   82.01  4299.1   80.63
  4313.7   82.34  4319.9   81.23  4334.5   81.25  4355.4   82.72  4449.2   83.87
  4550.3   82.05  4579.6   82.07  4642.1   82.46  4678.6   81.02  4778.7   80.74
    4785   79.75  4799.6   80.96    4885   78.12  4928.9   77.17  4955.9      78
  4977.1   76.17  4999.7   77.33  5041.4   76.77  5064.4   78.17  5178.3   81.98
  5229.2   81.53  5265.2   82.58  5295.1    81.6  5470.7   83.27  5495.1   83.06
#Mann= 8 ,-1 , 0
  4057.1     .11       0  4129.4     .15       0  4550.3     .17       0
  4579.6     .15       0    4885     .09       0  5064.4     .15       0
  5178.3     .17       0  5470.7     .15       0
Bank Sta=4885,5064.4
XS Rating Curve= 0 ,0
Exp/Cntr=0.3,0.1

Type RM Length L Ch R = 1 ,4500    ,616,616,616
XS GIS Cut Line= 4
      3879148.62     10032991.25      3880395.41     10032309.25
      3880535.53     10032084.83      3881029.48     10031720.95
#Sta/Elev= 30
       0   84.21   116.9   82.78   182.3   83.86   227.1   82.17   420.9    83.5
   470.7    82.1   603.2   81.42   699.3   82.69   774.2   81.75   831.2   82.84
   911.8   81.38    1037   82.56  1074.9    81.7  1162.2    75.2  1194.4    74.9
  1303.5   79.25  1363.2   83.22  1572.7   80.44  1609.3   77.59  1697.6   74.06
  1789.5   80.35  1825.2   82.36  1883.5   83.27    1990   82.95  2054.8   81.85
  2148.1   76.31  2184.3    77.3  2211.4   79.84  2240.6   79.65  2299.2   82.44
#Mann= 3 , 0 , 0
       0     .15       0  1572.7     .09       0  1789.5     .17       0
Bank Sta=1572.7,1789.5
XS Rating Curve= 0 ,0
Exp/Cntr=0.3,0.1

Type RM Length L Ch R = 1 ,3884    ,384,384,384
BEGIN DESCRIPTION:
Crystal Creek 003 8.0
END DESCRIPTION:
XS GIS Cut Line= 3
      3879154.17     10033018.18      3880611.43     10032858.73
       3881176.4     10032291.99
#Sta/Elev= 30
    2946   85.08  2949.7   85.08  3030.2   82.58  3100.6   84.23  3130.8   83.76
  3147.6   82.19  3337.5    82.8  3421.3   81.17  3550.1   81.16  3632.6   81.31
  3663.9   81.18    3700   83.14  3804.8   81.85  3945.6    82.7    4006   82.36
  4076.4   79.87    4187   81.35  4513.8   76.79  4636.9    77.2  4697.7   77.18
  4888.4   80.58  4938.1   76.55    5000   73.05    5023   75.07  5037.1   74.24
  5072.4   76.61  5086.6   78.51  5143.2   79.07  5169.3   80.75  5212.2   82.09
#Mann= 10 ,-1 , 0
    2946     .17       0  2949.7     .11       0  3337.5     .15       0
  3550.1     .11       0  3632.6     .15       0  4636.9     .17       0
  4888.4     .15       0  4938.1     .09       0  5072.4     .15       0
  5169.3     .17       0
#XS Ineff= 2 , 0
       0  4867.4   80.93               0
Permanent Ineff=
       F       F
Bank Sta=4938.1,5072.4
XS Rating Curve= 0 ,0
Exp/Cntr=0.3,0.1

Type RM Length L Ch R = 1 ,3500    ,416,416,416
BEGIN DESCRIPTION:
Crystal Creek 003 7.0
END DESCRIPTION:
XS GIS Cut Line= 3
      3879801.43     10033151.65      3881224.74      10032769.6
      3881453.29     10032617.38
#Sta/Elev= 30
  3526.3    84.1  3729.7   82.79  3750.4   81.93  3791.8   82.88  3937.7   80.71
  4029.9   81.74  4092.5   80.51  4133.5   80.93  4143.8   80.06  4185.3   81.48
  4202.2   80.32  4257.7   80.97  4282.2   79.42  4340.6   79.44  4371.6   80.81
    4382   79.37  4431.8   77.77  4487.3   78.12  4765.1   78.11  4837.6    80.8
    4879   80.43    4900   78.22  4936.2   75.39  4974.4   72.24  5008.1   72.87
  5038.1   75.47  5064.1   76.41  5101.2   79.79  5152.3   81.53  5274.6    82.4
#Mann= 6 ,-1 , 0
  3526.3     .15       0  4487.3     .17       0    4900     .15       0
  4936.2     .09       0  5038.1     .15       0  5064.1     .17       0
Bank Sta=4936.2,5038.1
XS Rating Curve= 0 ,0
Exp/Cntr=0.3,0.1

Type RM Length L Ch R = 1 ,3084    ,1084,1084,1084
BEGIN DESCRIPTION:
Crystal Creek 003 6.0
END DESCRIPTION:
XS GIS Cut Line= 3
      3879937.98     10033382.77      3881380.73     10033174.43
      3881505.73     10032606.75
#Sta/Elev= 30
  3493.5   84.28  3497.9   84.26  3562.7   83.53  3745.6   80.85  3815.9   81.91
  3978.4    80.7  4008.7   81.96  4040.3   81.89  4045.5   81.74  4220.8   79.88
  4308.4   80.01  4337.6   78.64  4379.4   78.46  4463.3   77.63  4489.2   78.42
  4725.4   77.39  4828.9   78.31  4874.3   74.15  4907.9   71.55  5002.4   70.53
  5026.3   71.76  5077.5   71.35  5096.7   72.48  5101.9   71.79  5159.4   74.13
  5220.9   73.43    5287   74.58  5330.8   78.18  5408.2   80.44  5532.5   82.21
#Mann= 12 ,-1 , 0
  3493.5     .15       0  3497.9     .11       0  3562.7     .15       0
  4040.3     .11       0  4045.5     .15       0  4337.6     .11       0
  4379.4     .17       0  4489.2     .11       0  4828.9     .15       0
  4874.3     .09       0  5159.4     .15       0  5408.2     .17       0
#XS Ineff= 2 , 0
       0                  5179.9       0   74.18
Permanent Ineff=
       F       F
Bank Sta=4874.3,5159.4
XS Rating Curve= 0 ,0
Exp/Cntr=0.3,0.1

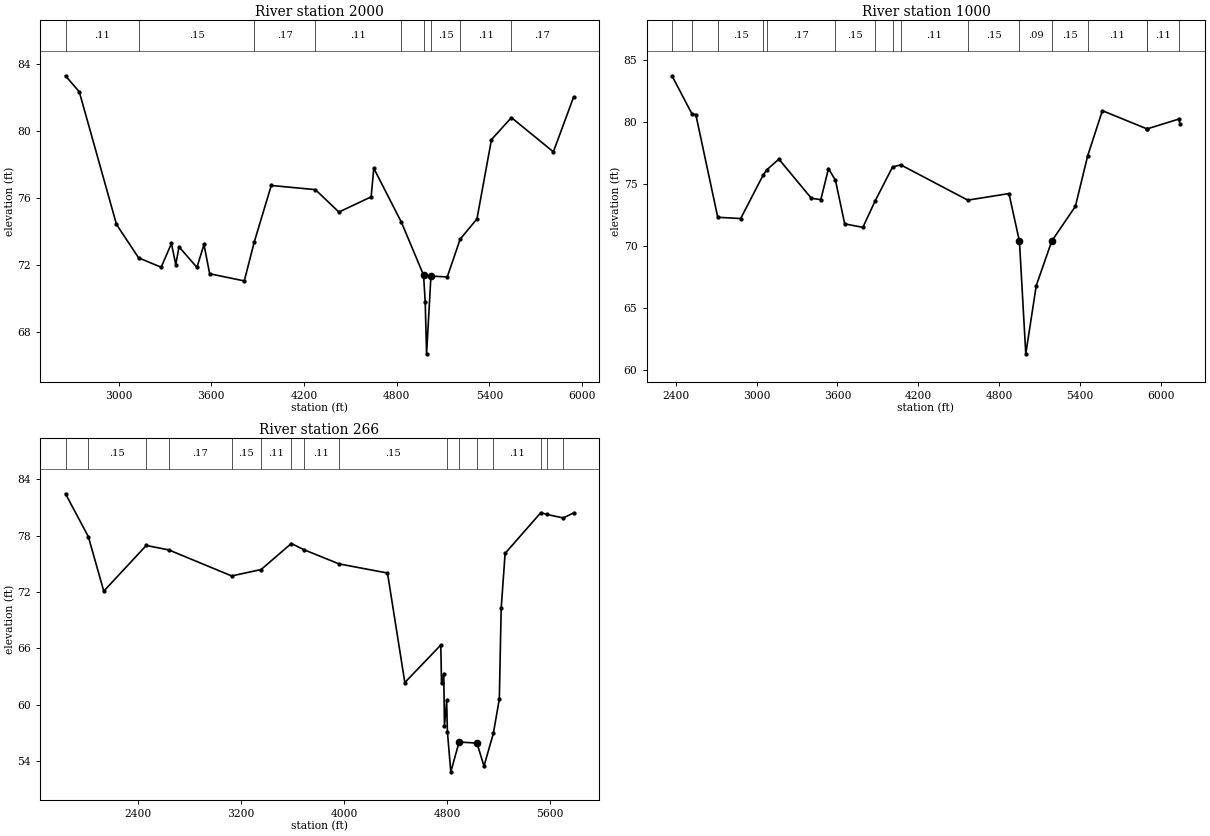
Type RM Length L Ch R = 1 ,2000    ,1000,1000,1000
BEGIN DESCRIPTION:
Crystal Creek 003 4.0
END DESCRIPTION:
XS GIS Cut Line= 5
      3880516.13     10034132.77      3881964.19     10033229.73
      3882196.34     10032636.82      3882113.49     10032106.94
      3881727.16     10031974.55
#Sta/Elev= 30
  2656.7   83.31    2746   82.35  2986.7   74.42  3129.9   72.42  3275.8   71.86
  3342.3   73.28  3370.2   72.02  3391.4   73.08  3507.3   71.85    3553   73.22
  3589.6   71.47  3813.7   71.04  3878.9   73.39  3988.4   76.75  4273.8    76.5
  4426.3   75.16  4634.8   76.07  4651.8   77.78  4830.6   74.55    4974   71.39
  4984.7   69.78  4993.5   66.68  5021.8   71.33  5127.3   71.28    5211   73.54
  5319.6   74.75  5413.4   79.49  5542.5   80.81  5814.2   78.76  5944.7   82.03
#Mann= 9 ,-1 , 0
  2656.7     .11       0  3129.9     .15       0  3878.9     .17       0
  4273.8     .11       0  4830.6     .15       0    4974     .09       0
  5021.8     .15       0    5211     .11       0  5542.5     .17       0
Bank Sta=4974,5021.8
XS Rating Curve= 0 ,0
Exp/Cntr=0.3,0.1

Type RM Length L Ch R = 1 ,1000    ,734,734,734
BEGIN DESCRIPTION:
Mapping XS 6d0336b8
END DESCRIPTION:
XS GIS Cut Line= 3
      3880767.85     10034911.07      3882743.21     10033176.86
      3882800.86     10032035.32
#Sta/Elev= 30
  2371.4    83.7  2520.4   80.62  2548.4   80.58  2711.3   72.31  2881.4   72.21
  3048.9   75.72  3077.1   76.15  3165.2   76.99  3406.2   73.84  3476.4   73.73
  3533.3   76.23  3584.9   75.29  3653.9   71.78  3788.6    71.5  3880.7   73.65
    4009   76.36  4069.9   76.53  4567.5   73.69  4873.1   74.22    4951   70.37
    4998   61.32  5075.9   66.82  5191.1    70.4  5366.3   73.19  5457.3   77.25
  5566.5   80.89  5899.3   79.42  5900.1   79.43  6132.6   80.21    6143   79.85
#Mann= 16 ,-1 , 0
  2371.4     .11       0  2520.4     .17       0  2711.3     .15       0
  3048.9     .11       0  3077.1     .17       0  3584.9     .15       0
  3880.7     .11       0    4009     .15       0  4069.9     .11       0
  4567.5     .15       0    4951     .09       0  5191.1     .15       0
  5457.3     .11       0  5899.3     .17       0  5900.1     .11       0
  6132.6     .17       0
Bank Sta=4951,5191.1
XS Rating Curve= 0 ,0
Exp/Cntr=0.3,0.1

Type RM Length L Ch R = 1 ,266     ,0,0,0
BEGIN DESCRIPTION:
Crystal Creek 003 2.0
END DESCRIPTION:
XS GIS Cut Line= 4
      3880863.58     10035045.66      3882843.01     10033303.22
      3883068.04     10032826.66      3882934.15     10032057.53
#Sta/Elev= 30
  1835.9   82.45  2013.2   77.89    2133   72.09  2462.8   76.95  2637.3   76.48
    3126   73.71  3354.6   74.39  3589.2   77.16    3687    76.5    3960   74.99
    4336   74.02  4470.7   62.37    4750   66.36  4755.5   62.27  4772.8   63.33
  4778.3    57.7  4795.5   60.47    4801   57.16  4827.6   52.87  4892.1   56.04
  5030.6   55.93  5085.2   53.48  5157.9   56.95  5204.4   60.62  5218.8   70.26
  5249.3   76.11    5527   80.45  5570.8   80.26  5700.2   79.88  5780.7   80.41
#Mann= 16 ,-1 , 0
  1835.9     .11       0  2013.2     .15       0  2462.8     .11       0
  2637.3     .17       0    3126     .15       0  3354.6     .11       0
  3589.2     .17       0    3687     .11       0    3960     .15       0
    4801     .08       0  4892.1     .06       0  5030.6     .08       0
  5157.9     .11       0    5527     .17       0  5570.8     .11       0
  5700.2     .17       0
Bank Sta=4892.1,5030.6
XS Rating Curve= 0 ,0
Exp/Cntr=0.3,0.1

Chan Stop Cuts=-1
Use User Specified Reach Order=0
Composite Channel Slope=5

--- Crystal Creek 003.g10 (geometry) ---

Geom Title=Existing Conditions
Program Version=4.10

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
River Reach=Crystal Creek 00,Reach-1

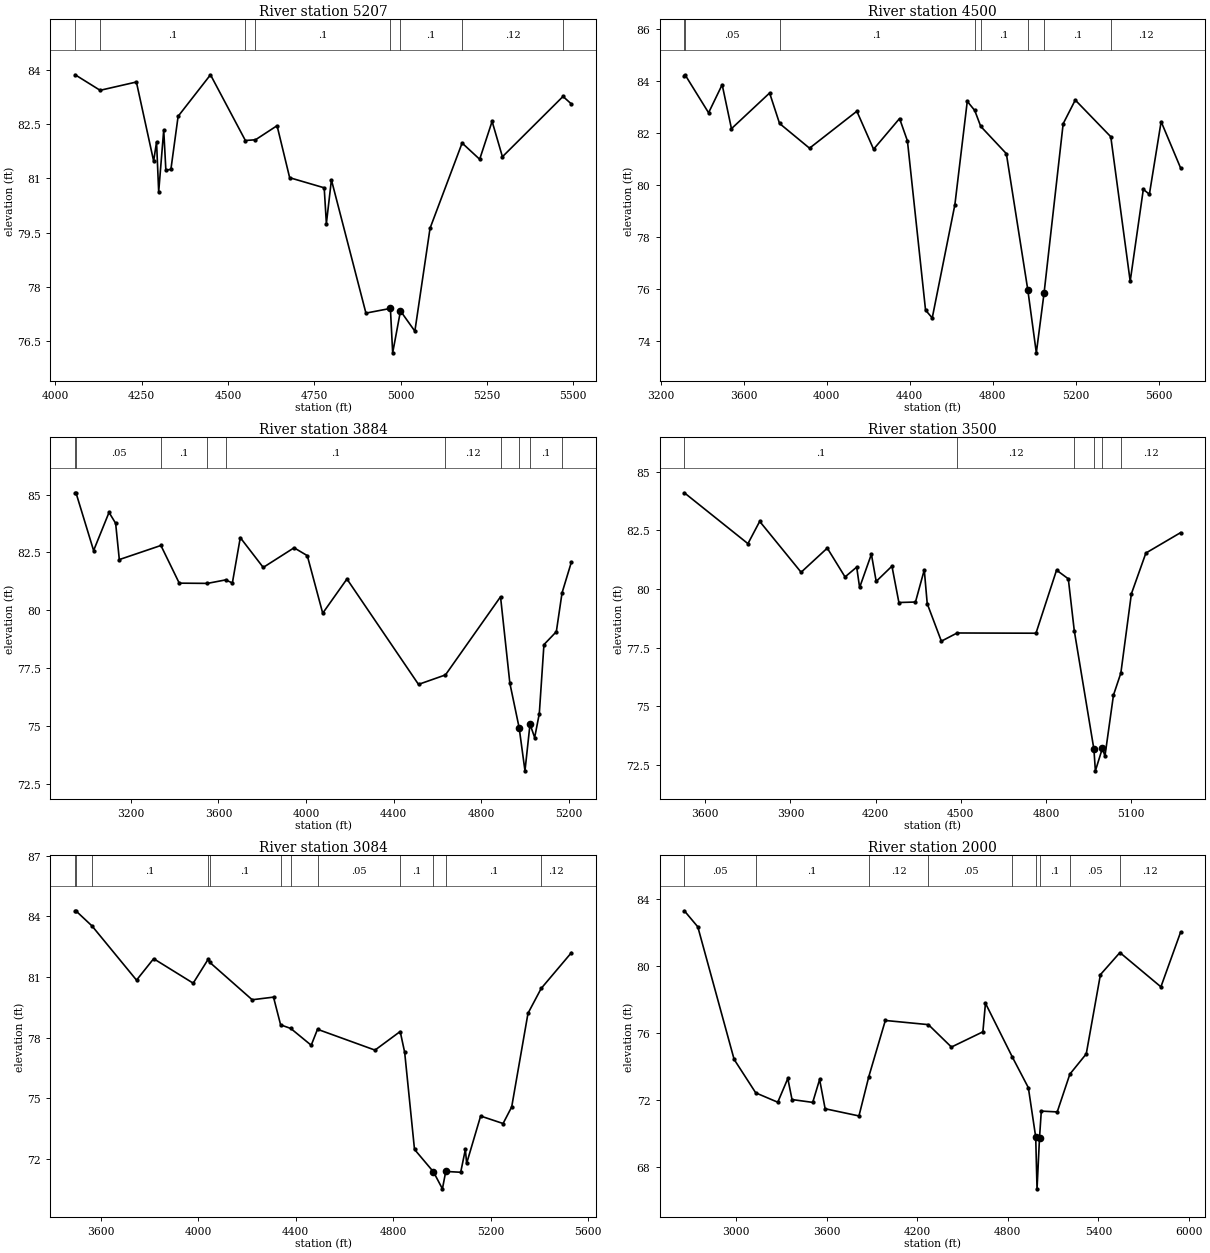
Type RM Length L Ch R = 1 ,5207    ,707,707,707
BEGIN DESCRIPTION:
Crystal Creek 003 10.0
END DESCRIPTION:
XS GIS Cut Line= 3
      3879318.25     10032630.13      3879927.61     10031812.45
        3880162.     10031466.06
#Sta/Elev= 30
  4057.1   83.87  4129.4   83.44  4234.5   83.67  4284.5   81.48  4292.9   82.01
  4299.1   80.63  4313.7   82.34  4319.9   81.23  4334.5   81.25  4355.4   82.72
  4449.2   83.87  4550.3   82.05  4579.6   82.07  4642.1   82.46  4678.6   81.02
  4778.7   80.74    4785   79.75  4799.6   80.96  4899.6   77.27  4970.5    77.4
  4977.1   76.17  4999.7   77.33  5041.4   76.77  5085.4   79.62  5178.3   81.98
  5229.2   81.53  5265.2   82.58  5295.1    81.6  5470.7   83.27  5495.1   83.06
#Mann= 8 ,-1 , 0
  4057.1     .05       0  4129.4      .1       0  4550.3     .12       0
  4579.6      .1       0  4970.5     .07       0  4999.7      .1       0
  5178.3     .12       0  5470.7      .1       0
Bank Sta=4970.5,4999.7
XS Rating Curve= 0 ,0
Exp/Cntr=0.3,0.1

Type RM Length L Ch R = 1 ,4500    ,616,616,616
BEGIN DESCRIPTION:
Mapping XS 0c22bed6
END DESCRIPTION:
XS GIS Cut Line= 4
      3879148.62     10032991.25      3880395.41     10032309.25
      3880535.53     10032084.83      3881103.38     10031666.51
#Sta/Elev= 30
  3314.3   84.21  3317.8   84.24  3431.2   82.78  3496.6   83.86  3541.4   82.17
  3725.2   83.54  3773.1   82.37  3917.5   81.42  4145.5   82.84  4226.1   81.38
  4351.3   82.56  4389.2    81.7  4476.5    75.2  4508.7    74.9  4617.8   79.25
  4677.5   83.22  4713.4   82.87  4742.2   82.26  4865.8   81.21  4969.1   75.98
  5010.2   73.56  5047.4   75.85  5139.5   82.36  5197.8   83.27  5368.9   81.86
  5462.4   76.31  5525.7   79.84  5554.9   79.65  5611.5   82.44  5705.3   80.66
#Mann= 8 ,-1 , 0
  3314.3     .12       0  3317.8     .05       0  3773.1      .1       0
  4713.4     .05       0  4742.2      .1       0  4969.1     .07       0
  5047.4      .1       0  5368.9     .12       0
Bank Sta=4969.1,5047.4
XS Rating Curve= 0 ,0
Exp/Cntr=0.3,0.1

Type RM Length L Ch R = 1 ,3884    ,384,384,384
BEGIN DESCRIPTION:
Crystal Creek 003 8.0
END DESCRIPTION:
XS GIS Cut Line= 3
      3879154.17     10033018.18      3880611.43     10032858.73
       3881176.4     10032291.99
#Sta/Elev= 30
    2946   85.08  2949.7   85.08  3030.2   82.58  3100.6   84.23  3130.8   83.76
  3147.6   82.19  3337.5    82.8  3421.3   81.17  3550.1   81.16  3632.6   81.31
  3663.9   81.18    3700   83.14  3804.8   81.85  3945.6    82.7    4006   82.36
  4076.4   79.87    4187   81.35  4513.8   76.79  4636.9    77.2  4888.4   80.58
    4931   76.84  4973.5   74.91    5000   73.05    5023   75.07  5044.2   74.49
  5065.4   75.52  5086.6   78.51  5143.2   79.07  5169.3   80.75  5212.2   82.09
#Mann= 10 ,-1 , 0
    2946     .12       0  2949.7     .05       0  3337.5      .1       0
  3550.1     .05       0  3632.6      .1       0  4636.9     .12       0
  4888.4      .1       0  4973.5     .07       0    5023      .1       0
  5169.3     .12       0
Bank Sta=4973.5,5023
XS Rating Curve= 0 ,0
Exp/Cntr=0.3,0.1

Type RM Length L Ch R = 1 ,3500    ,416,416,416
BEGIN DESCRIPTION:
Crystal Creek 003 7.0
END DESCRIPTION:
XS GIS Cut Line= 3
      3879801.43     10033151.65      3881224.74      10032769.6
      3881453.29     10032617.38
#Sta/Elev= 30
  3526.3    84.1  3750.4   81.93  3791.8   82.88  3937.7   80.71  4029.9   81.74
  4092.5   80.51  4133.5   80.93  4143.8   80.06  4185.3   81.48  4202.2   80.32
  4257.7   80.97  4282.2   79.42  4340.6   79.44  4371.6   80.81    4382   79.37
  4431.8   77.77  4487.3   78.12  4765.1   78.11  4837.6    80.8    4879   80.43
    4900   78.22 4969.15  73.165  4974.4   72.24    4999    73.2  5008.1   72.87
  5038.1   75.47  5064.1   76.41  5101.2   79.79  5152.3   81.53  5274.6    82.4
#Mann= 6 ,-1 , 0
  3526.3      .1       0  4487.3     .12       0    4900      .1       0
 4969.15     .07       0    4999      .1       0  5064.1     .12       0
Bank Sta=4969.15,4999
XS Rating Curve= 0 ,0
Exp/Cntr=0.3,0.1

Type RM Length L Ch R = 1 ,3084    ,1084,1084,1084
BEGIN DESCRIPTION:
Crystal Creek 003 6.0
END DESCRIPTION:
XS GIS Cut Line= 3
      3879937.98     10033382.77      3881380.73     10033174.43
      3881505.73     10032606.75
#Sta/Elev= 30
  3493.5   84.28  3497.9   84.26  3562.7   83.53  3745.6   80.85  3815.9   81.91
  3978.4    80.7  4040.3   81.89  4045.5   81.74  4220.8   79.88  4308.4   80.01
  4337.6   78.64  4379.4   78.46  4463.3   77.63  4489.2   78.42  4725.4   77.39
  4828.9   78.31  4847.3   77.28  4887.7   72.48  4965.5   71.37  5002.4   70.53
  5016.1   71.39  5077.5   71.35  5096.7   72.48  5101.9   71.79  5159.4   74.13
  5251.6   73.76    5287   74.58    5354   79.21  5408.2   80.44  5532.5   82.21
#Mann= 12 ,-1 , 0
  3493.5      .1       0  3497.9     .05       0  3562.7      .1       0
  4040.3     .05       0  4045.5      .1       0  4337.6     .05       0
  4379.4     .12       0  4489.2     .05       0  4828.9      .1       0
  4965.5     .07       0  5016.1      .1       0  5408.2     .12       0
Bank Sta=4965.5,5016.1
XS Rating Curve= 0 ,0
Exp/Cntr=0.3,0.1

Type RM Length L Ch R = 1 ,2000    ,1000,1000,1000
BEGIN DESCRIPTION:
Crystal Creek 003 4.0
END DESCRIPTION:
XS GIS Cut Line= 5
      3880516.13     10034132.77      3881964.19     10033229.73
      3882196.34     10032636.82      3882113.49     10032106.94
      3881727.16     10031974.55
#Sta/Elev= 30
  2656.7   83.31    2746   82.35  2986.7   74.42  3129.9   72.42  3275.8   71.86
  3342.3   73.28  3370.2   72.02  3507.3   71.85    3553   73.22  3589.6   71.47
  3813.7   71.04  3878.9   73.39  3988.4   76.75  4273.8    76.5  4426.3   75.16
  4634.8   76.07  4651.8   77.78  4830.6   74.55    4936   72.73  4984.7   69.78
  4993.5   66.68 5009.95  69.739  5021.8   71.33  5127.3   71.28    5211   73.54
  5319.6   74.75  5413.4   79.49  5542.5   80.81  5814.2   78.76  5944.7   82.03
#Mann= 9 ,-1 , 0
  2656.7     .05       0  3129.9      .1       0  3878.9     .12       0
  4273.8     .05       0  4830.6      .1       0  4984.7     .07       0
 5009.95      .1       0    5211     .05       0  5542.5     .12       0
Bank Sta=4984.7,5009.95
XS Rating Curve= 0 ,0
Exp/Cntr=0.3,0.1

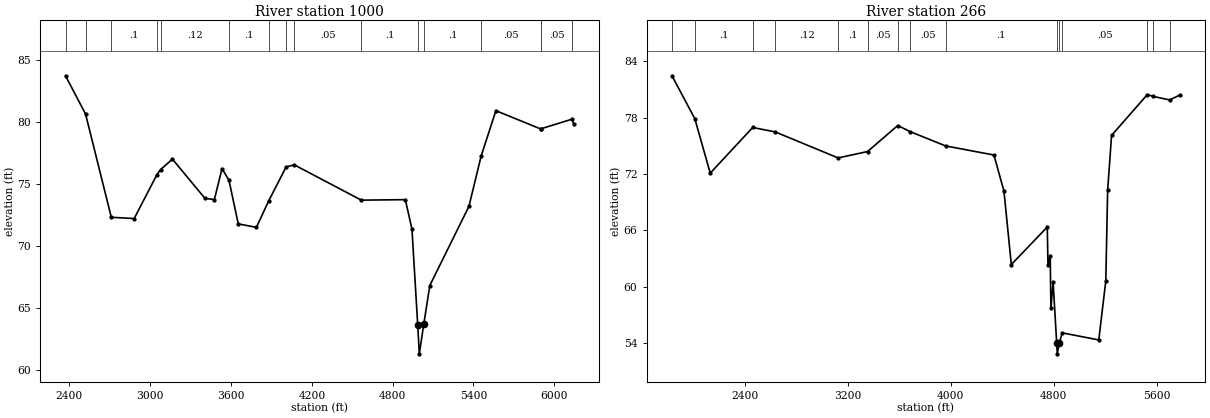
Type RM Length L Ch R = 1 ,1000    ,734,734,734
BEGIN DESCRIPTION:
Mapping XS 6d0336b8
END DESCRIPTION:
XS GIS Cut Line= 3
      3880767.85     10034911.07      3882743.21     10033176.86
      3882800.86     10032035.32
#Sta/Elev= 30
  2371.4    83.7  2520.4   80.62  2711.3   72.31  2881.4   72.21  3048.9   75.72
  3077.1   76.15  3165.2   76.99  3406.2   73.84  3476.4   73.73  3533.3   76.23
  3584.9   75.29  3653.9   71.78  3788.6    71.5  3880.7   73.65    4009   76.36
  4069.9   76.53  4567.5   73.69  4894.1   73.73  4943.4   71.36  4986.1   63.67
    4998   61.32 5030.86  63.692  5075.9   66.82  5366.3   73.19  5457.3   77.25
  5566.5   80.89  5899.3   79.42  5900.1   79.43  6132.6   80.21    6143   79.85
#Mann= 16 ,-1 , 0
  2371.4     .05       0  2520.4     .12       0  2711.3      .1       0
  3048.9     .05       0  3077.1     .12       0  3584.9      .1       0
  3880.7     .05       0    4009      .1       0  4069.9     .05       0
  4567.5      .1       0  4986.1     .07       0 5030.86      .1       0
  5457.3     .05       0  5899.3     .12       0  5900.1     .05       0
  6132.6     .12       0
Bank Sta=4986.1,5030.86
XS Rating Curve= 0 ,0
Exp/Cntr=0.3,0.1

Type RM Length L Ch R = 1 ,266     ,0,0,0
BEGIN DESCRIPTION:
Crystal Creek 003 2.0
END DESCRIPTION:
XS GIS Cut Line= 4
      3880863.58     10035045.66      3882843.01     10033303.22
      3883068.04     10032826.66      3882934.15     10032057.53
#Sta/Elev= 30
  1835.9   82.45  2013.2   77.89    2133   72.09  2462.8   76.95  2637.3   76.48
    3126   73.71  3354.6   74.39  3589.2   77.16    3687    76.5    3960   74.99
    4336   74.02  4413.8   70.16  4470.7   62.37    4750   66.36  4755.5   62.27
  4772.8   63.33  4778.3    57.7  4795.5   60.47 4823.04  54.035  4827.6   52.87
 4843.73  54.074    4867    55.1  5149.9   54.35  5204.4   60.62  5218.8   70.26
  5249.3   76.11    5527   80.45  5570.8   80.26  5700.2   79.88  5780.7   80.41
#Mann= 15 ,-1 , 0
  1835.9     .05       0  2013.2      .1       0  2462.8     .05       0
  2637.3     .12       0    3126      .1       0  3354.6     .05       0
  3589.2     .12       0    3687     .05       0    3960      .1       0
 4823.04     .07       0 4843.73      .1       0    4867     .05       0
    5527     .12       0  5570.8     .05       0  5700.2     .12       0
Bank Sta=4823.04,4843.73
XS Rating Curve= 0 ,0
Exp/Cntr=0.3,0.1