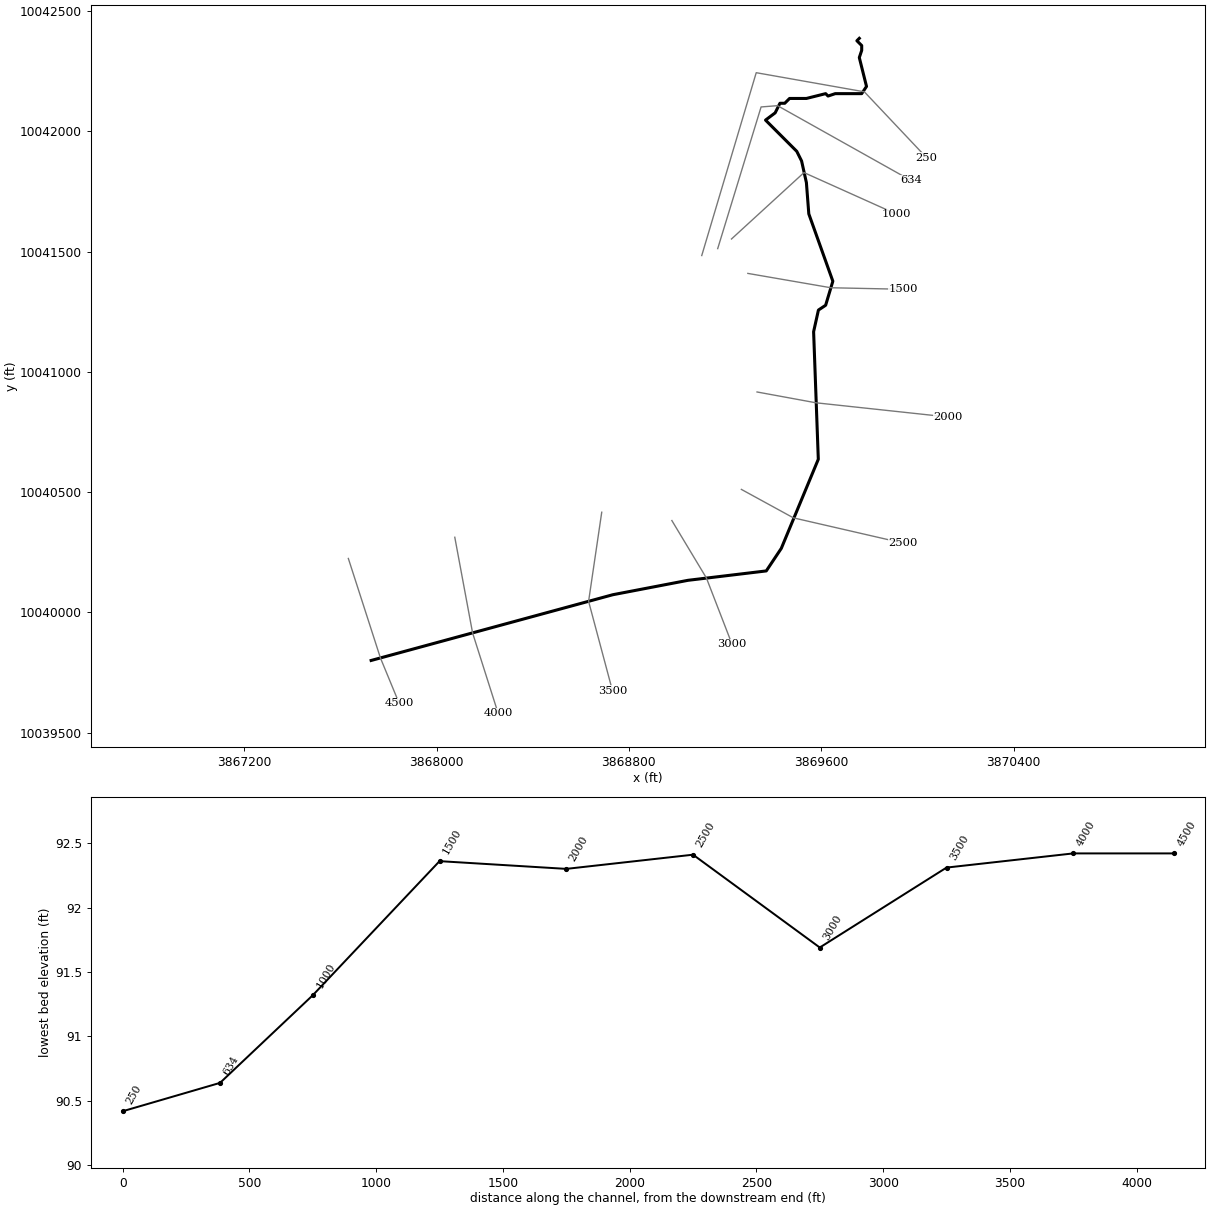
--- Crystal Creek 006.prj (project) ---

Proj Title=Crystal Creek 006 Base Level Engineering
Current Plan=p01
Default Exp/Contr=0.3,0.1
English Units
Geom File=g01
Flow File=f01
Flow File=f02
Plan File=p01
Y Axis Title=Elevation
X Axis Title(PF)=Main Channel Distance
X Axis Title(XS)=Station
BEGIN DESCRIPTION:
Crystal Creek 006
END DESCRIPTION:
DSS Export Rating Curves= 0
DSS Export Rating Curve Sorted= 0
DSS Export Volume Flow Curves= 0
DXF OffsetX= 0
DXF OffsetY= 0
DXF ScaleX= 1
DXF ScaleY= 10

--- Crystal Creek 006.p01 (plan) ---

Plan Title=Multiple Run
Program Version=4.10
Short Identifier=Multiple
Geom File=g01
Flow File=f01
Subcritical Flow
K Sum by GR= 0
Std Step Tol= 0.01
Critical Tol= 0.01
Num of Std Step Trials= 20
Max Error Tol= 0.3
Flow Tol Ratio= 0.001
Split Flow NTrial= 30
Split Flow Tol= 0.02
Split Flow Ratio= 0.02
Log Output Level= 0
Friction Slope Method= 1
Unsteady Friction Slope Method= 2
Unsteady Bridges Friction Slope Method= 1
Parabolic Critical Depth
Global Vel Dist= 1 , 1 , 1
Global Log Level= 0
CheckData=True
Encroach Param=-1 ,0,0, 0
BEGIN DESCRIPTION:
Multiple Run
END DESCRIPTION:
Computation Interval=1HOUR
Output Interval=1HOUR
Run HTab= 0
Run UNet= 0
Run PostProcess= 0
Run WQNet= 0
UNET Theta= 1
UNET Theta Warmup= 1
UNET ZTol= 0.02
UNET ZSATol= 0.05
UNET MxIter= 20
UNET MaxInSteps= 0
UNET DtIC= 0
UNET DtMin= 0
UNET MaxCRTS= 20
UNET WFStab= 2
UNET SFStab= 1
UNET WFX= 1
UNET SFX= 1
UNET DSS MLevel= 4
UNET DZMax Abort= 100
UNET Convert EG Bridges= 0
UNET Use Existing IB Tables=-1
UNET Froude Reduction=False
UNET Froude Limit= 1
UNET Froude Power= 10
UNET Time Slicing=0,0, 5
UNET Junction Losses=0
Instantaneous Interval=1HOUR
Write IC File= 0
Write IC File at Sim End=0
Echo Input=False
Echo Parameters=False
Echo Output=False
Write Detailed= 0
WQ AD Non Conservative
WQ ULTIMATE=-1
WQ Max Comp Step=1HOUR
WQ Output Interval=15MIN
WQ Output Selected Increments= 0
WQ Output face flow=0
WQ Output face velocity=0
WQ Output face area=0
WQ Output face dispersion=0
WQ Output cell volume=0
WQ Output cell surface area=0
WQ Output cell continuity=0
WQ Output cumulative cell continuity=0
WQ Output face conc=0
WQ Output face dconc_dx=0
WQ Output face courant=0
WQ Output face peclet=0
WQ Output face adv mass=0
WQ Output face disp mass=0
WQ Output cell mass=0
WQ Output cell source sink temp=0
WQ Output cell source sink nsm=0
WQ Output MaxMinRange=-1
WQ Daily Max Min Mean=-1
WQ Daily Range=0
WQ Daily Time=0
WQ Create Restart=0
WQ Fixed Restart=0
WQ System Summary=0
WQ Use Fixed Temperature=0
Sorting and Armoring Iterations= 10
XS Update Threshold= 0.02
Hydraulics Update Threshold= 0.02
Energy Slope Method= 1
Volume Change Method= 0
XS Weighting Method= 0
Number of US Weighted Cross Sections= 1
Number of DS Weighted Cross Sections= 1
Upstream XS Weight=0.25
Main XS Weight=0.5
Downstream XS Weight=0.25
Number of DS XS's Weighted with US Boundary= 1
Upstream Boundary Weight= 1
Weight of XSs Associated with US Boundary= 0
Number of US XS's Weighted with DS Boundary= 1
Downstream Boundary Weight= 0.5
Weight of XSs Associated with DS Boundary= 0.5
Sediment Output Level= 4
Mass or Volume Output= 0
Output Increment Type= 1
Profile and TS Output Increment= 10
XS Output Flag= 0
XS Output Increment= 10
Disregard all LS=0
Disregard all Conn=0
Disregard all Breaches=0
Disregard all Pumps=0

--- Crystal Creek 006.f01 (steady flow) ---

Flow Title=Multiple
Program Version=4.10
Number of Profiles= 7
Profile Names=10-year,25-year,50-year,1pct_min,100-year,1pct_plu,500-year
River Rch & RM=Crystal Creek 00,Reach-1         ,4500
     131     154     189      76     231     698     356
River Rch & RM=Crystal Creek 00,Reach-1         ,4000
     131     154     189      76     231     698     356
Boundary for River Rch & Prof#=Crystal Creek 00,Reach-1         , 1
Up Type= 0
Dn Type= 3
Dn Slope=0.005
Boundary for River Rch & Prof#=Crystal Creek 00,Reach-1         , 2
Up Type= 0
Dn Type= 3
Dn Slope=0.005
Boundary for River Rch & Prof#=Crystal Creek 00,Reach-1         , 3
Up Type= 0
Dn Type= 3
Dn Slope=0.005
Boundary for River Rch & Prof#=Crystal Creek 00,Reach-1         , 4
Up Type= 0
Dn Type= 3
Dn Slope=0.005
Boundary for River Rch & Prof#=Crystal Creek 00,Reach-1         , 5
Up Type= 0
Dn Type= 3
Dn Slope=0.005
Boundary for River Rch & Prof#=Crystal Creek 00,Reach-1         , 6
Up Type= 0
Dn Type= 3
Dn Slope=0.005
Boundary for River Rch & Prof#=Crystal Creek 00,Reach-1         , 7
Up Type= 0
Dn Type= 3
Dn Slope=0.005
DSS Import GetInterval= 0
DSS Import GetPeak= 0
DSS Import FillOption= 0

--- Crystal Creek 006.f02 (steady flow) ---

Flow Title=Orig_BLE_Flow
Program Version=4.10
Number of Profiles= 7
Profile Names=10-year,25-year,50-year,1pct_min,100-year,1pct_plu,500-year
River Rch & RM=Crystal Creek 00,Reach-1         ,4500
     131     151     164      59     178     537     207
River Rch & RM=Crystal Creek 00,Reach-1         ,4000
     131     151     164      59     178     537     207
Boundary for River Rch & Prof#=Crystal Creek 00,Reach-1         , 1
Up Type= 0
Dn Type= 3
Dn Slope=0.005
Boundary for River Rch & Prof#=Crystal Creek 00,Reach-1         , 2
Up Type= 0
Dn Type= 3
Dn Slope=0.005
Boundary for River Rch & Prof#=Crystal Creek 00,Reach-1         , 3
Up Type= 0
Dn Type= 3
Dn Slope=0.005
Boundary for River Rch & Prof#=Crystal Creek 00,Reach-1         , 4
Up Type= 0
Dn Type= 3
Dn Slope=0.005
Boundary for River Rch & Prof#=Crystal Creek 00,Reach-1         , 5
Up Type= 0
Dn Type= 3
Dn Slope=0.005
Boundary for River Rch & Prof#=Crystal Creek 00,Reach-1         , 6
Up Type= 0
Dn Type= 3
Dn Slope=0.005
Boundary for River Rch & Prof#=Crystal Creek 00,Reach-1         , 7
Up Type= 0
Dn Type= 3
Dn Slope=0.005
DSS Import GetInterval= 0
DSS Import GetPeak= 0
DSS Import FillOption= 0

--- Crystal Creek 006.g01 (geometry) ---

Geom Title=Existing Conditions
Program Version=4.10

River Reach=Crystal Creek 00,Reach-1
Reach XY= 30
      3867728.13     10039799.68      3868733.34     10040073.12
      3869045.84     10040133.01      3869371.36     10040172.08
      3869433.86     10040265.83      3869587.75     10040636.38
      3869568.24     10041166.86      3869588.24     10041256.86
      3869618.24     10041276.86      3869648.24     10041376.86
      3869548.24     10041656.86      3869538.24     10041786.86
      3869518.24     10041876.86      3869498.24     10041916.86
      3869368.24     10042046.86      3869408.24     10042076.86
      3869428.24     10042116.86      3869448.24     10042116.86
      3869468.24     10042136.86      3869538.24     10042136.86
      3869618.24     10042156.86      3869628.24     10042146.86
      3869658.24     10042156.86      3869768.24     10042156.86
      3869788.24     10042186.86      3869758.24     10042306.86
      3869768.24     10042336.86      3869768.24     10042356.86
      3869748.24     10042376.86      3869758.24     10042386.86

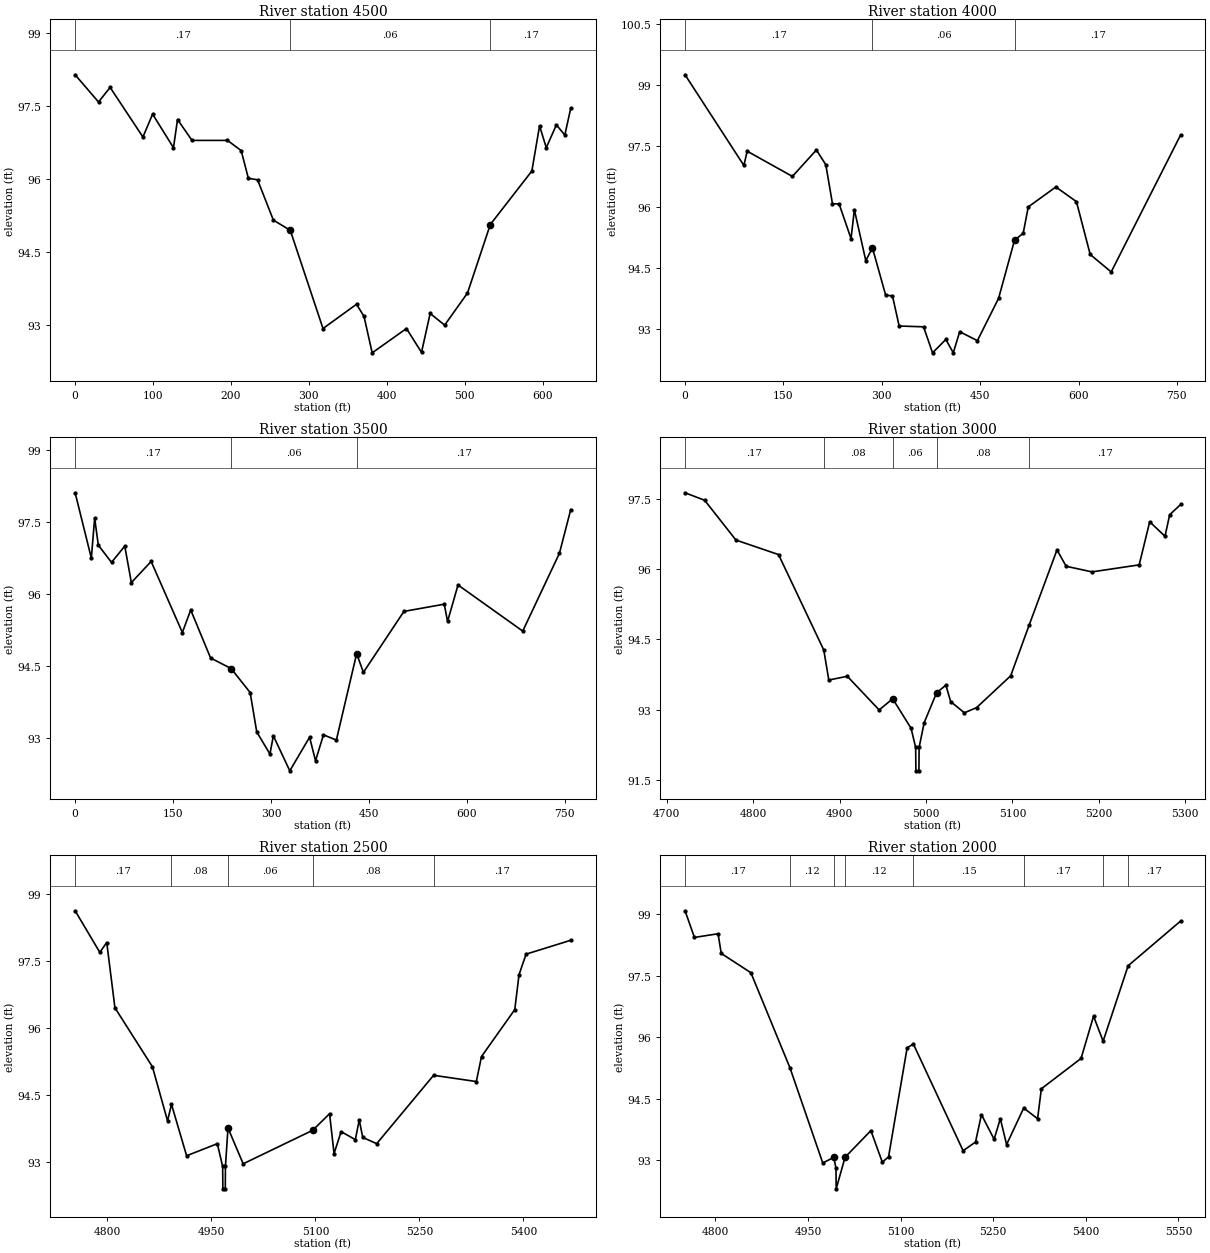
Type RM Length L Ch R = 1 ,4500    ,397,397,397
XS GIS Cut Line= 3
      3867633.37     10040223.85      3867766.79     10039810.16
      3867844.31     10039622.28
#Sta/Elev= 30
       0   98.14      30   97.58    44.9   97.88      87   96.86    99.4   97.33
   126.2   96.64   131.4   97.22     150   96.79   195.5   96.79   213.1   96.58
   222.3   96.01   234.1   95.98   254.4   95.15   276.1   94.94   318.1   92.92
   361.1   93.42   370.7   93.17   381.2   92.42   425.2   92.92   444.5   92.43
   455.6   93.23   474.2   92.99   503.5   93.65   532.8   95.06   586.1   96.16
     596   97.09   604.6   96.64   617.6   97.11   628.4    96.9     636   97.45
#Mann= 3 , 0 , 0
       0     .17       0   276.1     .06       0   532.8     .17       0
Bank Sta=276.1,532.8
XS Rating Curve= 0 ,0
Exp/Cntr=0.3,0.1

Type RM Length L Ch R = 1 ,4000    ,500,500,500
XS GIS Cut Line= 3
      3868076.02     10040312.06      3868150.08     10039914.07
      3868256.41     10039579.67
#Sta/Elev= 30
       0   99.26    89.7   97.03    94.8   97.38   163.7   96.76   200.3   97.41
   214.6   97.05   224.8   96.09     235   96.08   253.1   95.23   258.2   95.94
   275.6   94.69   285.8      95   305.9   93.84   316.3   93.82   326.5   93.08
   363.7   93.06   377.4   92.42   397.7   92.75     409   92.42   418.8   92.94
   445.8   92.72   478.1   93.76   502.4   95.19   515.6   95.36   523.4   96.01
   565.4    96.5   596.8   96.14   617.8   94.84   649.8   94.41   755.7   97.78
#Mann= 3 , 0 , 0
       0     .17       0   285.8     .06       0   502.4     .17       0
Bank Sta=285.8,502.4
XS Rating Curve= 0 ,0
Exp/Cntr=0.3,0.1

Type RM Length L Ch R = 1 ,3500    ,500,500,500
XS GIS Cut Line= 3
      3868687.13     10040416.22      3868632.48     10040045.55
       3868732.1     10039672.56
#Sta/Elev= 30
       0    98.1    24.8   96.74    29.9   97.57    35.5   97.01    55.7   96.65
      76   96.99    86.1   96.23   116.4   96.67   164.2   95.19     177   95.66
   207.4   94.66   238.9   94.44     268   93.94   278.1   93.12   298.3   92.66
   303.5   93.04   328.7   92.31     359   93.01   368.1   92.52   380.3   93.06
     400   92.95   431.1   94.75   441.4   94.36   503.5   95.63   565.2   95.78
   570.3   95.42   586.3   96.18   685.4   95.22   741.6   96.84   758.9   97.75
#Mann= 3 , 0 , 0
       0     .17       0   238.9     .06       0   431.1     .17       0
Bank Sta=238.9,431.1
XS Rating Curve= 0 ,0
Exp/Cntr=0.3,0.1

Type RM Length L Ch R = 1 ,3000    ,500,500,500
BEGIN DESCRIPTION:
Crystal Creek 006 6.0
END DESCRIPTION:
XS GIS Cut Line= 3
      3868978.78     10040381.53      3869122.51     10040142.52
      3869228.78     10039867.65
#Sta/Elev= 30
  4721.1   97.63  4743.8   97.47    4780   96.62  4829.3   96.31  4881.7   94.27
  4887.5   93.63  4908.9   93.71  4945.8   92.99  4961.4   93.23  4982.7    92.6
    4988   92.19  4988.3   91.69  4991.8   91.69    4992   92.19  4997.9   92.72
  5012.3   93.36    5023   93.52  5028.5   93.17  5044.4   92.93  5058.5   93.04
    5098   93.72  5119.5   94.81  5151.6   96.41  5162.2   96.06  5192.1   95.94
  5246.7   96.09  5258.9   97.01  5276.6    96.7    5282   97.16  5294.7   97.38
#Mann= 5 ,-1 , 0
  4721.1     .17       0  4881.7     .08       0  4961.4     .06       0
  5012.3     .08       0  5119.5     .17       0
Bank Sta=4961.4,5012.3
XS Rating Curve= 0 ,0
Exp/Cntr=0.3,0.1

Type RM Length L Ch R = 1 ,2500    ,500,500,500
BEGIN DESCRIPTION:
Crystal Creek 006 5.0
END DESCRIPTION:
XS GIS Cut Line= 3
      3869267.86     10040511.07      3869484.22     10040392.76
       3869940.6     10040287.75
#Sta/Elev= 30
  4753.4   98.63    4789    97.7    4799   97.92  4810.8   96.46  4864.9   95.14
  4886.7   93.93  4892.4    94.3  4914.2   93.15  4958.5   93.42  4966.2   92.91
  4966.5   92.41    4970   92.41  4970.2   92.91  4973.9   93.77  4995.8   92.97
  5096.1   93.72  5120.4   94.09  5126.9    93.2  5137.1   93.69  5157.6   93.51
  5163.2   93.95  5168.3   93.56  5188.4   93.42  5270.5   94.95  5332.1   94.81
  5339.6   95.37  5387.6   96.42  5393.7    97.2  5403.9   97.66  5468.3   97.97
#Mann= 5 ,-1 , 0
  4753.4     .17       0  4892.4     .08       0  4973.9     .06       0
  5096.1     .08       0  5270.5     .17       0
Bank Sta=4973.9,5096.1
XS Rating Curve= 0 ,0
Exp/Cntr=0.3,0.1

Type RM Length L Ch R = 1 ,2000    ,500,500,500
BEGIN DESCRIPTION:
Crystal Creek 006 4.0
END DESCRIPTION:
XS GIS Cut Line= 3
      3869332.95     10040916.23      3869577.76     10040871.28
      3870128.08     10040812.06
#Sta/Elev= 30
  4751.1   99.08  4766.3   98.43  4804.6   98.52  4809.7   98.04  4857.7   97.57
    4921   95.25  4974.1   92.93 4991.9393.06773  4995.5    92.8  4995.8    92.3
  5010.2   93.07    5052   93.72  5070.5   92.95  5080.6   93.08  5110.7   95.74
  5120.8   95.83  5201.3   93.23  5221.4   93.44    5231   94.11  5251.5   93.51
  5261.6   94.01  5271.7   93.38  5299.4   94.27  5321.9   94.01    5328   94.74
  5392.3   95.48  5412.5   96.51    5428    95.9  5468.5   97.74  5553.5   98.83
#Mann= 8 ,-1 , 0
  4751.1     .17       0    4921     .12       0 4991.93     .09       0
  5010.2     .12       0  5120.8     .15       0  5299.4     .17       0
    5428     .15       0  5468.5     .17       0
#XS Ineff= 2 , 0
       0                  5120.8       0   95.83
Permanent Ineff=
       F       F
Bank Sta=4991.93,5010.2
XS Rating Curve= 0 ,0
Exp/Cntr=0.3,0.1

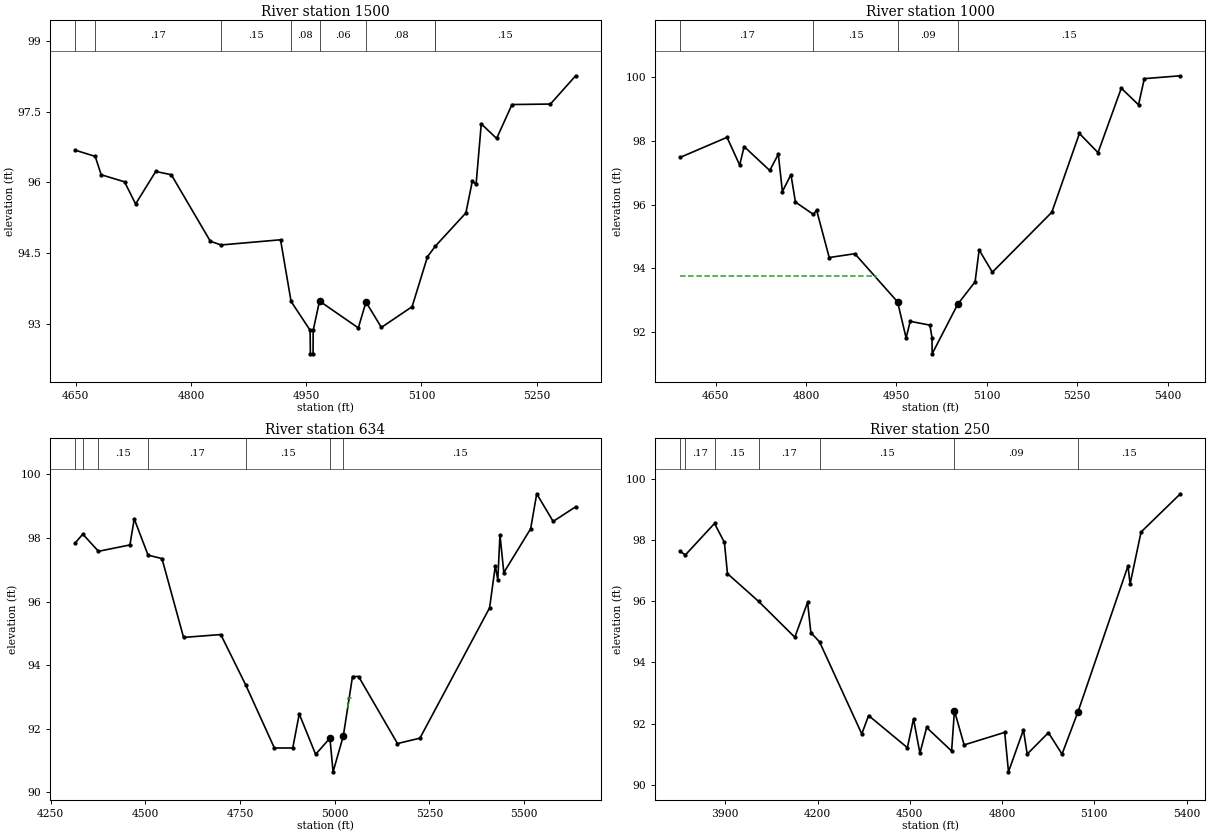
Type RM Length L Ch R = 1 ,1500    ,500,500,500
BEGIN DESCRIPTION:
Crystal Creek 006 3.0
END DESCRIPTION:
XS GIS Cut Line= 3
      3869294.78     10041409.28      3869640.07     10041349.64
       3869940.6     10041343.31
#Sta/Elev= 30
  4649.6   96.68  4675.4   96.55  4683.2   96.16  4713.6   96.01    4728   95.54
  4754.2   96.23  4774.5   96.16  4825.2   94.75  4839.1   94.67  4916.6   94.78
 4930.3193.47243  4955.1   92.86  4955.4   92.36  4958.9   92.36  4959.1   92.86
  4967.3   93.48  5017.8   92.91  5027.8   93.46  5047.8   92.92  5087.8   93.36
  5107.8   94.42  5117.8   94.64  5157.8   95.35  5166.1   96.02  5171.1   95.96
  5177.8   97.24  5197.8   96.93  5217.8   97.65  5267.8   97.66  5300.6   98.26
#Mann= 8 ,-1 , 0
  4649.6     .15       0  4675.4     .17       0  4839.1     .15       0
 4930.31     .08       0  4967.3     .06       0  5027.8     .08       0
  5117.8     .17       0  5117.8     .15       0
Bank Sta=4967.3,5027.8
XS Rating Curve= 0 ,0
Exp/Cntr=0.3,0.1

Type RM Length L Ch R = 1 ,1000    ,366,366,366
BEGIN DESCRIPTION:
Crystal Creek 006 2.0
END DESCRIPTION:
XS GIS Cut Line= 3
      3869226.69     10041552.41      3869528.24     10041828.58
      3869912.54     10041655.94
#Sta/Elev= 30
  4591.1   97.48  4668.9   98.11  4689.9   97.24  4697.3   97.82  4739.8   97.07
    4754   97.58  4760.8   96.41    4775   96.94  4782.4   96.08  4812.4   95.69
  4817.5   95.83  4838.5   94.34    4881   94.46  4951.9   92.95  4966.1   91.82
  4972.9   92.34  5005.6   92.22  5009.1   91.82  5009.3   91.32  5051.9   92.88
  5080.6   93.58  5087.3   94.58  5109.2   93.88  5207.9   95.76  5253.7   98.23
  5284.6   97.63  5323.2   99.65  5351.8   99.13  5361.4   99.95  5421.3  100.04
#Mann= 4 ,-1 , 0
  4591.1     .17       0  4812.4     .15       0  4951.9     .09       0
  5051.9     .15       0
#XS Ineff= 2 , 0
       0  4916.8   93.77  5087.3       0   94.58
Permanent Ineff=
       F       F
Bank Sta=4951.9,5051.9
XS Rating Curve= 0 ,0
Exp/Cntr=0.3,0.1

Type RM Length L Ch R = 1 ,634     ,384,384,384
BEGIN DESCRIPTION:
Mapping XS 2da346ee
END DESCRIPTION:
XS GIS Cut Line= 4
       3869169.4     10041512.46      3869349.82     10042101.53
      3869418.24     10042106.86      3869972.75     10041796.01
#Sta/Elev= 30
  4315.3   97.85  4334.9   98.12  4376.3   97.58  4459.3   97.78  4470.7    98.6
  4507.1   97.46  4543.9   97.35  4600.9   94.87  4699.1   94.96  4764.7   93.38
  4840.6   91.39  4889.1   91.39  4906.2   92.46  4949.5   91.19  4987.2    91.7
  4995.5   90.64  5022.691.77282  5046.8   93.64  5062.8   93.64  5165.5   91.53
  5224.8    91.7  5408.6    95.8  5423.7   97.12  5430.3   96.68    5436    98.1
  5446.2   96.91    5517   98.29    5533   99.39  5576.4   98.52  5635.7   98.98
#Mann= 7 ,-1 , 0
  4315.3     .15       0  4334.9     .17       0  4376.3     .15       0
  4507.1     .17       0  4764.7     .15       0  4987.2     .09       0
  5022.6     .15       0
#XS Ineff= 2 ,-1
    5034  5046.8   92.97  5046.8  5333.3   93.64
Permanent Ineff=
       F       F
Bank Sta=4987.2,5022.6
XS Rating Curve= 0 ,0
Exp/Cntr=0.3,0.1

Type RM Length L Ch R = 1 ,250     ,0,0,0
BEGIN DESCRIPTION:
Crystal Creek 006 1.0
END DESCRIPTION:
XS GIS Cut Line= 4
      3869103.05      10041483.6       3869329.6     10042243.99
      3869779.26     10042164.46      3870038.19     10041890.25
#Sta/Elev= 30
  3752.9   97.63  3769.8   97.51  3864.7   98.54  3896.9   97.92  3906.8    96.9
  4008.4   95.99  4125.9   94.82  4167.4   95.96  4178.1   94.97  4206.3   94.67
  4343.7   91.66  4365.9   92.26    4492   91.21    4512   92.15  4532.8   91.03
  4554.7   91.87  4635.9    91.1  4645.1   92.42  4676.6    91.3  4808.6   91.71
  4820.9   90.42  4869.5   91.79  4881.8      91  4950.8    91.7  4995.1      91
  5046.9   92.38  5209.6   97.15  5216.5   96.56  5252.1   98.26  5380.1   99.51
#Mann= 7 ,-1 , 0
  3752.9     .15       0  3769.8     .17       0  3864.7     .15       0
  4008.4     .17       0  4206.3     .15       0  4645.1     .09       0
  5046.9     .15       0
#XS Ineff= 2 , 0
       0  4645.1   92.42               0
Permanent Ineff=
       F       F
Bank Sta=4645.1,5046.9
XS Rating Curve= 0 ,0
Exp/Cntr=0.3,0.1

Chan Stop Cuts=-1
Use User Specified Reach Order=0
Composite Channel Slope=5

--- Crystal Creek 006.g10 (geometry) ---

Geom Title=Existing Conditions
Program Version=4.10

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
River Reach=Crystal Creek 00,Reach-1

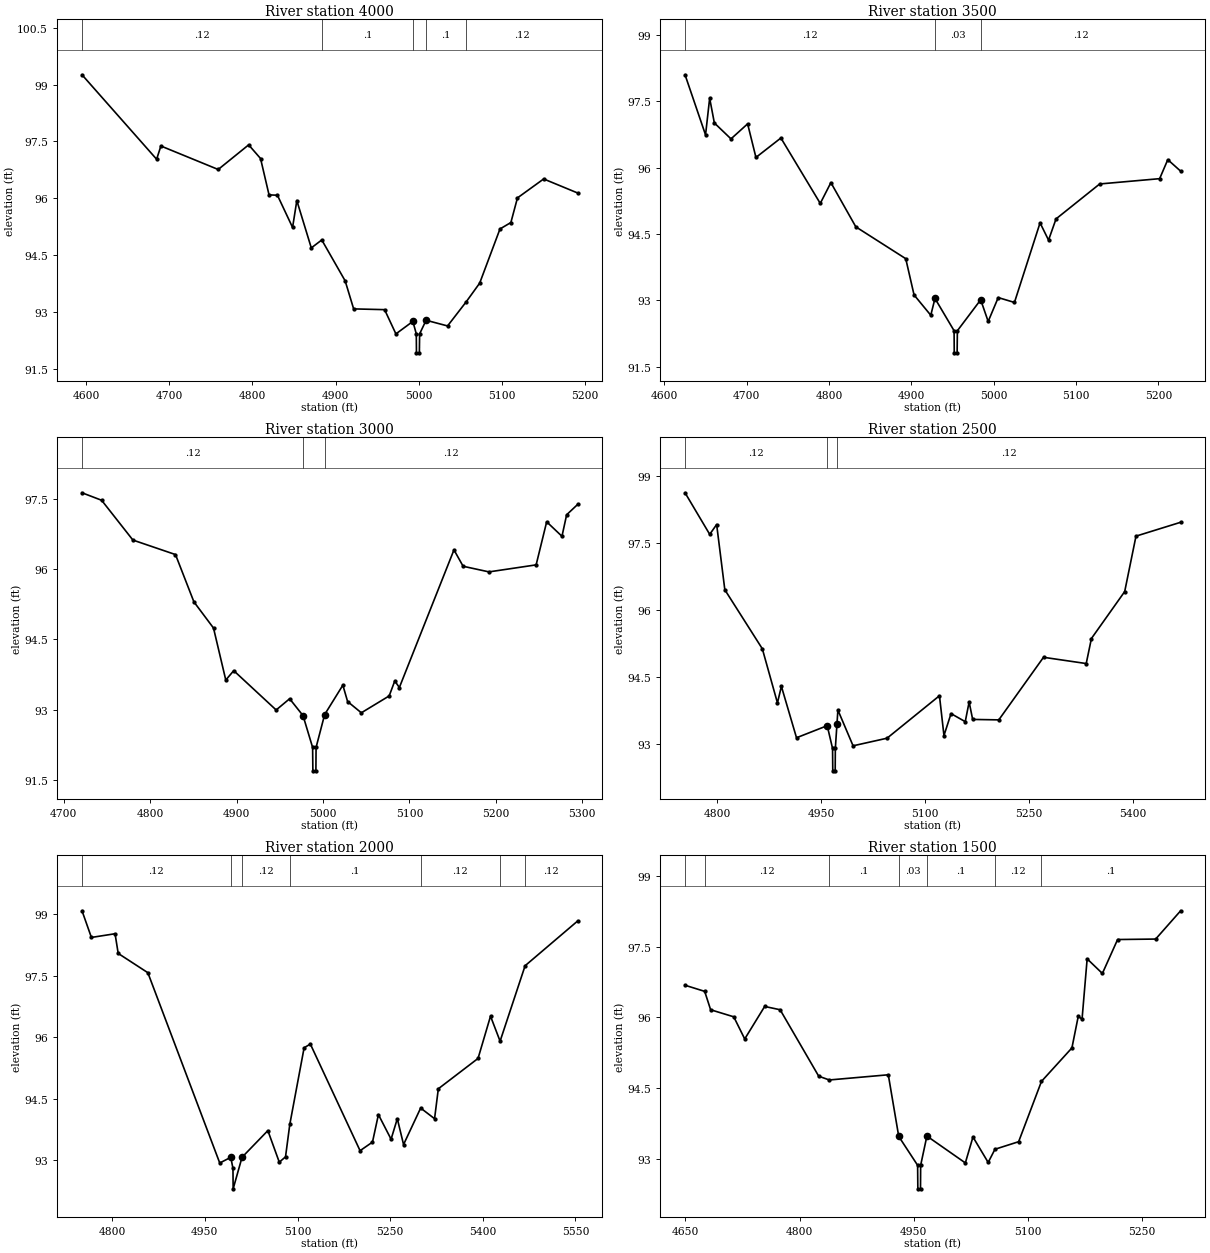
Type RM Length L Ch R = 1 ,4000    ,500,500,500
BEGIN DESCRIPTION:
Crystal Creek 006 8.0
END DESCRIPTION:
XS GIS Cut Line= 3
      3868076.02     10040312.04      3868150.08     10039914.07
      3868207.97     10039732.16
#Sta/Elev= 30
  4595.2   99.26  4684.9   97.03    4690   97.38  4758.9   96.76  4795.5   97.41
  4809.8   97.05    4820   96.09  4830.1   96.08  4848.3   95.23  4853.4   95.94
  4870.8   94.69  4883.4    94.9  4911.5   93.82  4921.7   93.08  4958.9   93.06
  4972.5   92.42  4992.9   92.75    4997   92.42  4997.2   91.92  5000.7   91.92
    5001   92.42  5008.8   92.78  5034.6   92.63  5057.1   93.27  5073.2   93.76
  5097.6   95.19  5110.7   95.36  5118.6   96.01  5150.1   96.51  5190.9   96.14
#Mann= 5 ,-1 , 0
  4595.2     .12       0  4883.4      .1       0  4992.9     .03       0
  5008.8      .1       0  5057.1     .12       0
Bank Sta=4992.9,5008.8
XS Rating Curve= 0 ,0
Exp/Cntr=0.3,0.1

Type RM Length L Ch R = 1 ,3500    ,500,500,500
BEGIN DESCRIPTION:
Crystal Creek 006 7.0
END DESCRIPTION:
XS GIS Cut Line= 3
      3868687.13     10040416.25      3868632.48     10040045.55
      3868690.58     10039826.01
#Sta/Elev= 30
  4625.3    98.1  4650.2   96.74  4655.2   97.57  4660.9   97.01  4681.1   96.65
  4701.3   96.99  4711.4   96.23  4741.7   96.67  4789.5   95.19  4802.4   95.66
  4832.7   94.66  4893.3   93.94  4903.4   93.12  4923.7   92.66  4928.8   93.04
    4952   92.31  4952.2   91.81  4955.7   91.81    4956   92.31  4984.3   93.01
  4993.4   92.52  5005.6   93.06  5025.3   92.95  5056.4   94.75  5066.7   94.36
  5075.8   94.84  5128.8   95.63  5201.6   95.75  5211.5   96.18  5227.1   95.92
#Mann= 3 , 0 , 0
  4625.3     .12       0  4928.8     .03       0  4984.3     .12       0
Bank Sta=4928.8,4984.3
XS Rating Curve= 0 ,0
Exp/Cntr=0.3,0.1

Type RM Length L Ch R = 1 ,3000    ,500,500,500
BEGIN DESCRIPTION:
Crystal Creek 006 6.0
END DESCRIPTION:
XS GIS Cut Line= 3
      3868978.78     10040381.53      3869122.51     10040142.52
      3869228.78     10039867.65
#Sta/Elev= 30
  4721.1   97.63  4743.8   97.47    4780   96.62  4829.3   96.31  4850.6    95.3
  4873.3   94.74  4887.5   93.63  4896.7   93.83  4945.8   92.99  4961.4   93.23
  4976.9   92.87    4988   92.19  4988.3   91.69  4991.8   91.69    4992   92.19
 5001.92  92.892    5023   93.52  5028.5   93.17  5044.4   92.93  5076.6   93.29
  5083.1   93.61  5088.4   93.47  5151.6   96.41  5162.2   96.06  5192.1   95.94
  5246.7   96.09  5258.9   97.01  5276.6    96.7    5282   97.16  5294.7   97.38
#Mann= 3 , 0 , 0
  4721.1     .12       0  4976.9     .03       0 5001.92     .12       0
Bank Sta=4976.9,5001.92
XS Rating Curve= 0 ,0
Exp/Cntr=0.3,0.1

Type RM Length L Ch R = 1 ,2500    ,500,500,500
BEGIN DESCRIPTION:
Crystal Creek 006 5.0
END DESCRIPTION:
XS GIS Cut Line= 3
      3869267.86     10040511.07      3869484.22     10040392.76
       3869940.6     10040287.75
#Sta/Elev= 30
  4753.4   98.63    4789    97.7    4799   97.92  4810.8   96.46  4864.9   95.14
  4886.7   93.93  4892.4    94.3  4914.2   93.15  4958.5   93.42  4966.2   92.91
  4966.5   92.41    4970   92.41  4970.2   92.91 4972.58  93.463  4973.9   93.77
  4995.8   92.97  5044.8   93.14  5120.4   94.09  5126.9    93.2  5137.1   93.69
  5157.6   93.51  5163.2   93.95  5168.3   93.56    5206   93.55  5270.5   94.95
  5332.1   94.81  5339.6   95.37  5387.6   96.42  5403.9   97.66  5468.3   97.97
#Mann= 3 , 0 , 0
  4753.4     .12       0  4958.5     .03       0 4972.58     .12       0
Bank Sta=4958.5,4972.58
XS Rating Curve= 0 ,0
Exp/Cntr=0.3,0.1

Type RM Length L Ch R = 1 ,2000    ,500,500,500
BEGIN DESCRIPTION:
Crystal Creek 006 4.0
END DESCRIPTION:
XS GIS Cut Line= 3
      3869332.95     10040916.23      3869577.76     10040871.28
      3870128.08     10040812.06
#Sta/Elev= 30
  4751.1   99.08  4766.3   98.43  4804.6   98.52  4809.7   98.04  4857.7   97.57
  4974.1   92.93 4991.93  93.068  4995.5    92.8  4995.8    92.3  5010.2   93.07
    5052   93.72  5070.5   92.95  5080.6   93.08  5087.5   93.87  5110.7   95.74
  5120.8   95.83  5201.3   93.23  5221.4   93.44    5231   94.11  5251.5   93.51
  5261.6   94.01  5271.7   93.38  5299.4   94.27  5321.9   94.01    5328   94.74
  5392.3   95.48  5412.5   96.51    5428    95.9  5468.5   97.74  5553.5   98.83
#Mann= 7 ,-1 , 0
  4751.1     .12       0 4991.93     .07       0  5010.2     .12       0
  5087.5      .1       0  5299.4     .12       0    5428      .1       0
  5468.5     .12       0
Bank Sta=4991.93,5010.2
XS Rating Curve= 0 ,0
Exp/Cntr=0.3,0.1

Type RM Length L Ch R = 1 ,1500    ,500,500,500
BEGIN DESCRIPTION:
Crystal Creek 006 3.0
END DESCRIPTION:
XS GIS Cut Line= 3
      3869294.78     10041409.28      3869640.07     10041349.64
       3869940.6     10041343.31
#Sta/Elev= 30
  4649.6   96.68  4675.4   96.55  4683.2   96.16  4713.6   96.01    4728   95.54
  4754.2   96.23  4774.5   96.16  4825.2   94.75  4839.1   94.67  4916.6   94.78
 4930.31  93.472  4955.1   92.86  4955.4   92.36  4958.9   92.36  4959.1   92.86
  4967.3   93.48  5017.8   92.91  5027.8   93.46  5047.8   92.92  5056.7    93.2
  5087.8   93.36  5117.8   94.64  5157.8   95.35  5166.1   96.02  5171.1   95.96
  5177.8   97.24  5197.8   96.93  5217.8   97.65  5267.8   97.66  5300.6   98.26
#Mann= 7 ,-1 , 0
  4649.6      .1       0  4675.4     .12       0  4839.1      .1       0
 4930.31     .03       0  4967.3      .1       0  5056.7     .12       0
  5117.8      .1       0
Bank Sta=4930.31,4967.3
XS Rating Curve= 0 ,0
Exp/Cntr=0.3,0.1

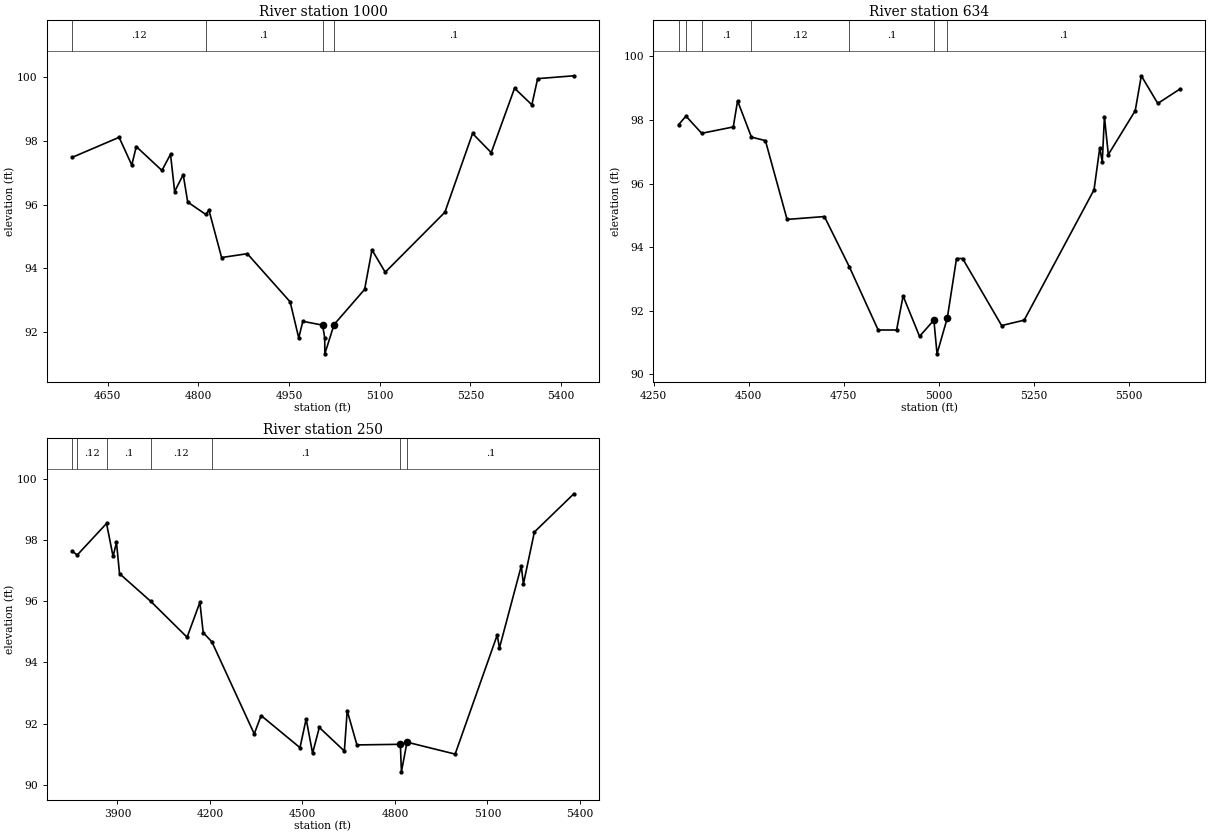
Type RM Length L Ch R = 1 ,1000    ,366,366,366
BEGIN DESCRIPTION:
Crystal Creek 006 2.0
END DESCRIPTION:
XS GIS Cut Line= 3
      3869226.69     10041552.41      3869528.24     10041828.58
      3869912.54     10041655.94
#Sta/Elev= 30
  4591.1   97.48  4668.9   98.11  4689.9   97.24  4697.3   97.82  4739.8   97.07
    4754   97.58  4760.8   96.41    4775   96.94  4782.4   96.08  4812.4   95.69
  4817.5   95.83  4838.5   94.34    4881   94.46  4951.9   92.95  4966.1   91.82
  4972.9   92.34  5005.6   92.22  5009.1   91.82  5009.3   91.32  5024.5  92.237
  5075.1   93.34  5087.3   94.58  5109.2   93.88  5207.9   95.76  5253.7   98.23
  5284.6   97.63  5323.2   99.65  5351.8   99.13  5361.4   99.95  5421.3  100.04
#Mann= 4 ,-1 , 0
  4591.1     .12       0  4812.4      .1       0  5005.6     .07       0
  5024.5      .1       0
Bank Sta=5005.6,5024.5
XS Rating Curve= 0 ,0
Exp/Cntr=0.3,0.1

Type RM Length L Ch R = 1 ,634     ,384,384,384
BEGIN DESCRIPTION:
Mapping XS 2da346ee
END DESCRIPTION:
XS GIS Cut Line= 4
       3869169.4     10041512.46      3869349.82     10042101.53
      3869418.24     10042106.86      3869972.75     10041796.01
#Sta/Elev= 30
  4315.3   97.85  4334.9   98.12  4376.3   97.58  4459.3   97.78  4470.7    98.6
  4507.1   97.46  4543.9   97.35  4600.9   94.87  4699.1   94.96  4764.7   93.38
  4840.6   91.39  4889.1   91.39  4906.2   92.46  4949.5   91.19  4987.2    91.7
  4995.5   90.64  5022.6  91.773  5046.8   93.64  5062.8   93.64  5165.5   91.53
  5224.8    91.7  5408.6    95.8  5423.7   97.12  5430.3   96.68    5436    98.1
  5446.2   96.91    5517   98.29    5533   99.39  5576.4   98.52  5635.7   98.98
#Mann= 7 ,-1 , 0
  4315.3      .1       0  4334.9     .12       0  4376.3      .1       0
  4507.1     .12       0  4764.7      .1       0  4987.2     .07       0
  5022.6      .1       0
Bank Sta=4987.2,5022.6
XS Rating Curve= 0 ,0
Exp/Cntr=0.3,0.1

Type RM Length L Ch R = 1 ,250     ,0,0,0
BEGIN DESCRIPTION:
Crystal Creek 006 1.0
END DESCRIPTION:
XS GIS Cut Line= 4
      3869103.05      10041483.6       3869329.6     10042243.99
      3869779.26     10042164.46      3870038.19     10041890.25
#Sta/Elev= 30
  3752.9   97.63  3769.8   97.51  3864.7   98.54  3885.9   97.46  3896.9   97.92
  3906.8    96.9  4008.4   95.99  4125.9   94.82  4167.4   95.96  4178.1   94.97
  4206.3   94.67  4343.7   91.66  4365.9   92.26    4492   91.21    4512   92.15
  4532.8   91.03  4554.7   91.87  4635.9    91.1  4645.1   92.42  4676.6    91.3
  4817.5   91.32  4820.9   90.42    4839   91.39  4995.1      91  5131.5   94.89
  5138.8   94.47  5209.6   97.15  5216.5   96.56  5252.1   98.26  5380.1   99.51
#Mann= 7 ,-1 , 0
  3752.9      .1       0  3769.8     .12       0  3864.7      .1       0
  4008.4     .12       0  4206.3      .1       0  4817.5     .07       0
    4839      .1       0
Bank Sta=4817.5,4839
XS Rating Curve= 0 ,0
Exp/Cntr=0.3,0.1