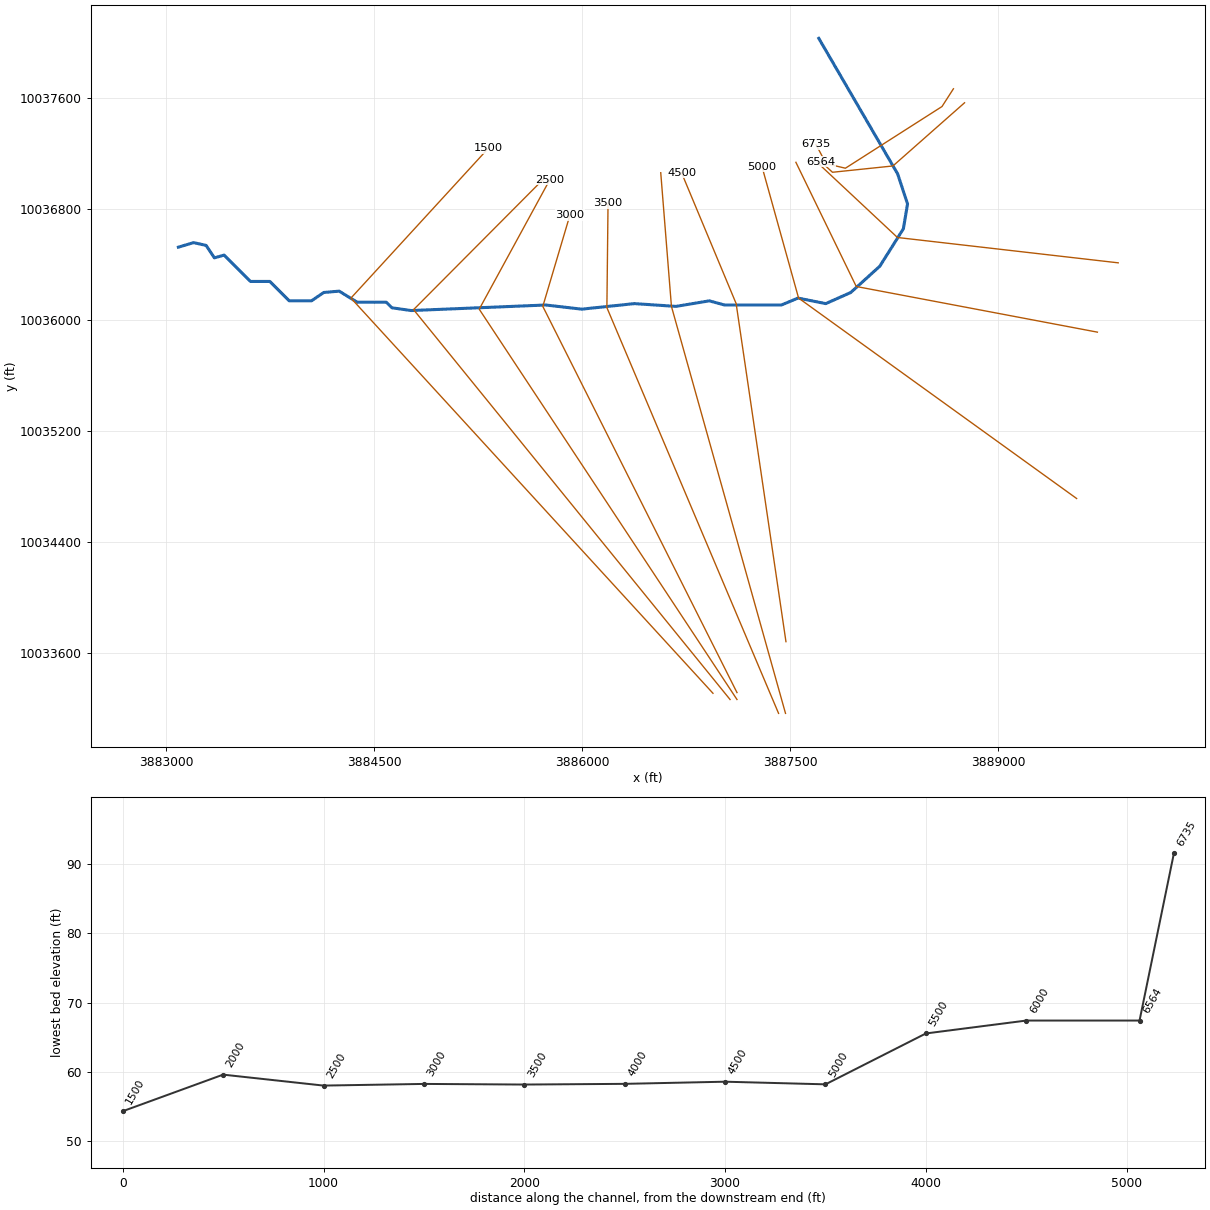
--- Crystal Creek 007.prj (project) ---

Proj Title=Crystal Creek 007 Base Level Engineering
Current Plan=p01
Default Exp/Contr=0.3,0.1
English Units
Geom File=g01
Flow File=f01
Flow File=f02
Plan File=p01
Y Axis Title=Elevation
X Axis Title(PF)=Main Channel Distance
X Axis Title(XS)=Station
BEGIN DESCRIPTION:
Crystal Creek 007
END DESCRIPTION:
DSS File=dss
DSS Export Rating Curves= 0
DSS Export Rating Curve Sorted= 0
DSS Export Volume Flow Curves= 0
DXF OffsetX= 0
DXF OffsetY= 0
DXF ScaleX= 1
DXF ScaleY= 10

--- Crystal Creek 007.p01 (plan) ---

Plan Title=Multiple Run
Program Version=4.10
Short Identifier=Multiple Run
Geom File=g01
Flow File=f01
Subcritical Flow
K Sum by GR= 0
Std Step Tol= 0.01
Critical Tol= 0.01
Num of Std Step Trials= 20
Max Error Tol= 0.3
Flow Tol Ratio= 0.001
Split Flow NTrial= 30
Split Flow Tol= 0.02
Split Flow Ratio= 0.02
Log Output Level= 0
Friction Slope Method= 1
Unsteady Friction Slope Method= 2
Unsteady Bridges Friction Slope Method= 1
Parabolic Critical Depth
Global Vel Dist= 1 , 1 , 1
Global Log Level= 0
CheckData=True
Encroach Param=-1 ,0,0, 0
BEGIN DESCRIPTION:
Multiple Run
END DESCRIPTION:
Computation Interval=1HOUR
Output Interval=1HOUR
Run HTab= 0
Run UNet= 0
Run PostProcess= 0
Run WQNet= 0
UNET Theta= 1
UNET Theta Warmup= 1
UNET ZTol= 0.02
UNET ZSATol= 0.05
UNET MxIter= 20
UNET MaxInSteps= 0
UNET DtIC= 0
UNET DtMin= 0
UNET MaxCRTS= 20
UNET WFStab= 2
UNET SFStab= 1
UNET WFX= 1
UNET SFX= 1
UNET DSS MLevel= 4
UNET DZMax Abort= 100
UNET Convert EG Bridges= 0
UNET Use Existing IB Tables=-1
UNET Froude Reduction=False
UNET Froude Limit= 1
UNET Froude Power= 10
UNET Time Slicing=0,0, 5
UNET Junction Losses=0
Instantaneous Interval=1HOUR
DSS File=dss
Write IC File= 0
Write IC File at Sim End=0
Echo Input=False
Echo Parameters=False
Echo Output=False
Write Detailed= 0
WQ AD Non Conservative
WQ ULTIMATE=-1
WQ Max Comp Step=1HOUR
WQ Output Interval=15MIN
WQ Output Selected Increments= 0
WQ Output face flow=0
WQ Output face velocity=0
WQ Output face area=0
WQ Output face dispersion=0
WQ Output cell volume=0
WQ Output cell surface area=0
WQ Output cell continuity=0
WQ Output cumulative cell continuity=0
WQ Output face conc=0
WQ Output face dconc_dx=0
WQ Output face courant=0
WQ Output face peclet=0
WQ Output face adv mass=0
WQ Output face disp mass=0
WQ Output cell mass=0
WQ Output cell source sink temp=0
WQ Output cell source sink nsm=0
WQ Output MaxMinRange=-1
WQ Daily Max Min Mean=-1
WQ Daily Range=0
WQ Daily Time=0
WQ Create Restart=0
WQ Fixed Restart=0
WQ System Summary=0
WQ Use Fixed Temperature=0
Sorting and Armoring Iterations= 10
XS Update Threshold= 0.02
Hydraulics Update Threshold= 0.02
Energy Slope Method= 1
Volume Change Method= 0
XS Weighting Method= 0
Number of US Weighted Cross Sections= 1
Number of DS Weighted Cross Sections= 1
Upstream XS Weight=0.25
Main XS Weight=0.5
Downstream XS Weight=0.25
Number of DS XS's Weighted with US Boundary= 1
Upstream Boundary Weight= 1
Weight of XSs Associated with US Boundary= 0
Number of US XS's Weighted with DS Boundary= 1
Downstream Boundary Weight= 0.5
Weight of XSs Associated with DS Boundary= 0.5
Sediment Output Level= 4
Mass or Volume Output= 0
Output Increment Type= 1
Profile and TS Output Increment= 10
XS Output Flag= 0
XS Output Increment= 10
Disregard all LS=0
Disregard all Conn=0
Disregard all Breaches=0
Disregard all Pumps=0

--- Crystal Creek 007.f01 (steady flow) ---

Flow Title=Multiple
Program Version=4.10
Number of Profiles= 7
Profile Names=10-year,25-year,50-year,1pct_min,100-year,1pct_plu,500-year
River Rch & RM=Crystal Creek 00,Reach-1         ,6735
     709     915    1195     511    1543    4660    2661
River Rch & RM=Crystal Creek 00,Reach-1         ,5000
    1144    1543    2079     917    2770    8365    5088
Boundary for River Rch & Prof#=Crystal Creek 00,Reach-1         , 1
Up Type= 0
Dn Type= 3
Dn Slope=0.01
Boundary for River Rch & Prof#=Crystal Creek 00,Reach-1         , 2
Up Type= 0
Dn Type= 3
Dn Slope=0.01
Boundary for River Rch & Prof#=Crystal Creek 00,Reach-1         , 3
Up Type= 0
Dn Type= 3
Dn Slope=0.01
Boundary for River Rch & Prof#=Crystal Creek 00,Reach-1         , 4
Up Type= 0
Dn Type= 3
Dn Slope=0.01
Boundary for River Rch & Prof#=Crystal Creek 00,Reach-1         , 5
Up Type= 0
Dn Type= 3
Dn Slope=0.01
Boundary for River Rch & Prof#=Crystal Creek 00,Reach-1         , 6
Up Type= 0
Dn Type= 3
Dn Slope=0.01
Boundary for River Rch & Prof#=Crystal Creek 00,Reach-1         , 7
Up Type= 0
Dn Type= 3
Dn Slope=0.01
DSS Import GetInterval= 0
DSS Import GetPeak= 0
DSS Import FillOption= 0

--- Crystal Creek 007.f02 (steady flow) ---

Flow Title=Orig_BLE_Flow
Program Version=4.10
Number of Profiles= 7
Profile Names=10-year,25-year,50-year,1pct_min,100-year,1pct_plu,500-year
River Rch & RM=Crystal Creek 00,Reach-1         ,6735
     709     897    1039     393    1187    3585    1547
River Rch & RM=Crystal Creek 00,Reach-1         ,5000
    1144    1513    1808     706    2131    6437    2958
Boundary for River Rch & Prof#=Crystal Creek 00,Reach-1         , 1
Up Type= 0
Dn Type= 3
Dn Slope=0.01
Boundary for River Rch & Prof#=Crystal Creek 00,Reach-1         , 2
Up Type= 0
Dn Type= 3
Dn Slope=0.01
Boundary for River Rch & Prof#=Crystal Creek 00,Reach-1         , 3
Up Type= 0
Dn Type= 3
Dn Slope=0.01
Boundary for River Rch & Prof#=Crystal Creek 00,Reach-1         , 4
Up Type= 0
Dn Type= 3
Dn Slope=0.01
Boundary for River Rch & Prof#=Crystal Creek 00,Reach-1         , 5
Up Type= 0
Dn Type= 3
Dn Slope=0.01
Boundary for River Rch & Prof#=Crystal Creek 00,Reach-1         , 6
Up Type= 0
Dn Type= 3
Dn Slope=0.01
Boundary for River Rch & Prof#=Crystal Creek 00,Reach-1         , 7
Up Type= 0
Dn Type= 3
Dn Slope=0.01
DSS Import GetInterval= 0
DSS Import GetPeak= 0
DSS Import FillOption= 0

--- Crystal Creek 007.g01 (geometry) ---

Geom Title=Existing Conditions
Program Version=4.10

River Reach=Crystal Creek 00,Reach-1
Reach XY= 30
      3887707.95     10038030.51        3888277.     10037052.18
      3888348.24     10036835.62      3888318.24     10036656.86
      3888148.24     10036386.86      3887938.24     10036196.86
      3887758.24     10036116.86      3887558.24     10036156.86
      3887438.24     10036106.86      3887028.24     10036106.86
      3886918.24     10036136.86      3886678.24     10036096.86
      3886378.24     10036116.86      3885998.24     10036076.86
      3885738.24     10036106.86      3884768.24     10036066.86
      3884628.24     10036086.86      3884588.24     10036126.86
      3884378.24     10036126.86      3884248.24     10036206.86
      3884137.24     10036197.28      3884048.24     10036136.86
      3883888.24     10036136.86      3883748.24     10036276.86
      3883608.24     10036276.86      3883418.24     10036466.86
      3883348.24     10036446.86      3883288.24     10036536.86
      3883198.24     10036556.86       3883088.3     10036524.09

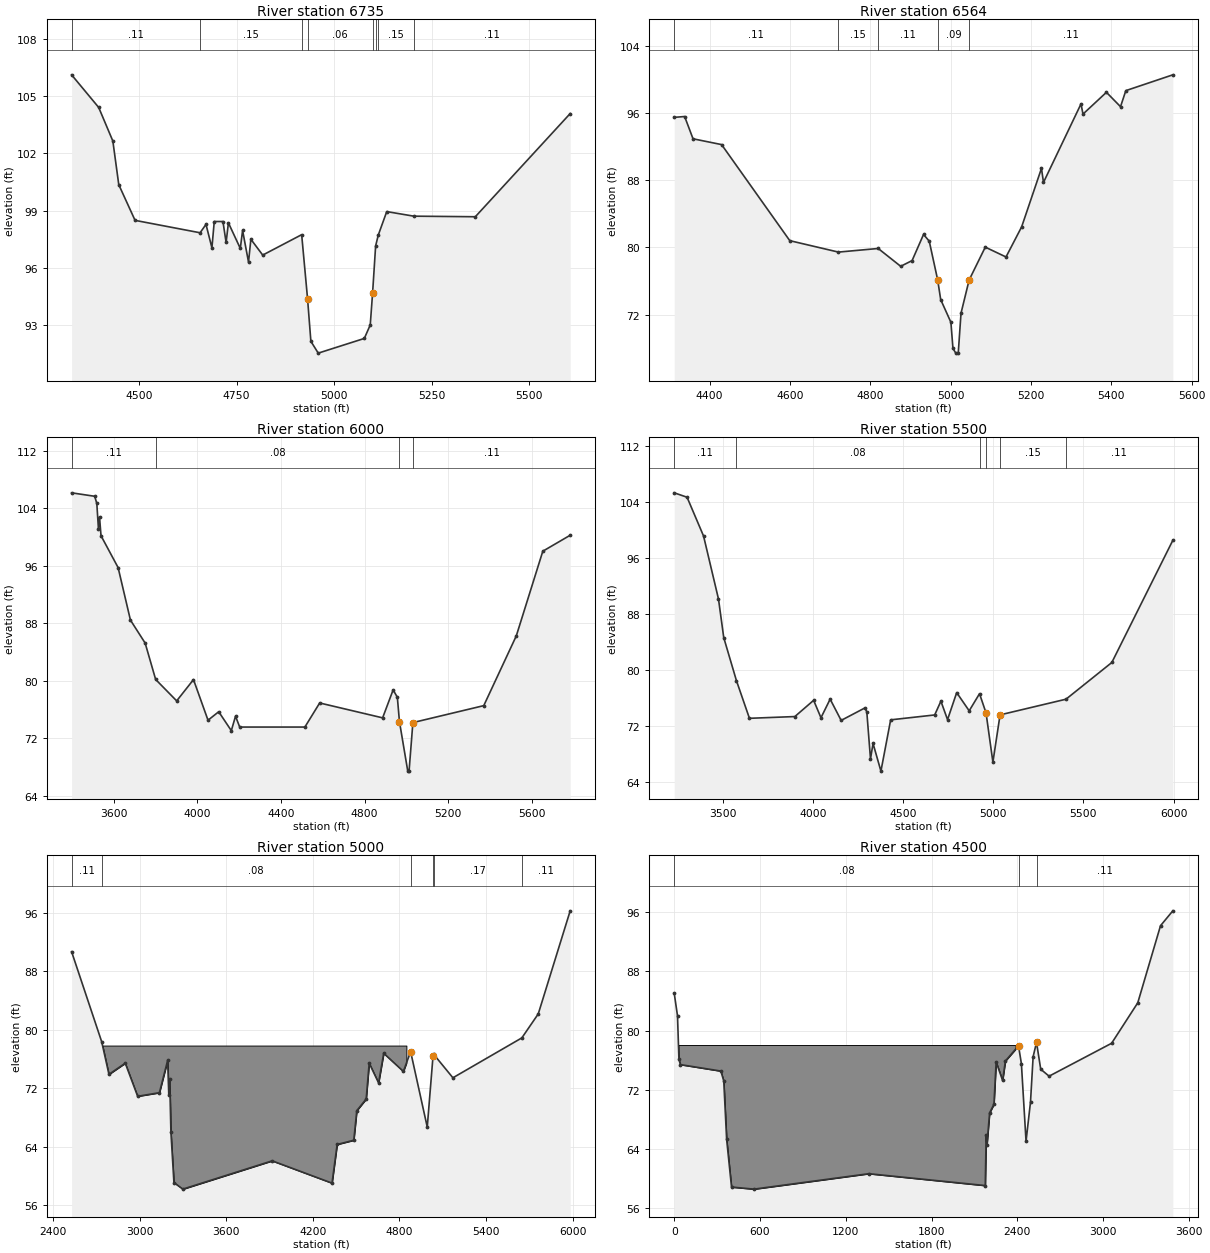
Type RM Length L Ch R = 1 ,6735    ,171,171,171
BEGIN DESCRIPTION:
Mapping XS 5325128f
END DESCRIPTION:
XS GIS Cut Line= 5
      3888679.16     10037666.61      3888596.67     10037538.54
      3887900.05     10037093.66      3887761.16     10037126.22
      3887687.39     10037265.09
#Sta/Elev= 30
  4326.7  106.12  4396.2  104.41  4432.5  102.65  4447.7  100.36  4489.5   98.49
  4656.3   97.84  4671.4   98.28  4686.6   97.05  4692.6   98.43  4714.9   98.43
    4723   97.33  4728.9   98.36  4759.4   97.02  4765.3   97.96  4780.5    96.3
  4786.5    97.5  4816.9   96.67  4916.8   97.74    4932   94.36  4940.4   92.15
  4959.3   91.53  5077.5    92.3  5092.7   93.01  5098.7   94.68  5106.5   97.15
  5113.3   97.72    5135   98.95  5204.5   98.71  5362.2   98.68  5605.5  104.09
#Mann= 8 ,-1 , 0
  4326.7     .11       0  4656.3     .15       0  4916.8     .08       0
    4932     .06       0  5098.7     .08       0  5106.5     .11       0
  5113.3     .15       0  5204.5     .11       0
Bank Sta=4932,5098.7
XS Rating Curve= 0 ,0
Exp/Cntr=0.3,0.1

Type RM Length L Ch R = 1 ,6564    ,564,564,564
BEGIN DESCRIPTION:
Crystal Creek 007 13.0
END DESCRIPTION:
XS GIS Cut Line= 4
      3888759.44     10037565.68      3888242.94     10037109.94
      3887806.74     10037064.37      3887722.54     10037141.07
#Sta/Elev= 30
  4311.8   95.47  4337.7   95.57  4358.6   92.92  4429.7   92.23  4599.5    80.8
  4720.6   79.44  4819.6   79.87  4875.6   77.75    4904   78.43  4932.5   81.54
  4946.7   80.74  4967.6   76.15  4975.2   73.79  5000.6   71.09  5005.7   67.99
  5012.7   67.42  5018.9   67.42  5025.8   72.17    5046   76.12  5086.2   80.03
  5137.8   78.86  5176.7   82.44  5226.1    89.4  5231.1   87.73  5324.5   97.07
  5329.5   95.86  5387.8   98.45  5422.9   96.74  5436.1   98.65  5553.1  100.53
#Mann= 5 ,-1 , 0
  4311.8     .11       0  4720.6     .15       0  4819.6     .11       0
  4967.6     .09       0    5046     .11       0
Bank Sta=4967.6,5046
XS Rating Curve= 0 ,0
Exp/Cntr=0.3,0.1

Type RM Length L Ch R = 1 ,6000    ,500,500,500
BEGIN DESCRIPTION:
Crystal Creek 007 12.0
END DESCRIPTION:
XS GIS Cut Line= 3
      3889867.82     10036411.07      3888275.29     10036593.91
       3887702.1     10037130.27
#Sta/Elev= 30
    3397  106.13  3507.7  105.65  3517.8  104.65  3525.6   101.1  3530.7  102.79
  3537.9  100.16  3619.8   95.73  3678.8   88.43  3749.3   85.23  3799.6   80.17
  3900.3   77.19  3980.8   80.15  4050.4    74.5  4101.6   75.68    4162   73.05
  4182.1   75.06  4202.2   73.55  4514.3   73.55  4585.2    76.9  4886.7   74.83
    4937   78.72  4957.2   77.69  4967.2   74.32  5007.1   67.42  5013.3   67.42
  5031.6   74.17  5371.1   76.53  5526.9   86.23  5653.9   98.01    5785  100.23
#Mann= 4 ,-1 , 0
    3397     .11       0  3799.6     .08       0  4967.2     .09       0
  5031.6     .11       0
Bank Sta=4967.2,5031.6
XS Rating Curve= 0 ,0
Exp/Cntr=0.3,0.1

Type RM Length L Ch R = 1 ,5500    ,500,500,500
BEGIN DESCRIPTION:
Crystal Creek 007 11.0
END DESCRIPTION:
XS GIS Cut Line= 3
      3889717.84     10035911.07      3887978.24     10036240.39
      3887542.87      10037136.2
#Sta/Elev= 30
  3229.5  105.34  3300.7  104.71  3392.3   99.16  3475.1   90.16  3504.3   84.64
  3574.7   78.49  3646.8   73.11  3898.8   73.36    4003   75.68  4043.7   73.19
  4094.6   75.85  4155.7   72.81    4288    74.6  4298.1   74.01  4318.5   67.31
  4332.7   69.51  4376.4   65.56  4430.4   72.89  4674.7   73.59  4709.2   75.56
    4746   72.92  4796.8   76.78  4866.1   74.18  4923.5   76.63  4959.7   73.87
  4997.7   66.85  5037.4    73.6  5403.2   75.84  5657.6   81.09    5996   98.55
#Mann= 6 ,-1 , 0
  3229.5     .11       0  3574.7     .08       0  4923.5     .15       0
  4959.7     .07       0  5037.4     .15       0  5403.2     .11       0
Bank Sta=4959.7,5037.4
XS Rating Curve= 0 ,0
Exp/Cntr=0.3,0.1

Type RM Length L Ch R = 1 ,5000    ,500,500,500
BEGIN DESCRIPTION:
Crystal Creek 007 10.0
END DESCRIPTION:
XS GIS Cut Line= 3
      3889567.89     10034711.05      3887562.18     10036156.86
      3887298.48     10037104.25
#Sta/Elev= 30
  2527.5    90.7  2736.1   78.38  2786.4   73.92  2899.4   75.45  2985.3   70.92
  3136.2   71.41  3193.2   75.83  3201.2   71.12  3207.4   73.22  3215.9      66
  3236.8   59.12  3298.7   58.22  3917.8   62.09  4332.6   59.04  4368.2   64.33
  4483.5   64.91  4504.4   68.96  4569.4   70.55  4590.3   75.45  4655.3   72.75
  4690.9    76.8  4827.1   74.32  4877.4   77.03  4992.7   66.71  5032.5   76.38
  5037.7   76.65  5170.5   73.45  5648.4   78.91  5762.1   82.19  5983.4   96.29
#Mann= 6 ,-1 , 0
  2527.5     .11       0  2736.1     .08       0  4877.4     .07       0
  5032.5     .11       0  5037.7     .17       0  5648.4     .11       0
#Block Obstruct= 2 , 0
       0    4848   77.86               0
Bank Sta=4877.4,5032.5
XS Rating Curve= 0 ,0
Exp/Cntr=0.3,0.1

Type RM Length L Ch R = 1 ,4500    ,500,500,500
XS GIS Cut Line= 3
      3887471.11     10033678.39      3887111.88     10036116.86
      3886717.85     10037061.07
#Sta/Elev= 30
       0   85.02    22.9   81.99      33    76.1    43.1    75.4   326.1   74.53
   346.4    73.2   366.6   65.32   400.8   58.88   558.6    58.6  1361.3   60.68
  2175.9   59.08  2182.3   65.94  2187.4   64.52  2206.2   68.88  2236.6   70.06
    2252   75.76  2297.2   73.26  2316.6   75.89  2408.4   77.94  2428.6   75.53
  2461.1   65.06  2492.3   70.35  2510.7   76.47  2534.4    78.4  2563.8   74.78
  2622.3   73.84  3059.7   78.28  3242.7   83.74  3401.8   94.14  3487.9   96.15
#Mann= 3 , 0 , 0
       0     .08       0  2408.4     .07       0  2534.4     .11       0
#Block Obstruct= 2 , 0
       0  2386.3   78.04               0
Bank Sta=2408.4,2534.4
XS Rating Curve= 0 ,0
Exp/Cntr=0.3,0.1

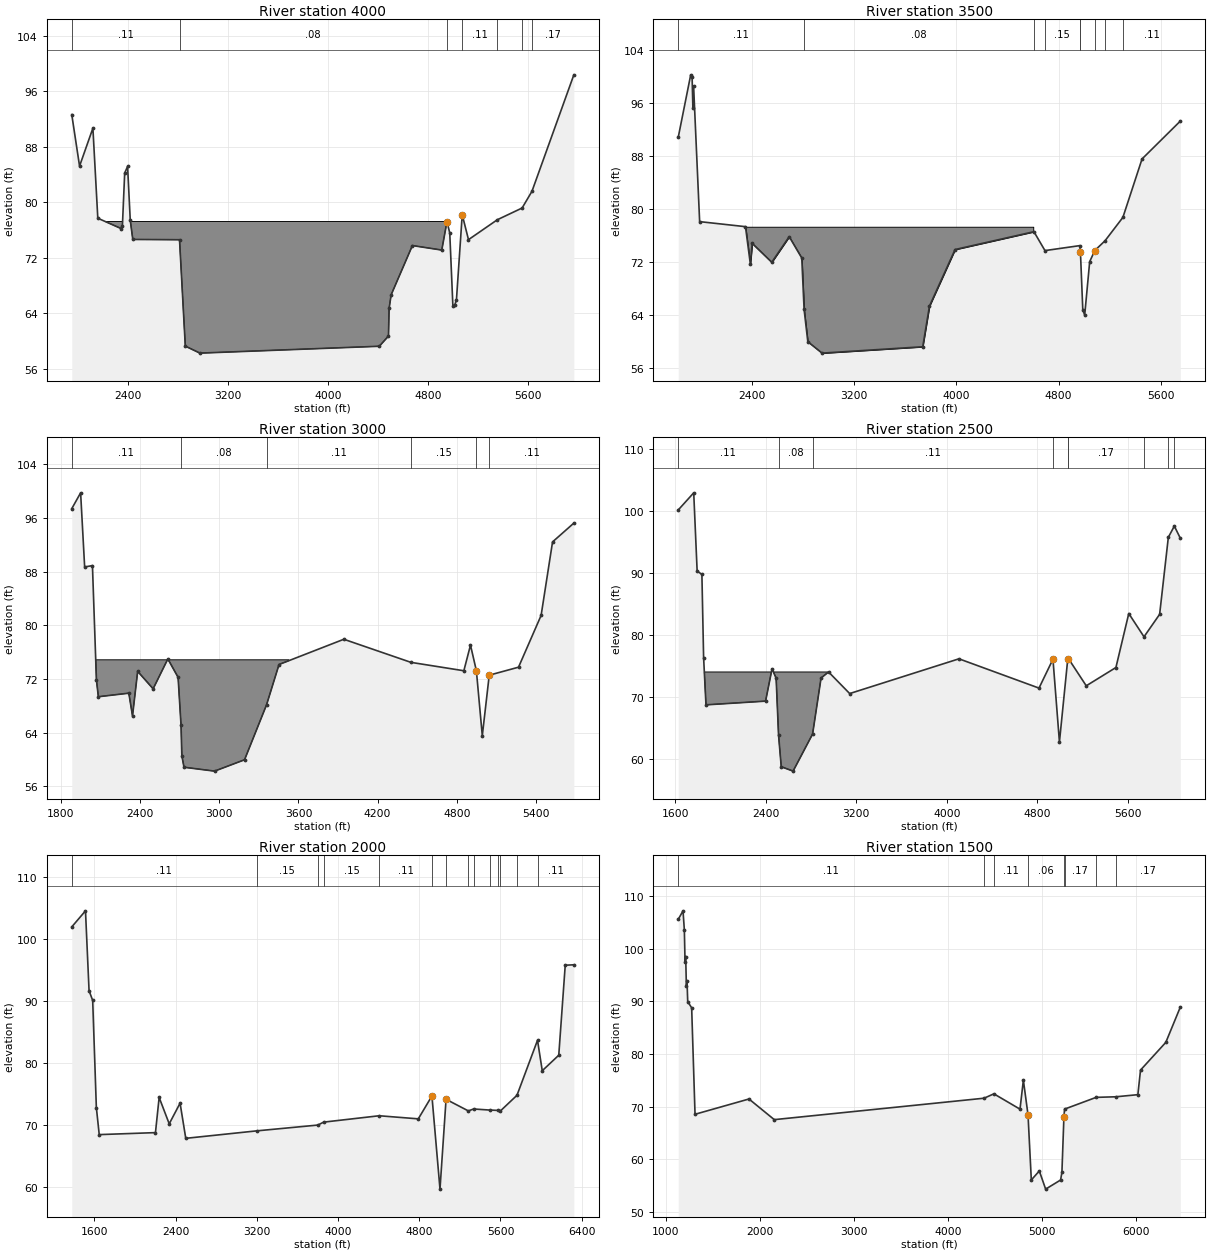
Type RM Length L Ch R = 1 ,4000    ,500,500,500
BEGIN DESCRIPTION:
Crystal Creek 007 8.0
END DESCRIPTION:
XS GIS Cut Line= 3
      3887467.85     10033161.09      3886645.02     10036096.86
      3886567.85     10037061.08
#Sta/Elev= 30
  1951.1   92.66  2013.4   85.24  2120.1    90.7  2159.4   77.73  2345.7   76.24
  2356.1    76.6  2374.4   84.24  2397.6   85.19  2418.9   77.45  2439.2   74.67
  2813.1   74.63  2859.3    59.3    2976   58.29  4411.2   59.28  4484.6   60.75
  4489.8   64.76  4505.9   66.69  4675.9   73.79  4910.9   73.14  4952.4   77.25
  4974.7    75.6  4999.6   65.15  5014.3   65.21  5028.2   65.97  5074.4   78.23
  5124.6   74.64  5355.3   77.51  5553.5    79.2  5632.3   81.61  5967.3   98.39
#Mann= 7 ,-1 , 0
  1951.1     .11       0  2813.1     .08       0  4952.4     .07       0
  5074.4     .11       0  5355.3     .17       0  5553.5     .11       0
  5632.3     .17       0
#Block Obstruct= 2 , 0
       0  4952.4   77.25               0
Bank Sta=4952.4,5074.4
XS Rating Curve= 0 ,0
Exp/Cntr=0.3,0.1

Type RM Length L Ch R = 1 ,3500    ,500,500,500
BEGIN DESCRIPTION:
Crystal Creek 007 7.0
END DESCRIPTION:
XS GIS Cut Line= 3
      3887417.86     10033161.05      3886179.39     10036088.02
      3886187.71     10036840.57
#Sta/Elev= 30
  1821.8   90.75  1919.5  100.18  1930.4   99.84  1936.6   95.13    1942   98.52
  1989.4   78.03  2348.2   77.27  2386.5   71.62    2401   74.75    2554    71.9
  2690.5   75.76  2788.9   72.54  2807.2   64.78  2836.3   59.92  2947.8   58.19
    3736   59.15  3788.8   65.29  3989.2   73.82  4606.6   76.51    4693   73.66
  4965.4   74.41  4970.8   73.39  4989.1   64.73    5004   63.93  5043.1   71.99
  5083.1   73.67  5163.1   75.14  5303.1   78.67  5453.1   87.49  5752.6    93.2
#Mann= 9 ,-1 , 0
  1821.8     .11       0  2807.2     .08       0  4606.6     .11       0
    4693     .15       0  4965.4     .11       0  4970.8     .07       0
  5083.1     .11       0  5163.1     .15       0  5303.1     .11       0
#Block Obstruct= 2 , 0
       0  4601.2   77.26               0
Bank Sta=4970.8,5083.1
XS Rating Curve= 0 ,0
Exp/Cntr=0.3,0.1

Type RM Length L Ch R = 1 ,3000    ,500,500,500
BEGIN DESCRIPTION:
Crystal Creek 007 6.0
END DESCRIPTION:
XS GIS Cut Line= 3
      3887117.85     10033311.08      3885717.15     10036096.86
      3885912.96     10036755.78
#Sta/Elev= 30
  1881.9   97.37    1949   99.73  1979.5   88.69  2038.6   88.89  2068.8   71.87
  2083.4   69.36  2314.4   69.89  2342.3    66.5  2381.4   73.14  2498.6   70.54
  2610.2   74.99  2687.8   72.25  2710.2   65.08  2716.2   60.57  2732.6   58.86
  2964.4   58.28  3191.5   59.97    3358   68.14  3452.9   74.16    3944   77.92
  4452.6   74.48  4853.7   73.23    4904   77.05  4948.7   73.23  4993.5   63.56
  5046.1   72.57  5268.1   73.76  5439.3   81.47    5526   92.42  5687.4   95.22
#Mann= 6 ,-1 , 0
  1881.9     .11       0  2710.2     .08       0    3358     .11       0
  4452.6     .15       0  4948.7     .07       0  5046.1     .11       0
#Block Obstruct= 2 , 0
       0  3527.2   74.86               0
Bank Sta=4948.7,5046.1
XS Rating Curve= 0 ,0
Exp/Cntr=0.3,0.1

Type RM Length L Ch R = 1 ,2500    ,500,500,500
BEGIN DESCRIPTION:
Crystal Creek 007 5.0
END DESCRIPTION:
XS GIS Cut Line= 3
      3887117.84     10033261.08      3885258.47     10036076.63
      3885767.87      10037011.1
#Sta/Elev= 30
  1625.9  100.13  1762.8  102.89    1793   90.29  1835.1   89.74  1850.2   76.35
  1871.2   68.72    2398   69.32  2455.2   74.53  2491.3   73.02  2512.7   63.85
  2536.5   58.75  2641.3   58.04 2813.66 64.0134  2888.6   73.05  2954.9   74.02
  3141.5   70.54  4107.7   76.14  4815.1   71.42  4938.5   76.08  4995.7   62.73
  5069.8   76.18  5075.5   76.17  5232.8   71.79  5495.1   74.74  5608.7   83.44
  5743.4   79.69  5881.5   83.31  5958.4   95.72  6011.4   97.53  6064.3   95.58
#Mann= 9 ,-1 , 0
  1625.9     .11       0  2512.7     .08       0 2813.66     .11       0
  4938.5     .07       0  5069.8     .11       0  5075.5     .17       0
  5743.4     .11       0  5958.4     .17       0  6011.4     .11       0
#Block Obstruct= 2 , 0
       0  2954.9   74.02               0
Bank Sta=4938.5,5069.8
XS Rating Curve= 0 ,0
Exp/Cntr=0.3,0.1

Type RM Length L Ch R = 1 ,2000    ,500,500,500
BEGIN DESCRIPTION:
Crystal Creek 007 4.0
END DESCRIPTION:
XS GIS Cut Line= 3
      3887067.86     10033261.06      3884784.83     10036073.46
      3885717.82     10037011.04
#Sta/Elev= 30
  1377.6   101.9  1512.7  104.49  1547.9   91.61  1583.7   90.04  1619.7   72.78
  1648.1   68.41  2201.9   68.73  2238.2    74.4  2337.4   70.15  2444.4   73.48
  2500.4   67.81  3197.6   69.01  3802.1   69.95  3857.8   70.42  4405.8   71.45
  4790.6   70.95  4924.9   74.64  5004.3   59.62  5064.1    74.1  5283.9   72.23
    5335   72.54  5493.3   72.37  5578.2   72.31    5597   72.19  5762.6   74.75
  5964.9   83.62  6011.6   78.71  6174.2   81.21  6237.9   95.72  6322.7   95.79
#Mann= 14 ,-1 , 0
  1377.6     .11       0  3197.6     .15       0  3802.1     .11       0
  3857.8     .15       0  4405.8     .11       0  4924.9     .06       0
  5064.1     .11       0  5283.9     .17       0    5335     .11       0
  5493.3     .15       0  5578.2     .17       0    5597     .15       0
  5762.6     .17       0  5964.9     .11       0
Bank Sta=4924.9,5064.1
XS Rating Curve= 0 ,0
Exp/Cntr=0.3,0.1

Type RM Length L Ch R = 1 ,1500    ,0,0,0
BEGIN DESCRIPTION:
Crystal Creek 007 3.0
END DESCRIPTION:
XS GIS Cut Line= 3
      3886944.67     10033305.88      3884333.13     10036156.86
       3885326.6     10037239.93
#Sta/Elev= 30
  1133.7  105.55  1184.5  107.17  1198.7  103.53  1206.1   97.38  1212.9   98.49
  1220.3   92.83  1227.1   93.81  1234.5   89.93  1276.4   88.76  1312.2   68.55
  1885.6   71.45  2154.5   67.53  4384.3    71.6  4488.4   72.43    4766   69.52
  4801.7   75.02  4851.1   68.46  4886.2   56.08  4971.3   57.79  5038.5   54.34
  5197.2   56.07  5211.4   57.52  5232.9   68.12  5239.7   69.53  5575.3   71.76
  5784.8   71.87  6018.5   72.27  6046.9   76.94  6315.7    82.2  6469.7   88.89
#Mann= 8 ,-1 , 0
  1133.7     .11       0  4384.3     .15       0  4488.4     .11       0
  4851.1     .06       0  5232.9     .08       0  5239.7     .17       0
  5575.3     .15       0  5784.8     .17       0
Bank Sta=4851.1,5232.9
XS Rating Curve= 0 ,0
Exp/Cntr=0.3,0.1

Chan Stop Cuts=-1
Use User Specified Reach Order=0
Composite Channel Slope=5

--- Crystal Creek 007.g10 (geometry) ---

Geom Title=Existing Conditions
Program Version=4.10

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
River Reach=Crystal Creek 00,Reach-1

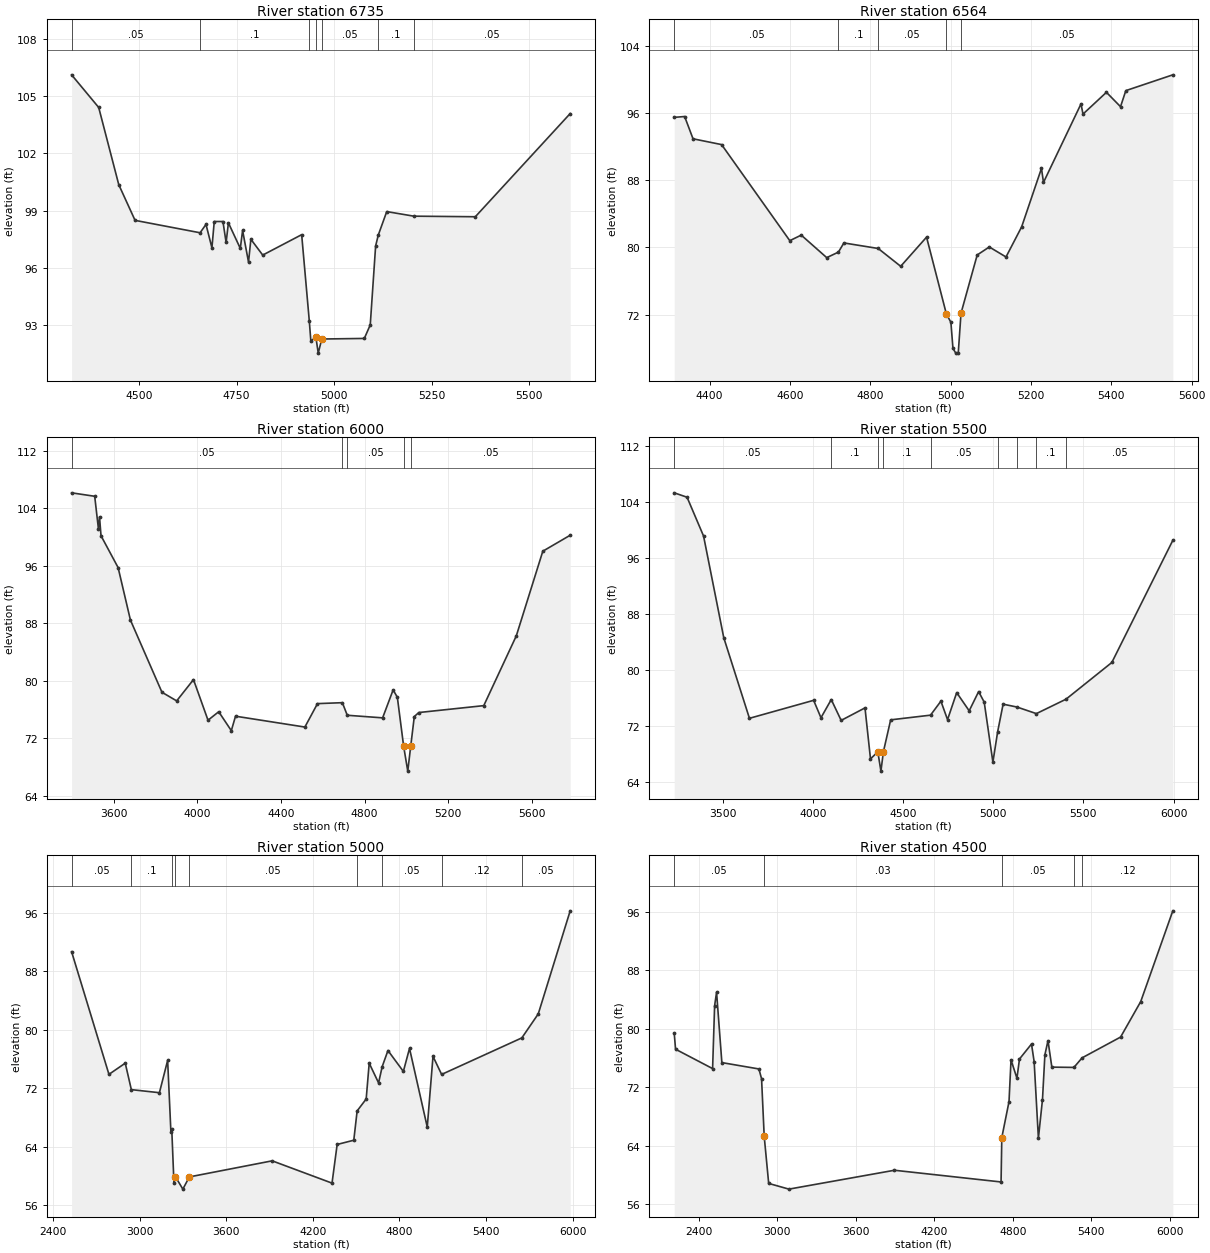
Type RM Length L Ch R = 1 ,6735    ,171,171,171
BEGIN DESCRIPTION:
Mapping XS 5325128f
END DESCRIPTION:
XS GIS Cut Line= 5
      3888679.16     10037666.61      3888596.67     10037538.54
      3887900.05     10037093.66      3887761.16     10037126.22
      3887687.39     10037265.09
#Sta/Elev= 30
  4326.7  106.12  4396.2  104.41  4447.7  100.36  4489.5   98.49  4656.3   97.84
  4671.4   98.28  4686.6   97.05  4692.6   98.43  4714.9   98.43    4723   97.33
  4728.9   98.36  4759.4   97.02  4765.3   97.96  4780.5    96.3  4786.5    97.5
  4816.9   96.67  4916.8   97.74  4936.3   93.23  4940.4   92.15  4953.1   92.39
  4959.3   91.53  4968.4   92.27  5077.5    92.3  5092.7   93.01  5106.5   97.15
  5113.3   97.72    5135   98.95  5204.5   98.71  5362.2   98.68  5605.5  104.09
#Mann= 7 ,-1 , 0
  4326.7     .05       0  4656.3      .1       0  4936.3     .05       0
  4953.1     .03       0  4968.4     .05       0  5113.3      .1       0
  5204.5     .05       0
Bank Sta=4953.1,4968.4
XS Rating Curve= 0 ,0
Exp/Cntr=0.3,0.1

Type RM Length L Ch R = 1 ,6564    ,564,564,564
BEGIN DESCRIPTION:
Crystal Creek 007 13.0
END DESCRIPTION:
XS GIS Cut Line= 4
      3888759.44     10037565.68      3888242.94     10037109.94
      3887806.74     10037064.37      3887722.54     10037141.07
#Sta/Elev= 30
  4311.8   95.47  4337.7   95.57  4358.6   92.92  4429.7   92.23  4599.5    80.8
    4628   81.46  4691.5   78.78  4720.6   79.44  4734.2   80.53  4819.6   79.87
  4875.6   77.75    4940   81.22  4989.4   72.07  5000.6   71.09  5005.7   67.99
  5012.7   67.42  5018.9   67.42  5025.8   72.17  5066.1    79.1  5096.2   80.05
  5137.8   78.86  5176.7   82.44  5226.1    89.4  5231.1   87.73  5324.5   97.07
  5329.5   95.86  5387.8   98.45  5422.9   96.74  5436.1   98.65  5553.1  100.53
#Mann= 5 ,-1 , 0
  4311.8     .05       0  4720.6      .1       0  4819.6     .05       0
  4989.4     .07       0  5025.8     .05       0
Bank Sta=4989.4,5025.8
XS Rating Curve= 0 ,0
Exp/Cntr=0.3,0.1

Type RM Length L Ch R = 1 ,6000    ,500,500,500
BEGIN DESCRIPTION:
Crystal Creek 007 12.0
END DESCRIPTION:
XS GIS Cut Line= 3
      3889867.82     10036411.07      3888275.29     10036593.91
       3887702.1     10037130.27
#Sta/Elev= 30
    3397  106.13  3507.7  105.65  3525.6   101.1  3530.7  102.79  3537.9  100.16
  3619.8   95.73  3678.8   88.43  3829.8   78.39  3900.3   77.19  3980.8   80.15
  4050.4    74.5  4101.6   75.68    4162   73.05  4182.1   75.06  4514.3   73.55
  4574.7   76.81  4693.9   76.94  4717.3   75.19  4886.7   74.83    4937   78.72
  4957.2   77.69  4987.4   70.87  5007.1   67.42  5021.4  70.937  5038.4   75.01
  5059.9   75.57  5371.1   76.53  5526.9   86.23  5653.9   98.01    5785  100.23
#Mann= 5 ,-1 , 0
    3397     .05       0  4693.9      .1       0  4717.3     .05       0
  4987.4     .07       0  5021.4     .05       0
Bank Sta=4987.4,5021.4
XS Rating Curve= 0 ,0
Exp/Cntr=0.3,0.1

Type RM Length L Ch R = 1 ,5500    ,500,500,500
BEGIN DESCRIPTION:
Crystal Creek 007 11.0
END DESCRIPTION:
XS GIS Cut Line= 3
      3889717.84     10035911.07      3887978.24     10036240.39
      3887542.87      10037136.2
#Sta/Elev= 30
  3229.5  105.34  3300.7  104.71  3392.3   99.16  3504.3   84.64  3646.8   73.11
    4003   75.68  4043.7   73.19  4100.8   75.79  4155.7   72.81    4288    74.6
  4318.5   67.31  4359.2   68.32  4376.4   65.56  4390.1   68.33  4430.4   72.89
  4651.6   73.56  4709.2   75.56    4746   72.92  4796.8   76.78  4866.1   74.18
  4918.5   76.93  4949.5   75.42  4997.7   66.85  5024.1    71.2  5054.4   75.13
  5131.5   74.72  5238.9   73.78  5403.2   75.84  5657.6   81.09    5996   98.55
#Mann= 9 ,-1 , 0
  3229.5     .05       0  4100.8      .1       0  4359.2     .03       0
  4390.1      .1       0  4651.6     .05       0  5024.1      .1       0
  5131.5     .05       0  5238.9      .1       0  5403.2     .05       0
Bank Sta=4359.2,4390.1
XS Rating Curve= 0 ,0
Exp/Cntr=0.3,0.1

Type RM Length L Ch R = 1 ,5000    ,500,500,500
BEGIN DESCRIPTION:
Crystal Creek 007 10.0
END DESCRIPTION:
XS GIS Cut Line= 3
      3889567.89     10034711.05      3887562.18     10036156.86
      3887298.48     10037104.25
#Sta/Elev= 30
  2527.5    90.7  2786.4   73.92  2899.4   75.45  2941.6   71.83  3136.2   71.41
  3193.2   75.83  3215.9      66  3221.8   66.41  3236.8   59.12 3247.58  59.899
  3298.7   58.22  3343.6   59.89  3917.8   62.09  4332.6   59.04  4368.2   64.33
  4483.5   64.91  4506.7   68.92  4569.4   70.55  4590.3   75.45  4655.3   72.75
  4680.4   74.98  4720.3   77.18  4827.1   74.32  4869.7   77.47  4992.7   66.71
  5032.5   76.38  5092.3   73.91  5648.4   78.91  5762.1   82.19  5983.4   96.29
#Mann= 9 ,-1 , 0
  2527.5     .05       0  2941.6      .1       0  3221.8     .05       0
 3247.58     .03       0  3343.6     .05       0  4506.7      .1       0
  4680.4     .05       0  5092.3     .12       0  5648.4     .05       0
Bank Sta=3247.58,3343.6
XS Rating Curve= 0 ,0
Exp/Cntr=0.3,0.1

Type RM Length L Ch R = 1 ,4500    ,500,500,500
BEGIN DESCRIPTION:
Crystal Creek 007 9.0
END DESCRIPTION:
XS GIS Cut Line= 3
      3887517.85     10033361.11      3887111.88     10036116.86
      3886717.86     10037061.05
#Sta/Elev= 30
  2214.5   79.42  2224.6   77.23  2507.6   74.58    2523   83.17  2537.9   85.02
  2578.4    75.4  2861.3   74.53  2881.6    73.2  2901.8   65.32    2936   58.88
  3090.6    58.1  3896.5   60.68  4711.1   59.08 4716.76  65.147  4771.8   70.06
  4787.2   75.76  4832.4   73.26  4851.8   75.89  4943.6   77.94  4963.8   75.53
  4996.3   65.06  5027.5   70.35  5045.9   76.47  5069.6    78.4    5099   74.78
  5267.6   74.74  5330.1   76.05  5624.1   78.89  5777.9   83.74  6023.1   96.15
#Mann= 5 ,-1 , 0
  2214.5     .05       0  2901.8     .03       0 4716.76     .05       0
  5267.6      .1       0  5330.1     .12       0
Bank Sta=2901.8,4716.76
XS Rating Curve= 0 ,0
Exp/Cntr=0.3,0.1

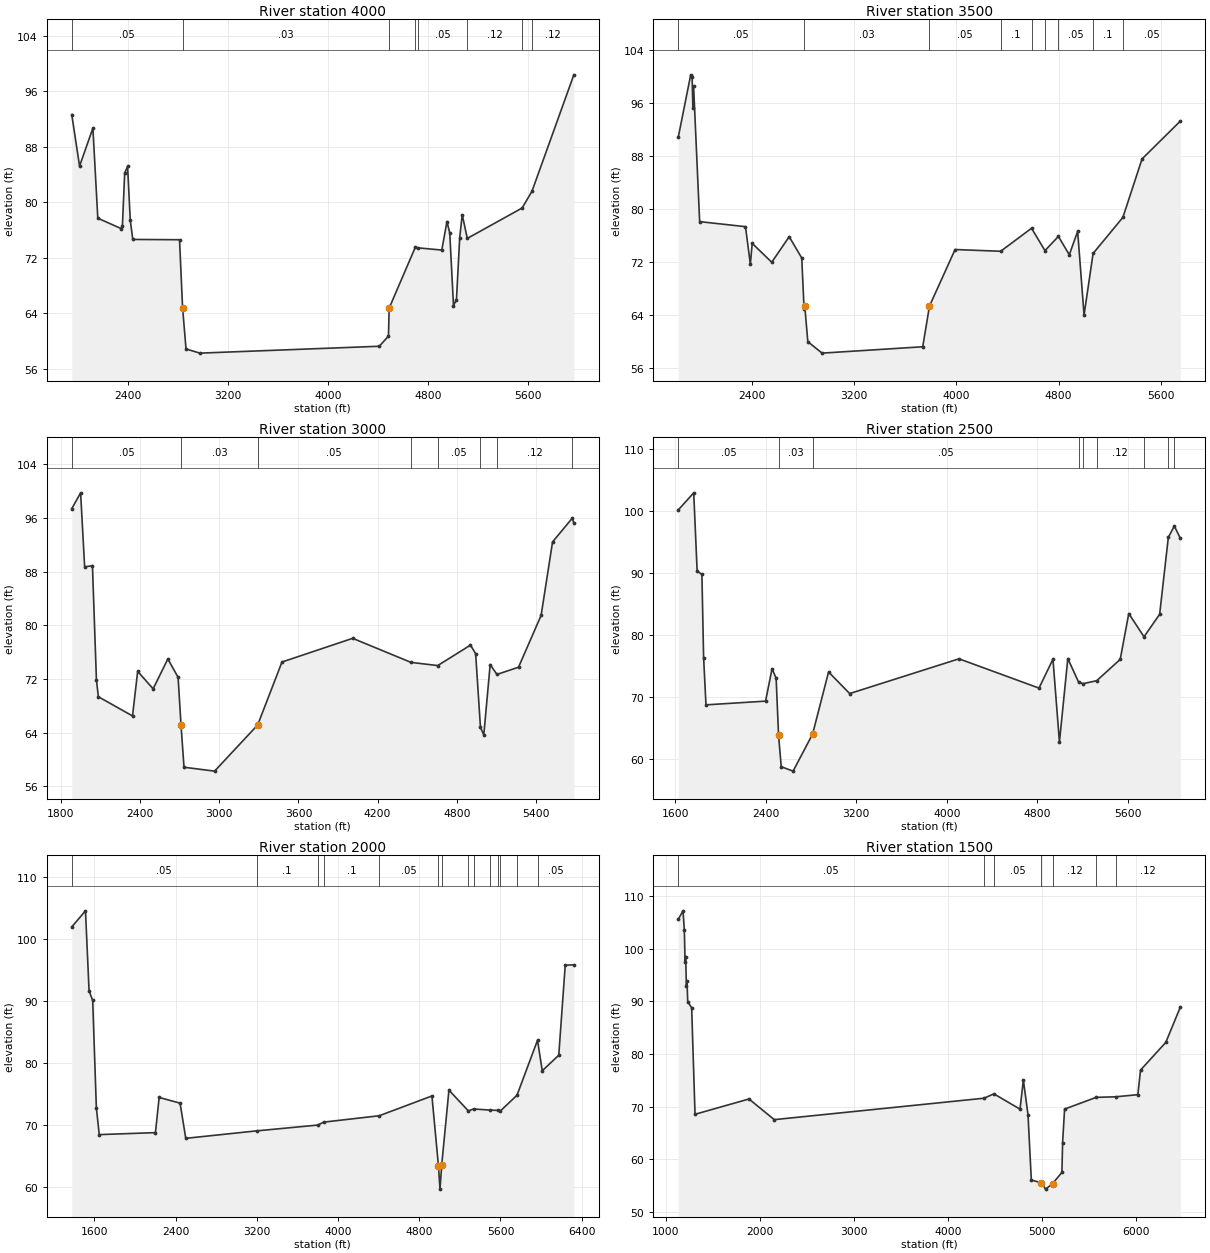
Type RM Length L Ch R = 1 ,4000    ,500,500,500
BEGIN DESCRIPTION:
Crystal Creek 007 8.0
END DESCRIPTION:
XS GIS Cut Line= 3
      3887467.85     10033161.09      3886645.02     10036096.86
      3886567.85     10037061.08
#Sta/Elev= 30
  1951.1   92.66  2013.4   85.24  2120.1    90.7  2159.4   77.73  2345.7   76.24
  2356.1    76.6  2374.4   84.24  2397.6   85.19  2418.9   77.45  2439.2   74.67
  2813.1   74.63  2837.4  64.863    2865   58.89    2976   58.29  4411.2   59.28
  4484.6   60.75  4489.8   64.76    4699   73.54  4719.2   73.46  4910.9   73.14
  4952.4   77.25  4974.7    75.6  5004.6   65.15  5028.2   65.97  5054.4   74.95
  5074.4   78.23  5115.1   74.82  5553.5    79.2  5632.3   81.61  5967.3   98.39
#Mann= 8 ,-1 , 0
  1951.1     .05       0  2837.4     .03       0  4489.8     .05       0
    4699      .1       0  4719.2     .05       0  5115.1     .12       0
  5553.5     .05       0  5632.3     .12       0
Bank Sta=2837.4,4489.8
XS Rating Curve= 0 ,0
Exp/Cntr=0.3,0.1

Type RM Length L Ch R = 1 ,3500    ,500,500,500
BEGIN DESCRIPTION:
Crystal Creek 007 7.0
END DESCRIPTION:
XS GIS Cut Line= 3
      3887417.86     10033161.05      3886179.39     10036088.02
      3886187.71     10036840.57
#Sta/Elev= 30
  1821.8   90.75  1919.5  100.18  1930.4   99.84  1936.6   95.13    1942   98.52
  1989.4   78.03  2348.2   77.27  2386.5   71.62    2401   74.75    2554    71.9
  2690.5   75.76  2788.9   72.54  2807.2   64.78  2812.6   65.25  2836.3   59.92
  2947.8   58.19    3736   59.15  3788.8   65.29  3989.2   73.82  4346.2   73.56
  4587.9   77.03    4693   73.66  4798.1    75.8  4883.5   73.03    4949   76.56
  4998.9   63.93  5069.8   73.23  5303.1   78.67  5453.1   87.49  5752.6    93.2
#Mann= 9 ,-1 , 0
  1821.8     .05       0  2807.2     .03       0  3788.8     .05       0
  4346.2      .1       0  4587.9     .05       0    4693      .1       0
  4798.1     .05       0  5069.8      .1       0  5303.1     .05       0
Bank Sta=2812.6,3788.8
XS Rating Curve= 0 ,0
Exp/Cntr=0.3,0.1

Type RM Length L Ch R = 1 ,3000    ,500,500,500
BEGIN DESCRIPTION:
Crystal Creek 007 6.0
END DESCRIPTION:
XS GIS Cut Line= 3
      3887117.85     10033311.08      3885717.15     10036096.86
      3885912.96     10036755.78
#Sta/Elev= 30
  1881.9   97.37    1949   99.73  1979.5   88.69  2038.6   88.89  2068.8   71.87
  2083.4   69.36  2342.3    66.5  2381.4   73.14  2498.6   70.54  2610.2   74.99
  2687.8   72.25  2710.2   65.08  2732.6   58.86  2964.4   58.28    3291   65.16
  3475.2   74.53    4011   78.06  4452.6   74.48  4655.5      74    4904   77.05
    4943   75.78  4979.7   64.79  5004.8   63.68  5053.2   74.15  5104.5   72.68
  5268.1   73.76  5439.3   81.47    5526   92.42  5675.5   95.95  5687.4   95.22
#Mann= 8 ,-1 , 0
  1881.9     .05       0  2710.2     .03       0    3291     .05       0
  4452.6      .1       0  4655.5     .05       0  4979.7      .1       0
  5104.5     .12       0  5675.5     .05       0
Bank Sta=2710.2,3291
XS Rating Curve= 0 ,0
Exp/Cntr=0.3,0.1

Type RM Length L Ch R = 1 ,2500    ,500,500,500
BEGIN DESCRIPTION:
Crystal Creek 007 5.0
END DESCRIPTION:
XS GIS Cut Line= 3
      3887117.84     10033261.08      3885258.47     10036076.63
      3885767.87      10037011.1
#Sta/Elev= 30
  1625.9  100.13  1762.8  102.89    1793   90.29  1835.1   89.74  1850.2   76.35
  1871.2   68.72    2398   69.32  2455.2   74.53  2491.3   73.02  2512.7   63.85
  2536.5   58.75  2641.3   58.04 2813.66  64.013  2954.9   74.02  3141.5   70.54
  4107.7   76.14  4815.1   71.42  4938.5   76.08  4995.7   62.73  5069.8   76.18
  5165.4   72.37  5205.5   72.14    5325   72.61  5533.1   76.05  5608.7   83.44
  5743.4   79.69  5881.5   83.31  5958.4   95.72  6011.4   97.53  6064.3   95.58
#Mann= 9 ,-1 , 0
  1625.9     .05       0  2512.7     .03       0 2813.66     .05       0
  5165.4     .12       0  5205.5      .1       0    5325     .12       0
  5743.4     .05       0  5958.4     .12       0  6011.4     .05       0
Bank Sta=2512.7,2813.66
XS Rating Curve= 0 ,0
Exp/Cntr=0.3,0.1

Type RM Length L Ch R = 1 ,2000    ,500,500,500
BEGIN DESCRIPTION:
Crystal Creek 007 4.0
END DESCRIPTION:
XS GIS Cut Line= 3
      3887067.86     10033261.06      3884784.83     10036073.46
      3885717.82     10037011.04
#Sta/Elev= 30
  1377.6   101.9  1512.7  104.49  1547.9   91.61  1583.7   90.04  1619.7   72.78
  1648.1   68.41  2201.9   68.73  2238.2    74.4  2444.4   73.48  2500.4   67.81
  3197.6   69.01  3802.1   69.95  3857.8   70.42  4405.8   71.45  4924.9   74.64
  4988.9   63.41  5004.3   59.62  5021.7   63.59  5092.4   75.58  5283.9   72.23
    5335   72.54  5493.3   72.37  5578.2   72.31    5597   72.19  5762.6   74.75
  5964.9   83.62  6011.6   78.71  6174.2   81.21  6237.9   95.72  6322.7   95.79
#Mann= 14 ,-1 , 0
  1377.6     .05       0  3197.6      .1       0  3802.1     .05       0
  3857.8      .1       0  4405.8     .05       0  4988.9     .03       0
  5021.7     .05       0  5283.9     .12       0    5335     .05       0
  5493.3      .1       0  5578.2     .12       0    5597      .1       0
  5762.6     .12       0  5964.9     .05       0
Bank Sta=4988.9,5021.7
XS Rating Curve= 0 ,0
Exp/Cntr=0.3,0.1

Type RM Length L Ch R = 1 ,1500    ,0,0,0
BEGIN DESCRIPTION:
Crystal Creek 007 3.0
END DESCRIPTION:
XS GIS Cut Line= 3
      3886944.67     10033305.88      3884333.13     10036156.86
       3885326.6     10037239.93
#Sta/Elev= 30
  1133.7  105.55  1184.5  107.17  1198.7  103.53  1206.1   97.38  1212.9   98.49
  1220.3   92.83  1227.1   93.81  1234.5   89.93  1276.4   88.76  1312.2   68.55
  1885.6   71.45  2154.5   67.53  4384.3    71.6  4488.4   72.43    4766   69.52
  4801.7   75.02  4851.1   68.46  4886.2   56.08  4992.3   55.53  5038.5   54.34
  5112.7   55.39  5211.4   57.52  5218.8   63.18  5239.7   69.53  5575.3   71.76
  5784.8   71.87  6018.5   72.27  6046.9   76.94  6315.7    82.2  6469.7   88.89
#Mann= 7 ,-1 , 0
  1133.7     .05       0  4384.3      .1       0  4488.4     .05       0
  4992.3     .03       0  5112.7     .12       0  5575.3      .1       0
  5784.8     .12       0
Bank Sta=4992.3,5112.7
XS Rating Curve= 0 ,0
Exp/Cntr=0.3,0.1