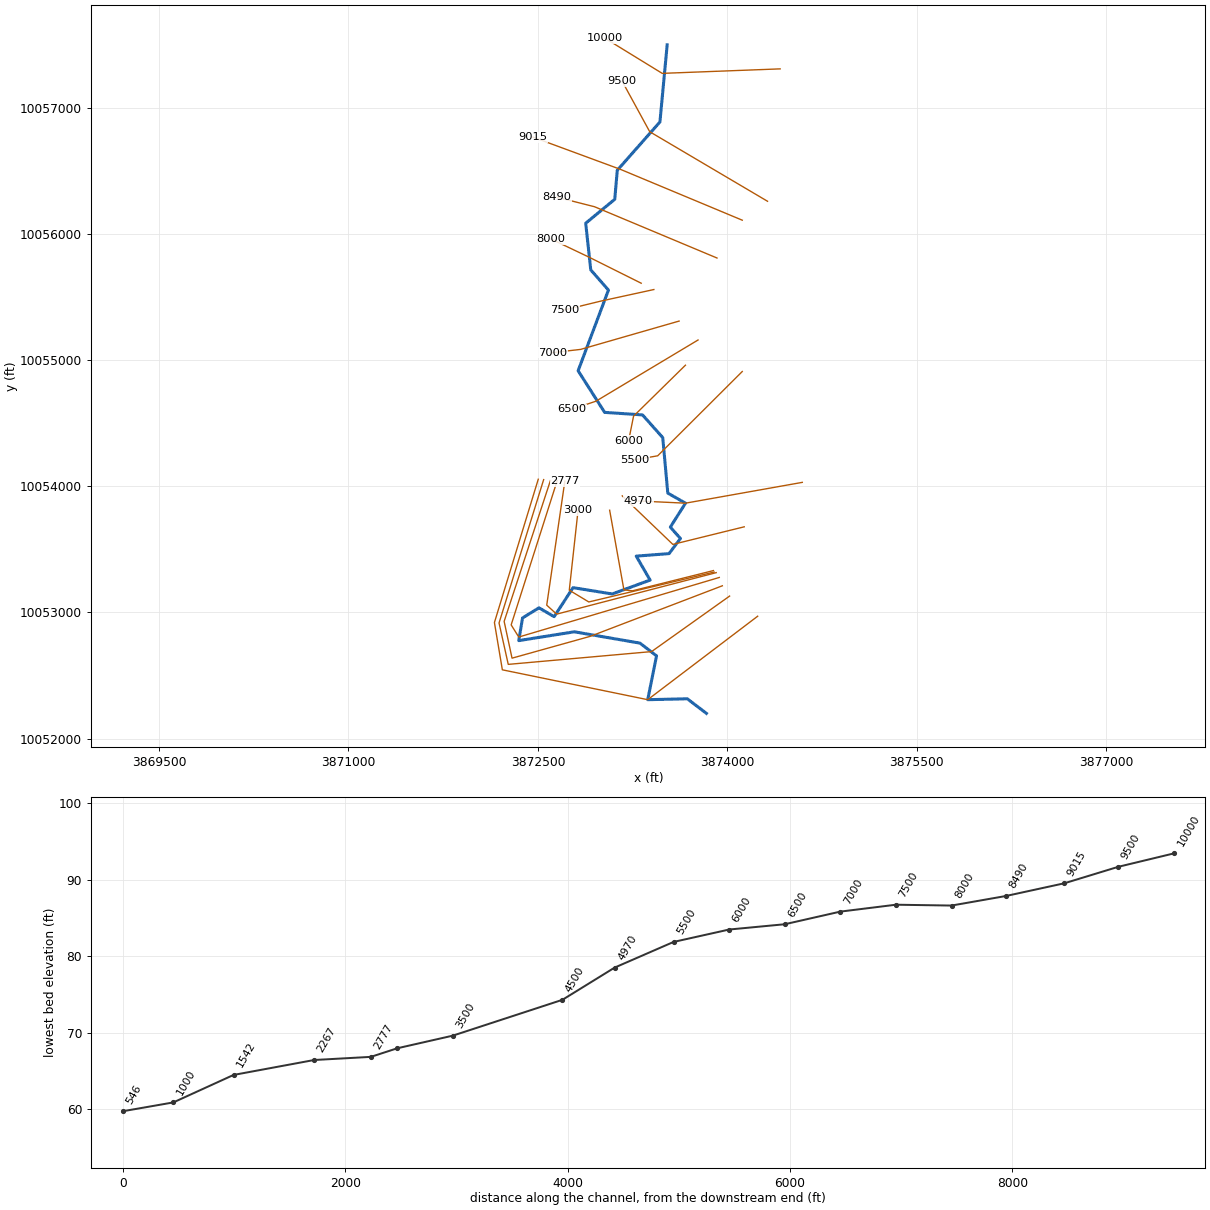
--- Crystal Creek 008.prj (project) ---

Proj Title=Crystal Creek 008 Base Level Engineering
Current Plan=p01
Default Exp/Contr=0.3,0.1
English Units
Geom File=g01
Flow File=f01
Flow File=f02
Plan File=p01
Y Axis Title=Elevation
X Axis Title(PF)=Main Channel Distance
X Axis Title(XS)=Station
BEGIN DESCRIPTION:
Crystal Creek 008
END DESCRIPTION:
DSS Export Rating Curves= 0
DSS Export Rating Curve Sorted= 0
DSS Export Volume Flow Curves= 0
DXF OffsetX= 0
DXF OffsetY= 0
DXF ScaleX= 1
DXF ScaleY= 10

--- Crystal Creek 008.p01 (plan) ---

Plan Title=Multiple Run
Short Identifier=Multiple
Geom File=g01
Flow File=f01
Subcritical Flow
K Sum by GR= 0
Std Step Tol= 0.01
Critical Tol= 0.01
Num of Std Step Trials= 20
Max Error Tol= 0.3
Flow Tol Ratio= 0.001
Split Flow NTrial= 30
Split Flow Tol= 0.02
Split Flow Ratio= 0.02
Log Output Level= 0
Friction Slope Method= 1
Unsteady Friction Slope Method= 2
Unsteady Bridges Friction Slope Method= 1
Parabolic Critical Depth
Global Vel Dist=  1 , 1 , 1
Global Log Level= 0
CheckData=True
Encroach Param= -1, 0, 0, 0
BEGIN DESCRIPTION:
Multiple Run
END DESCRIPTION:

--- Crystal Creek 008.f01 (steady flow) ---

Flow Title=Multiple
Program Version=4.10
Number of Profiles= 7
Profile Names=10-year,25-year,50-year,1pct_min,100-year,1pct_plu,500-year
River Rch & RM=Crystal Creek 00,Reach-1         ,10000
     565     736     969     419    1266    3823    2233
River Rch & RM=Crystal Creek 00,Reach-1         ,5500
     688     915    1221     536    1619    4889    2933
River Rch & RM=Crystal Creek 00,Reach-1         ,2777
    1074    1465    1987     885    2673    8072    4995
River Rch & RM=Crystal Creek 00,Reach-1         ,2267
    1074    1465    1987     885    2673    8072    4995
River Rch & RM=Crystal Creek 00,Reach-1         ,546
    1095    1494    2029     904    2730    8244    5108
Boundary for River Rch & Prof#=Crystal Creek 00,Reach-1         , 1
Up Type= 0
Dn Type= 3
Dn Slope=0.003
Boundary for River Rch & Prof#=Crystal Creek 00,Reach-1         , 2
Up Type= 0
Dn Type= 3
Dn Slope=0.003
Boundary for River Rch & Prof#=Crystal Creek 00,Reach-1         , 3
Up Type= 0
Dn Type= 3
Dn Slope=0.003
Boundary for River Rch & Prof#=Crystal Creek 00,Reach-1         , 4
Up Type= 0
Dn Type= 3
Dn Slope=0.003
Boundary for River Rch & Prof#=Crystal Creek 00,Reach-1         , 5
Up Type= 0
Dn Type= 3
Dn Slope=0.003
Boundary for River Rch & Prof#=Crystal Creek 00,Reach-1         , 6
Up Type= 0
Dn Type= 3
Dn Slope=0.003
Boundary for River Rch & Prof#=Crystal Creek 00,Reach-1         , 7
Up Type= 0
Dn Type= 3
Dn Slope=0.003
DSS Import GetInterval= 0
DSS Import GetPeak= 0
DSS Import FillOption= 0

--- Crystal Creek 008.f02 (steady flow) ---

Flow Title=Orig_BLE_Flow
Program Version=4.10
Number of Profiles= 7
Profile Names=10-year,25-year,50-year,1pct_min,100-year,1pct_plu,500-year
River Rch & RM=Crystal Creek 00,Reach-1         ,10000
     565     722     843     323     974    2941    1298
River Rch & RM=Crystal Creek 00,Reach-1         ,5500
     688     897    1062     412    1245    3759    1705
River Rch & RM=Crystal Creek 00,Reach-1         ,2777
    1074    1436    1728     681    2056    6208    2904
River Rch & RM=Crystal Creek 00,Reach-1         ,2267
    1074    1436    1728     681    2056    6208    2904
River Rch & RM=Crystal Creek 00,Reach-1         ,546
    1095    1465    1764     695    2100    6341    2970
Boundary for River Rch & Prof#=Crystal Creek 00,Reach-1         , 1
Up Type= 0
Dn Type= 3
Dn Slope=0.003
Boundary for River Rch & Prof#=Crystal Creek 00,Reach-1         , 2
Up Type= 0
Dn Type= 3
Dn Slope=0.003
Boundary for River Rch & Prof#=Crystal Creek 00,Reach-1         , 3
Up Type= 0
Dn Type= 3
Dn Slope=0.003
Boundary for River Rch & Prof#=Crystal Creek 00,Reach-1         , 4
Up Type= 0
Dn Type= 3
Dn Slope=0.003
Boundary for River Rch & Prof#=Crystal Creek 00,Reach-1         , 5
Up Type= 0
Dn Type= 3
Dn Slope=0.003
Boundary for River Rch & Prof#=Crystal Creek 00,Reach-1         , 6
Up Type= 0
Dn Type= 3
Dn Slope=0.003
Boundary for River Rch & Prof#=Crystal Creek 00,Reach-1         , 7
Up Type= 0
Dn Type= 3
Dn Slope=0.003
DSS Import GetInterval= 0
DSS Import GetPeak= 0
DSS Import FillOption= 0

--- Crystal Creek 008.g01 (geometry) ---

Geom Title=Existing Conditions
Program Version=4.10

River Reach=Crystal Creek 00,Reach-1
Reach XY= 30
      3873523.24     10057501.86      3873465.94     10056890.09
      3873128.24     10056506.86      3873108.24     10056276.86
      3872878.24     10056086.86      3872918.24     10055716.86
      3873058.24     10055556.86      3872818.24     10054916.86
      3873028.24     10054586.86      3873328.24     10054566.86
      3873488.24     10054386.86      3873528.24     10053946.86
      3873668.24     10053866.86      3873548.24     10053676.86
      3873628.24     10053586.86      3873538.24     10053466.86
      3873278.24     10053446.86      3873388.24     10053256.86
      3873088.24     10053146.86      3872778.24     10053196.86
      3872628.24     10052966.86      3872508.24     10053036.86
      3872378.24     10052956.86      3872348.24     10052776.86
      3872788.24     10052846.86      3873308.24     10052756.86
      3873439.09     10052655.75      3873369.26     10052308.41
      3873682.58     10052315.57      3873834.07     10052199.88

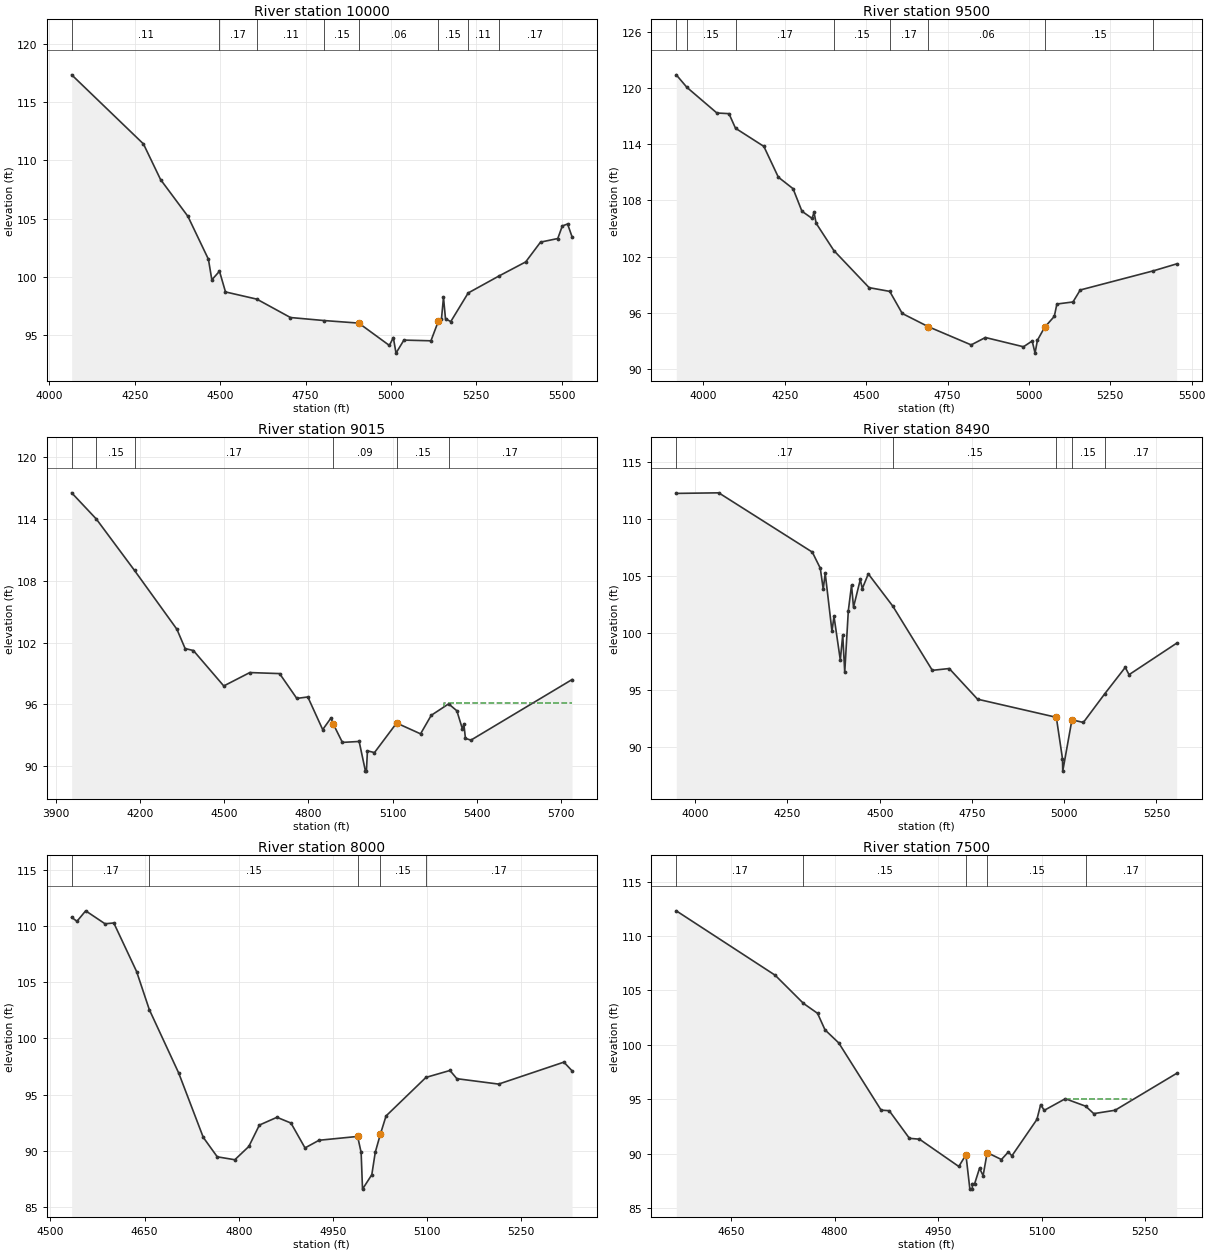
Type RM Length L Ch R = 1 ,10000   ,500,500,500
BEGIN DESCRIPTION:
Crystal Creek 008 19.0
END DESCRIPTION:
XS GIS Cut Line= 3
      3874417.84     10057311.07      3873483.92     10057275.42
      3873032.22     10057553.24
#Sta/Elev= 30
  4065.4  117.35  4275.5  111.41  4325.6  108.35  4405.6  105.19  4465.7   101.5
  4475.7   99.73  4498.1  100.47  4515.7   98.69  4607.5   98.07  4705.9   96.49
  4804.5   96.23    4906   96.01  4995.5   94.09  5007.1   94.77  5014.9   93.43
    5038   94.55  5117.2   94.49  5138.5   96.15    5148   96.37  5153.9   98.22
  5159.8   96.38  5175.2   96.14  5226.2    98.6  5315.1  100.04  5394.6  101.27
    5438  102.97  5488.5  103.28  5501.8  104.36  5517.2  104.53  5530.3  103.43
#Mann= 8 ,-1 , 0
  4065.4     .11       0  4498.1     .17       0  4607.5     .11       0
  4804.5     .15       0    4906     .06       0  5138.5     .15       0
  5226.2     .11       0  5315.1     .17       0
#XS Ineff= 2 , 0
       0                  5153.9       0   98.22
Permanent Ineff=
       F       F
Bank Sta=4906,5138.5
XS Rating Curve= 0 ,0
Exp/Cntr=0.3,0.1

Type RM Length L Ch R = 1 ,9500    ,485,485,485
BEGIN DESCRIPTION:
Crystal Creek 008 18.0
END DESCRIPTION:
XS GIS Cut Line= 3
      3874317.81      10056261.1      3873385.18     10056812.62
      3873167.84      10057211.1
#Sta/Elev= 30
  3916.5  121.43  3949.2  120.09  4041.3  117.35  4078.4  117.28  4098.5  115.72
  4185.6  113.78  4230.1  110.49  4275.3  109.26  4302.6  106.85  4333.9  106.08
  4339.7  106.74  4346.3  105.56  4400.6  102.65    4509   98.68  4572.4   98.28
  4610.8   95.92  4690.7   94.51  4822.6   92.56  4866.3   93.35  4983.3   92.36
  5010.1   92.98  5018.8   91.68  5026.2   93.06  5048.1   94.43    5078   95.61
    5086   96.93  5135.4   97.15  5157.7   98.43  5382.7  100.48  5453.9  101.22
#Mann= 8 ,-1 , 0
  3916.5     .17       0  3949.2     .15       0  4098.5     .17       0
  4400.6     .15       0  4572.4     .17       0  4690.7     .06       0
  5048.1     .15       0  5382.7     .11       0
#XS Ineff= 2 , 0
       0                    5086       0   96.93
Permanent Ineff=
       F       F
Bank Sta=4690.7,5048.1
XS Rating Curve= 0 ,0
Exp/Cntr=0.3,0.1

Type RM Length L Ch R = 1 ,9015    ,525,525,525
BEGIN DESCRIPTION:
Crystal Creek 008 17.0
END DESCRIPTION:
XS GIS Cut Line= 3
      3874117.87     10056111.06      3873154.89     10056513.52
      3872461.48     10056769.63
#Sta/Elev= 30
  3956.3  116.55  4044.3     114  4180.3  109.01  4331.3   103.3  4360.5  101.43
  4389.9  101.24  4498.2    97.8    4591    99.1  4697.1      99  4758.4   96.59
  4797.7   96.73  4850.7   93.56    4880   94.68  4888.4    94.1  4920.9   92.32
  4980.6   92.41    5003   89.53  5006.5   89.53  5010.1    91.5  5035.2   91.33
  5114.1    94.2  5199.4   93.15  5237.5   94.95  5299.5   96.06  5328.7   95.39
  5348.5   93.63  5353.8   94.09  5359.3   92.71  5378.9   92.54  5739.2   98.42
#Mann= 6 ,-1 , 0
  3956.3     .17       0  4044.3     .15       0  4180.3     .17       0
  4888.4     .09       0  5114.1     .15       0  5299.5     .17       0
#XS Ineff= 2 , 0
       0                  5284.7       0    96.1
Permanent Ineff=
       F       F
Bank Sta=4888.4,5114.1
XS Rating Curve= 0 ,0
Exp/Cntr=0.3,0.1

Type RM Length L Ch R = 1 ,8490    ,490,490,490
BEGIN DESCRIPTION:
Crystal Creek 008 16.0
END DESCRIPTION:
XS GIS Cut Line= 3
      3873917.82     10055811.08      3872948.24     10056217.71
      3872652.83      10056292.8
#Sta/Elev= 30
  3948.6  112.23  4063.7  112.28  4317.3  107.08  4338.9  105.67  4346.9  103.84
  4352.3  105.22  4370.6  100.15  4376.1  101.44  4393.2   97.62  4399.8   99.83
  4405.2   96.53  4414.9  101.93  4423.6  104.18    4429  102.25  4447.4  104.68
  4452.8  103.88  4469.1  105.17  4535.5  102.34  4642.6   96.71  4688.4   96.87
  4765.2   94.18  4978.7   92.59  4995.4   88.96  4996.1   87.87    5021   92.37
    5052   92.14  5110.1   94.66  5165.5   96.97  5175.8   96.33  5304.8   99.09
#Mann= 5 ,-1 , 0
  3948.6     .17       0  4535.5     .15       0  4978.7     .09       0
    5021     .15       0  5110.1     .17       0
Bank Sta=4978.7,5021
XS Rating Curve= 0 ,0
Exp/Cntr=0.3,0.1

Type RM Length L Ch R = 1 ,8000    ,500,500,500
BEGIN DESCRIPTION:
Crystal Creek 008 15.0
END DESCRIPTION:
XS GIS Cut Line= 3
      3873317.84     10055611.08      3872900.99     10055819.62
      3872602.27      10055962.2
#Sta/Elev= 30
  4533.9  110.76  4542.3  110.41  4556.2  111.34    4587  110.19    4601  110.26
  4637.3  105.95  4657.6  102.56  4704.4   96.93  4743.5   91.22  4765.8   89.49
  4793.8   89.23  4816.1   90.41  4832.9   92.31  4860.9      93  4883.2   92.49
  4905.6   90.28  4927.9   90.96  4989.4    91.3    4995   89.88  4997.2   86.62
    5012    87.9  5017.5   89.89  5025.6   91.49  5034.7   93.12  5098.396.54436
  5136.5   97.16  5147.5   96.43    5214   95.95    5318    97.9    5331   97.13
#Mann= 5 ,-1 , 0
  4533.9     .17       0  4657.6     .15       0  4989.4     .09       0
  5025.6     .15       0  5098.3     .17       0
Bank Sta=4989.4,5025.6
XS Rating Curve= 0 ,0
Exp/Cntr=0.3,0.1

Type RM Length L Ch R = 1 ,7500    ,500,500,500
BEGIN DESCRIPTION:
Crystal Creek 008 14.0
END DESCRIPTION:
XS GIS Cut Line= 3
      3873417.85     10055561.07      3872998.24     10055469.46
      3872711.15     10055399.46
#Sta/Elev= 30
  4570.5  112.31  4713.8  106.39  4754.8   103.8  4775.2  102.89    4786  101.37
  4805.9  100.17  4867.3   93.99    4879   93.94  4908.3    91.4  4922.9   91.32
  4979.9   88.81  4990.2   89.89  4995.9   86.73  4999.4   86.73  4999.6   87.23
  5002.8   87.23  5009.9   88.65  5015.1   87.97    5021   90.09  5041.6   89.45
  5051.6   90.14  5056.8   89.79    5093   93.13  5098.5    94.5  5103.6   93.97
  5134.2   95.04  5163.8   94.35  5175.4   93.67  5206.3   93.98  5295.5   97.37
#Mann= 5 ,-1 , 0
  4570.5     .17       0  4754.8     .15       0  4990.2     .06       0
    5021     .15       0  5163.8     .17       0
#XS Ineff= 2 ,-1
  5098.5  5134.2    94.5  5134.2  5228.7   95.04
Permanent Ineff=
       F       F
Bank Sta=4990.2,5021
XS Rating Curve= 0 ,0
Exp/Cntr=0.3,0.1

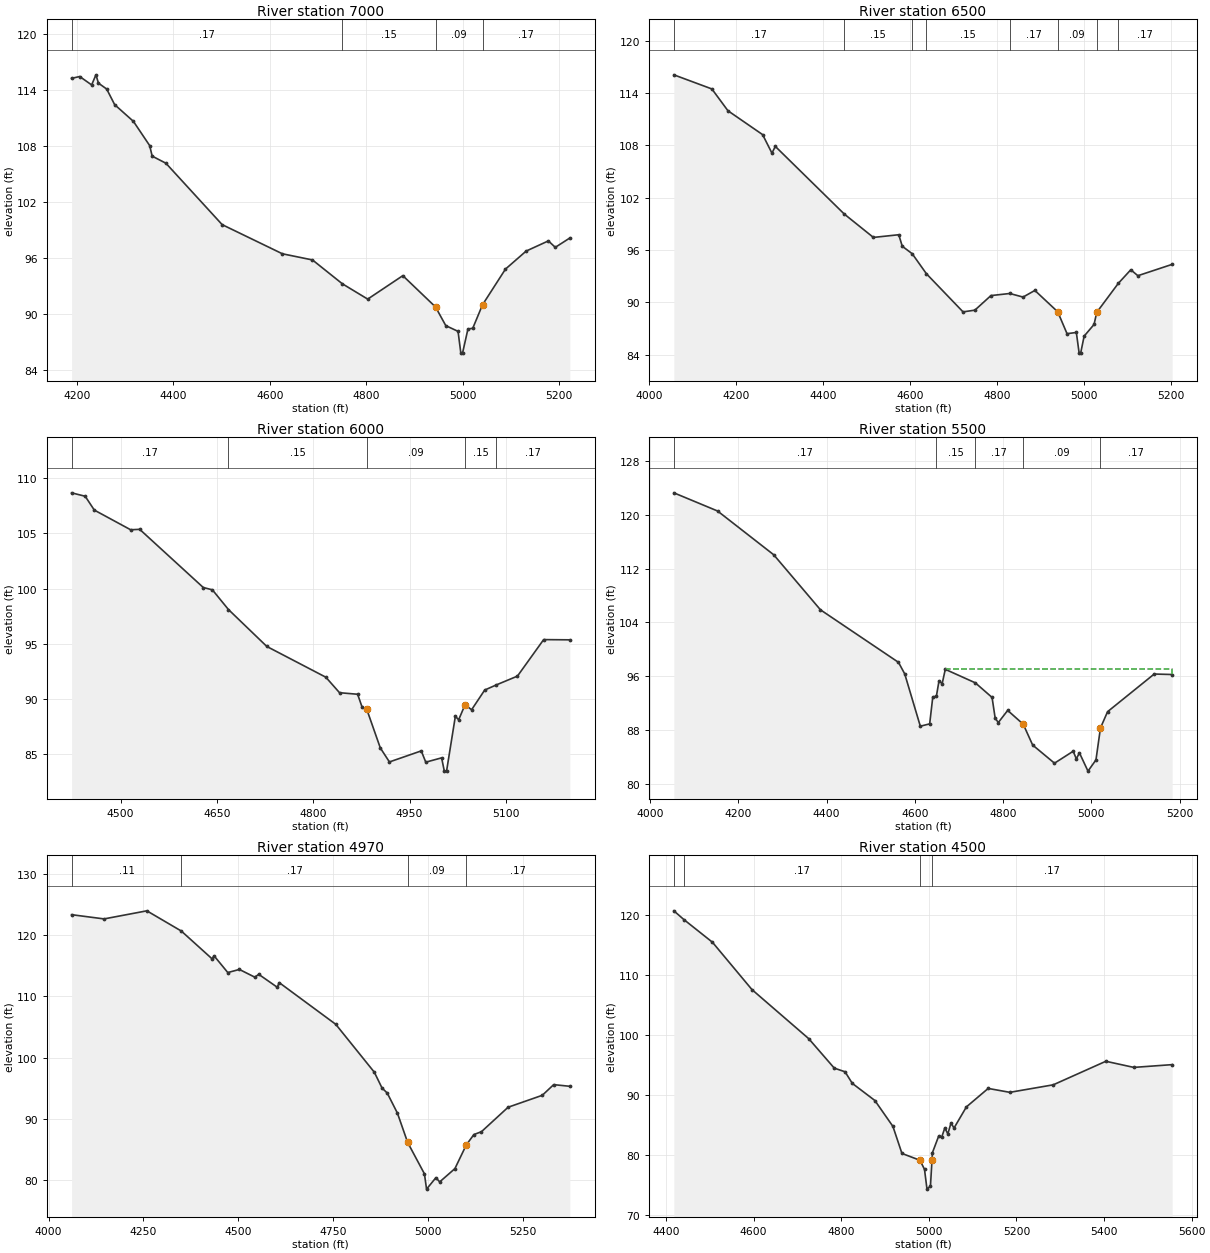
Type RM Length L Ch R = 1 ,7000    ,500,500,500
BEGIN DESCRIPTION:
Crystal Creek 008 13.0
END DESCRIPTION:
XS GIS Cut Line= 3
      3873617.82     10055311.06      3872838.24     10055086.44
      3872617.89     10055061.08
#Sta/Elev= 30
  4188.7  115.23  4205.5  115.43  4230.3  114.53  4239.2  115.61  4244.4  114.72
  4261.5  114.09    4278  112.42  4316.9  110.63  4350.6  108.04  4355.8  106.91
  4384.3  106.15  4500.9   99.58  4625.8   96.46  4688.2    95.8  4750.1   93.25
  4802.7   91.61  4875.5   94.12  4943.3   90.77  4964.6   88.77    4990   88.16
  4995.8   85.83  4999.3   85.83  5010.5   88.41  5020.5   88.49  5040.7      91
  5088.3   94.82  5131.2   96.75  5177.3   97.84  5191.6   97.15  5221.8   98.15
#Mann= 4 ,-1 , 0
  4188.7     .17       0  4750.1     .15       0  4943.3     .09       0
  5040.7     .17       0
#XS Ineff= 2 , 0
       0  4875.5   94.12               0
Permanent Ineff=
       F       F
Bank Sta=4943.3,5040.7
XS Rating Curve= 0 ,0
Exp/Cntr=0.3,0.1

Type RM Length L Ch R = 1 ,6500    ,500,500,500
BEGIN DESCRIPTION:
Crystal Creek 008 12.0
END DESCRIPTION:
XS GIS Cut Line= 3
      3873767.81     10055161.05      3872959.45     10054675.65
      3872767.84     10054611.07
#Sta/Elev= 30
  4057.1   116.1  4144.5  114.48  4181.4  111.98  4261.1  109.24  4282.5  107.12
  4290.3  107.89  4448.8  100.13  4515.7   97.45    4574   97.76    4582   96.44
  4604.9   95.58  4637.6   93.28  4721.7   88.91  4748.9   89.11  4785.8   90.78
    4829   91.02  4859.6   90.61  4886.8   91.37  4939.3   88.92  4960.7   86.41
  4982.1   86.55  4988.5   84.18    4992   84.18    5000   86.13  5022.8   87.47
    5029   88.86  5078.5   92.18  5107.2   93.74  5123.5   93.06  5202.2   94.36
#Mann= 8 ,-1 , 0
  4057.1     .17       0  4448.8     .15       0  4604.9     .17       0
  4637.6     .15       0    4829     .17       0  4939.3     .09       0
    5029     .15       0  5078.5     .17       0
#XS Ineff= 2 , 0
       0  4886.8   91.37               0
Permanent Ineff=
       F       F
Bank Sta=4939.3,5029
XS Rating Curve= 0 ,0
Exp/Cntr=0.3,0.1

Type RM Length L Ch R = 1 ,6000    ,500,500,500
BEGIN DESCRIPTION:
Crystal Creek 008 11.0
END DESCRIPTION:
XS GIS Cut Line= 3
      3873667.87     10054961.09      3873257.11     10054556.86
      3873217.85     10054361.06
#Sta/Elev= 30
  4423.7  108.65  4444.9  108.34  4459.1  107.09  4515.7  105.31  4529.8  105.35
  4628.8  100.09    4643   99.88    4668    98.1  4727.8   94.76  4819.7   91.98
    4841   90.58  4869.2   90.44  4876.3   89.25  4883.4   89.08  4904.5   85.59
  4918.7   84.32  4968.3   85.32  4975.3    84.3    5000   84.69  5004.2   83.49
  5007.7   83.49  5021.4   88.45  5026.5   88.13  5036.5   89.49  5046.7   89.04
  5067.1   90.82  5085.4   91.29  5118.1   92.08  5158.9   95.38  5199.7   95.36
#Mann= 5 ,-1 , 0
  4423.7     .17       0    4668     .15       0  4883.4     .09       0
  5036.5     .15       0  5085.4     .17       0
Bank Sta=4883.4,5036.5
XS Rating Curve= 0 ,0
Exp/Cntr=0.3,0.1

Type RM Length L Ch R = 1 ,5500    ,530,530,530
BEGIN DESCRIPTION:
Crystal Creek 008 10.0
END DESCRIPTION:
XS GIS Cut Line= 3
      3874117.84     10054911.06      3873448.24     10054242.54
      3873267.86     10054211.07
#Sta/Elev= 30
  4053.8  123.26  4152.8  120.56  4280.1  114.05  4386.1  105.86  4562.9   98.05
    4577   96.34  4612.4   88.55  4633.6    88.9  4640.7   92.92  4648.7   92.97
  4654.8   95.31  4661.9   94.88    4669   97.01  4737.1      95    4775   92.83
  4782.1   89.73  4789.2    89.1  4810.4    90.9  4845.7   88.84    4867   85.75
  4916.5   83.05  4958.9   84.83    4966   83.69    4973   84.59  4992.4   81.87
  5010.5   83.54  5020.7   88.29  5036.8   90.71  5142.5   96.31  5183.1   96.24
#Mann= 5 ,-1 , 0
  4053.8     .17       0  4648.7     .15       0  4737.1     .17       0
  4845.7     .09       0  5020.7     .17       0
#XS Ineff= 2 ,-1
    4669  4562.9   97.01  4810.4    4669    90.9
Permanent Ineff=
       F       F
Bank Sta=4845.7,5020.7
XS Rating Curve= 0 ,0
Exp/Cntr=0.3,0.1

Type RM Length L Ch R = 1 ,4970    ,470,470,470
BEGIN DESCRIPTION:
Crystal Creek 008 9.0
END DESCRIPTION:
XS GIS Cut Line= 3
      3874593.04     10054031.84      3873668.24     10053866.86
      3873295.34     10053884.26
#Sta/Elev= 30
  4060.6  123.33  4146.2  122.64  4258.9  123.96  4349.7  120.66  4430.8  116.12
  4435.9  116.62  4472.2  113.88  4502.7  114.39  4543.3  113.13  4553.7  113.59
  4602.5  111.48  4607.6  112.24  4756.6  105.43  4858.2   97.61  4878.5   95.03
  4892.2   94.21  4919.1   90.92    4946   86.14  4990.2   81.02  4995.8   78.52
  5020.4   80.39  5030.4    79.7  5070.5   81.87  5100.5   85.74  5120.5   87.43
  5140.5    87.9  5210.6   91.89  5300.7   93.84  5330.7   95.58  5373.3   95.31
#Mann= 4 ,-1 , 0
  4060.6     .11       0  4349.7     .17       0    4946     .09       0
  5100.5     .17       0
Bank Sta=4946,5100.5
XS Rating Curve= 0 ,0
Exp/Cntr=0.3,0.1

Type RM Length L Ch R = 1 ,4500    ,986,986,986
BEGIN DESCRIPTION:
Crystal Creek 008 8.0
END DESCRIPTION:
XS GIS Cut Line= 3
      3874133.38      10053679.4      3873568.24     10053539.94
      3873167.66     10053924.66
#Sta/Elev= 30
  4417.9  120.63  4440.7  119.18    4506   115.4  4596.2  107.52  4725.7   99.36
  4784.1   94.45  4808.7   93.84  4825.3   91.91  4876.8   89.06    4918   84.75
  4938.6   80.25  4979.8   79.11  4990.1    77.6  4995.8   74.31  5003.7   74.81
 5007.2679.21596  5008.2   80.38  5022.3    83.1  5029.2   82.93  5036.5   84.49
  5043.4    83.5  5050.6   85.31  5057.5   84.48  5085.8      88  5135.5   91.07
  5184.9   90.42    5284   91.67  5404.1   95.59  5467.9   94.57  5555.4   95.03
#Mann= 4 ,-1 , 0
  4417.9     .11       0  4440.7     .17       0  4979.8     .09       0
 5007.26     .17       0
#XS Ineff= 2 , 0
       0                  5036.5       0   84.49
Permanent Ineff=
       F       F
Bank Sta=4979.8,5007.26
XS Rating Curve= 0 ,0
Exp/Cntr=0.3,0.1

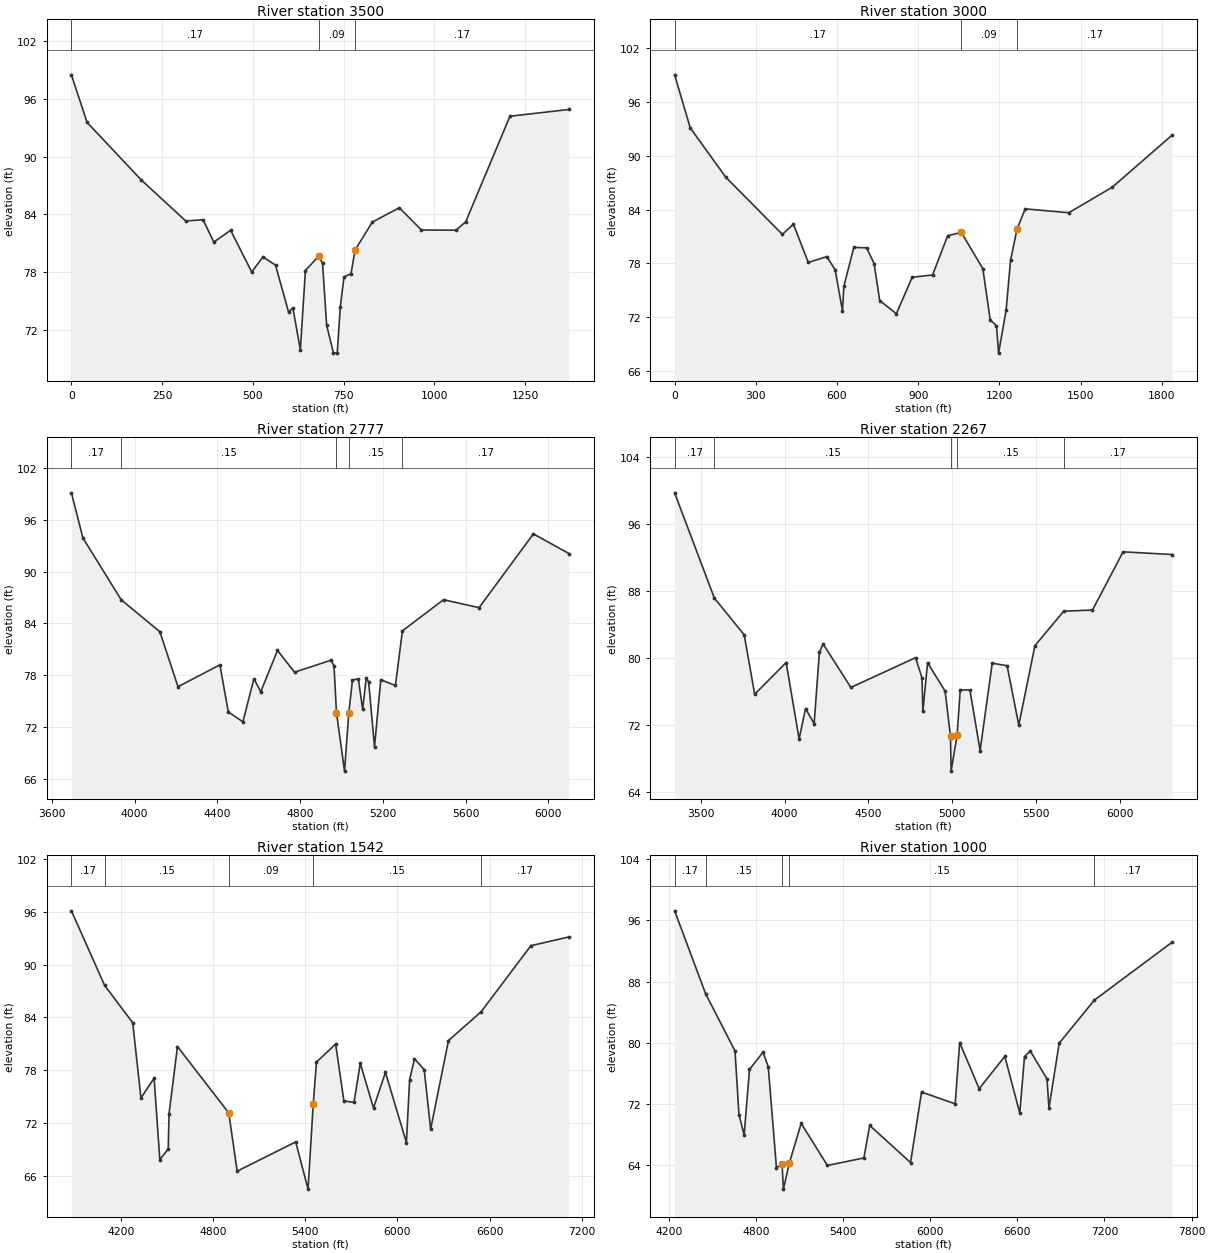
Type RM Length L Ch R = 1 ,3500    ,500,500,500
XS GIS Cut Line= 4
      3873889.52     10053332.37      3873248.07     10053171.67
      3873180.84     10053179.47      3873067.85     10053811.07
#Sta/Elev= 30
       0   98.47      43   93.55   191.5   87.61   315.1   83.32   362.5   83.46
   392.3   81.14   438.6   82.36   496.6   78.04   527.5    79.6   562.2   78.75
   598.3   73.87     610   74.32   630.6   69.99   644.6   78.19   681.6   79.71
   691.7   78.94   703.1   72.51   721.9   69.63   732.3   69.67   740.7   74.44
   750.9   77.52   770.2   77.87   781.4   80.32   829.1   83.22   903.3   84.69
   964.2   82.39  1059.5   82.37  1086.1   83.24    1208   94.18  1370.6   94.88
#Mann= 3 , 0 , 0
       0     .17       0   681.6     .09       0   781.4     .17       0
Bank Sta=681.6,781.4
XS Rating Curve= 0 ,0
Exp/Cntr=0.3,0.1

Type RM Length L Ch R = 1 ,3000    ,237,237,237
XS GIS Cut Line= 4
      3873894.91     10053320.52      3872902.66     10053083.41
      3872748.24     10053176.86      3872817.85     10053811.07
#Sta/Elev= 30
       0   99.04    57.9   93.11   189.2   87.61     398   81.24   439.1   82.36
     494    78.1   562.5   78.75   593.3   77.27   620.3    72.7   625.4   75.44
   662.3   79.78   709.6   79.73   737.2   77.97   757.8   73.85   819.5   72.38
   877.9   76.45   953.2    76.7  1009.2   81.09  1059.5   81.45    1139   77.41
  1166.2   71.69  1189.4   71.04  1197.2   67.98    1225   72.78  1241.6   78.37
  1265.3   81.82  1295.5   84.08  1456.4   83.65  1617.4    86.5  1838.7   92.32
#Mann= 3 , 0 , 0
       0     .17       0  1059.5     .09       0  1265.3     .17       0
Bank Sta=1059.5,1265.3
XS Rating Curve= 0 ,0
Exp/Cntr=0.3,0.1

Type RM Length L Ch R = 1 ,2777    ,510,510,510
BEGIN DESCRIPTION:
Crystal Creek 008 5.0
END DESCRIPTION:
XS GIS Cut Line= 4
      3873911.48     10053315.92      3872648.24     10052986.86
      3872569.68     10053058.05      3872713.09     10054041.23
#Sta/Elev= 30
  3694.6   99.12    3750    93.9  3935.2   86.72    4122   83.02  4209.8   76.65
  4412.3   79.18  4452.8   73.73  4523.5   72.57  4576.7   77.58  4609.7   76.06
  4690.7   80.85  4773.1   78.33  4948.7   79.71  4963.8   79.07 4975.76 73.6554
  5014.7   66.86  5035.373.60796  5053.1   77.43  5081.5   77.55  5102.4   74.01
  5119.2   77.61  5131.2   77.22  5159.6   69.68  5189.9   77.45  5260.7   76.79
  5294.5   83.12  5493.1   86.73  5664.9   85.81  5927.6   94.36  6099.6   92.08
#Mann= 5 ,-1 , 0
  3694.6     .17       0  3935.2     .15       0 4975.76     .09       0
  5035.3     .15       0  5294.5     .17       0
Bank Sta=4975.76,5035.3
XS Rating Curve= 0 ,0
Exp/Cntr=0.3,0.1

Type RM Length L Ch R = 1 ,2267    ,725,725,725
BEGIN DESCRIPTION:
Crystal Creek 008 4.0
END DESCRIPTION:
XS GIS Cut Line= 4
      3873935.83     10053277.73      3872348.24     10052805.28
        3872288.     10052901.64      3872652.13     10054044.29
#Sta/Elev= 30
  3343.6   99.74  3580.7   87.15  3758.8   82.76  3821.4   75.65  4009.2   79.44
  4086.6    70.3    4125   73.94  4176.2   72.12  4207.5   80.65  4229.7   81.67
  4395.3   76.46  4781.3   80.02  4819.9    77.6  4825.1    73.6  4853.1   79.41
  4957.8   76.02    4990   70.61  4993.6   66.45 5029.5270.75797    5048   76.15
  5105.8   76.17  5166.6   68.91    5239   79.36  5327.7   79.06  5397.4   71.97
    5494   81.47  5665.7   85.58  5837.2   85.72  6019.9   92.68  6312.9   92.36
#Mann= 5 ,-1 , 0
  3343.6     .17       0  3580.7     .15       0    4990     .09       0
 5029.52     .15       0  5665.7     .17       0
Bank Sta=4990,5029.52
XS Rating Curve= 0 ,0
Exp/Cntr=0.3,0.1

Type RM Length L Ch R = 1 ,1542    ,542,542,542
BEGIN DESCRIPTION:
Crystal Creek 008 3.0
END DESCRIPTION:
XS GIS Cut Line= 5
      3873960.13     10053211.76      3872914.23     10052810.87
      3872294.95     10052637.75      3872232.45     10052929.41
      3872598.77     10054045.95
#Sta/Elev= 30
  3879.9    96.1  4095.7   87.64  4278.6   83.39  4332.1   74.85  4417.8    77.1
  4454.9   67.85  4509.7   69.06    4515   73.08  4569.7   80.69  4903.4   73.15
  4958.1   66.54  5338.9   69.86    5419    64.5  5453.1   74.22  5473.9   78.92
  5598.5   80.98  5652.3   74.51    5718   74.35  5758.9   78.78  5844.9   73.71
  5922.6   77.76  6058.8   69.79  6079.9   76.92  6111.4   79.29  6174.6   78.08
  6216.7   71.32  6332.6   81.37  6544.6   84.63  6868.4   92.14  7116.4   93.14
#Mann= 5 ,-1 , 0
  3879.9     .17       0  4095.7     .15       0  4903.4     .09       0
  5453.1     .15       0  6544.6     .17       0
Bank Sta=4903.4,5453.1
XS Rating Curve= 0 ,0
Exp/Cntr=0.3,0.1

Type RM Length L Ch R = 1 ,1000    ,454,454,454
BEGIN DESCRIPTION:
Crystal Creek 008 2.0
END DESCRIPTION:
XS GIS Cut Line= 5
      3874017.59     10053130.14       3873399.6     10052689.83
        3872265.     10052588.49      3872192.08     10052916.61
      3872545.38     10054053.75
#Sta/Elev= 30
  4241.2   97.23  4454.8    86.4    4657   78.94    4684   70.63  4719.7   67.97
  4756.6   76.53    4850   78.79  4885.7   76.88  4942.2   63.68  4980.764.21459
    4990   60.91 5030.0364.26411  5112.2   69.49  5292.9      64  5543.9   64.98
  5584.1   69.22  5865.2   64.38    5941   73.58  6172.5   72.04  6203.2   80.03
  6337.5   74.02  6514.1   78.23    6617   70.83  6649.5   78.21  6689.3   78.94
  6804.5   75.29  6817.6   71.47  6888.3   79.96    7130   85.57    7666   93.14
#Mann= 5 ,-1 , 0
  4241.2     .17       0  4454.8     .15       0  4980.7     .09       0
 5030.03     .15       0    7130     .17       0
Bank Sta=4980.7,5030.03
XS Rating Curve= 0 ,0
Exp/Cntr=0.3,0.1

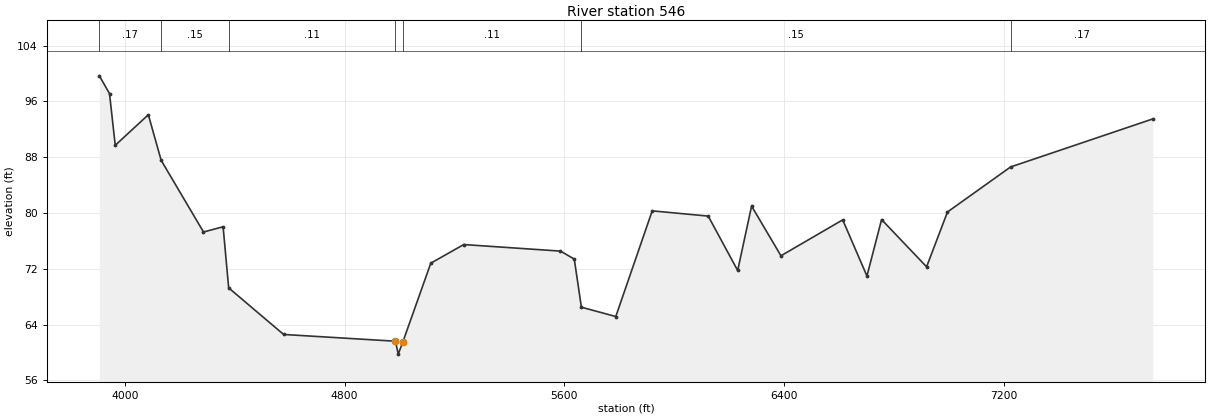
Type RM Length L Ch R = 1 ,546     ,0,0,0
BEGIN DESCRIPTION:
Crystal Creek 008 1.0
END DESCRIPTION:
XS GIS Cut Line= 5
      3874239.84     10052970.44      3873369.26     10052308.41
      3872218.31     10052545.31      3872155.51     10052920.41
      3872502.63     10054056.78
#Sta/Elev= 30
  3906.3   99.66  3943.4   97.11  3964.2    89.7  4084.8   94.08  4131.5   87.55
  4285.7   77.27  4357.2   78.02  4377.4   69.26  4577.6   62.58  4985.1   61.61
  4995.1   59.76  5011.6   61.47  5113.7    72.8  5233.8   75.47  5586.1   74.53
  5636.4   73.39  5662.3   66.49  5787.6   65.15  5920.3    80.3  6124.3   79.55
  6231.6   71.75  6282.3   80.98  6389.3   73.86  6614.2   79.01  6702.5   70.96
  6755.8   79.05  6919.8   72.28  6995.9   80.14  7225.6   86.59  7743.6   93.48
#Mann= 7 ,-1 , 0
  3906.3     .17       0  4131.5     .15       0  4377.4     .11       0
  4985.1     .09       0  5011.6     .11       0  5662.3     .15       0
  7225.6     .17       0
Bank Sta=4985.1,5011.6
XS Rating Curve= 0 ,0
Exp/Cntr=0.3,0.1

Chan Stop Cuts=-1
Use User Specified Reach Order=0
Composite Channel Slope=5

--- Crystal Creek 008.g10 (geometry) ---

Geom Title=Existing Conditions
Program Version=4.10

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
River Reach=Crystal Creek 00,Reach-1

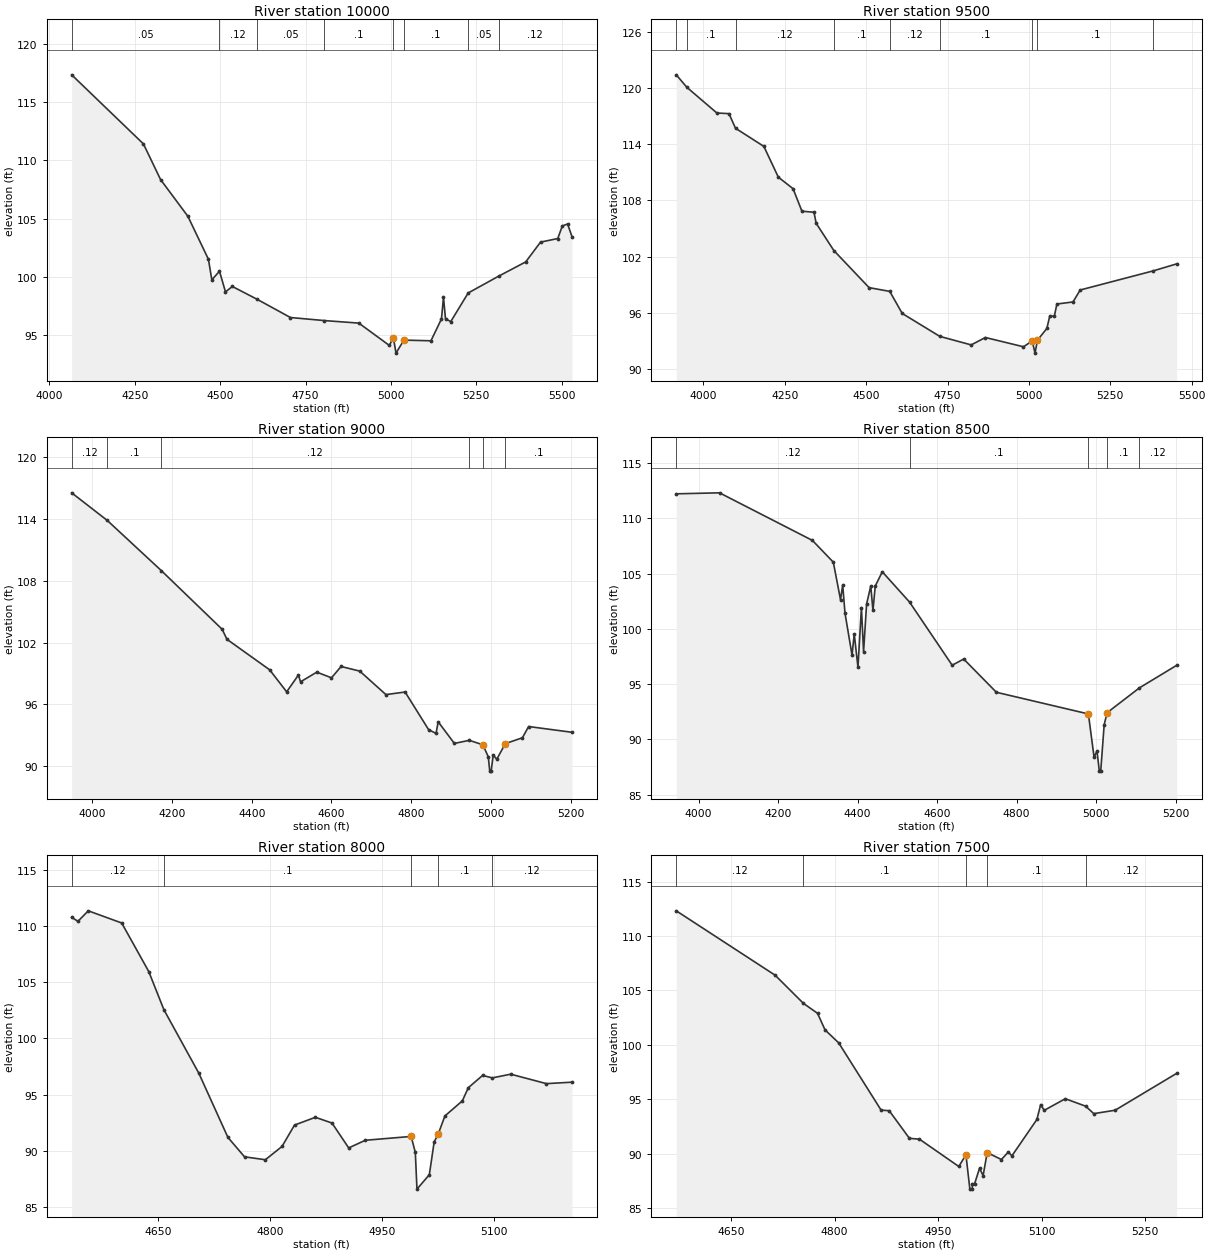
Type RM Length L Ch R = 1 ,10000   ,500,500,500
BEGIN DESCRIPTION:
Crystal Creek 008 19.0
END DESCRIPTION:
XS GIS Cut Line= 3
      3874417.84     10057311.07      3873483.92     10057275.42
      3873032.22     10057553.24
#Sta/Elev= 30
  4065.4  117.35  4275.5  111.41  4325.6  108.35  4405.6  105.19  4465.7   101.5
  4475.7   99.73  4498.1  100.47  4515.7   98.69  4535.7   99.16  4607.5   98.07
  4705.9   96.49  4804.5   96.23    4906   96.01  4995.5   94.09  5007.1   94.77
  5014.9   93.43    5038   94.55  5117.2   94.49    5148   96.37  5153.9   98.22
  5159.8   96.38  5175.2   96.14  5226.2    98.6  5315.1  100.04  5394.6  101.27
    5438  102.97  5488.5  103.28  5501.8  104.36  5517.2  104.53  5530.3  103.43
#Mann= 8 ,-1 , 0
  4065.4     .05       0  4498.1     .12       0  4607.5     .05       0
  4804.5      .1       0  5007.1     .03       0    5038      .1       0
  5226.2     .05       0  5315.1     .12       0
Bank Sta=5007.1,5038
XS Rating Curve= 0 ,0
Exp/Cntr=0.3,0.1

Type RM Length L Ch R = 1 ,9500    ,500,500,500
BEGIN DESCRIPTION:
Crystal Creek 008 18.0
END DESCRIPTION:
XS GIS Cut Line= 3
      3874317.81      10056261.1      3873385.18     10056812.62
      3873167.84      10057211.1
#Sta/Elev= 30
  3916.5  121.43  3949.2  120.09  4041.3  117.35  4078.4  117.28  4098.5  115.72
  4185.6  113.78  4230.1  110.49  4275.3  109.26  4302.6  106.85  4339.7  106.74
  4346.3  105.56  4400.6  102.65    4509   98.68  4572.4   98.28  4610.8   95.92
  4726.2   93.47  4822.6   92.56  4866.3   93.35  4983.3   92.36  5010.1   92.98
  5018.8   91.68  5026.2   93.06  5055.2   94.32  5064.2   95.67    5078   95.61
    5086   96.93  5135.4   97.15  5157.7   98.43  5382.7  100.48  5453.9  101.22
#Mann= 9 ,-1 , 0
  3916.5     .12       0  3949.2      .1       0  4098.5     .12       0
  4400.6      .1       0  4572.4     .12       0  4726.2      .1       0
  5010.1     .03       0  5026.2      .1       0  5382.7     .05       0
Bank Sta=5010.1,5026.2
XS Rating Curve= 0 ,0
Exp/Cntr=0.3,0.1

Type RM Length L Ch R = 1 ,9000    ,500,500,500
BEGIN DESCRIPTION:
Crystal Creek 008 17.0
END DESCRIPTION:
XS GIS Cut Line= 3
      3874117.83     10056111.08      3873143.01     10056506.86
      3872967.87     10056611.06
#Sta/Elev= 30
  3947.9  116.55  4037.2  113.87  4173.1  108.99  4325.6   103.3  4337.6  102.33
  4444.7   99.37  4487.5   97.23    4517   98.86  4522.3    98.2  4563.1   99.14
    4600   98.59  4624.1   99.69    4671   99.24  4736.6   96.96  4784.8   97.21
  4843.7   93.56  4862.4   93.19  4867.8   94.32  4908.4   92.22  4945.9   92.52
  4979.9  92.089  4993.6   90.92  4997.2   89.53  5000.7   89.53    5006   91.08
  5014.9   90.69  5036.3    92.2  5079.2   92.77  5094.8   93.86  5203.8    93.3
#Mann= 6 ,-1 , 0
  3947.9     .12       0  4037.2      .1       0  4173.1     .12       0
  4945.9      .1       0  4979.9     .03       0  5036.3      .1       0
Bank Sta=4979.9,5036.3
XS Rating Curve= 0 ,0
Exp/Cntr=0.3,0.1

Type RM Length L Ch R = 1 ,8500    ,500,500,500
BEGIN DESCRIPTION:
Crystal Creek 008 16.0
END DESCRIPTION:
XS GIS Cut Line= 3
      3873917.87     10055811.06      3872947.49     10056227.61
      3872752.81     10056284.42
#Sta/Elev= 30
    3944  112.23  4052.8  112.32  4286.5  108.01  4339.1  106.04  4357.2  102.64
  4362.7  103.98  4368.4  101.44  4386.2   97.62  4391.7   99.54  4401.1   96.53
  4409.8  101.93  4415.2   97.93  4422.8  102.25  4433.3  103.88  4438.8  101.67
  4444.6  103.88  4462.3  105.17  4530.8  102.43  4638.1   96.71  4667.1   97.27
  4749.3   94.26  4980.8  92.297  4995.1   88.37  5002.4   88.95  5008.3   87.12
  5011.8   87.12  5020.5   91.33  5027.9   92.41  5109.2   94.66  5202.8    96.7
#Mann= 5 ,-1 , 0
    3944     .12       0  4530.8      .1       0  4980.8     .07       0
  5027.9      .1       0  5109.2     .12       0
Bank Sta=4980.8,5027.9
XS Rating Curve= 0 ,0
Exp/Cntr=0.3,0.1

Type RM Length L Ch R = 1 ,8000    ,500,500,500
BEGIN DESCRIPTION:
Crystal Creek 008 15.0
END DESCRIPTION:
XS GIS Cut Line= 3
      3873317.84     10055611.08      3872900.99     10055819.62
      3872705.02     10055880.79
#Sta/Elev= 30
  4533.9  110.76  4542.3  110.41  4556.2  111.34    4601  110.26  4637.3  105.95
  4657.6  102.56  4704.4   96.93  4743.5   91.22  4765.8   89.49  4793.8   89.23
  4816.1   90.41  4832.9   92.31  4860.9      93  4883.2   92.49  4905.6   90.28
  4927.9   90.96  4989.4    91.3    4995   89.88  4997.2   86.62  5013.8    87.9
  5020.3   90.82  5025.6   91.49  5034.7   93.12  5058.1   94.46  5066.1   95.63
  5085.3   96.72  5098.3    96.5    5123   96.83  5170.9   95.99  5205.3   96.12
#Mann= 5 ,-1 , 0
  4533.9     .12       0  4657.6      .1       0  4989.4     .07       0
  5025.6      .1       0  5098.3     .12       0
Bank Sta=4989.4,5025.6
XS Rating Curve= 0 ,0
Exp/Cntr=0.3,0.1

Type RM Length L Ch R = 1 ,7500    ,500,500,500
BEGIN DESCRIPTION:
Crystal Creek 008 14.0
END DESCRIPTION:
XS GIS Cut Line= 3
      3873417.85     10055561.07      3872998.24     10055469.46
      3872711.15     10055399.46
#Sta/Elev= 30
  4570.5  112.31  4713.8  106.39  4754.8   103.8  4775.2  102.89    4786  101.37
  4805.9  100.17  4867.3   93.99    4879   93.94  4908.3    91.4  4922.9   91.32
  4979.9   88.81  4990.2   89.89  4995.9   86.73  4999.4   86.73  4999.6   87.23
  5002.8   87.23  5009.9   88.65  5015.1   87.97    5021   90.09  5041.6   89.45
  5051.6   90.14  5056.8   89.79    5093   93.13  5098.5    94.5  5103.6   93.97
  5134.2   95.04  5163.8   94.35  5175.4   93.67  5206.3   93.98  5295.5   97.37
#Mann= 5 ,-1 , 0
  4570.5     .12       0  4754.8      .1       0  4990.2     .03       0
    5021      .1       0  5163.8     .12       0
Bank Sta=4990.2,5021
XS Rating Curve= 0 ,0
Exp/Cntr=0.3,0.1