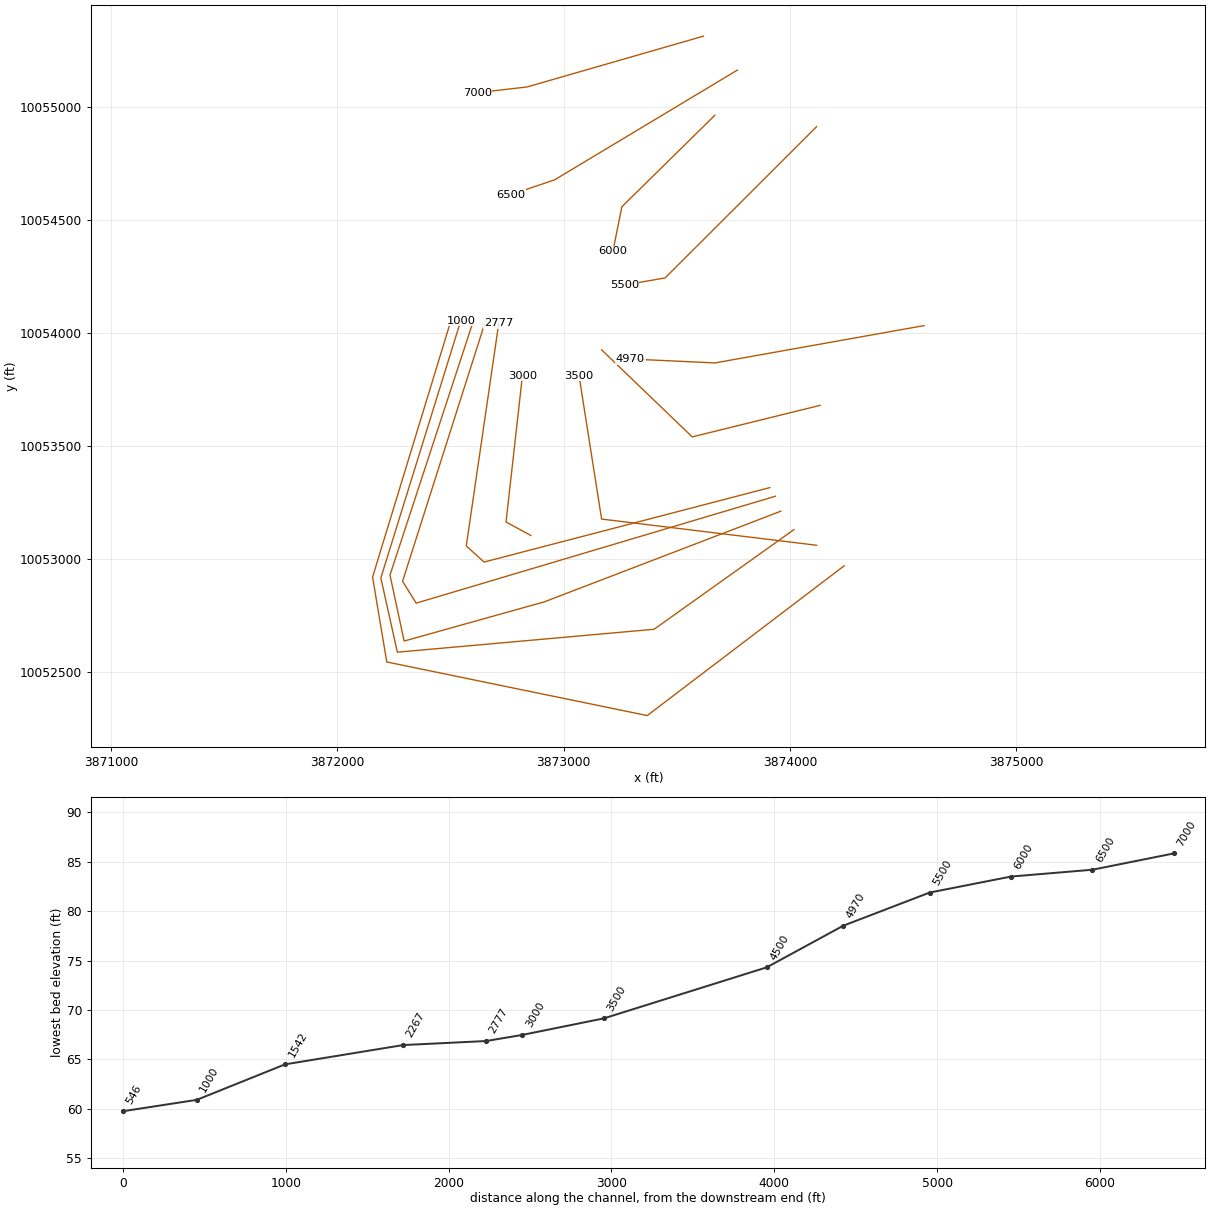
HEC-RAS study Crystal Creek 008.prj: Crystal Creek 008 Base Level Engineering

--- Crystal Creek 008.g10 (geometry) --- (continued)

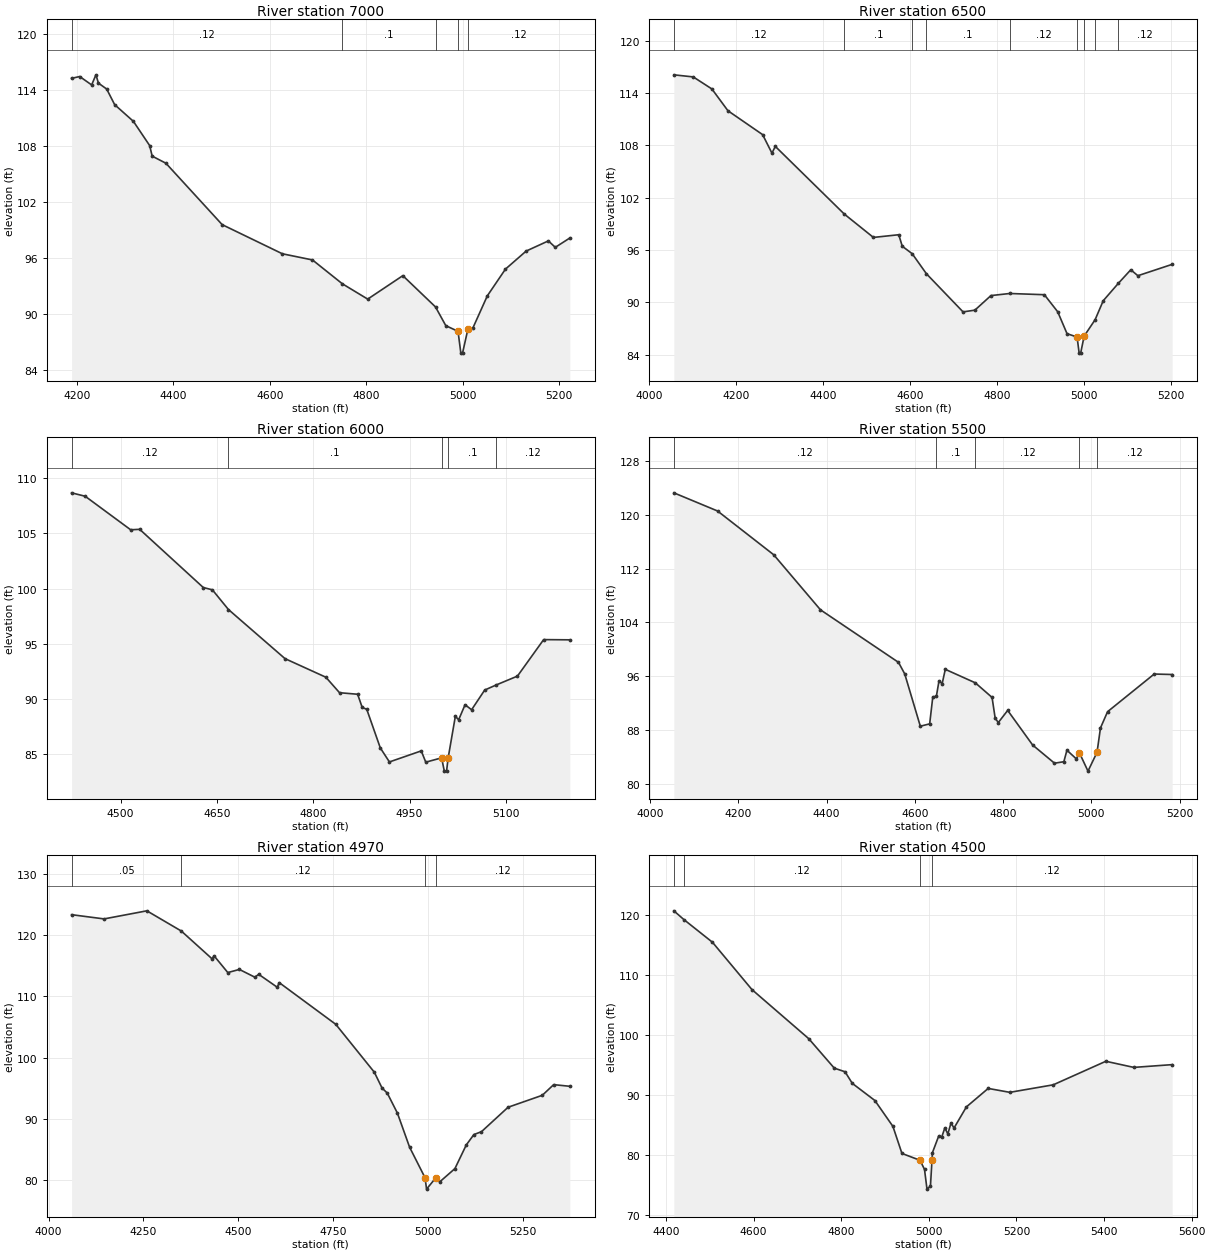
Type RM Length L Ch R = 1 ,7000    ,500,500,500
BEGIN DESCRIPTION:
Crystal Creek 008 13.0
END DESCRIPTION:
XS GIS Cut Line= 3
      3873617.82     10055311.06      3872838.24     10055086.44
      3872617.89     10055061.08
#Sta/Elev= 30
  4188.7  115.23  4205.5  115.43  4230.3  114.53  4239.2  115.61  4244.4  114.72
  4261.5  114.09    4278  112.42  4316.9  110.63  4350.6  108.04  4355.8  106.91
  4384.3  106.15  4500.9   99.58  4625.8   96.46  4688.2    95.8  4750.1   93.25
  4802.7   91.61  4875.5   94.12  4943.3   90.77  4964.6   88.77    4990   88.16
  4995.8   85.83  4999.3   85.83  5010.5   88.41  5020.5   88.49  5050.7   91.96
  5088.3   94.82  5131.2   96.75  5177.3   97.84  5191.6   97.15  5221.8   98.15
#Mann= 5 ,-1 , 0
  4188.7     .12       0  4750.1      .1       0  4943.3     .12       0
    4990     .07       0  5010.5     .12       0
Bank Sta=4990,5010.5
XS Rating Curve= 0 ,0
Exp/Cntr=0.3,0.1

Type RM Length L Ch R = 1 ,6500    ,500,500,500
BEGIN DESCRIPTION:
Crystal Creek 008 12.0
END DESCRIPTION:
XS GIS Cut Line= 3
      3873767.81     10055161.05      3872959.45     10054675.65
      3872767.84     10054611.07
#Sta/Elev= 30
  4057.1   116.1  4101.7  115.86  4144.5  114.48  4181.4  111.98  4261.1  109.24
  4282.5  107.12  4290.3  107.89  4448.8  100.13  4515.7   97.45    4574   97.76
    4582   96.44  4604.9   95.58  4637.6   93.28  4721.7   88.91  4748.9   89.11
  4785.8   90.78    4829   91.02  4908.6   90.88  4939.3   88.92  4960.7   86.41
 4983.81  86.026  4988.5   84.18    4992   84.18    5000   86.13  5025.2   88.01
  5043.9   90.19  5078.5   92.18  5107.2   93.74  5123.5   93.06  5202.2   94.36
#Mann= 9 ,-1 , 0
  4057.1     .12       0  4448.8      .1       0  4604.9     .12       0
  4637.6      .1       0    4829     .12       0 4983.81     .07       0
    5000     .12       0  5025.2      .1       0  5078.5     .12       0
Bank Sta=4983.81,5000
XS Rating Curve= 0 ,0
Exp/Cntr=0.3,0.1

Type RM Length L Ch R = 1 ,6000    ,500,500,500
BEGIN DESCRIPTION:
Crystal Creek 008 11.0
END DESCRIPTION:
XS GIS Cut Line= 3
      3873667.87     10054961.09      3873257.11     10054556.86
      3873217.85     10054361.06
#Sta/Elev= 30
  4423.7  108.65  4444.9  108.34  4515.7  105.31  4529.8  105.35  4628.8  100.09
    4643   99.88    4668    98.1  4756.1   93.66  4819.7   91.98    4841   90.58
  4869.2   90.44  4876.3   89.25  4883.4   89.08  4904.5   85.59  4918.7   84.32
  4968.3   85.32  4975.3    84.3    5000   84.69  5004.2   83.49  5007.7   83.49
 5010.17  84.679  5021.4   88.45  5026.5   88.13  5036.5   89.49  5046.7   89.04
  5067.1   90.82  5085.4   91.29  5118.1   92.08  5158.9   95.38  5199.7   95.36
#Mann= 5 ,-1 , 0
  4423.7     .12       0    4668      .1       0    5000     .07       0
 5010.17      .1       0  5085.4     .12       0
Bank Sta=5000,5010.17
XS Rating Curve= 0 ,0
Exp/Cntr=0.3,0.1

Type RM Length L Ch R = 1 ,5500    ,530,530,530
BEGIN DESCRIPTION:
Crystal Creek 008 10.0
END DESCRIPTION:
XS GIS Cut Line= 3
      3874117.84     10054911.06      3873448.24     10054242.54
      3873267.86     10054211.07
#Sta/Elev= 30
  4053.8  123.26  4152.8  120.56  4280.1  114.05  4386.1  105.86  4562.9   98.05
    4577   96.34  4612.4   88.55  4633.6    88.9  4640.7   92.92  4648.7   92.97
  4654.8   95.31  4661.9   94.88    4669   97.01  4737.1      95    4775   92.83
  4782.1   89.73  4789.2    89.1  4810.4    90.9    4867   85.75  4916.5   83.05
  4937.7   83.27  4944.7   84.98    4966   83.69    4973   84.59  4992.4   81.87
 5012.92  84.667  5020.7   88.29  5036.8   90.71  5142.5   96.31  5183.1   96.24
#Mann= 5 ,-1 , 0
  4053.8     .12       0  4648.7      .1       0  4737.1     .12       0
    4973     .07       0 5012.92     .12       0
Bank Sta=4973,5012.92
XS Rating Curve= 0 ,0
Exp/Cntr=0.3,0.1

Type RM Length L Ch R = 1 ,4970    ,470,470,470
BEGIN DESCRIPTION:
Crystal Creek 008 9.0
END DESCRIPTION:
XS GIS Cut Line= 3
      3874593.04     10054031.84      3873668.24     10053866.86
      3873295.34     10053884.26
#Sta/Elev= 30
  4060.6  123.33  4146.2  122.64  4258.9  123.96  4349.7  120.66  4430.8  116.12
  4435.9  116.62  4472.2  113.88  4502.7  114.39  4543.3  113.13  4553.7  113.59
  4602.5  111.48  4607.6  112.24  4756.6  105.43  4858.2   97.61  4878.5   95.03
  4892.2   94.21  4919.1   90.92  4951.1   85.37 4991.95   80.36  4995.8   78.52
  5020.4   80.39  5030.4    79.7  5070.5   81.87  5100.5   85.74  5120.5   87.43
  5140.5    87.9  5210.6   91.89  5300.7   93.84  5330.7   95.58  5373.3   95.31
#Mann= 4 ,-1 , 0
  4060.6     .05       0  4349.7     .12       0 4991.95     .07       0
  5020.4     .12       0
Bank Sta=4991.95,5020.4
XS Rating Curve= 0 ,0
Exp/Cntr=0.3,0.1

Type RM Length L Ch R = 1 ,4500    ,1000,1000,1000
BEGIN DESCRIPTION:
Crystal Creek 008 8.0
END DESCRIPTION:
XS GIS Cut Line= 3
      3874133.38      10053679.4      3873568.24     10053539.94
      3873167.66     10053924.66
#Sta/Elev= 30
  4417.9  120.63  4440.7  119.18    4506   115.4  4596.2  107.52  4725.7   99.36
  4784.1   94.45  4808.7   93.84  4825.3   91.91  4876.8   89.06    4918   84.75
  4938.6   80.25  4979.8   79.11  4990.1    77.6  4995.8   74.31  5003.7   74.81
 5007.26  79.216  5008.2   80.38  5022.3    83.1  5029.2   82.93  5036.5   84.49
  5043.4    83.5  5050.6   85.31  5057.5   84.48  5085.8      88  5135.5   91.07
  5184.9   90.42    5284   91.67  5404.1   95.59  5467.9   94.57  5555.4   95.03
#Mann= 4 ,-1 , 0
  4417.9     .05       0  4440.7     .12       0  4979.8     .07       0
 5007.26     .12       0
Bank Sta=4979.8,5007.26
XS Rating Curve= 0 ,0
Exp/Cntr=0.3,0.1

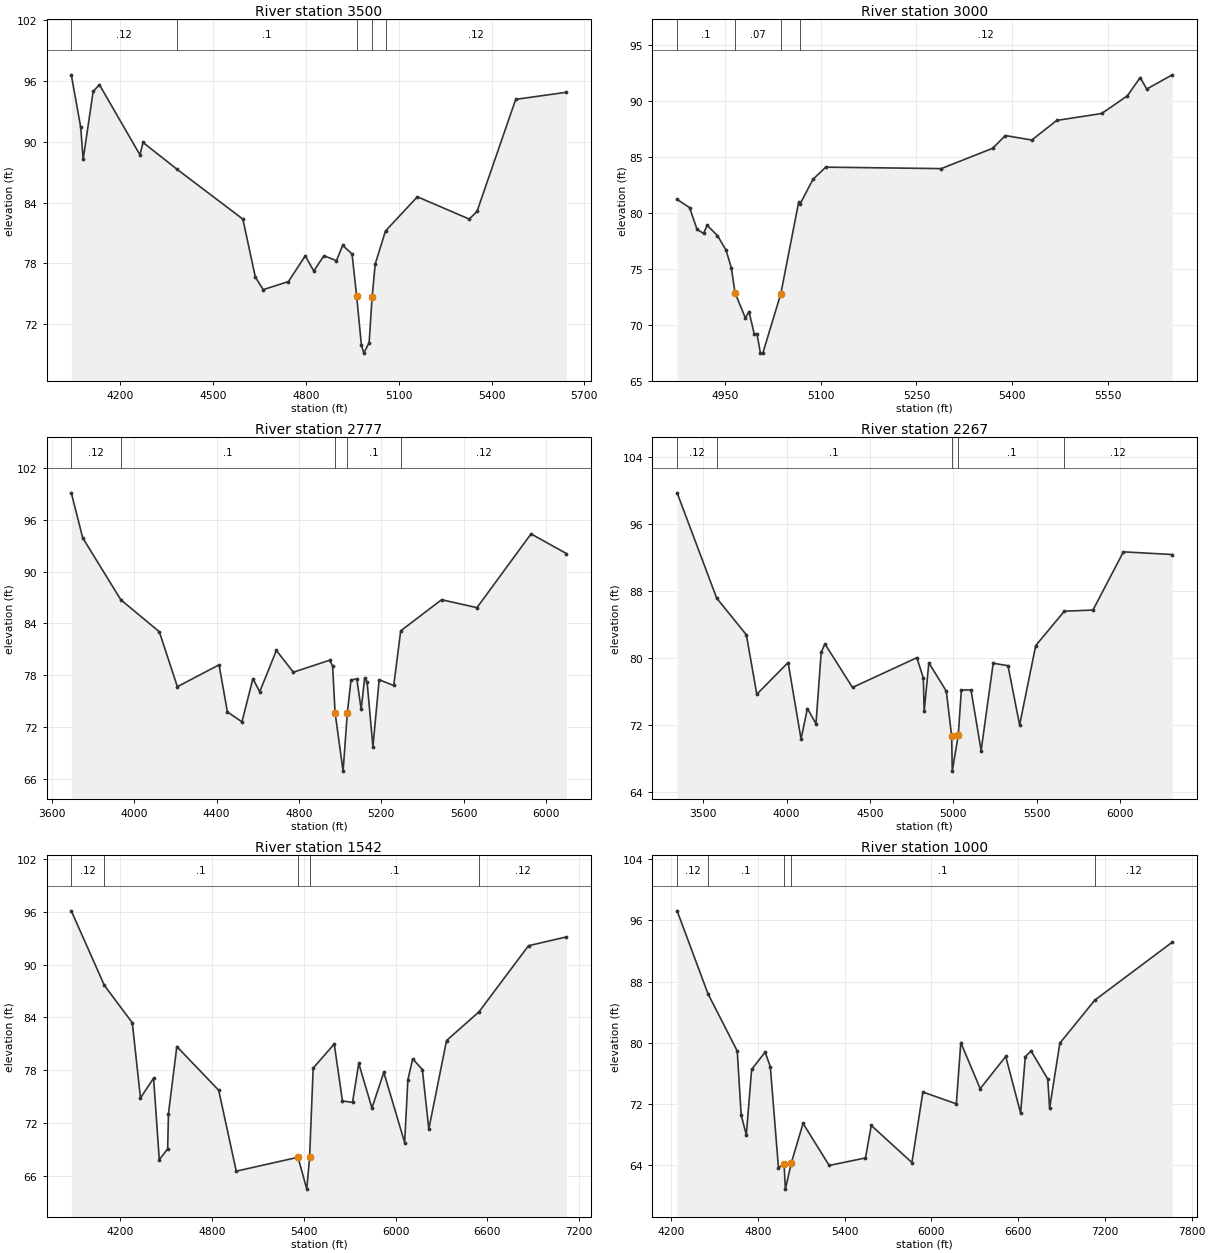
Type RM Length L Ch R = 1 ,3500    ,500,500,500
BEGIN DESCRIPTION:
Crystal Creek 008 7.0
END DESCRIPTION:
XS GIS Cut Line= 3
      3874117.88     10053061.07      3873167.71     10053176.86
      3873067.86     10053811.05
#Sta/Elev= 30
  4042.8    96.6  4073.1   91.45  4081.1   88.26  4113.4   94.96  4133.5   95.63
  4264.5   88.71  4274.5   89.93  4383.2   87.31  4596.9   82.37  4637.2   76.65
  4662.6   75.41  4744.2   76.21  4798.4   78.75  4825.8   77.25  4858.8   78.76
  4899.1   78.27  4919.3   79.78  4949.5   78.94 4964.42  74.763  4979.7   69.96
  4987.3   69.15  5004.7   70.17  5014.4   74.71  5024.5   77.96  5057.6    81.2
  5160.5   84.57  5328.2   82.37  5353.1   83.13  5478.1   94.18    5642   94.88
#Mann= 5 ,-1 , 0
  4042.8     .12       0  4383.2      .1       0 4964.42     .07       0
  5014.4      .1       0  5057.6     .12       0
Bank Sta=4964.42,5014.4
XS Rating Curve= 0 ,0
Exp/Cntr=0.3,0.1

Type RM Length L Ch R = 1 ,3000    ,223,223,223
BEGIN DESCRIPTION:
Crystal Creek 008 6.0
END DESCRIPTION:
XS GIS Cut Line= 3
      3872855.31     10053104.21      3872745.23     10053163.86
      3872817.85      10053811.1
#Sta/Elev= 30
  4874.8    81.2  4894.3   80.47    4906   78.53  4916.2   78.16  4921.9   78.89
  4938.1   77.97  4951.5   76.67  4959.9   75.08  4965.6   72.87  4981.8   70.62
  4987.5   71.18  4995.7   69.21    5000   69.21  5005.4   67.48  5009.2   67.48
  5037.4   72.78  5065.5   80.98  5067.8   80.81  5087.8   82.99  5107.9   84.08
    5289   83.95  5369.5   85.76  5389.6    86.9    5431    86.5  5470.1   88.25
  5540.6   88.87  5580.8   90.44    5601   92.08  5611.2   91.05  5651.3   92.32
#Mann= 4 ,-1 , 0
  4874.8      .1       0  4965.6     .07       0  5037.4      .1       0
  5067.8     .12       0
Bank Sta=4965.6,5037.4
XS Rating Curve= 0 ,0
Exp/Cntr=0.3,0.1

Type RM Length L Ch R = 1 ,2777    ,510,510,510
BEGIN DESCRIPTION:
Crystal Creek 008 5.0
END DESCRIPTION:
XS GIS Cut Line= 4
      3873911.48     10053315.92      3872648.24     10052986.86
      3872569.68     10053058.05      3872713.09     10054041.23
#Sta/Elev= 30
  3694.6   99.12    3750    93.9  3935.2   86.72    4122   83.02  4209.8   76.65
  4412.3   79.18  4452.8   73.73  4523.5   72.57  4576.7   77.58  4609.7   76.06
  4690.7   80.85  4773.1   78.33  4948.7   79.71  4963.8   79.07 4975.76  73.655
  5014.7   66.86  5035.3  73.608  5053.1   77.43  5081.5   77.55  5102.4   74.01
  5119.2   77.61  5131.2   77.22  5159.6   69.68  5189.9   77.45  5260.7   76.79
  5294.5   83.12  5493.1   86.73  5664.9   85.81  5927.6   94.36  6099.6   92.08
#Mann= 5 ,-1 , 0
  3694.6     .12       0  3935.2      .1       0 4975.76     .07       0
  5035.3      .1       0  5294.5     .12       0
Bank Sta=4975.76,5035.3
XS Rating Curve= 0 ,0
Exp/Cntr=0.3,0.1

Type RM Length L Ch R = 1 ,2267    ,725,725,725
BEGIN DESCRIPTION:
Crystal Creek 008 4.0
END DESCRIPTION:
XS GIS Cut Line= 4
      3873935.83     10053277.73      3872348.24     10052805.28
        3872288.     10052901.64      3872652.13     10054044.29
#Sta/Elev= 30
  3343.6   99.74  3580.7   87.15  3758.8   82.76  3821.4   75.65  4009.2   79.44
  4086.6    70.3    4125   73.94  4176.2   72.12  4207.5   80.65  4229.7   81.67
  4395.3   76.46  4781.3   80.02  4819.9    77.6  4825.1    73.6  4853.1   79.41
  4957.8   76.02    4990   70.61  4993.6   66.45 5029.52  70.758    5048   76.15
  5105.8   76.17  5166.6   68.91    5239   79.36  5327.7   79.06  5397.4   71.97
    5494   81.47  5665.7   85.58  5837.2   85.72  6019.9   92.68  6312.9   92.36
#Mann= 5 ,-1 , 0
  3343.6     .12       0  3580.7      .1       0    4990     .07       0
 5029.52      .1       0  5665.7     .12       0
Bank Sta=4990,5029.52
XS Rating Curve= 0 ,0
Exp/Cntr=0.3,0.1

Type RM Length L Ch R = 1 ,1542    ,542,542,542
BEGIN DESCRIPTION:
Crystal Creek 008 3.0
END DESCRIPTION:
XS GIS Cut Line= 5
      3873960.13     10053211.76      3872914.23     10052810.87
      3872294.95     10052637.75      3872232.45     10052929.41
      3872598.77     10054045.95
#Sta/Elev= 30
  3879.9    96.1  4095.7   87.64  4278.6   83.39  4332.1   74.85  4417.8    77.1
  4454.9   67.85  4509.7   69.06    4515   73.08  4569.7   80.69  4843.3   75.73
  4958.1   66.54 5361.81  68.118    5419    64.5 5437.53  68.132  5460.9   78.24
  5598.5   80.98  5652.3   74.51    5718   74.35  5758.9   78.78  5844.9   73.71
  5922.6   77.76  6058.8   69.79  6079.9   76.92  6111.4   79.29  6174.6   78.08
  6216.7   71.32  6332.6   81.37  6544.6   84.63  6868.4   92.14  7116.4   93.14
#Mann= 5 ,-1 , 0
  3879.9     .12       0  4095.7      .1       0 5361.81     .07       0
 5437.53      .1       0  6544.6     .12       0
Bank Sta=5361.81,5437.53
XS Rating Curve= 0 ,0
Exp/Cntr=0.3,0.1

Type RM Length L Ch R = 1 ,1000    ,454,454,454
BEGIN DESCRIPTION:
Crystal Creek 008 2.0
END DESCRIPTION:
XS GIS Cut Line= 5
      3874017.59     10053130.14       3873399.6     10052689.83
        3872265.     10052588.49      3872192.08     10052916.61
      3872545.38     10054053.75
#Sta/Elev= 30
  4241.2   97.23  4454.8    86.4    4657   78.94    4684   70.63  4719.7   67.97
  4756.6   76.53    4850   78.79  4885.7   76.88  4942.2   63.68  4980.7  64.215
    4990   60.91 5030.03  64.264  5112.2   69.49  5292.9      64  5543.9   64.98
  5584.1   69.22  5865.2   64.38    5941   73.58  6172.5   72.04  6203.2   80.03
  6337.5   74.02  6514.1   78.23    6617   70.83  6649.5   78.21  6689.3   78.94
  6804.5   75.29  6817.6   71.47  6888.3   79.96    7130   85.57    7666   93.14
#Mann= 5 ,-1 , 0
  4241.2     .12       0  4454.8      .1       0  4980.7     .07       0
 5030.03      .1       0    7130     .12       0
Bank Sta=4980.7,5030.03
XS Rating Curve= 0 ,0
Exp/Cntr=0.3,0.1

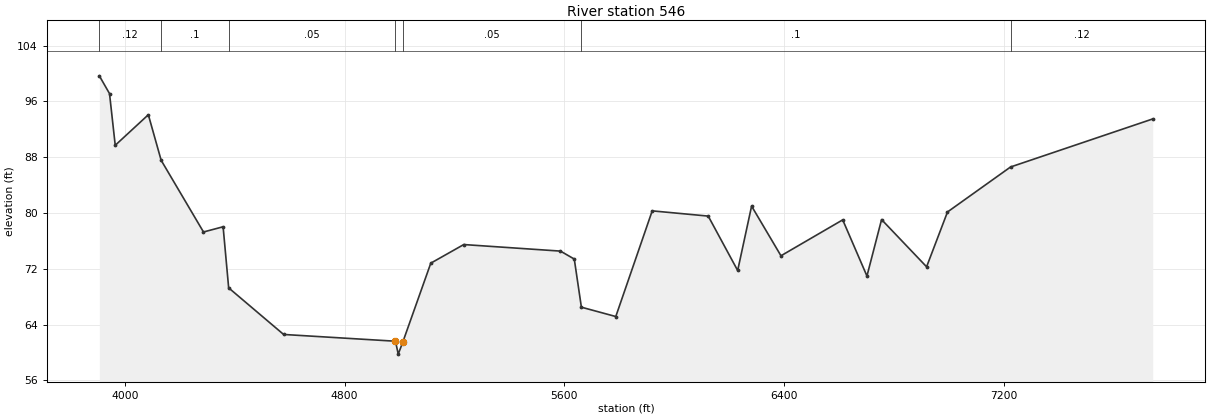
Type RM Length L Ch R = 1 ,546     ,0,0,0
BEGIN DESCRIPTION:
Crystal Creek 008 1.0
END DESCRIPTION:
XS GIS Cut Line= 5
      3874239.84     10052970.44      3873369.26     10052308.41
      3872218.31     10052545.31      3872155.51     10052920.41
      3872502.63     10054056.78
#Sta/Elev= 30
  3906.3   99.66  3943.4   97.11  3964.2    89.7  4084.8   94.08  4131.5   87.55
  4285.7   77.27  4357.2   78.02  4377.4   69.26  4577.6   62.58  4985.1   61.61
  4995.1   59.76  5011.6   61.47  5113.7    72.8  5233.8   75.47  5586.1   74.53
  5636.4   73.39  5662.3   66.49  5787.6   65.15  5920.3    80.3  6124.3   79.55
  6231.6   71.75  6282.3   80.98  6389.3   73.86  6614.2   79.01  6702.5   70.96
  6755.8   79.05  6919.8   72.28  6995.9   80.14  7225.6   86.59  7743.6   93.48
#Mann= 7 ,-1 , 0
  3906.3     .12       0  4131.5      .1       0  4377.4     .05       0
  4985.1     .07       0  5011.6     .05       0  5662.3      .1       0
  7225.6     .12       0
Bank Sta=4985.1,5011.6
XS Rating Curve= 0 ,0
Exp/Cntr=0.3,0.1