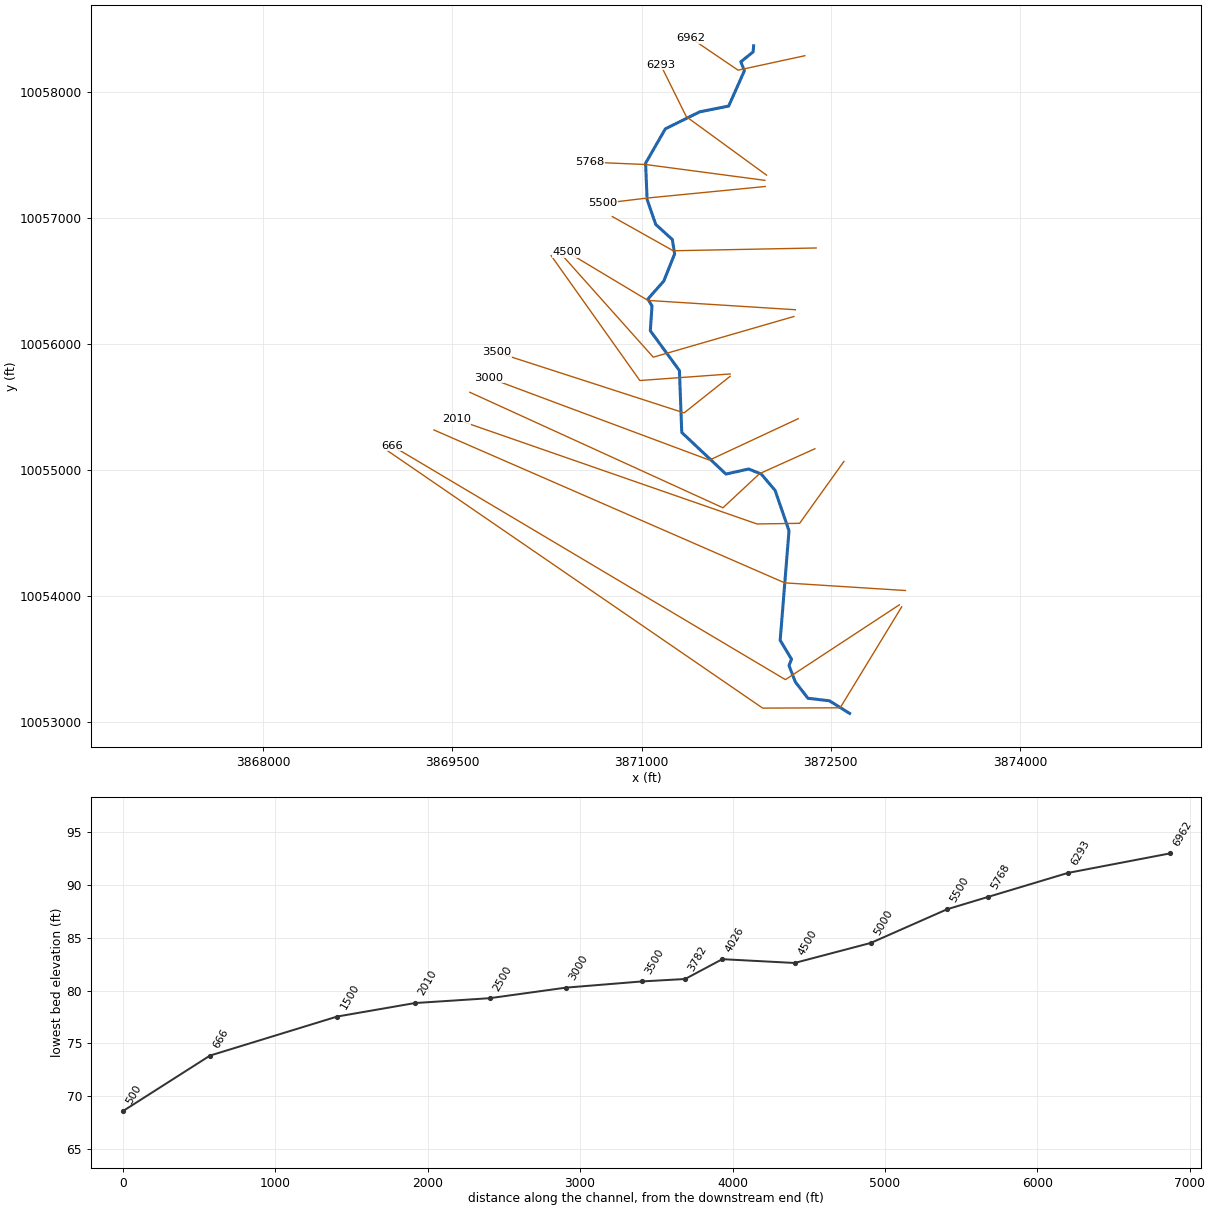
--- Crystal Creek 009.prj (project) ---

Proj Title=Crystal Creek 009 Base Level Engineering
Current Plan=p01
Default Exp/Contr=0.3,0.1
English Units
Geom File=g01
Flow File=f01
Flow File=f02
Plan File=p01
Y Axis Title=Elevation
X Axis Title(PF)=Main Channel Distance
X Axis Title(XS)=Station
BEGIN DESCRIPTION:
Crystal Creek 009
END DESCRIPTION:
DSS Export Rating Curves= 0
DSS Export Rating Curve Sorted= 0
DSS Export Volume Flow Curves= 0
DXF OffsetX= 0
DXF OffsetY= 0
DXF ScaleX= 1
DXF ScaleY= 10

--- Crystal Creek 009.p01 (plan) ---

Plan Title=Multiple Run
Short Identifier=Multiple
Geom File=g01
Flow File=f01
Subcritical Flow
K Sum by GR= 0
Std Step Tol= 0.01
Critical Tol= 0.01
Num of Std Step Trials= 20
Max Error Tol= 0.3
Flow Tol Ratio= 0.001
Split Flow NTrial= 30
Split Flow Tol= 0.02
Split Flow Ratio= 0.02
Log Output Level= 0
Friction Slope Method= 1
Unsteady Friction Slope Method= 2
Unsteady Bridges Friction Slope Method= 1
Parabolic Critical Depth
Global Vel Dist=  1 , 1 , 1
Global Log Level= 0
CheckData=True
Encroach Param= -1, 0, 0, 0
BEGIN DESCRIPTION:
Multiple Run
END DESCRIPTION:

--- Crystal Creek 009.f01 (steady flow) ---

Flow Title=Multiple
Program Version=4.10
Number of Profiles= 7
Profile Names=10-year,25-year,50-year,1pct_min,100-year,1pct_plu,500-year
River Rch & RM=Crystal Creek 00,Reach-1         ,6962
     485     628     825     356    1074    3243    1880
Boundary for River Rch & Prof#=Crystal Creek 00,Reach-1         , 1
Up Type= 0
Dn Type= 3
Dn Slope=0.009
Boundary for River Rch & Prof#=Crystal Creek 00,Reach-1         , 2
Up Type= 0
Dn Type= 3
Dn Slope=0.009
Boundary for River Rch & Prof#=Crystal Creek 00,Reach-1         , 3
Up Type= 0
Dn Type= 3
Dn Slope=0.009
Boundary for River Rch & Prof#=Crystal Creek 00,Reach-1         , 4
Up Type= 0
Dn Type= 3
Dn Slope=0.009
Boundary for River Rch & Prof#=Crystal Creek 00,Reach-1         , 5
Up Type= 0
Dn Type= 3
Dn Slope=0.009
Boundary for River Rch & Prof#=Crystal Creek 00,Reach-1         , 6
Up Type= 0
Dn Type= 3
Dn Slope=0.009
Boundary for River Rch & Prof#=Crystal Creek 00,Reach-1         , 7
Up Type= 0
Dn Type= 3
Dn Slope=0.009
DSS Import GetInterval= 0
DSS Import GetPeak= 0
DSS Import FillOption= 0

--- Crystal Creek 009.f02 (steady flow) ---

Flow Title=Orig_BLE_FLow
Program Version=4.10
Number of Profiles= 7
Profile Names=10-year,25-year,50-year,1pct_min,100-year,1pct_plu,500-year
River Rch & RM=Crystal Creek 00,Reach-1         ,6962
     485     616     717     273     826    2494    1093
Boundary for River Rch & Prof#=Crystal Creek 00,Reach-1         , 1
Up Type= 0
Dn Type= 3
Dn Slope=0.009
Boundary for River Rch & Prof#=Crystal Creek 00,Reach-1         , 2
Up Type= 0
Dn Type= 3
Dn Slope=0.009
Boundary for River Rch & Prof#=Crystal Creek 00,Reach-1         , 3
Up Type= 0
Dn Type= 3
Dn Slope=0.009
Boundary for River Rch & Prof#=Crystal Creek 00,Reach-1         , 4
Up Type= 0
Dn Type= 3
Dn Slope=0.009
Boundary for River Rch & Prof#=Crystal Creek 00,Reach-1         , 5
Up Type= 0
Dn Type= 3
Dn Slope=0.009
Boundary for River Rch & Prof#=Crystal Creek 00,Reach-1         , 6
Up Type= 0
Dn Type= 3
Dn Slope=0.009
Boundary for River Rch & Prof#=Crystal Creek 00,Reach-1         , 7
Up Type= 0
Dn Type= 3
Dn Slope=0.009
DSS Import GetInterval= 0
DSS Import GetPeak= 0
DSS Import FillOption= 0

--- Crystal Creek 009.g01 (geometry) ---

Geom Title=Existing Conditions
Program Version=4.10

River Reach=Crystal Creek 00,Reach-1
Reach XY= 30
       3871887.8       10058367.      3871884.19     10058318.46
      3871786.27     10058239.82      3871814.92     10058168.99
      3871689.92     10057888.26      3871459.83     10057842.39
       3871187.7     10057706.97      3871031.54     10057434.49
      3871043.47     10057147.16      3871111.83     10056948.59
      3871243.43     10056828.96      3871261.66     10056714.37
      3871175.98     10056499.61      3871049.59     10056356.08
       3871082.4     10056301.39      3871068.92      10056104.5
      3871299.55     10055788.62      3871318.24     10055296.86
      3871668.24     10054966.86      3871848.24     10055006.86
      3871948.24     10054966.86      3872058.24     10054836.86
      3872168.24     10054516.86      3872098.24     10053646.86
      3872188.24     10053496.86      3872168.24     10053446.86
      3872218.24     10053316.86      3872318.24     10053186.86
      3872488.24     10053166.86      3872648.24     10053066.86

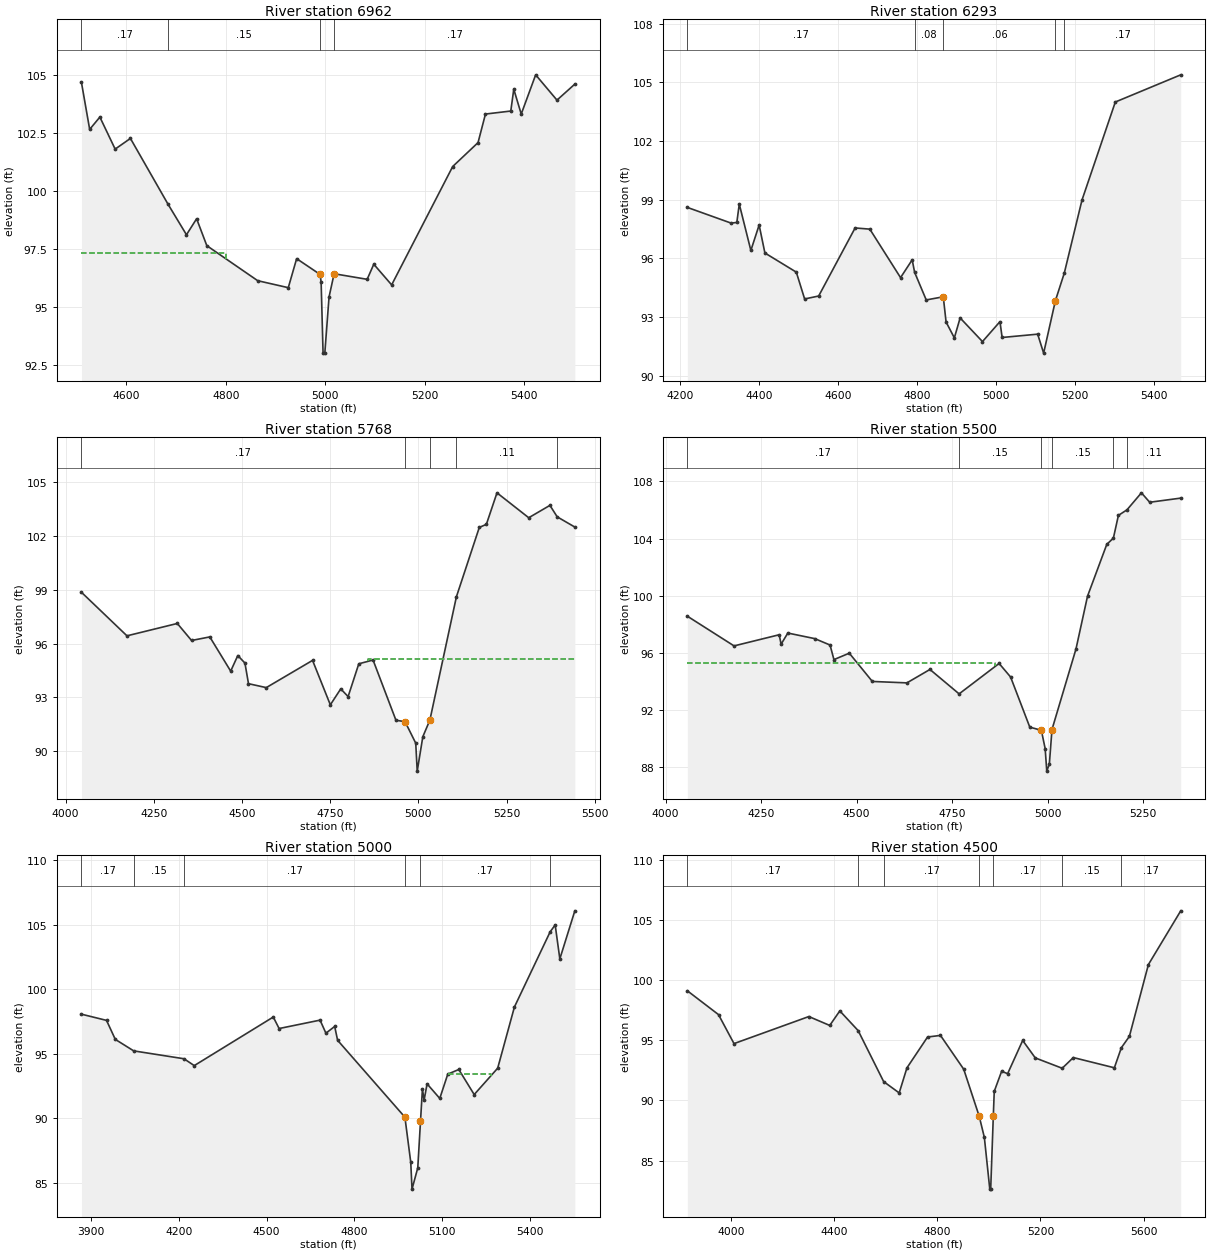
Type RM Length L Ch R = 1 ,6962    ,669,669,669
BEGIN DESCRIPTION:
Crystal Creek 009 14.0
END DESCRIPTION:
XS GIS Cut Line= 3
      3872294.02     10058288.16      3871764.54     10058173.15
      3871392.81     10058426.01
#Sta/Elev= 30
  4510.1  104.67  4526.6  102.65  4547.1  103.18  4577.8   101.8  4608.5  102.26
  4684.2   99.42  4721.1   98.11  4741.5    98.8    4762   97.64  4864.3   96.13
  4925.7   95.83  4942.5   97.08 4989.62    96.4  4991.7   96.06  4995.6   93.01
  4999.1   93.01  5007.6   95.43  5017.8   96.43  5084.2   96.19  5097.5   96.84
  5133.4   95.95  5256.1  101.05    5307  102.08  5321.9  103.31  5372.8  103.44
  5378.8  104.38  5393.8  103.31  5422.8     105  5465.6  103.91  5501.5   104.6
#Mann= 4 ,-1 , 0
  4510.1     .17       0  4684.2     .15       0 4989.62     .09       0
  5017.8     .17       0
#XS Ineff= 2 , 0
       0  4800.2   97.31               0
Permanent Ineff=
       F       F
Bank Sta=4989.62,5017.8
XS Rating Curve= 0 ,0
Exp/Cntr=0.3,0.1

Type RM Length L Ch R = 1 ,6293    ,525,525,525
BEGIN DESCRIPTION:
Crystal Creek 009 13.0
END DESCRIPTION:
XS GIS Cut Line= 3
      3871990.25      10057339.8      3871354.38     10057804.23
       3871150.5     10058216.34
#Sta/Elev= 30
  4219.4   98.61  4329.7   97.81  4344.4   97.84  4350.6   98.78  4379.9   96.41
  4400.8   97.71  4415.4   96.28  4494.8    95.3  4515.8   93.93  4551.3   94.08
  4643.4   97.56  4680.6    97.5  4758.3   95.02  4787.7   95.93  4793.9   95.29
  4823.2   93.88  4866.3   94.04  4873.4   92.75  4894.3   91.94  4908.9   92.96
  4965.4   91.75  5009.6   92.77  5015.1   91.96  5104.9   92.13    5120   91.16
  5149.7   93.84  5172.2   95.25    5217   98.99  5301.2     104  5466.6  105.39
#Mann= 5 ,-1 , 0
  4219.4     .17       0  4793.9     .08       0  4866.3     .06       0
  5149.7     .08       0  5172.2     .17       0
#XS Ineff= 2 , 0
       0  4787.7   95.93               0
Permanent Ineff=
       F       F
Bank Sta=4866.3,5149.7
XS Rating Curve= 0 ,0
Exp/Cntr=0.3,0.1

Type RM Length L Ch R = 1 ,5768    ,268,268,268
BEGIN DESCRIPTION:
Crystal Creek 009 12.0
END DESCRIPTION:
XS GIS Cut Line= 3
      3871977.19     10057298.59      3871031.03     10057424.45
      3870587.31     10057442.97
#Sta/Elev= 30
  4044.9   98.86  4173.9   96.43  4316.6   97.12    4357   96.17  4408.7   96.37
  4467.9   94.46  4488.1   95.33  4508.3   94.91  4518.4   93.76  4568.8   93.54
    4700   95.06  4750.4   92.58  4779.9   93.47  4800.8   93.04  4831.1   94.87
  4871.5   95.08  4936.4   91.72  4962.2   91.64  4992.5   90.44  4996.7   88.88
  5012.6    90.8  5032.6   91.73  5107.8   98.61  5172.7  102.48  5192.7  102.65
  5222.8  104.41  5312.8  103.02  5372.9  103.71  5393.5  103.07  5443.5   102.5
#Mann= 5 ,-1 , 0
  4044.9     .17       0  4962.2     .09       0  5032.6     .17       0
  5107.8     .11       0  5393.5     .17       0
#XS Ineff= 4 ,-1
  4871.5  4858.2   95.08  4858.2    4700   95.11    4700  4488.1   95.06
  4488.1  4437.7   95.33
Permanent Ineff=
       F       F       F       F
Bank Sta=4962.2,5032.6
XS Rating Curve= 0 ,0
Exp/Cntr=0.3,0.1

Type RM Length L Ch R = 1 ,5500    ,500,500,500
BEGIN DESCRIPTION:
Crystal Creek 009 11.0
END DESCRIPTION:
XS GIS Cut Line= 3
      3871979.42     10057249.76      3871041.02     10057157.71
      3870695.75     10057115.87
#Sta/Elev= 30
  4057.1   98.56  4179.2   96.48  4297.3   97.26  4302.3    96.6  4319.9   97.38
  4390.3   96.99  4430.4   96.54  4440.5   95.52  4480.7   95.97    4541   93.99
  4631.4   93.89  4691.7   94.83    4768   93.12  4872.6   95.25  4902.7    94.3
  4952.9   90.79  4983.1   90.57  4993.1   89.29  4997.3   87.71  5004.1   88.21
  5010.9   90.62  5073.7   96.26  5103.9   99.96  5154.3  103.59  5171.6  104.03
  5184.7  105.62  5207.2  106.01  5244.9   107.2  5266.6  106.54  5347.8  106.83
#Mann= 6 ,-1 , 0
  4057.1     .17       0    4768     .15       0  4983.1     .09       0
  5010.9     .15       0  5171.6     .17       0  5207.2     .11       0
#XS Ineff= 2 , 0
       0  4862.5    95.3               0
Permanent Ineff=
       F       F
Bank Sta=4983.1,5010.9
XS Rating Curve= 0 ,0
Exp/Cntr=0.3,0.1

Type RM Length L Ch R = 1 ,5000    ,500,500,500
BEGIN DESCRIPTION:
Crystal Creek 009 10.0
END DESCRIPTION:
XS GIS Cut Line= 3
       3872383.5     10056761.69      3871250.62     10056739.62
      3870767.89     10057011.05
#Sta/Elev= 30
  3866.9   98.06  3952.6   97.58  3982.6   96.11  4045.5   95.22  4217.5   94.61
  4252.6   94.08  4522.7   97.84  4542.7   96.95  4682.7    97.6  4702.7   96.59
  4732.7   97.11  4742.7   96.04  4972.8   90.09  4992.8    86.6  4997.1   84.52
  5016.8   86.17  5026.1   89.76  5032.7   92.27  5038.4    91.4  5048.6   92.67
    5092   91.54  5119.4   93.42    5157   93.78  5209.7   91.84    5290   93.88
  5347.3   98.62  5469.3  104.43  5486.6  104.97  5502.5  102.34  5553.8  106.06
#Mann= 6 ,-1 , 0
  3866.9     .17       0  4045.5     .15       0  4217.5     .17       0
  4972.8     .09       0  5026.1     .17       0  5469.3     .11       0
#XS Ineff= 3 ,-1
  5032.7  5048.6   92.27  5048.6  5119.4   92.67  5119.4    5267   93.42
Permanent Ineff=
       F       F       F
Bank Sta=4972.8,5026.1
XS Rating Curve= 0 ,0
Exp/Cntr=0.3,0.1

Type RM Length L Ch R = 1 ,4500    ,474,474,474
BEGIN DESCRIPTION:
Crystal Creek 009 9.0
END DESCRIPTION:
XS GIS Cut Line= 3
      3872218.49     10056271.46      3871050.03     10056345.33
      3870411.84     10056728.73
#Sta/Elev= 30
  3829.2   99.11  3950.1   97.13  4010.2   94.72  4300.8   96.97  4381.9   96.23
    4421   97.44  4492.2    95.8  4591.2   91.56  4651.5   90.62  4681.5    92.7
  4761.7   95.27  4811.8    95.4    4902   92.59  4962.1   88.68  4982.1   86.92
  5003.2   82.62  5006.7   82.62  5016.988.70988  5020.5   90.75  5049.2   92.42
  5072.5   92.22  5130.9   94.98  5179.8   93.53  5284.3   92.67  5327.5   93.56
  5486.8   92.71    5514   94.38  5545.1   95.32  5618.9  101.29  5744.5  105.76
#Mann= 7 ,-1 , 0
  3829.2     .17       0  4492.2     .15       0  4591.2     .17       0
  4962.1     .09       0  5016.9     .17       0  5284.3     .15       0
    5514     .17       0
Bank Sta=4962.1,5016.9
XS Rating Curve= 0 ,0
Exp/Cntr=0.3,0.1

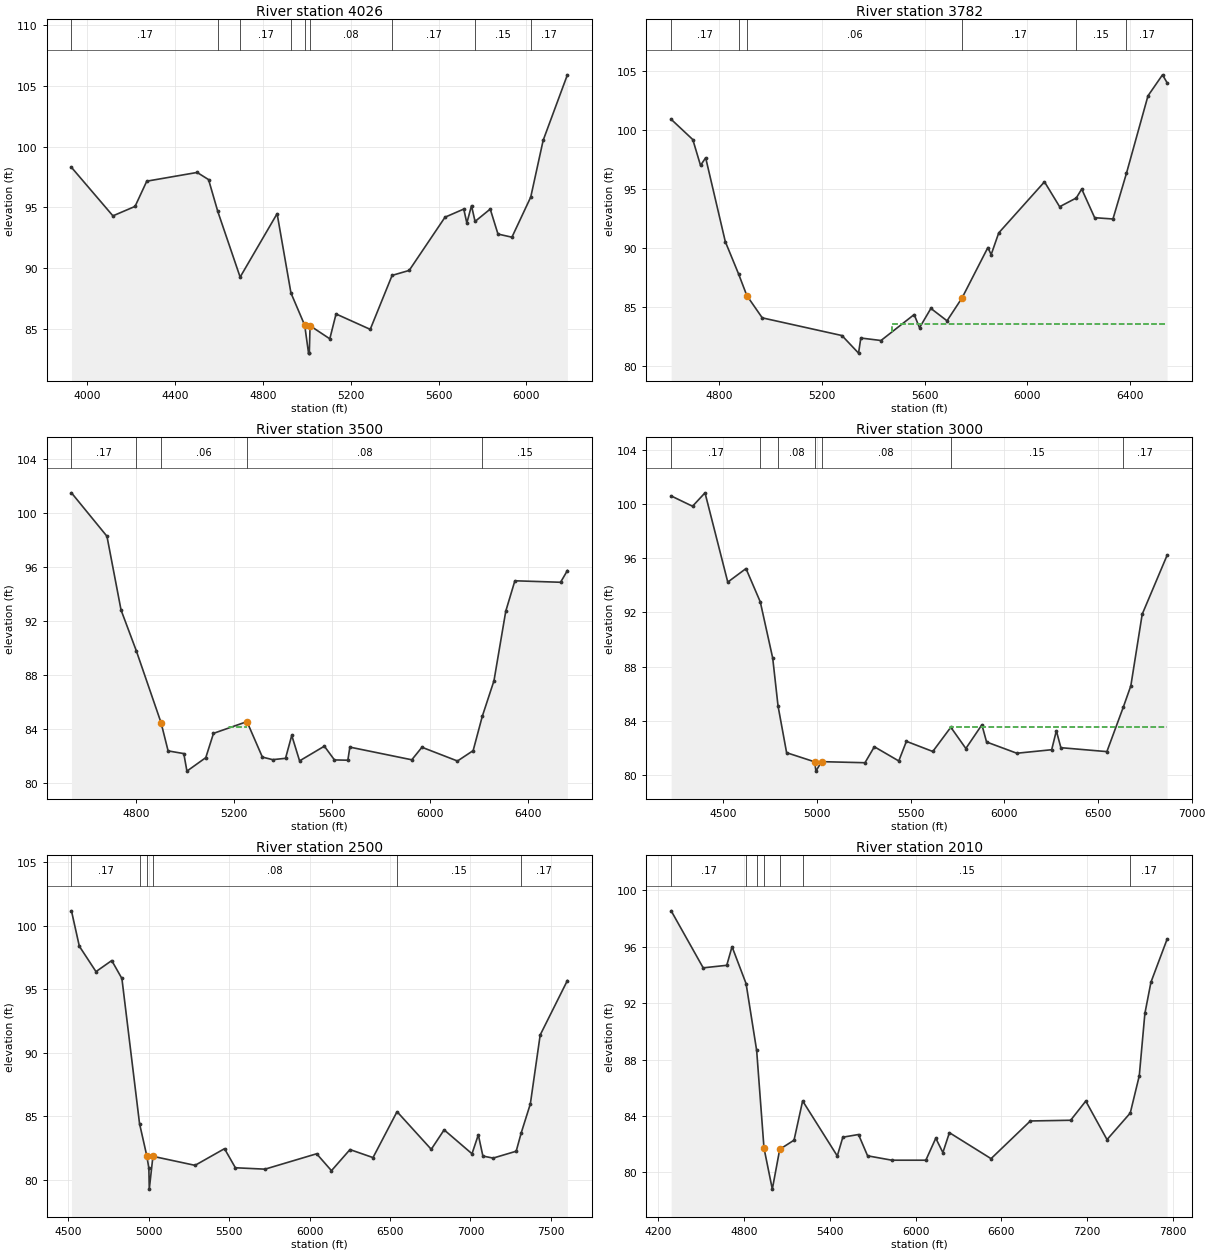
Type RM Length L Ch R = 1 ,4026    ,244,244,244
BEGIN DESCRIPTION:
Mapping XS 31c25574
END DESCRIPTION:
XS GIS Cut Line= 3
      3872206.96     10056217.68      3871092.37     10055894.76
      3870363.22     10056712.46
#Sta/Elev= 30
  3930.1    98.3  4118.7    94.3  4219.4   95.08  4272.7   97.16  4501.8   97.88
  4553.8   97.29  4595.8   94.66  4697.4   89.25  4865.6   94.48  4928.6   87.94
  4991.1   85.28  5008.6   82.98  5012.1   82.98  5015.5   85.24  5105.3   84.16
  5133.7   86.21  5289.2   84.94  5388.7   89.39  5466.4    89.8  5629.5   94.19
  5714.7   94.86  5728.7   93.71  5749.9   95.14  5766.1   93.84  5835.1   94.86
  5870.3    92.8  5933.8   92.54  6019.4   95.85  6075.9  100.53  6186.1  105.93
#Mann= 9 ,-1 , 0
  3930.1     .17       0  4595.8     .15       0  4697.4     .17       0
  4928.6     .08       0  4991.1     .06       0  5015.5     .08       0
  5388.7     .17       0  5766.1     .15       0  6019.4     .17       0
#XS Ineff= 2 , 0
       0                  5133.7       0   86.21
Permanent Ineff=
       F       F
Bank Sta=4991.1,5015.5
XS Rating Curve= 0 ,0
Exp/Cntr=0.3,0.1

Type RM Length L Ch R = 1 ,3782    ,282,282,282
BEGIN DESCRIPTION:
Crystal Creek 009 8.0
END DESCRIPTION:
XS GIS Cut Line= 3
      3871702.04     10055761.48      3870985.89     10055709.39
       3870282.8      10056701.1
#Sta/Elev= 30
  4611.7  100.92  4696.1    99.2  4726.2   97.01  4746.2   97.66  4822.8   90.55
  4874.6   87.81  4906.7   85.98  4966.9   84.09  5277.6   82.59  5342.3    81.1
  5351.2   82.38  5429.9   82.17  5559.2   84.37  5580.1   83.25  5624.4   84.89
  5687.3   83.84  5746.2   85.79  5846.6   90.05  5859.4   89.45  5888.9   91.29
  6067.3   95.62  6126.4   93.51  6191.3   94.25  6212.5   95.01    6263   92.58
  6334.3   92.47  6386.9   96.34  6470.9  102.91  6527.5  104.69  6545.4  104.02
#Mann= 6 ,-1 , 0
  4611.7     .17       0  4874.6     .15       0  4906.7     .06       0
  5746.2     .17       0  6191.3     .15       0  6386.9     .17       0
#XS Ineff= 2 , 0
       0  5127.2    83.3    5473       0   83.53
Permanent Ineff=
       F       F
Bank Sta=4906.7,5746.2
XS Rating Curve= 0 ,0
Exp/Cntr=0.3,0.1

Type RM Length L Ch R = 1 ,3500    ,500,500,500
BEGIN DESCRIPTION:
Crystal Creek 009 7.0
END DESCRIPTION:
XS GIS Cut Line= 3
      3871701.09     10055742.54      3871336.99     10055452.51
      3869852.53     10055933.38
#Sta/Elev= 30
  4534.5   101.5  4679.5   98.28  4737.1   92.81  4799.4   89.79  4900.5   84.46
  4929.3   82.37  4993.4   82.17  5006.2   80.87  5083.2   81.87  5114.7   83.67
  5251.4   84.54  5314.4   81.91  5356.5   81.72    5409   81.82  5434.4   83.52
  5466.4   81.63  5567.6   82.72  5608.8    81.7  5663.6   81.68  5671.8   82.65
  5924.8   81.71  5966.2   82.64  6111.4   81.62  6175.4   82.39  6212.7   84.93
  6260.5   87.57  6308.7   92.73  6345.9   94.98  6532.6   94.87  6560.4   95.74
#Mann= 5 ,-1 , 0
  4534.5     .17       0  4799.4     .15       0  4900.5     .06       0
  5251.4     .08       0  6212.7     .15       0
#XS Ineff= 3 ,-1
  5114.7  5178.4   83.67  5178.4  5251.4   84.11  5251.4  6212.7   84.54
Permanent Ineff=
       F       F       F
Bank Sta=4900.5,5251.4
XS Rating Curve= 0 ,0
Exp/Cntr=0.3,0.1

Type RM Length L Ch R = 1 ,3000    ,500,500,500
BEGIN DESCRIPTION:
Crystal Creek 009 6.0
END DESCRIPTION:
XS GIS Cut Line= 3
      3872241.48     10055406.54      3871537.58     10055077.52
      3869787.04     10055732.05
#Sta/Elev= 30
    4223  100.59    4337   99.83  4403.6  100.82    4525   94.23  4622.2   95.23
  4698.5   92.77  4764.8   88.62  4793.2   85.09  4838.9   81.64  4988.480.96721
  4995.3   80.28  5025.4   80.98  5257.1    80.9    5307   82.08  5437.4   81.03
    5478   82.48  5618.8   81.73    5715   83.52  5795.2   81.95  5880.8    83.7
  5905.7   82.43  6067.3    81.6  6253.2   81.86  6278.1   83.26  6302.2   82.01
  6547.7   81.72  6635.7   85.02  6675.5   86.58  6736.1   91.86  6868.9   96.21
#Mann= 7 ,-1 , 0
    4223     .17       0  4698.5     .15       0  4793.2     .08       0
  4988.4     .06       0  5025.4     .08       0    5715     .15       0
  6635.7     .17       0
#XS Ineff= 2 , 0
       0                  5709.7       0   83.55
Permanent Ineff=
       F       F
Bank Sta=4988.4,5025.4
XS Rating Curve= 0 ,0
Exp/Cntr=0.3,0.1

Type RM Length L Ch R = 1 ,2500    ,490,490,490
BEGIN DESCRIPTION:
Crystal Creek 009 5.0
END DESCRIPTION:
XS GIS Cut Line= 4
      3872373.85     10055167.82      3871935.06     10054970.04
      3871644.66     10054699.07      3869638.27     10055616.06
#Sta/Elev= 30
  4518.7  101.16  4567.6   98.38  4671.2   96.38  4769.2   97.25  4832.4   95.84
  4942.1   84.43  4987.381.89602    5000   80.93  5002.7   79.28  5025.4   81.86
  5287.3   81.15  5470.6   82.46  5538.2   80.96  5722.4   80.85  6043.7   82.06
  6135.8   80.73  6250.9   82.39  6394.2   81.76  6543.7   85.37  6756.4   82.41
  6836.5   83.94  7009.9   82.06  7049.2   83.55  7077.7   81.88  7141.3   81.72
  7284.8   82.26  7316.2   83.71  7372.8   85.98    7434    91.4  7603.2   95.68
#Mann= 6 ,-1 , 0
  4518.7     .17       0  4942.1     .08       0  4987.3     .06       0
  5025.4     .08       0  6543.7     .15       0  7316.2     .17       0
#XS Ineff= 2 , 0
       0                  6543.7       0   85.37
Permanent Ineff=
       F       F
Bank Sta=4987.3,5025.4
XS Rating Curve= 0 ,0
Exp/Cntr=0.3,0.1

Type RM Length L Ch R = 1 ,2010    ,510,510,510
BEGIN DESCRIPTION:
Crystal Creek 009 4.0
END DESCRIPTION:
XS GIS Cut Line= 4
      3872603.69     10055067.21      3872252.56      10054575.8
      3871915.06      10054570.6      3869531.26      10055400.7
#Sta/Elev= 30
  4291.7   98.54  4515.5    94.5  4680.2   94.68  4717.1      96  4815.3   93.38
  4889.1   88.65  4940.4   81.73  4998.6   78.82  5050.4   81.64  5150.4   82.29
  5210.4   85.07  5452.6   81.17  5491.4    82.5  5600.9   82.69  5664.4   81.18
  5833.8   80.87  6071.5   80.87  6140.9   82.43  6190.5   81.41  6236.2   82.82
  6527.2   80.98  6801.7   83.65  7083.3    83.7  7189.2   85.06  7337.5   82.33
  7499.9   84.21    7563   86.85  7602.2   91.27  7644.5   93.48  7757.4   96.53
#Mann= 7 ,-1 , 0
  4291.7     .17       0  4815.3     .15       0  4889.1     .08       0
  4940.4     .06       0  5050.4     .08       0  5210.4     .15       0
  7499.9     .17       0
#XS Ineff= 2 , 0
       0                  5210.4       0   85.07
Permanent Ineff=
       F       F
Bank Sta=4940.4,5050.4
XS Rating Curve= 0 ,0
Exp/Cntr=0.3,0.1

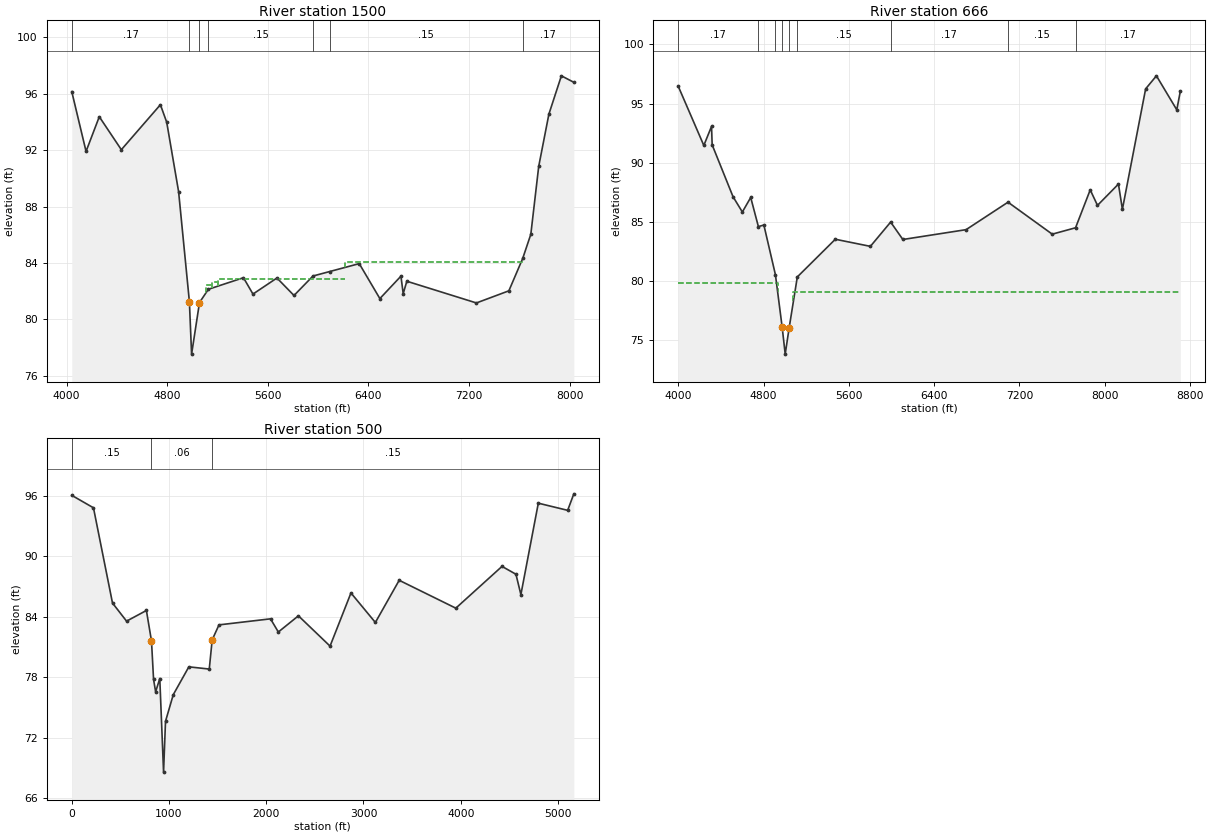
Type RM Length L Ch R = 1 ,1500    ,834,834,834
BEGIN DESCRIPTION:
Crystal Creek 009 3.0
END DESCRIPTION:
XS GIS Cut Line= 3
      3873091.19     10054042.18      3872134.42     10054103.05
      3869354.28      10055316.7
#Sta/Elev= 30
  4041.3   96.16  4154.9   91.92  4260.1   94.38  4435.4   92.04  4746.1   95.23
  4796.2   93.99  4890.7   89.07  4976.5   81.27    4994   77.54  5056.9    81.2
  5127.5   82.14  5406.5   82.96  5482.1    81.8  5672.8   82.94  5808.3    81.7
  5959.1   83.08  6092.9    83.4  6327.1   83.96  6491.1   81.48  6658.7   83.07
  6676.6   81.83  6705.5   82.71  7258.7   81.17  7516.8   82.03    7627   84.33
  7691.4   86.04  7754.2   90.86  7835.3   94.57  7934.4   97.28  8033.5   96.82
#Mann= 7 ,-1 , 0
  4041.3     .17       0  4976.5     .09       0  5056.9     .17       0
  5127.5     .15       0  5959.1     .17       0  6092.9     .15       0
    7627     .17       0
#XS Ineff= 4 ,-1
  5109.2    5156   82.42    5156  5202.8   82.66  5202.8  6210.1   82.88
  6210.1  7631.7   84.07
Permanent Ineff=
       F       F       F       F
Bank Sta=4976.5,5056.9
XS Rating Curve= 0 ,0
Exp/Cntr=0.3,0.1

Type RM Length L Ch R = 1 ,666     ,573,573,573
BEGIN DESCRIPTION:
Crystal Creek 009 1.0
END DESCRIPTION:
XS GIS Cut Line= 3
       3873042.6     10053928.46      3872139.83     10053334.72
      3869021.67      10055191.4
#Sta/Elev= 30
  3999.3   96.46  4239.3   91.46  4311.6   93.07  4317.6   91.51  4513.4   87.13
  4600.8   85.84  4679.1   87.07    4751   84.61  4802.6   84.74  4911.1   80.54
  4974.5   76.09  5002.7   73.84 5039.88 76.0673  5116.4   80.36  5472.7   83.54
  5801.8   82.94  5991.7   84.99  6106.3   83.52  6699.4   84.35  7092.7   86.67
  7507.5   83.97  7726.3   84.51  7863.8   87.71    7932    86.4  8128.6    88.2
  8165.6   86.07  8383.7   96.24  8484.9   97.34  8675.8   94.47  8708.9   96.03
#Mann= 9 ,-1 , 0
  3999.3     .17       0    4751     .15       0  4911.1     .12       0
  4974.5     .09       0 5039.88     .12       0  5116.4     .15       0
  5991.7     .17       0  7092.7     .15       0  7726.3     .17       0
#XS Ineff= 2 , 0
       0  4932.2   79.85  5079.8       0   79.11
Permanent Ineff=
       F       F
Bank Sta=4974.5,5039.88
XS Rating Curve= 0 ,0
Exp/Cntr=0.3,0.1

Type RM Length L Ch R = 1 ,500     ,0,0,0
XS GIS Cut Line= 4
      3873061.39     10053912.51      3872573.95     10053111.14
      3871959.61     10053108.67      3868983.35      10055154.1
#Sta/Elev= 30
       0   96.06   223.2   94.82   418.9   85.36   563.5   83.56   767.6   84.62
   819.9   81.59   841.2   77.77   862.5   76.54   905.2   77.86   944.1   68.56
   964.1   73.61  1044.1   76.26  1204.1   79.02  1414.1    78.8  1444.1    81.7
  1514.1   83.19    2044   83.79  2124.5   82.48    2331   84.09  2656.3   81.08
  2871.4   86.36  3122.4   83.43  3367.4   87.62  3949.9   84.85  4424.9      89
  4568.3   88.22    4619    86.2  4798.3   95.28  5100.1   94.57  5163.7   96.21
#Mann= 3 , 0 , 0
       0     .15       0   819.9     .06       0  1444.1     .15       0
Bank Sta=819.9,1444.1
XS Rating Curve= 0 ,0
Exp/Cntr=0.3,0.1

Chan Stop Cuts=-1
Use User Specified Reach Order=0
Composite Channel Slope=5

--- Crystal Creek 009.g10 (geometry) ---

Geom Title=Existing Conditions
Program Version=4.10

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
River Reach=Crystal Creek 00,Reach-1

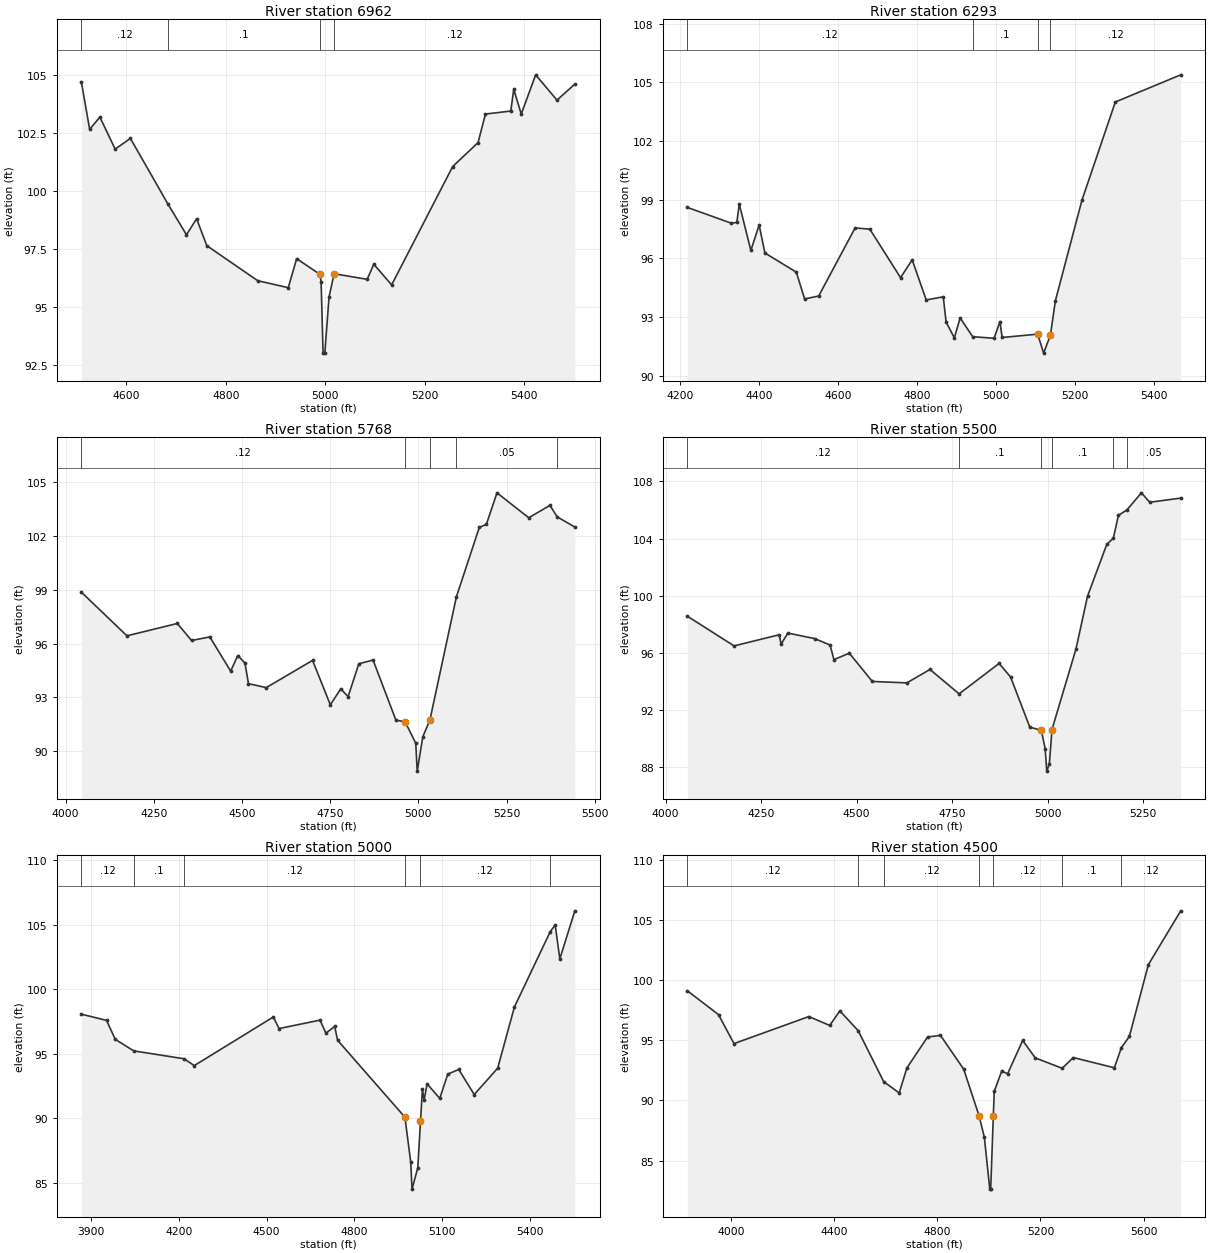
Type RM Length L Ch R = 1 ,6962    ,669,669,669
BEGIN DESCRIPTION:
Crystal Creek 009 14.0
END DESCRIPTION:
XS GIS Cut Line= 3
      3872294.02     10058288.16      3871764.54     10058173.15
      3871392.81     10058426.01
#Sta/Elev= 30
  4510.1  104.67  4526.6  102.65  4547.1  103.18  4577.8   101.8  4608.5  102.26
  4684.2   99.42  4721.1   98.11  4741.5    98.8    4762   97.64  4864.3   96.13
  4925.7   95.83  4942.5   97.08 4989.62    96.4  4991.7   96.06  4995.6   93.01
  4999.1   93.01  5007.6   95.43  5017.8   96.43  5084.2   96.19  5097.5   96.84
  5133.4   95.95  5256.1  101.05    5307  102.08  5321.9  103.31  5372.8  103.44
  5378.8  104.38  5393.8  103.31  5422.8     105  5465.6  103.91  5501.5   104.6
#Mann= 4 ,-1 , 0
  4510.1     .12       0  4684.2      .1       0 4989.62     .07       0
  5017.8     .12       0
Bank Sta=4989.62,5017.8
XS Rating Curve= 0 ,0
Exp/Cntr=0.3,0.1

Type RM Length L Ch R = 1 ,6293    ,525,525,525
BEGIN DESCRIPTION:
Crystal Creek 009 13.0
END DESCRIPTION:
XS GIS Cut Line= 3
      3871990.25      10057339.8      3871354.38     10057804.23
       3871150.5     10058216.34
#Sta/Elev= 30
  4219.4   98.61  4329.7   97.81  4344.4   97.84  4350.6   98.78  4379.9   96.41
  4400.8   97.71  4415.4   96.28  4494.8    95.3  4515.8   93.93  4551.3   94.08
  4643.4   97.56  4680.6    97.5  4758.3   95.02  4787.7   95.93  4823.2   93.88
  4866.3   94.04  4873.4   92.75  4894.3   91.94  4908.9   92.96  4940.7      92
  4994.7   91.92  5009.6   92.77  5015.1   91.96  5104.9   92.13    5120   91.16
  5137.2   92.08  5149.7   93.84    5217   98.99  5301.2     104  5466.6  105.39
#Mann= 4 ,-1 , 0
  4219.4     .12       0  4940.7      .1       0  5104.9     .03       0
  5137.2     .12       0
Bank Sta=5104.9,5137.2
XS Rating Curve= 0 ,0
Exp/Cntr=0.3,0.1

Type RM Length L Ch R = 1 ,5768    ,268,268,268
BEGIN DESCRIPTION:
Crystal Creek 009 12.0
END DESCRIPTION:
XS GIS Cut Line= 3
      3871977.19     10057298.59      3871031.03     10057424.45
      3870587.31     10057442.97
#Sta/Elev= 30
  4044.9   98.86  4173.9   96.43  4316.6   97.12    4357   96.17  4408.7   96.37
  4467.9   94.46  4488.1   95.33  4508.3   94.91  4518.4   93.76  4568.8   93.54
    4700   95.06  4750.4   92.58  4779.9   93.47  4800.8   93.04  4831.1   94.87
  4871.5   95.08  4936.4   91.72  4962.2   91.64  4992.5   90.44  4996.7   88.88
  5012.6    90.8  5032.6   91.73  5107.8   98.61  5172.7  102.48  5192.7  102.65
  5222.8  104.41  5312.8  103.02  5372.9  103.71  5393.5  103.07  5443.5   102.5
#Mann= 5 ,-1 , 0
  4044.9     .12       0  4962.2     .07       0  5032.6     .12       0
  5107.8     .05       0  5393.5     .12       0
Bank Sta=4962.2,5032.6
XS Rating Curve= 0 ,0
Exp/Cntr=0.3,0.1

Type RM Length L Ch R = 1 ,5500    ,500,500,500
BEGIN DESCRIPTION:
Crystal Creek 009 11.0
END DESCRIPTION:
XS GIS Cut Line= 3
      3871979.42     10057249.76      3871041.02     10057157.71
      3870695.75     10057115.87
#Sta/Elev= 30
  4057.1   98.56  4179.2   96.48  4297.3   97.26  4302.3    96.6  4319.9   97.38
  4390.3   96.99  4430.4   96.54  4440.5   95.52  4480.7   95.97    4541   93.99
  4631.4   93.89  4691.7   94.83    4768   93.12  4872.6   95.25  4902.7    94.3
  4952.9   90.79  4983.1   90.57  4993.1   89.29  4997.3   87.71  5004.1   88.21
  5010.9   90.62  5073.7   96.26  5103.9   99.96  5154.3  103.59  5171.6  104.03
  5184.7  105.62  5207.2  106.01  5244.9   107.2  5266.6  106.54  5347.8  106.83
#Mann= 6 ,-1 , 0
  4057.1     .12       0    4768      .1       0  4983.1     .07       0
  5010.9      .1       0  5171.6     .12       0  5207.2     .05       0
Bank Sta=4983.1,5010.9
XS Rating Curve= 0 ,0
Exp/Cntr=0.3,0.1

Type RM Length L Ch R = 1 ,5000    ,500,500,500
BEGIN DESCRIPTION:
Crystal Creek 009 10.0
END DESCRIPTION:
XS GIS Cut Line= 3
       3872383.5     10056761.69      3871250.62     10056739.62
      3870767.89     10057011.05
#Sta/Elev= 30
  3866.9   98.06  3952.6   97.58  3982.6   96.11  4045.5   95.22  4217.5   94.61
  4252.6   94.08  4522.7   97.84  4542.7   96.95  4682.7    97.6  4702.7   96.59
  4732.7   97.11  4742.7   96.04  4972.8   90.09  4992.8    86.6  4997.1   84.52
  5016.8   86.17  5026.1   89.76  5032.7   92.27  5038.4    91.4  5048.6   92.67
    5092   91.54  5119.4   93.42    5157   93.78  5209.7   91.84    5290   93.88
  5347.3   98.62  5469.3  104.43  5486.6  104.97  5502.5  102.34  5553.8  106.06
#Mann= 6 ,-1 , 0
  3866.9     .12       0  4045.5      .1       0  4217.5     .12       0
  4972.8     .07       0  5026.1     .12       0  5469.3     .05       0
Bank Sta=4972.8,5026.1
XS Rating Curve= 0 ,0
Exp/Cntr=0.3,0.1

Type RM Length L Ch R = 1 ,4500    ,474,474,474
BEGIN DESCRIPTION:
Crystal Creek 009 9.0
END DESCRIPTION:
XS GIS Cut Line= 3
      3872218.49     10056271.46      3871050.03     10056345.33
      3870411.84     10056728.73
#Sta/Elev= 30
  3829.2   99.11  3950.1   97.13  4010.2   94.72  4300.8   96.97  4381.9   96.23
    4421   97.44  4492.2    95.8  4591.2   91.56  4651.5   90.62  4681.5    92.7
  4761.7   95.27  4811.8    95.4    4902   92.59  4962.1   88.68  4982.1   86.92
  5003.2   82.62  5006.7   82.62  5016.9   88.71  5020.5   90.75  5049.2   92.42
  5072.5   92.22  5130.9   94.98  5179.8   93.53  5284.3   92.67  5327.5   93.56
  5486.8   92.71    5514   94.38  5545.1   95.32  5618.9  101.29  5744.5  105.76
#Mann= 7 ,-1 , 0
  3829.2     .12       0  4492.2      .1       0  4591.2     .12       0
  4962.1     .07       0  5016.9     .12       0  5284.3      .1       0
    5514     .12       0
Bank Sta=4962.1,5016.9
XS Rating Curve= 0 ,0
Exp/Cntr=0.3,0.1

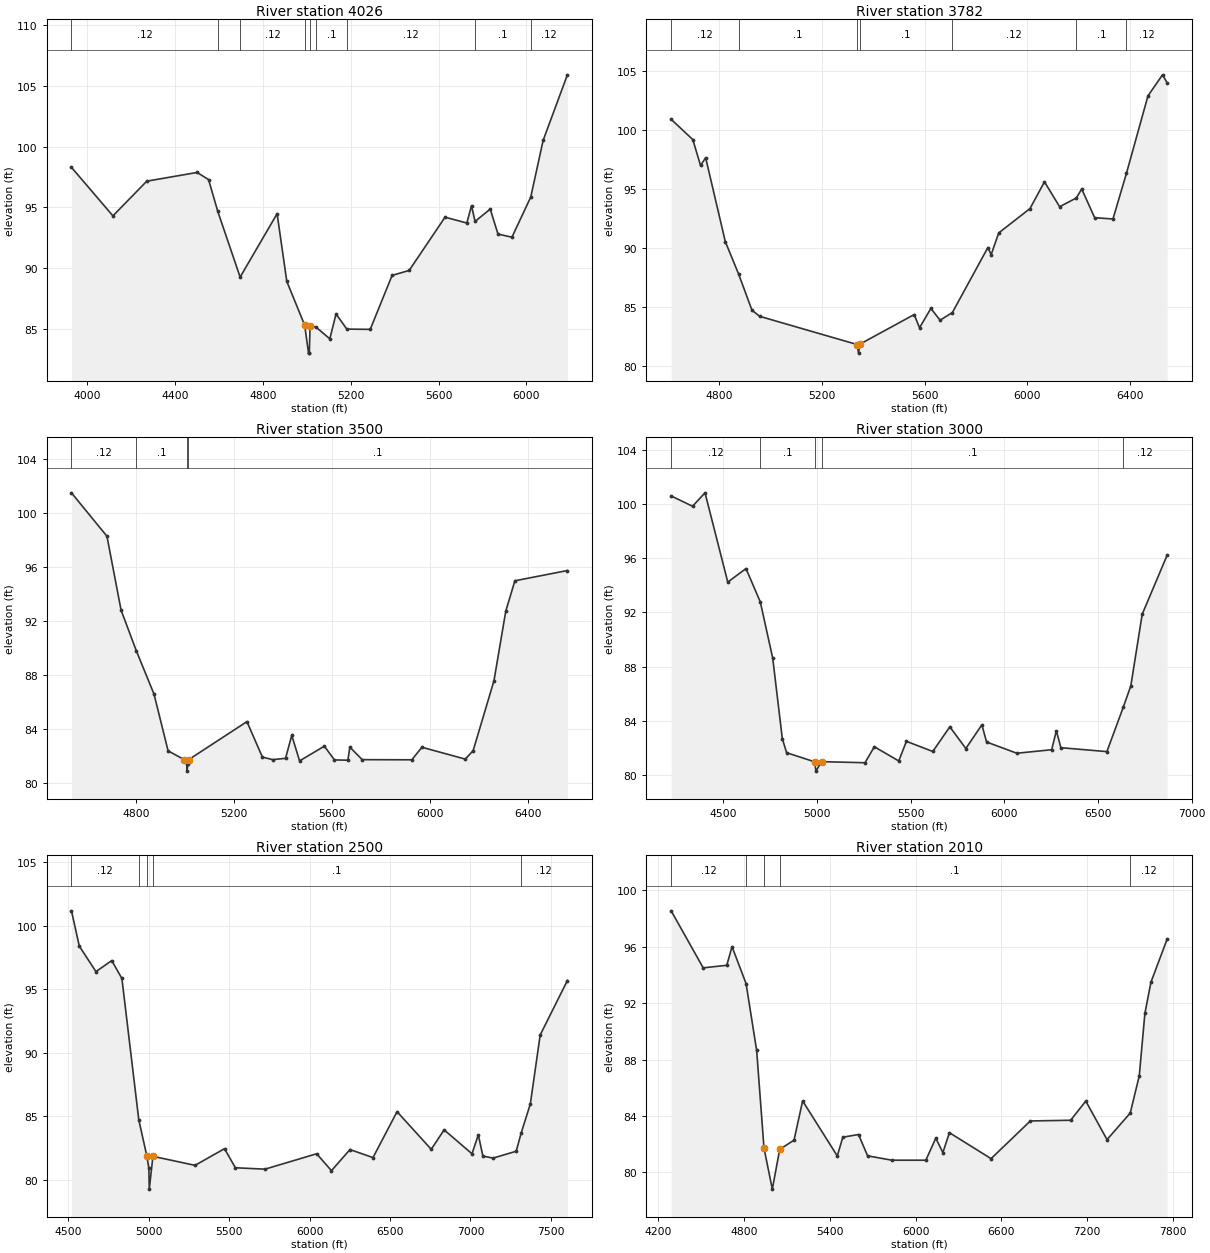
Type RM Length L Ch R = 1 ,4026    ,244,244,244
BEGIN DESCRIPTION:
Mapping XS 31c25574
END DESCRIPTION:
XS GIS Cut Line= 3
      3872206.96     10056217.68      3871092.37     10055894.76
      3870363.22     10056712.46
#Sta/Elev= 30
  3930.1    98.3  4118.7    94.3  4272.7   97.16  4501.8   97.88  4553.8   97.29
  4595.8   94.66  4697.4   89.25  4865.6   94.48  4909.6    88.9  4991.1   85.28
  5008.6   82.98  5012.1   82.98  5015.5   85.24  5042.2   85.13  5105.3   84.16
  5133.7   86.21  5182.9   84.96  5289.2   84.94  5388.7   89.39  5466.4    89.8
  5629.5   94.19  5728.7   93.71  5749.9   95.14  5766.1   93.84  5835.1   94.86
  5870.3    92.8  5933.8   92.54  6019.4   95.85  6075.9  100.53  6186.1  105.93
#Mann= 9 ,-1 , 0
  3930.1     .12       0  4595.8      .1       0  4697.4     .12       0
  4991.1     .03       0  5015.5     .12       0  5042.2      .1       0
  5182.9     .12       0  5766.1      .1       0  6019.4     .12       0
Bank Sta=4991.1,5015.5
XS Rating Curve= 0 ,0
Exp/Cntr=0.3,0.1

Type RM Length L Ch R = 1 ,3782    ,282,282,282
BEGIN DESCRIPTION:
Crystal Creek 009 8.0
END DESCRIPTION:
XS GIS Cut Line= 3
      3871702.04     10055761.48      3870985.89     10055709.39
       3870282.8      10056701.1
#Sta/Elev= 30
  4611.7  100.92  4696.1    99.2  4726.2   97.01  4746.2   97.66  4822.8   90.55
  4874.6   87.81  4926.7   84.74  4956.8   84.22  5336.5   81.83  5342.3    81.1
 5347.82  81.863  5559.2   84.37  5580.1   83.25  5624.4   84.89  5660.1   83.89
  5708.2   84.54  5846.6   90.05  5859.4   89.45  5888.9   91.29  6010.7   93.35
  6067.3   95.62  6126.4   93.51  6191.3   94.25  6212.5   95.01    6263   92.58
  6334.3   92.47  6386.9   96.34  6470.9  102.91  6527.5  104.69  6545.4  104.02
#Mann= 7 ,-1 , 0
  4611.7     .12       0  4874.6      .1       0  5336.5     .03       0
 5347.82      .1       0  5708.2     .12       0  6191.3      .1       0
  6386.9     .12       0
Bank Sta=5336.5,5347.82
XS Rating Curve= 0 ,0
Exp/Cntr=0.3,0.1

Type RM Length L Ch R = 1 ,3500    ,500,500,500
BEGIN DESCRIPTION:
Crystal Creek 009 7.0
END DESCRIPTION:
XS GIS Cut Line= 3
      3871701.09     10055742.54      3871336.99     10055452.51
      3869852.53     10055933.38
#Sta/Elev= 30
  4534.5   101.5  4679.5   98.28  4737.1   92.81  4799.4   89.79  4871.7   86.58
  4929.3   82.37 4996.16  81.715    5006   81.37  5006.2   80.87    5010   81.37
  5013.2   81.72  5251.4   84.54  5314.4   81.91  5356.5   81.72    5409   81.82
  5434.4   83.52  5466.4   81.63  5567.6   82.72  5608.8    81.7  5663.6   81.68
  5671.8   82.65  5722.3   81.72  5924.8   81.71  5966.2   82.64  6143.4   81.76
  6175.4   82.39  6260.5   87.57  6308.7   92.73  6345.9   94.98  6560.4   95.74
#Mann= 4 ,-1 , 0
  4534.5     .12       0  4799.4      .1       0    5006     .03       0
    5010      .1       0
Bank Sta=4996.16,5013.2
XS Rating Curve= 0 ,0
Exp/Cntr=0.3,0.1

Type RM Length L Ch R = 1 ,3000    ,500,500,500
BEGIN DESCRIPTION:
Crystal Creek 009 6.0
END DESCRIPTION:
XS GIS Cut Line= 3
      3872241.48     10055406.54      3871537.58     10055077.52
      3869787.04     10055732.05
#Sta/Elev= 30
    4223  100.59    4337   99.83  4403.6  100.82    4525   94.23  4622.2   95.23
  4698.5   92.77  4764.8   88.62    4816   82.68  4838.9   81.64  4988.4  80.967
  4995.3   80.28  5025.4   80.98  5257.1    80.9    5307   82.08  5437.4   81.03
    5478   82.48  5618.8   81.73  5709.7   83.55  5795.2   81.95  5880.8    83.7
  5905.7   82.43  6067.3    81.6  6253.2   81.86  6278.1   83.26  6302.2   82.01
  6547.7   81.72  6635.7   85.02  6675.5   86.58  6736.1   91.86  6868.9   96.21
#Mann= 5 ,-1 , 0
    4223     .12       0  4698.5      .1       0  4988.4     .03       0
  5025.4      .1       0  6635.7     .12       0
Bank Sta=4988.4,5025.4
XS Rating Curve= 0 ,0
Exp/Cntr=0.3,0.1

Type RM Length L Ch R = 1 ,2500    ,490,490,490
BEGIN DESCRIPTION:
Crystal Creek 009 5.0
END DESCRIPTION:
XS GIS Cut Line= 4
      3872373.85     10055167.82      3871935.06     10054970.04
      3871644.66     10054699.07      3869638.27     10055616.06
#Sta/Elev= 30
  4518.7  101.16  4567.6   98.38  4671.2   96.38  4769.2   97.25  4832.4   95.84
  4937.4   84.73  4987.3  81.896    5000   80.93  5002.7   79.28  5025.4   81.86
  5287.3   81.15  5470.6   82.46  5538.2   80.96  5722.4   80.85  6043.7   82.06
  6135.8   80.73  6250.9   82.39  6394.2   81.76  6543.7   85.37  6756.4   82.41
  6836.5   83.94  7009.9   82.06  7049.2   83.55  7077.7   81.88  7141.3   81.72
  7284.8   82.26  7316.2   83.71  7372.8   85.98    7434    91.4  7603.2   95.68
#Mann= 5 ,-1 , 0
  4518.7     .12       0  4937.4      .1       0  4987.3     .03       0
  5025.4      .1       0  7316.2     .12       0
Bank Sta=4987.3,5025.4
XS Rating Curve= 0 ,0
Exp/Cntr=0.3,0.1

Type RM Length L Ch R = 1 ,2010    ,510,510,510
BEGIN DESCRIPTION:
Crystal Creek 009 4.0
END DESCRIPTION:
XS GIS Cut Line= 4
      3872603.69     10055067.21      3872252.56      10054575.8
      3871915.06      10054570.6      3869531.26      10055400.7
#Sta/Elev= 30
  4291.7   98.54  4515.5    94.5  4680.2   94.68  4717.1      96  4815.3   93.38
  4889.1   88.65  4940.4   81.73  4998.6   78.82  5050.4   81.64  5150.4   82.29
  5210.4   85.07  5452.6   81.17  5491.4    82.5  5600.9   82.69  5664.4   81.18
  5833.8   80.87  6071.5   80.87  6140.9   82.43  6190.5   81.41  6236.2   82.82
  6527.2   80.98  6801.7   83.65  7083.3    83.7  7189.2   85.06  7337.5   82.33
  7499.9   84.21    7563   86.85  7602.2   91.27  7644.5   93.48  7757.4   96.53
#Mann= 5 ,-1 , 0
  4291.7     .12       0  4815.3      .1       0  4940.4     .03       0
  5050.4      .1       0  7499.9     .12       0
Bank Sta=4940.4,5050.4
XS Rating Curve= 0 ,0
Exp/Cntr=0.3,0.1

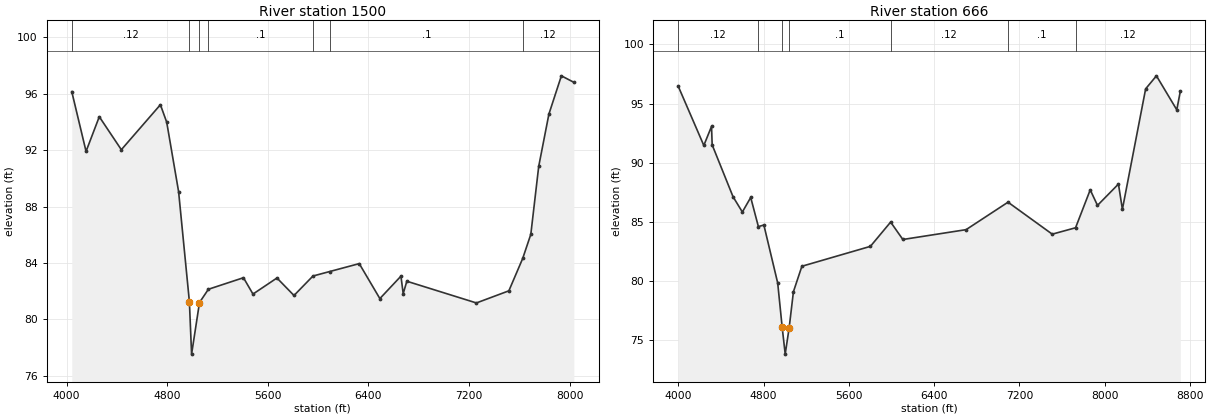
Type RM Length L Ch R = 1 ,1500    ,834,834,834
BEGIN DESCRIPTION:
Crystal Creek 009 3.0
END DESCRIPTION:
XS GIS Cut Line= 3
      3873091.19     10054042.18      3872134.42     10054103.05
      3869354.28      10055316.7
#Sta/Elev= 30
  4041.3   96.16  4154.9   91.92  4260.1   94.38  4435.4   92.04  4746.1   95.23
  4796.2   93.99  4890.7   89.07  4976.5   81.27    4994   77.54  5056.9    81.2
  5127.5   82.14  5406.5   82.96  5482.1    81.8  5672.8   82.94  5808.3    81.7
  5959.1   83.08  6092.9    83.4  6327.1   83.96  6491.1   81.48  6658.7   83.07
  6676.6   81.83  6705.5   82.71  7258.7   81.17  7516.8   82.03    7627   84.33
  7691.4   86.04  7754.2   90.86  7835.3   94.57  7934.4   97.28  8033.5   96.82
#Mann= 7 ,-1 , 0
  4041.3     .12       0  4976.5     .07       0  5056.9     .12       0
  5127.5      .1       0  5959.1     .12       0  6092.9      .1       0
    7627     .12       0
Bank Sta=4976.5,5056.9
XS Rating Curve= 0 ,0
Exp/Cntr=0.3,0.1

Type RM Length L Ch R = 1 ,666     ,0,0,0
BEGIN DESCRIPTION:
Crystal Creek 009 1.0
END DESCRIPTION:
XS GIS Cut Line= 3
       3873042.6     10053928.46      3872139.83     10053334.72
      3869021.67      10055191.4
#Sta/Elev= 30
  3999.3   96.46  4239.3   91.46  4311.6   93.07  4317.6   91.51  4513.4   87.13
  4600.8   85.84  4679.1   87.07    4751   84.61  4802.6   84.74  4932.2   79.85
  4974.5   76.09  5002.7   73.84 5039.88  76.067  5079.8   79.11  5159.2   81.26
  5801.8   82.94  5991.7   84.99  6106.3   83.52  6699.4   84.35  7092.7   86.67
  7507.5   83.97  7726.3   84.51  7863.8   87.71    7932    86.4  8128.6    88.2
  8165.6   86.07  8383.7   96.24  8484.9   97.34  8675.8   94.47  8708.9   96.03
#Mann= 7 ,-1 , 0
  3999.3     .12       0    4751      .1       0  4974.5     .07       0
 5039.88      .1       0  5991.7     .12       0  7092.7      .1       0
  7726.3     .12       0
Bank Sta=4974.5,5039.88
XS Rating Curve= 0 ,0
Exp/Cntr=0.3,0.1