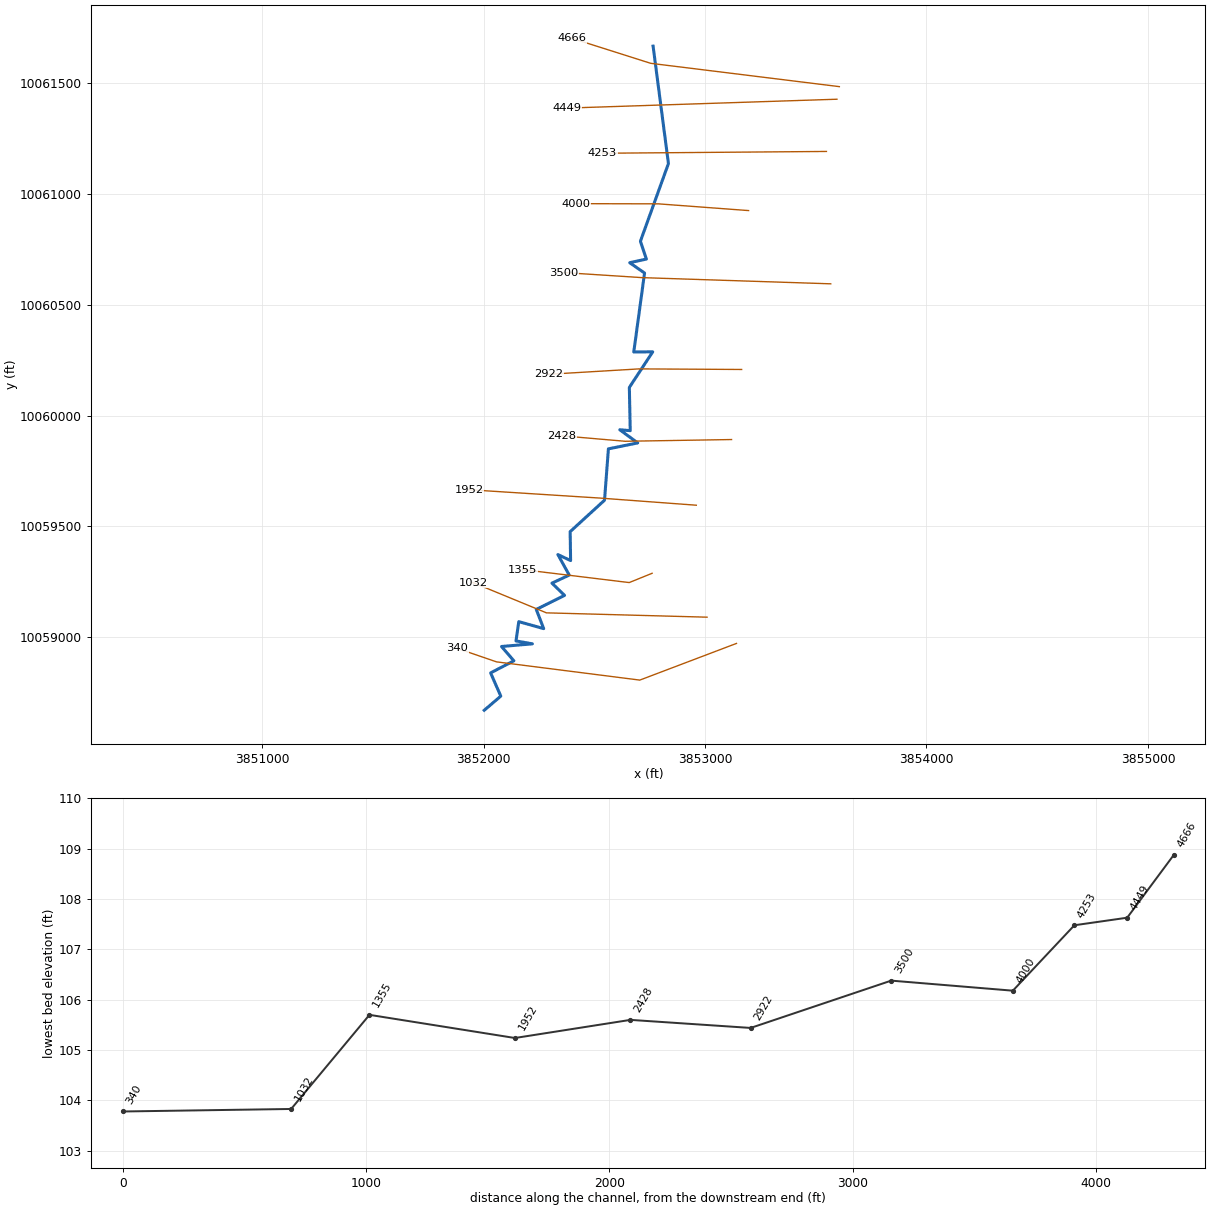
--- Crystal Creek 010.prj (project) ---

Proj Title=Crystal Creek 010 Base Level Engineering
Current Plan=p01
Default Exp/Contr=0.3,0.1
English Units
Geom File=g01
Flow File=f01
Flow File=f02
Plan File=p01
Y Axis Title=Elevation
X Axis Title(PF)=Main Channel Distance
X Axis Title(XS)=Station
BEGIN DESCRIPTION:
Crystal Creek 010
END DESCRIPTION:
DSS Export Rating Curves= 0
DSS Export Rating Curve Sorted= 0
DSS Export Volume Flow Curves= 0
DXF OffsetX= 0
DXF OffsetY= 0
DXF ScaleX= 1
DXF ScaleY= 10

--- Crystal Creek 010.p01 (plan) ---

Plan Title=Multiple Run
Short Identifier=Multiple
Geom File=g01
Flow File=f01
Subcritical Flow
K Sum by GR= 0
Std Step Tol= 0.01
Critical Tol= 0.01
Num of Std Step Trials= 20
Max Error Tol= 0.3
Flow Tol Ratio= 0.001
Split Flow NTrial= 30
Split Flow Tol= 0.02
Split Flow Ratio= 0.02
Log Output Level= 0
Friction Slope Method= 1
Unsteady Friction Slope Method= 2
Unsteady Bridges Friction Slope Method= 1
Parabolic Critical Depth
Global Vel Dist=  1 , 1 , 1
Global Log Level= 0
CheckData=True
Encroach Param= -1, 0, 0, 0
BEGIN DESCRIPTION:
Multiple Run
END DESCRIPTION:

--- Crystal Creek 010.f01 (steady flow) ---

Flow Title=Multiple
Program Version=4.10
Number of Profiles= 7
Profile Names=10-year,25-year,50-year,1pct_min,100-year,1pct_plu,500-year
River Rch & RM=Crystal Creek 01,Reach-1         ,4666
     256     317     404     169     511    1543     843
Boundary for River Rch & Prof#=Crystal Creek 01,Reach-1         , 1
Up Type= 0
Dn Type= 3
Dn Slope=0.005
Boundary for River Rch & Prof#=Crystal Creek 01,Reach-1         , 2
Up Type= 0
Dn Type= 3
Dn Slope=0.005
Boundary for River Rch & Prof#=Crystal Creek 01,Reach-1         , 3
Up Type= 0
Dn Type= 3
Dn Slope=0.005
Boundary for River Rch & Prof#=Crystal Creek 01,Reach-1         , 4
Up Type= 0
Dn Type= 3
Dn Slope=0.005
Boundary for River Rch & Prof#=Crystal Creek 01,Reach-1         , 5
Up Type= 0
Dn Type= 3
Dn Slope=0.005
Boundary for River Rch & Prof#=Crystal Creek 01,Reach-1         , 6
Up Type= 0
Dn Type= 3
Dn Slope=0.005
Boundary for River Rch & Prof#=Crystal Creek 01,Reach-1         , 7
Up Type= 0
Dn Type= 3
Dn Slope=0.005
DSS Import GetInterval= 0
DSS Import GetPeak= 0
DSS Import FillOption= 0

--- Crystal Creek 010.f02 (steady flow) ---

Flow Title=Orig_BLE_Flow
Program Version=4.10
Number of Profiles= 7
Profile Names=10-year,25-year,50-year,1pct_min,100-year,1pct_plu,500-year
River Rch & RM=Crystal Creek 01,Reach-1         ,4666
     256     311     351     130     393    1187     490
Boundary for River Rch & Prof#=Crystal Creek 01,Reach-1         , 1
Up Type= 0
Dn Type= 3
Dn Slope=0.005
Boundary for River Rch & Prof#=Crystal Creek 01,Reach-1         , 2
Up Type= 0
Dn Type= 3
Dn Slope=0.005
Boundary for River Rch & Prof#=Crystal Creek 01,Reach-1         , 3
Up Type= 0
Dn Type= 3
Dn Slope=0.005
Boundary for River Rch & Prof#=Crystal Creek 01,Reach-1         , 4
Up Type= 0
Dn Type= 3
Dn Slope=0.005
Boundary for River Rch & Prof#=Crystal Creek 01,Reach-1         , 5
Up Type= 0
Dn Type= 3
Dn Slope=0.005
Boundary for River Rch & Prof#=Crystal Creek 01,Reach-1         , 6
Up Type= 0
Dn Type= 3
Dn Slope=0.005
Boundary for River Rch & Prof#=Crystal Creek 01,Reach-1         , 7
Up Type= 0
Dn Type= 3
Dn Slope=0.005
DSS Import GetInterval= 0
DSS Import GetPeak= 0
DSS Import FillOption= 0

--- Crystal Creek 010.g01 (geometry) ---

Geom Title=Existing Conditions
Program Version=4.10

River Reach=Crystal Creek 01,Reach-1
Reach XY= 30
      3852765.46     10061667.71      3852834.73      10061137.5
      3852708.24     10060786.86      3852735.14     10060706.31
      3852659.59     10060689.98      3852726.88     10060643.35
      3852678.24     10060286.86      3852763.79     10060287.58
      3852658.24     10060126.86      3852662.21     10059931.56
      3852615.02     10059935.67      3852696.07     10059876.16
      3852563.72     10059849.48       3852546.1     10059617.47
      3852390.98      10059475.5      3852392.99     10059344.93
      3852335.59     10059372.05      3852386.77     10059279.36
      3852308.63     10059243.02      3852365.63     10059187.89
      3852237.92      10059124.3      3852271.53     10059037.61
      3852159.03     10059069.27       3852146.4     10058982.12
      3852220.62     10058968.98      3852080.86     10058956.93
      3852136.76     10058892.42      3852031.84     10058837.72
       3852077.7     10058732.83      3852003.11     10058669.07

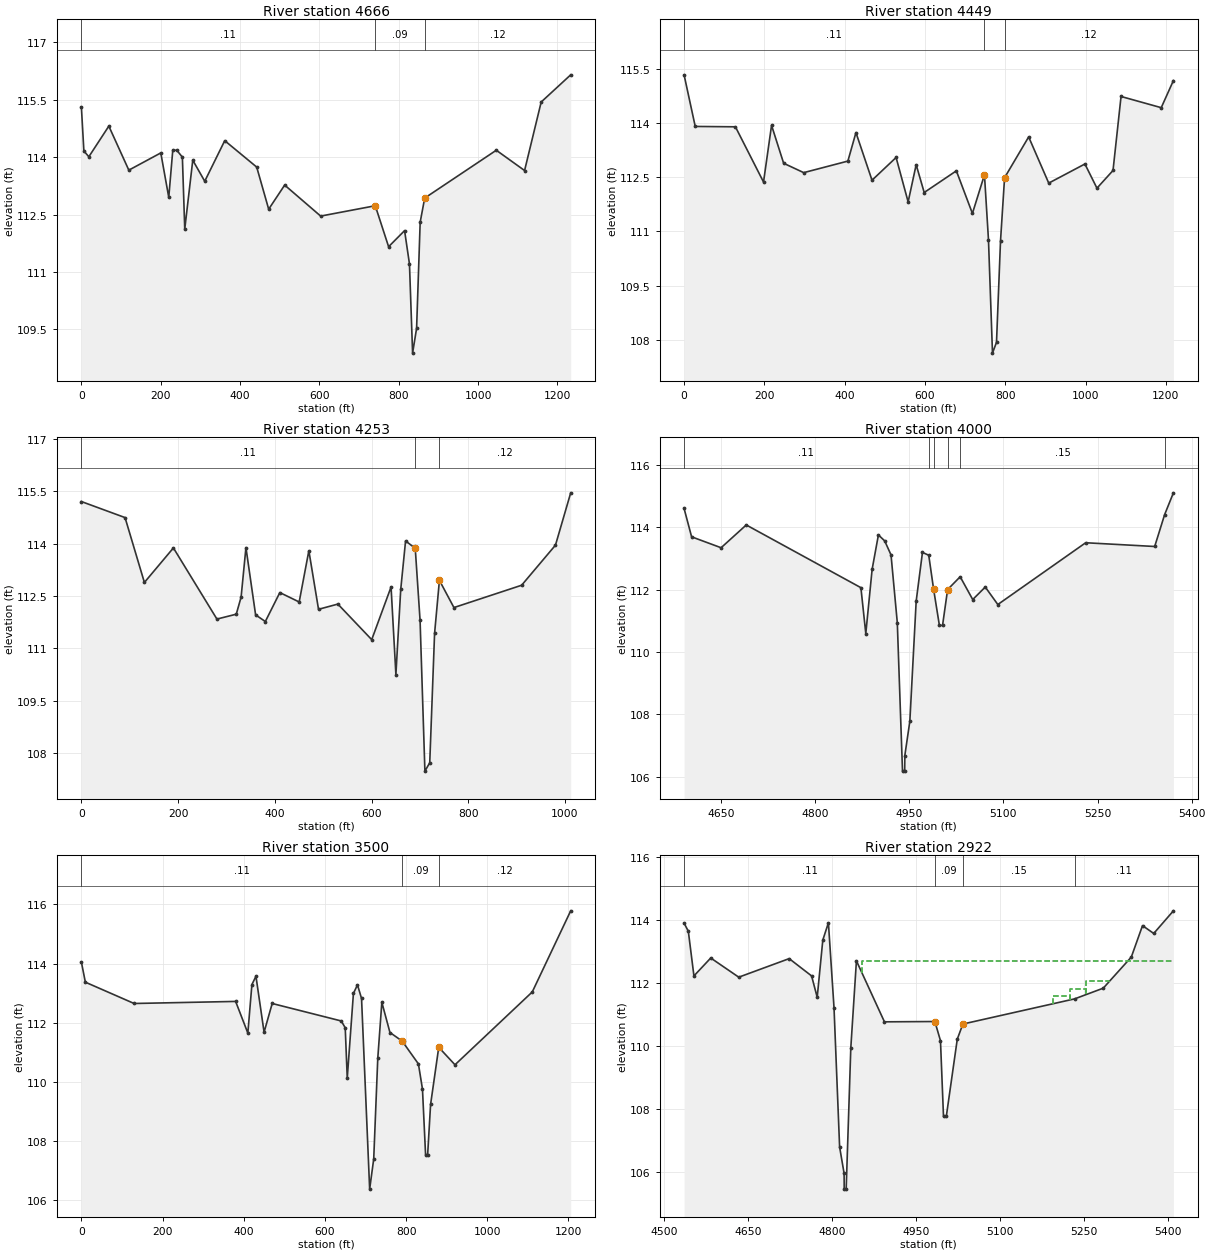
Type RM Length L Ch R = 1 ,4666    ,192,192,192
XS GIS Cut Line= 3
      3853606.53     10061484.97      3852754.86     10061590.24
        3852397.     10061703.74
#Sta/Elev= 30
       0  115.31     6.3  114.16    18.8  114.01    69.2  114.81   119.6  113.66
   200.2  114.11   220.3  112.95   230.4  114.18   240.5  114.18   254.6     114
   260.6  112.12   280.8  113.92     311  113.37   361.4  114.43     442  113.74
   472.2  112.64   512.5  113.27   603.2  112.46   740.9  112.73   774.5  111.66
   814.8  112.08   827.1  111.21     835  108.88   845.1  109.53   854.1   112.3
   865.5  112.93    1046  114.18  1117.3  113.65  1159.2  115.44  1233.6  116.15
#Mann= 3 , 0 , 0
       0     .11       0   740.9     .09       0   865.5     .12       0
Bank Sta=740.9,865.5
XS Rating Curve= 0 ,0
Exp/Cntr=0.3,0.1

Type RM Length L Ch R = 1 ,4449    ,217,217,217
XS GIS Cut Line= 2
      3853595.68     10061428.14      3852377.58      10061388.1
#Sta/Elev= 30
       0  115.34    27.8  113.91   127.9   113.9   197.9  112.37   217.9  113.94
     248  112.89     298  112.63     408  112.95   428.1  113.74   468.1  112.42
   528.1  113.05   558.1  111.82   578.1  112.85   598.1  112.08   678.2  112.68
   718.2   111.5   748.2  112.57   758.2  110.77   768.2  107.63   778.2  107.93
   788.2  110.74   798.3  112.49   858.3  113.62   908.3  112.34   998.4  112.87
  1028.4   112.2  1068.4  112.69  1088.4  114.74  1188.5  114.43  1218.8  115.18
#Mann= 3 , 0 , 0
       0     .11       0   748.2     .09       0   798.3     .12       0
Bank Sta=748.2,798.3
XS Rating Curve= 0 ,0
Exp/Cntr=0.3,0.1

Type RM Length L Ch R = 1 ,4253    ,253,253,253
XS GIS Cut Line= 2
      3853548.19     10061192.33      3852536.32     10061184.21
#Sta/Elev= 30
       0  115.21    90.3  114.75   130.3  112.89   190.3  113.88   280.3  111.84
   320.3  111.98   330.3  112.47   340.3  113.89   360.3  111.96   380.4  111.77
   410.4   112.6   450.4  112.33   470.4   113.8   490.4  112.12   530.4  112.27
   600.4  111.25   640.4  112.76   650.4  110.25   660.4  112.69   670.4  114.08
   690.4  113.87   700.4   111.8   710.4  107.48   720.4  107.72   730.4  111.43
   740.4  112.95   770.4  112.17   910.4  112.81   980.4  113.96  1011.9  115.46
#Mann= 3 , 0 , 0
       0     .11       0   690.4     .09       0   740.4     .12       0
Bank Sta=690.4,740.4
XS Rating Curve= 0 ,0
Exp/Cntr=0.3,0.1

Type RM Length L Ch R = 1 ,4000    ,500,500,500
BEGIN DESCRIPTION:
Crystal Creek 010 8.0
END DESCRIPTION:
XS GIS Cut Line= 3
      3853196.69     10060925.31      3852788.93     10060955.73
      3852418.03     10060956.56
#Sta/Elev= 30
  4591.1   114.6  4603.1  113.69  4650.1  113.34  4690.2  114.07  4872.9  112.06
  4880.7  110.59  4890.8  112.65  4900.8  113.75  4910.8  113.56  4920.9  113.11
  4930.9  110.94  4939.2  106.18  4942.7  106.18  4942.9  106.68  4950.9  107.78
    4961  111.63    4971  113.19    4981   113.1 4988.77  112.01    4998  110.85
    5003  110.85  5011.1     112  5031.1  112.41  5051.1  111.68  5071.1  112.08
  5091.1  111.52  5231.1   113.5  5341.1  113.38  5356.9   114.4  5370.9   115.1
#Mann= 6 ,-1 , 0
  4591.1     .11       0    4981     .12       0 4988.77     .09       0
  5011.1     .12       0  5031.1     .15       0  5356.9     .11       0
#XS Ineff= 2 , 0
       0    4971  113.19  5031.1       0  112.41
Permanent Ineff=
       T       F
Bank Sta=4988.77,5011.1
XS Rating Curve= 0 ,0
Exp/Cntr=0.3,0.1

Type RM Length L Ch R = 1 ,3500    ,578,578,578
XS GIS Cut Line= 3
      3853567.69     10060594.62      3852717.49     10060622.48
      3852363.36     10060645.36
#Sta/Elev= 30
       0  114.05     9.8  113.37   129.9  112.65     380  112.72   410.1  111.65
   420.1  113.29   430.1  113.57   450.1  111.68   470.1  112.65   640.2  112.06
     650  111.83     655  110.13   670.2  112.99   680.2  113.28   690.2  112.82
   710.2  106.38   720.2   107.4   730.2   110.8   740.2  112.69   760.2  111.67
   790.3  111.38   830.3  110.61   840.3  109.76     848  107.53     853  107.53
   860.3  109.24   880.4  111.17   920.4  110.58  1110.8  113.04  1205.5  115.78
#Mann= 3 , 0 , 0
       0     .11       0   790.3     .09       0   880.4     .12       0
Bank Sta=790.3,880.4
XS Rating Curve= 0 ,0
Exp/Cntr=0.3,0.1

Type RM Length L Ch R = 1 ,2922    ,494,494,494
BEGIN DESCRIPTION:
Crystal Creek 010 6.0
END DESCRIPTION:
XS GIS Cut Line= 3
       3853165.4     10060207.86      3852701.91     10060210.47
      3852292.84     10060186.07
#Sta/Elev= 30
  4535.8   113.9  4543.4  113.64  4553.4  112.22  4583.4  112.79  4633.4  112.18
  4723.4  112.77  4763.4  112.22  4773.4  111.54  4783.4  113.36  4793.4  113.91
  4803.4  111.21  4813.4  106.78  4821.4  105.94  4821.6  105.44  4825.1  105.44
  4833.4  109.94  4843.4   112.7  4893.4  110.76  4983.4  110.77  4993.4  110.16
  4998.8  107.75  5003.8  107.75  5023.4  110.21  5033.4  110.69  5232.8  111.49
  5283.9  111.83    5334  112.82    5354  113.82    5374  113.57  5409.1  114.29
#Mann= 4 ,-1 , 0
  4535.8     .11       0  4983.4     .09       0  5033.4     .15       0
  5232.8     .11       0
#XS Ineff= 5 ,-1
  4853.4  4793.4  112.71  5193.7  5223.8  111.59  5223.8  5253.8   111.8
  5253.8  5293.9  112.05  4793.4  4535.8  113.91
Permanent Ineff=
       F       F       F       F       F
Bank Sta=4983.4,5033.4
XS Rating Curve= 0 ,0
Exp/Cntr=0.3,0.1

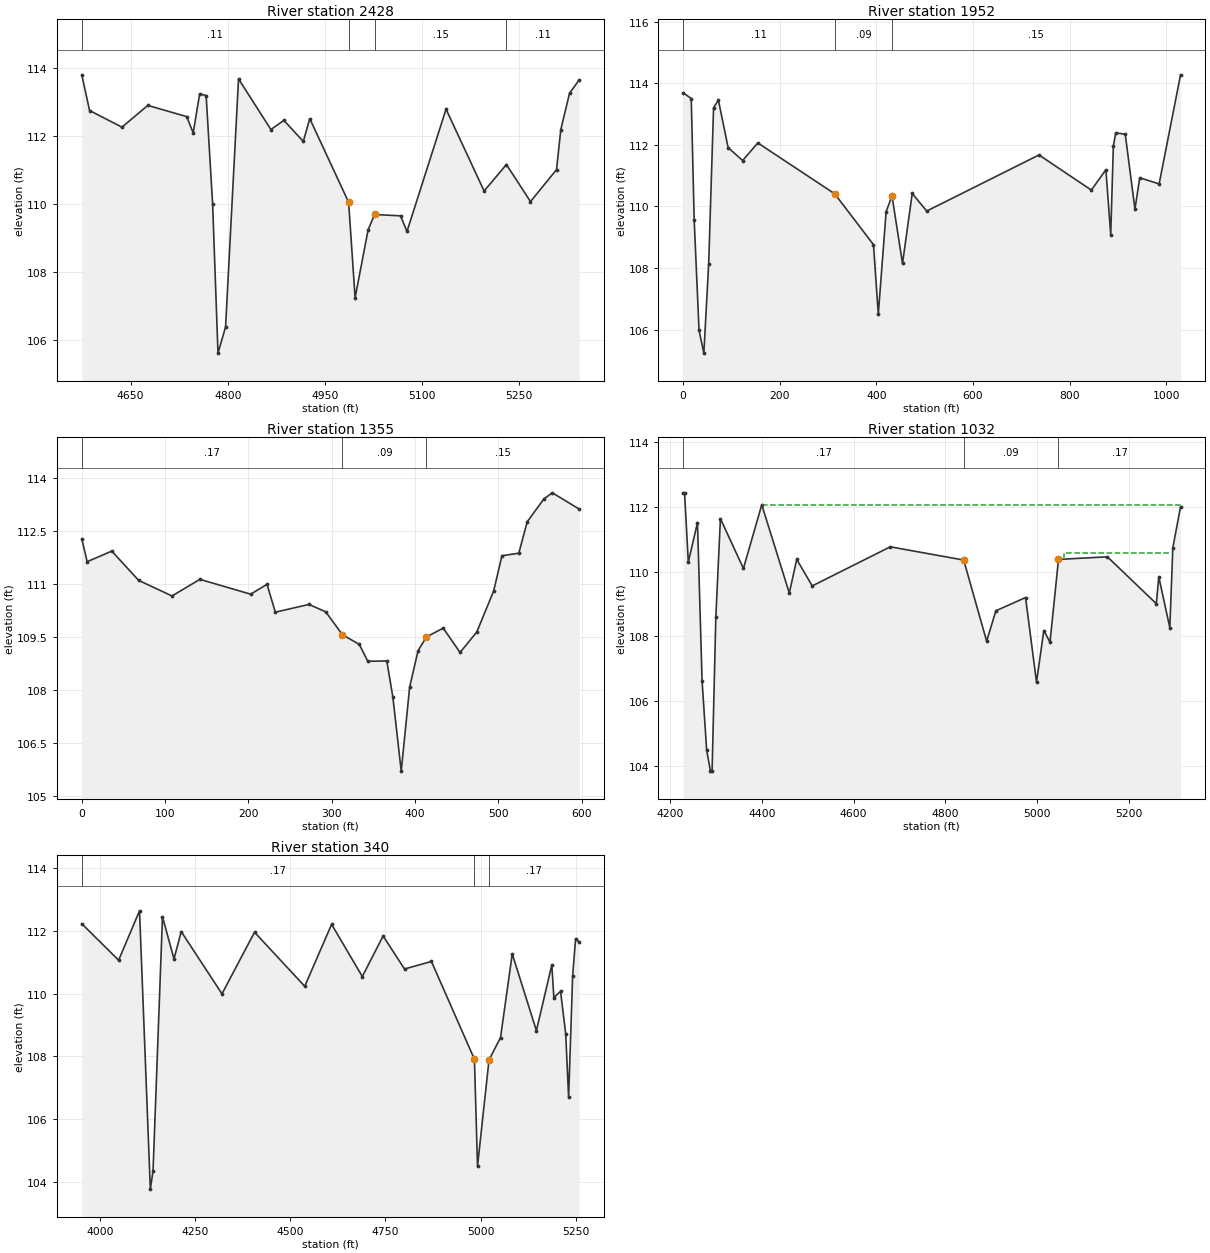
Type RM Length L Ch R = 1 ,2428    ,475,475,475
BEGIN DESCRIPTION:
Crystal Creek 010 5.0
END DESCRIPTION:
XS GIS Cut Line= 3
      3853119.84     10059891.46      3852639.41     10059883.64
      3852352.97     10059908.38
#Sta/Elev= 30
  4574.6  113.79  4586.6  112.74  4636.6  112.25  4676.6  112.89  4736.6  112.56
  4746.6  112.08  4756.6  113.23  4766.6  113.18  4776.6  109.99  4784.9   105.6
  4796.6  106.37  4816.6  113.67  4866.6  112.18  4886.6  112.45  4916.6  111.83
  4926.6   112.5  4986.6  110.04  4996.6  107.23  5016.7  109.23  5026.7  109.68
  5066.7  109.64  5076.7  109.18    5137  112.78  5195.8  110.37  5230.2  111.15
  5267.4  110.06  5307.6     111  5314.2  112.18  5327.7  113.25  5342.6  113.64
#Mann= 4 ,-1 , 0
  4574.6     .11       0  4986.6     .09       0  5026.7     .15       0
  5230.2     .11       0
#XS Ineff= 2 , 0
       0  4926.6   112.5    5137       0  112.78
Permanent Ineff=
       F       F
Bank Sta=4986.6,5026.7
XS Rating Curve= 0 ,0
Exp/Cntr=0.3,0.1

Type RM Length L Ch R = 1 ,1952    ,598,598,598
XS GIS Cut Line= 3
      3852960.65      10059594.9      3852526.13     10059627.13
      3851933.68     10059664.89
#Sta/Elev= 30
       0  113.69    16.8   113.5    22.9  109.56    32.9  105.98    42.9  105.24
    52.9  108.14      63   113.2      73  113.45    93.1  111.91   123.1  111.49
   154.6  112.06   313.7  110.41   393.9  108.76   403.9   106.5   420.1  109.83
   432.3  110.34     454  108.15   474.1  110.42   504.1  109.85   736.5  111.67
   844.8  110.53   874.9  111.19   884.9  109.08   890.3  111.95   895.3  112.39
     915  112.34     935  109.91     945  110.93   985.1  110.73  1029.4  114.27
#Mann= 3 , 0 , 0
       0     .11       0   313.7     .09       0   432.3     .15       0
Bank Sta=313.7,432.3
XS Rating Curve= 0 ,0
Exp/Cntr=0.3,0.1

Type RM Length L Ch R = 1 ,1355    ,322,322,322
XS GIS Cut Line= 3
      3852761.13     10059287.57      3852657.64     10059245.62
      3852175.86     10059304.22
#Sta/Elev= 30
       0  112.27     6.5  111.63      36  111.93    68.3   111.1   108.3  110.66
   141.7  111.13   202.7  110.71   222.3  110.99   232.3   110.2   272.6  110.42
   292.8  110.21   312.9  109.56   333.1  109.29   343.2  108.81   366.1  108.82
   373.4  107.79   383.4   105.7   393.5  108.08   403.6  109.11   413.7   109.5
   433.8  109.75     454  109.06   474.1  109.64   494.3   110.8   504.3   111.8
   524.5  111.87   534.6  112.76   554.7  113.41   564.8  113.58     597  113.12
#Mann= 3 , 0 , 0
       0     .17       0   312.9     .09       0   413.7     .15       0
Bank Sta=312.9,413.7
XS Rating Curve= 0 ,0
Exp/Cntr=0.3,0.1

Type RM Length L Ch R = 1 ,1032    ,692,692,692
BEGIN DESCRIPTION:
Crystal Creek 010 2.0
END DESCRIPTION:
XS GIS Cut Line= 3
      3853009.16     10059089.37      3852283.94      10059108.9
      3851952.34     10059245.45
#Sta/Elev= 30
  4228.3  112.44  4231.4  112.44  4239.6   110.3  4259.6  111.52  4269.6  106.62
  4279.6  104.48  4287.9  103.83  4291.4  103.83  4299.6   108.6  4309.6  111.64
  4359.7   110.1  4399.7  112.07  4459.7  109.34  4475.9  110.38  4509.7  109.56
  4679.8  110.77  4839.8  110.36  4889.8  107.85  4909.9  108.79  4974.6   109.2
  4998.5  106.58  5014.4  108.18  5027.9  107.82  5046.4  110.38    5153  110.46
  5259.6  109.01    5265  109.84    5289  108.27  5295.6  110.74  5312.4  112.01
#Mann= 3 , 0 , 0
  4228.3     .17       0  4839.8     .09       0  5046.4     .17       0
#XS Ineff= 5 ,-1
  5057.7  5295.6  110.59  4839.8  4749.8  110.36  4749.8  4679.8  110.47
  4679.8  4419.7  110.77  4399.7  4231.4  112.07
Permanent Ineff=
       F       F       F       F       F
Bank Sta=4839.8,5046.4
XS Rating Curve= 0 ,0
Exp/Cntr=0.3,0.1

Type RM Length L Ch R = 1 ,340     ,0,0,0
BEGIN DESCRIPTION:
Crystal Creek 010 1.0
END DESCRIPTION:
XS GIS Cut Line= 4
      3853141.98     10058970.87      3852705.45     10058805.26
      3852058.68     10058887.55      3851881.58     10058948.31
#Sta/Elev= 30
  3952.9  112.22  4049.6  111.06  4104.5  112.63  4132.9  103.78    4140  104.36
  4164.8  112.44    4195   111.1    4214  111.97    4321  109.99  4406.5  111.95
  4538.3  110.23  4608.9   112.2  4689.5  110.54  4744.1  111.83  4800.4  110.78
    4871  111.02  4983.9  107.91    4992  104.51  5022.2  107.89  5052.4   108.6
  5083.2  111.26  5146.6  108.82  5187.1  110.91  5192.4  109.87  5210.1  110.07
  5223.6  108.71  5231.2   106.7  5241.8  110.57  5249.6  111.74    5259  111.64
#Mann= 3 , 0 , 0
  3952.9     .17       0  4983.9     .09       0  5022.2     .17       0
#XS Ineff= 2 , 0
       0    4871  111.02  5083.2       0  111.26
Permanent Ineff=
       T       T
Bank Sta=4983.9,5022.2
XS Rating Curve= 0 ,0
Exp/Cntr=0.3,0.1

Chan Stop Cuts=-1
Use User Specified Reach Order=0
Composite Channel Slope=5

--- Crystal Creek 010.g10 (geometry) ---

Geom Title=Existing Conditions
Program Version=4.10

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
River Reach=Crystal Creek 01,Reach-1

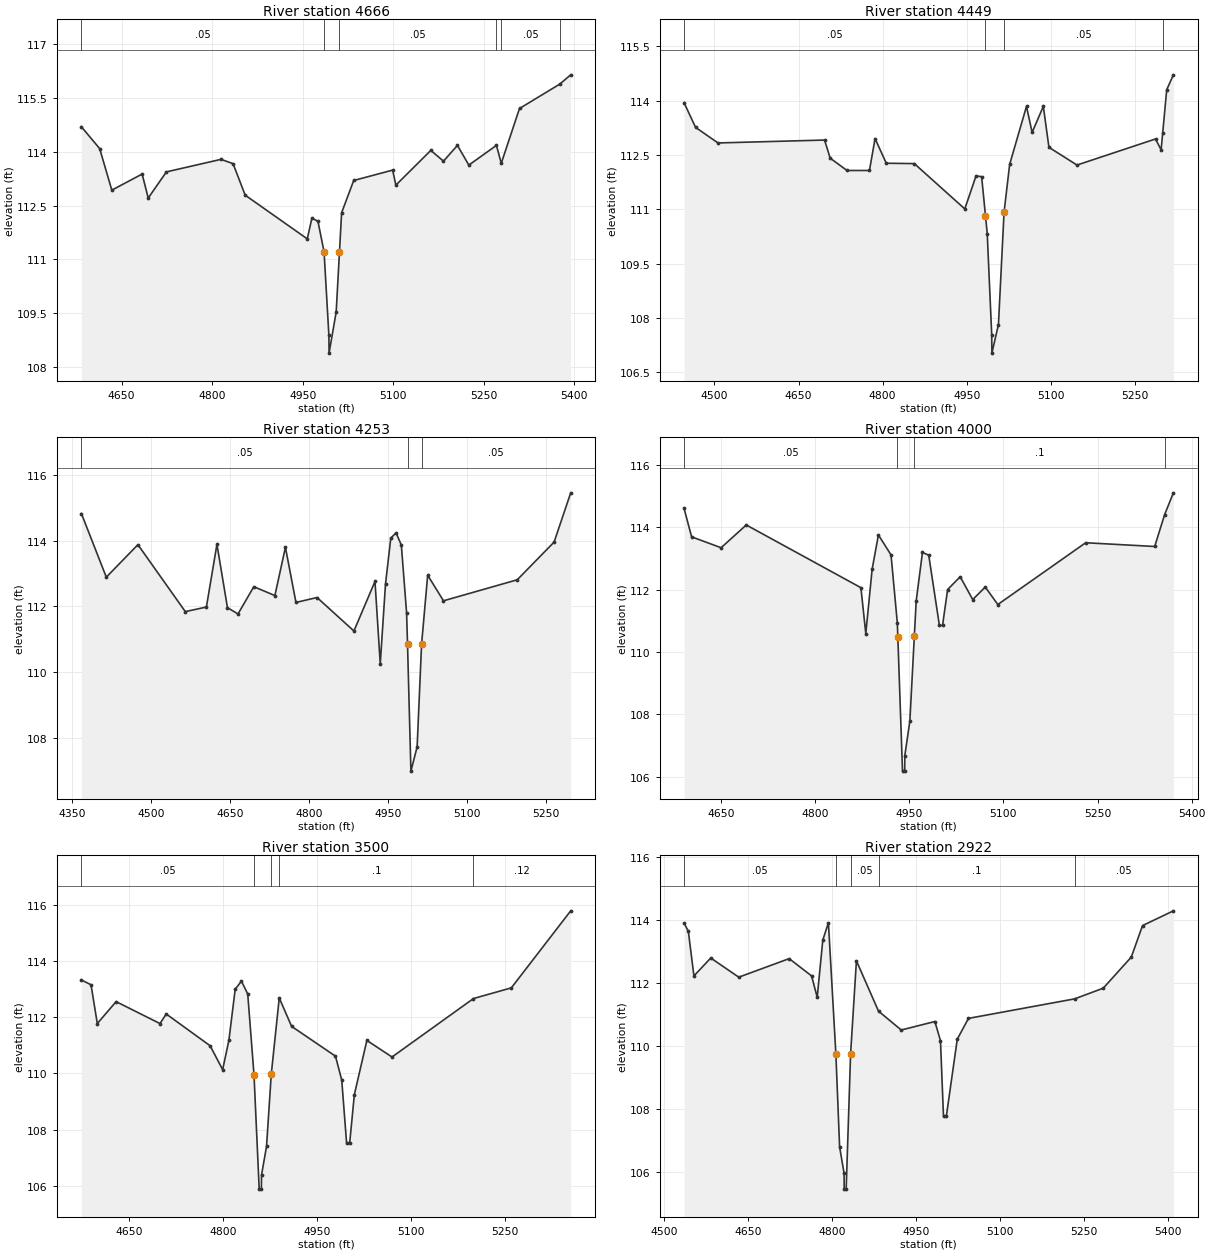
Type RM Length L Ch R = 1 ,4666    ,217,217,217
BEGIN DESCRIPTION:
Crystal Creek 010 9.0
END DESCRIPTION:
XS GIS Cut Line= 3
      3853188.04     10061630.17      3852754.86     10061590.24
      3852397.04     10061703.73
#Sta/Elev= 30
  4583.5   114.7  4613.8  114.09  4633.9  112.93  4684.1  113.38  4694.2  112.71
  4724.3  113.44  4814.7  113.79  4834.7  113.67  4854.8  112.79  4957.6  111.57
  4965.3  112.15  4975.3  112.06  4985.4  111.21  4993.4  108.88  4993.7  108.38
  5005.5  109.53 5010.95 111.208  5014.5   112.3  5034.5   113.2    5099  113.49
  5104.3  113.07  5162.2  114.04  5183.2  113.74  5206.3  114.18  5225.2  113.63
  5270.9  114.18  5278.9  113.68  5309.1  115.21  5375.7  115.89  5393.9  116.15
#Mann= 6 ,-1 , 0
  4583.5     .05       0  4985.4     .07       0 5010.95     .05       0
  5270.9    .075       0  5278.9     .05       0  5375.7    .075       0
Bank Sta=4985.4,5010.95
XS Rating Curve= 0 ,0
Exp/Cntr=0.3,0.1

Type RM Length L Ch R = 1 ,4449    ,196,196,196
BEGIN DESCRIPTION:
Mapping XS 7bfc2062
END DESCRIPTION:
XS GIS Cut Line= 2
      3853378.38     10061380.61      3852505.99     10061382.78
#Sta/Elev= 30
  4445.9  113.94  4466.4  113.26  4506.4  112.83  4696.4  112.91  4706.4  112.41
  4736.4  112.07  4776.4  112.07  4786.4  112.95  4806.4  112.27  4856.4  112.26
  4946.4  111.01  4966.4  111.92  4976.4   111.9 4983.26 110.823  4986.4  110.33
  4994.4  107.53  4994.7  107.03  5006.4  107.82  5016.4  110.92  5026.4  112.24
  5056.4  113.84  5066.4  113.12  5086.4  113.84  5096.4  112.71  5146.4  112.22
  5286.4  112.94  5296.4  112.64  5299.2   113.1  5306.4   114.3  5318.3  114.71
#Mann= 4 ,-1 , 0
  4445.9     .05       0 4983.26     .07       0  5016.4     .05       0
  5299.2    .075       0
Bank Sta=4983.26,5016.4
XS Rating Curve= 0 ,0
Exp/Cntr=0.3,0.1

Type RM Length L Ch R = 1 ,4253    ,253,253,253
BEGIN DESCRIPTION:
Mapping XS 25e82f52
END DESCRIPTION:
XS GIS Cut Line= 2
      3853465.13      10061191.8      3852536.36     10061184.21
#Sta/Elev= 30
  4368.1  114.83  4415.4  112.89  4475.4  113.88  4565.4  111.84  4605.4  111.98
  4625.4  113.89  4645.4  111.96  4665.4  111.77  4695.4   112.6  4735.4  112.33
  4755.4   113.8  4775.4  112.12  4815.4  112.27  4885.4  111.25  4925.4  112.76
  4935.4  110.25  4945.4  112.69  4955.4  114.08  4965.4  114.24  4975.4  113.87
  4985.4   111.8 4987.14  110.86  4993.6  106.98  5005.4  107.72 5013.81  110.84
  5025.4  112.95  5055.4  112.17  5195.4  112.81  5265.4  113.96  5296.9  115.46
#Mann= 3 , 0 , 0
  4368.1     .05       0 4987.14     .07       0 5013.81     .05       0
Bank Sta=4987.14,5013.81
XS Rating Curve= 0 ,0
Exp/Cntr=0.3,0.1

Type RM Length L Ch R = 1 ,4000    ,500,500,500
BEGIN DESCRIPTION:
Crystal Creek 010 8.0
END DESCRIPTION:
XS GIS Cut Line= 3
      3853196.69     10060925.31      3852788.93     10060955.73
      3852418.03     10060956.56
#Sta/Elev= 30
  4591.1   114.6  4603.1  113.69  4650.1  113.34  4690.2  114.07  4872.9  112.06
  4880.7  110.59  4890.8  112.65  4900.8  113.75  4920.9  113.11  4930.9  110.94
 4931.75 110.487  4939.2  106.18  4942.7  106.18  4942.9  106.68  4950.9  107.78
  4958.1 110.523    4961  111.63    4971  113.19    4981   113.1    4998  110.85
    5003  110.85  5011.1     112  5031.1  112.41  5051.1  111.68  5071.1  112.08
  5091.1  111.52  5231.1   113.5  5341.1  113.38  5356.9   114.4  5370.9   115.1
#Mann= 4 ,-1 , 0
  4591.1     .05       0  4930.9     .07       0  4958.1      .1       0
  5356.9     .05       0
Bank Sta=4931.75,4958.1
XS Rating Curve= 0 ,0
Exp/Cntr=0.3,0.1

Type RM Length L Ch R = 1 ,3500    ,578,578,578
BEGIN DESCRIPTION:
Crystal Creek 010 7.0
END DESCRIPTION:
XS GIS Cut Line= 3
      3853143.29     10060623.23      3852717.49     10060622.48
      3852363.33     10060645.37
#Sta/Elev= 30
  4574.2  113.32  4589.6  113.15  4599.6  111.77  4629.6  112.55  4699.6  111.77
  4709.6  112.11  4779.6  110.98  4799.6  110.13  4809.6  111.18  4819.6  112.99
  4829.6  113.28  4839.6  112.82  4849.6  109.95  4857.9  105.88  4861.4  105.88
  4861.6  106.38  4869.6   107.4 4877.13  109.96  4889.9  112.68  4909.6  111.67
  4979.6  110.61  4989.6  109.76  4997.3  107.53  5002.3  107.53  5009.7  109.24
  5029.7  111.17  5069.8  110.58  5199.8  112.66  5260.2  113.04  5354.9  115.78
#Mann= 5 ,-1 , 0
  4574.2     .05       0  4849.6     .07       0 4877.13     .05       0
  4889.9      .1       0  5199.8     .12       0
Bank Sta=4849.6,4877.13
XS Rating Curve= 0 ,0
Exp/Cntr=0.3,0.1

Type RM Length L Ch R = 1 ,2922    ,494,494,494
BEGIN DESCRIPTION:
Crystal Creek 010 6.0
END DESCRIPTION:
XS GIS Cut Line= 3
       3853165.4     10060207.86      3852701.91     10060210.47
      3852292.84     10060186.07
#Sta/Elev= 30
  4535.8   113.9  4543.4  113.64  4553.4  112.22  4583.4  112.79  4633.4  112.18
  4723.4  112.77  4763.4  112.22  4773.4  111.54  4783.4  113.36  4793.4  113.91
 4806.72 109.739  4813.4  106.78  4821.4  105.94  4821.6  105.44  4825.1  105.44
 4833.01 109.745  4843.4   112.7  4882.8   111.1  4923.4   110.5  4983.4  110.77
  4993.4  110.16  4998.8  107.75  5003.8  107.75  5023.4  110.21  5043.4  110.87
  5232.8  111.49  5283.9  111.83    5334  112.82    5354  113.82  5409.1  114.29
#Mann= 5 ,-1 , 0
  4535.8     .05       0 4806.72     .07       0 4833.01     .05       0
  4882.8      .1       0  5232.8     .05       0
Bank Sta=4806.72,4833.01
XS Rating Curve= 0 ,0
Exp/Cntr=0.3,0.1

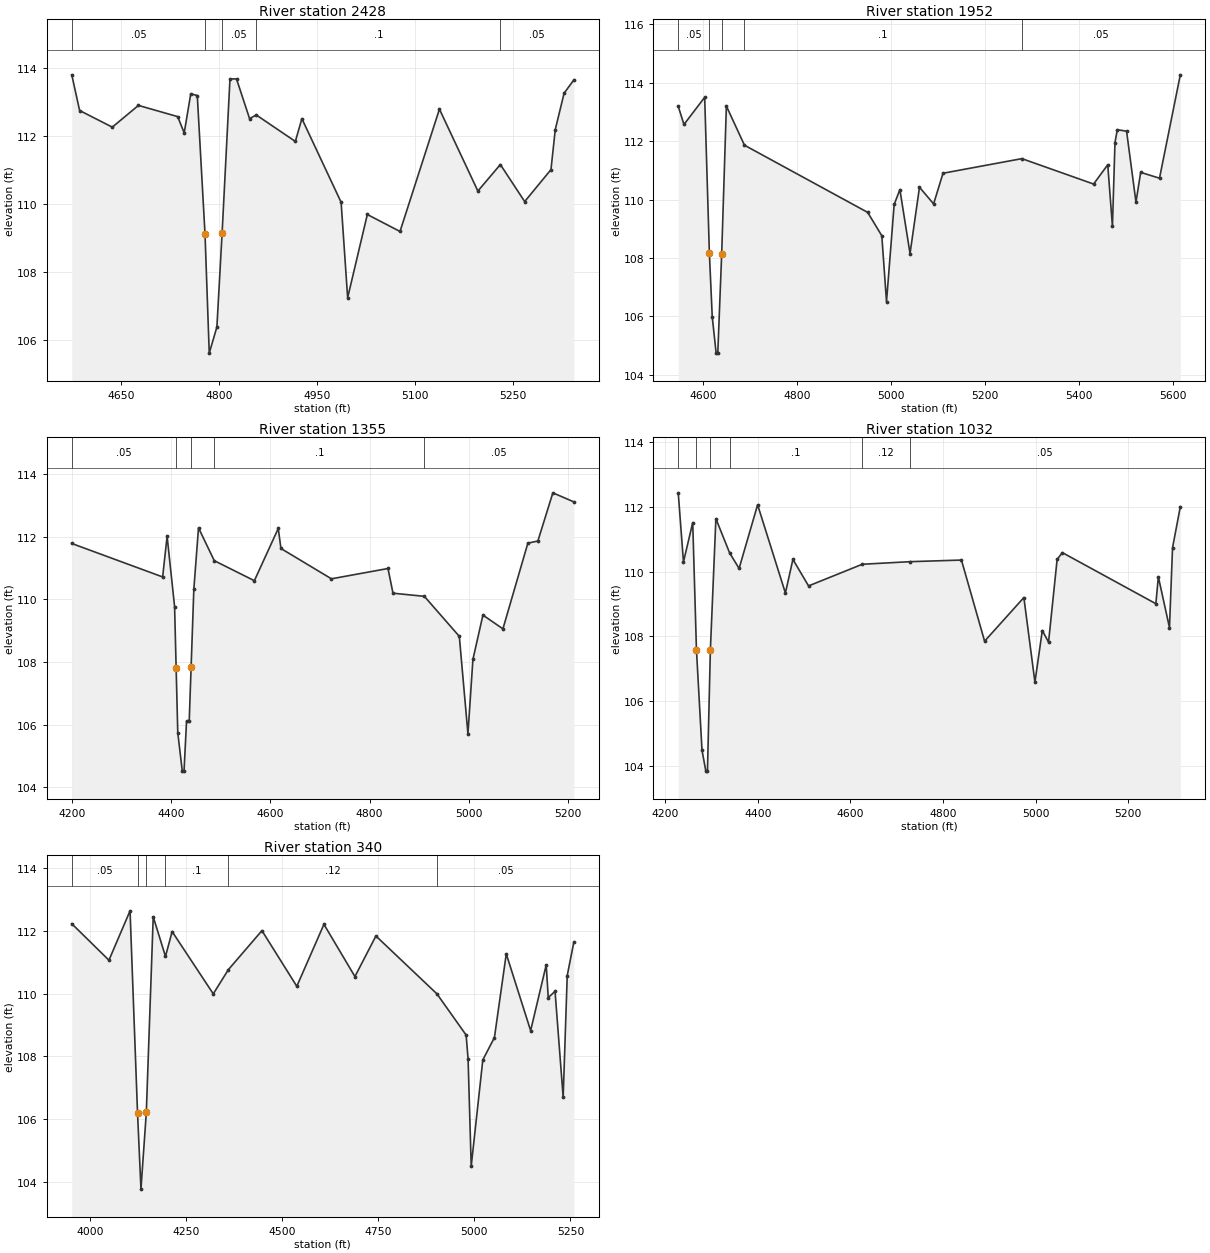
Type RM Length L Ch R = 1 ,2428    ,476,476,476
BEGIN DESCRIPTION:
Crystal Creek 010 5.0
END DESCRIPTION:
XS GIS Cut Line= 3
      3853119.84     10059891.46      3852639.41     10059883.64
      3852352.97     10059908.38
#Sta/Elev= 30
  4574.6  113.79  4586.6  112.74  4636.6  112.25  4676.6  112.89  4736.6  112.56
  4746.6  112.08  4756.6  113.23  4766.6  113.18 4778.42 109.105  4784.9   105.6
  4796.6  106.37 4804.58 109.139  4816.6  113.67  4826.6  113.67  4846.6   112.5
  4856.7  112.61  4916.6  111.83  4926.6   112.5  4986.6  110.04  4996.6  107.23
  5026.7  109.68  5076.7  109.18    5137  112.78  5195.8  110.37  5230.2  111.15
  5267.4  110.06  5307.6     111  5314.2  112.18  5327.7  113.25  5342.6  113.64
#Mann= 5 ,-1 , 0
  4574.6     .05       0 4778.42     .07       0 4804.58     .05       0
  4856.7      .1       0  5230.2     .05       0
Bank Sta=4778.42,4804.58
XS Rating Curve= 0 ,0
Exp/Cntr=0.3,0.1

Type RM Length L Ch R = 1 ,1952    ,597,597,597
BEGIN DESCRIPTION:
Crystal Creek 010 4.0
END DESCRIPTION:
XS GIS Cut Line= 3
      3853000.06     10059591.98      3852526.13     10059627.13
      3851933.67      10059664.9
#Sta/Elev= 30
  4546.8  113.19    4559  112.57  4603.1   113.5  4613.1 108.164  4619.2  105.98
  4627.5  104.74    4631  104.74  4639.3  108.14  4649.3   113.2  4687.8  111.86
  4950.1  109.56  4980.2  108.76  4990.2   106.5  5006.5  109.83  5018.7  110.34
  5040.3  108.15  5060.4  110.42  5090.5  109.85  5110.5   110.9  5278.4   111.4
  5431.1  110.53  5461.2  111.19  5471.2  109.08  5476.6  111.95  5481.6  112.39
  5501.3  112.34  5521.3  109.91  5531.3  110.93  5571.4  110.73  5615.7  114.27
#Mann= 5 ,-1 , 0
  4546.8     .05       0  4613.1     .07       0  4639.3     .05       0
  4687.8      .1       0  5278.4     .05       0
Bank Sta=4613.1,4639.3
XS Rating Curve= 0 ,0
Exp/Cntr=0.3,0.1

Type RM Length L Ch R = 1 ,1355    ,323,323,323
BEGIN DESCRIPTION:
Crystal Creek 010 3.0
END DESCRIPTION:
XS GIS Cut Line= 3
      3853145.94     10059443.55      3852657.64     10059245.62
      3852175.88     10059304.22
#Sta/Elev= 30
  4199.7  111.79  4382.9  110.72  4391.9  112.02    4407  109.77  4410.1 107.818
  4413.4  105.74  4422.5  104.51    4426  104.51  4431.1  106.11  4436.5  106.12
 4440.28 107.831  4445.8  110.33  4455.2  112.29    4487  111.24  4567.8   110.6
    4616  112.27  4621.4  111.63  4723.2  110.66  4837.2  110.99  4847.3   110.2
  4910.5   110.1    4981  108.82  4998.4   105.7  5008.4  108.08  5028.6   109.5
  5068.9  109.06  5119.2   111.8  5139.4  111.87  5169.6  113.41  5211.9  113.12
#Mann= 5 ,-1 , 0
  4199.7     .05       0  4410.1     .07       0 4440.28     .05       0
    4487      .1       0  4910.5     .05       0
Bank Sta=4410.1,4440.28
XS Rating Curve= 0 ,0
Exp/Cntr=0.3,0.1

Type RM Length L Ch R = 1 ,1032    ,692,692,692
BEGIN DESCRIPTION:
Crystal Creek 010 2.0
END DESCRIPTION:
XS GIS Cut Line= 3
      3853009.16     10059089.37      3852283.94      10059108.9
      3851952.34     10059245.45
#Sta/Elev= 30
  4228.3  112.44  4239.6   110.3  4259.6  111.52 4267.63 107.585  4279.6  104.48
  4287.9  103.83  4291.4  103.83 4297.67  107.57  4309.6  111.64  4339.3  110.58
  4359.7   110.1  4399.7  112.07  4459.7  109.34  4475.9  110.38  4509.7  109.56
  4625.7  110.23    4729  110.31  4839.8  110.36  4889.8  107.85  4974.6   109.2
  4998.5  106.58  5014.4  108.18  5027.9  107.82  5046.4  110.38  5057.7  110.59
  5259.6  109.01    5265  109.84    5289  108.27  5295.6  110.74  5312.4  112.01
#Mann= 6 ,-1 , 0
  4228.3     .05       0 4267.63     .07       0 4297.67     .05       0
  4339.3      .1       0  4625.7     .12       0    4729     .05       0
Bank Sta=4267.63,4297.67
XS Rating Curve= 0 ,0
Exp/Cntr=0.3,0.1

Type RM Length L Ch R = 1 ,340     ,0,0,0
BEGIN DESCRIPTION:
Crystal Creek 010 1.0
END DESCRIPTION:
XS GIS Cut Line= 4
      3853141.98     10058970.87      3852705.45     10058805.26
      3852058.68     10058887.55      3851881.58     10058948.31
#Sta/Elev= 30
  3952.9  112.22  4049.6  111.06  4104.5  112.63 4123.93 106.215  4132.9  103.78
 4146.82 106.218  4164.8  112.44  4196.7  111.18    4214  111.97    4321  109.99
  4360.3  110.76  4447.6     112  4538.3  110.23  4608.9   112.2  4689.5  110.54
  4744.1  111.83  4902.8  109.99  4978.8  108.68  4983.9  107.91    4992  104.51
  5022.2  107.89  5052.4   108.6  5083.2  111.26  5146.6  108.82  5187.1  110.91
  5192.4  109.87  5210.1  110.07  5231.2   106.7  5241.8  110.57    5259  111.64
#Mann= 6 ,-1 , 0
  3952.9     .05       0 4123.93     .07       0 4146.82     .05       0
  4196.7      .1       0  4360.3     .12       0  4902.8     .05       0
Bank Sta=4123.93,4146.82
XS Rating Curve= 0 ,0
Exp/Cntr=0.3,0.1