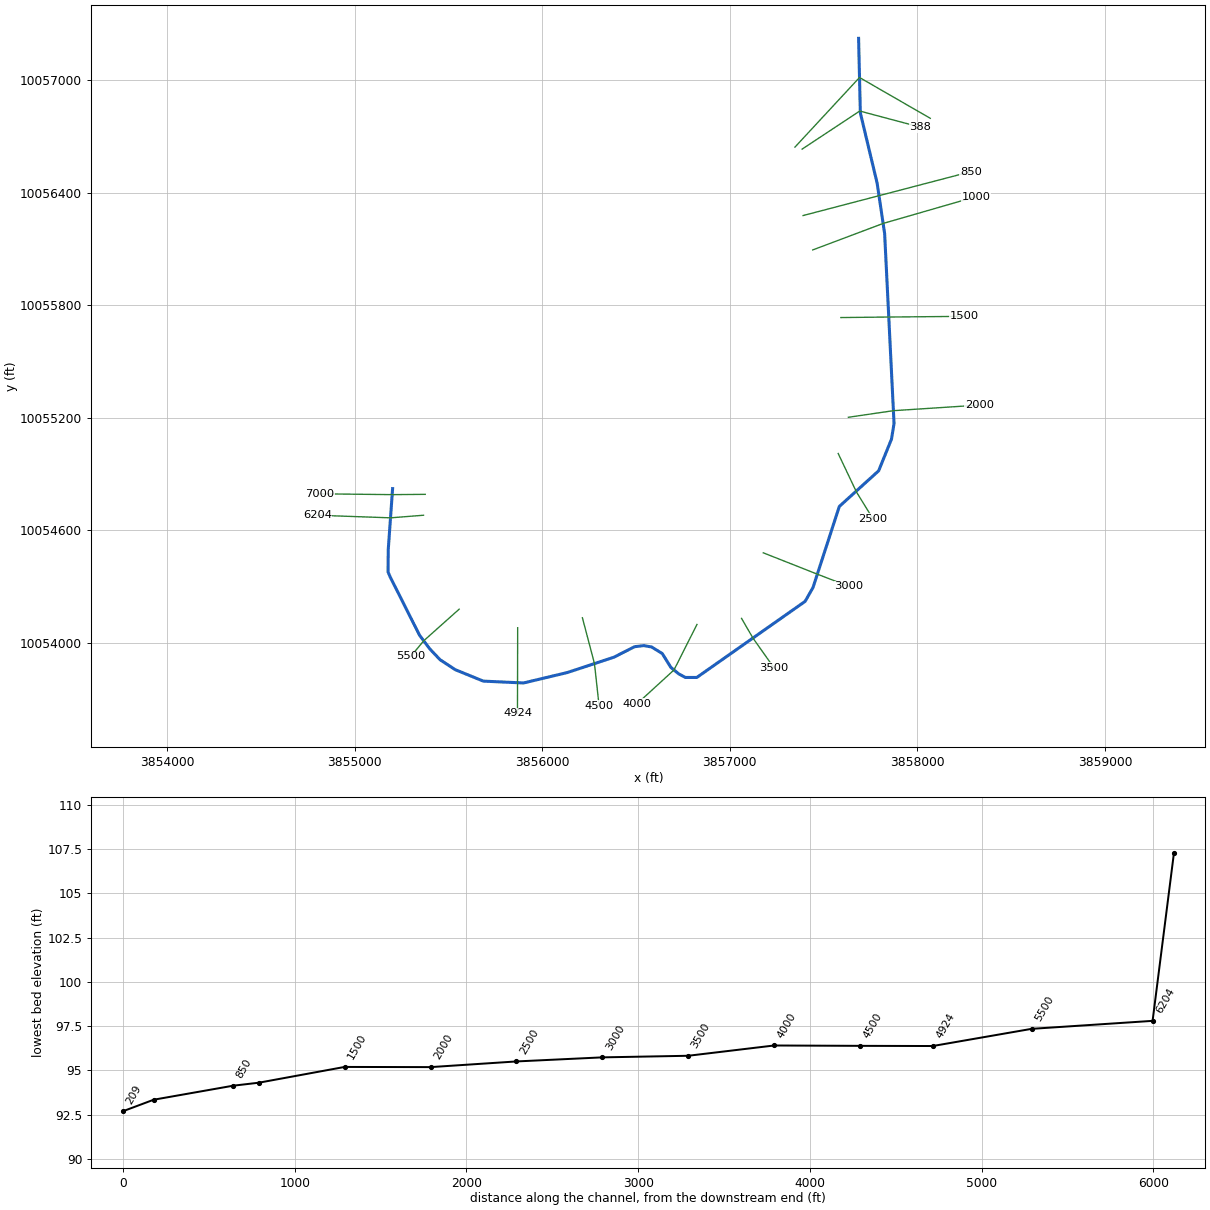
--- Crystal Creek 012.prj (project) ---

Proj Title=Crystal Creek 012 Base Level Engineering
Current Plan=p01
Default Exp/Contr=0.3,0.1
English Units
Geom File=g01
Flow File=f01
Flow File=f02
Plan File=p01
Y Axis Title=Elevation
X Axis Title(PF)=Main Channel Distance
X Axis Title(XS)=Station
BEGIN DESCRIPTION:
Crystal Creek 012
END DESCRIPTION:
DSS Export Rating Curves= 0
DSS Export Rating Curve Sorted= 0
DSS Export Volume Flow Curves= 0
DXF OffsetX= 0
DXF OffsetY= 0
DXF ScaleX= 1
DXF ScaleY= 10

--- Crystal Creek 012.p01 (plan) ---

Plan Title=Multiple Run
Short Identifier=Multiple
Geom File=g01
Flow File=f01
Subcritical Flow
K Sum by GR= 0
Std Step Tol= 0.01
Critical Tol= 0.01
Num of Std Step Trials= 20
Max Error Tol= 0.3
Flow Tol Ratio= 0.001
Split Flow NTrial= 30
Split Flow Tol= 0.02
Split Flow Ratio= 0.02
Log Output Level= 0
Friction Slope Method= 1
Unsteady Friction Slope Method= 2
Unsteady Bridges Friction Slope Method= 1
Parabolic Critical Depth
Global Vel Dist=  1 , 1 , 1
Global Log Level= 0
CheckData=True
Encroach Param= -1, 0, 0, 0
BEGIN DESCRIPTION:
Multiple Run
END DESCRIPTION:

--- Crystal Creek 012.f01 (steady flow) ---

Flow Title=Multiple
Program Version=4.10
Number of Profiles= 7
Profile Names=10-year,25-year,50-year,1pct_min,100-year,1pct_plu,500-year
River Rch & RM=Crystal Creek 01,Reach-1         ,7000
     366     468     608     260     785    2371    1352
River Rch & RM=Crystal Creek 01,Reach-1         ,6204
     366     468     608     260     785    2371    1352
River Rch & RM=Crystal Creek 01,Reach-1         ,1500
     381     487     630     269     813    2455    1393
Boundary for River Rch & Prof#=Crystal Creek 01,Reach-1         , 1
Up Type= 0
Dn Type= 3
Dn Slope=0.004
Boundary for River Rch & Prof#=Crystal Creek 01,Reach-1         , 2
Up Type= 0
Dn Type= 3
Dn Slope=0.004
Boundary for River Rch & Prof#=Crystal Creek 01,Reach-1         , 3
Up Type= 0
Dn Type= 3
Dn Slope=0.004
Boundary for River Rch & Prof#=Crystal Creek 01,Reach-1         , 4
Up Type= 0
Dn Type= 3
Dn Slope=0.004
Boundary for River Rch & Prof#=Crystal Creek 01,Reach-1         , 5
Up Type= 0
Dn Type= 3
Dn Slope=0.004
Boundary for River Rch & Prof#=Crystal Creek 01,Reach-1         , 6
Up Type= 0
Dn Type= 3
Dn Slope=0.004
Boundary for River Rch & Prof#=Crystal Creek 01,Reach-1         , 7
Up Type= 0
Dn Type= 3
Dn Slope=0.004
DSS Import GetInterval= 0
DSS Import GetPeak= 0
DSS Import FillOption= 0

--- Crystal Creek 012.f02 (steady flow) ---

Flow Title=Orig_BLE_Flow
Program Version=4.10
Number of Profiles= 7
Profile Names=10-year,25-year,50-year,1pct_min,100-year,1pct_plu,500-year
River Rch & RM=Crystal Creek 01,Reach-1         ,7000
     366     459     529     200     604    1825     786
River Rch & RM=Crystal Creek 01,Reach-1         ,6204
     366     459     529     200     604    1825     786
River Rch & RM=Crystal Creek 01,Reach-1         ,1500
     381     477     548     207     625    1888     810
Boundary for River Rch & Prof#=Crystal Creek 01,Reach-1         , 1
Up Type= 0
Dn Type= 3
Dn Slope=0.004
Boundary for River Rch & Prof#=Crystal Creek 01,Reach-1         , 2
Up Type= 0
Dn Type= 3
Dn Slope=0.004
Boundary for River Rch & Prof#=Crystal Creek 01,Reach-1         , 3
Up Type= 0
Dn Type= 3
Dn Slope=0.004
Boundary for River Rch & Prof#=Crystal Creek 01,Reach-1         , 4
Up Type= 0
Dn Type= 3
Dn Slope=0.004
Boundary for River Rch & Prof#=Crystal Creek 01,Reach-1         , 5
Up Type= 0
Dn Type= 3
Dn Slope=0.004
Boundary for River Rch & Prof#=Crystal Creek 01,Reach-1         , 6
Up Type= 0
Dn Type= 3
Dn Slope=0.004
Boundary for River Rch & Prof#=Crystal Creek 01,Reach-1         , 7
Up Type= 0
Dn Type= 3
Dn Slope=0.004
DSS Import GetInterval= 0
DSS Import GetPeak= 0
DSS Import FillOption= 0

--- Crystal Creek 012.g01 (geometry) ---

Geom Title=Existing Conditions
Program Version=4.10

River Reach=Crystal Creek 01,Reach-1
Reach XY= 30
      3855201.86     10054823.22      3855178.65     10054497.92
      3855177.51     10054379.06      3855188.93     10054352.28
      3855345.49     10054041.53      3855399.65     10053969.22
      3855454.67     10053911.06      3855535.94     10053857.75
      3855685.62     10053796.82       3855899.8     10053786.97
      3856132.94     10053842.45       3856381.9     10053924.36
      3856491.82     10053980.26      3856540.66     10053986.25
      3856582.65     10053978.89      3856639.58     10053943.88
      3856685.46     10053869.98      3856727.07     10053835.67
      3856762.56     10053816.51      3856823.75      10053816.3
      3857401.26     10054221.93       3857443.3     10054295.87
      3857583.57     10054728.02      3857793.37     10054918.23
       3857861.7     10055086.88      3857875.38     10055170.06
      3857825.23     10056182.83      3857785.13     10056452.35
      3857695.68     10056826.55      3857686.38     10057223.96

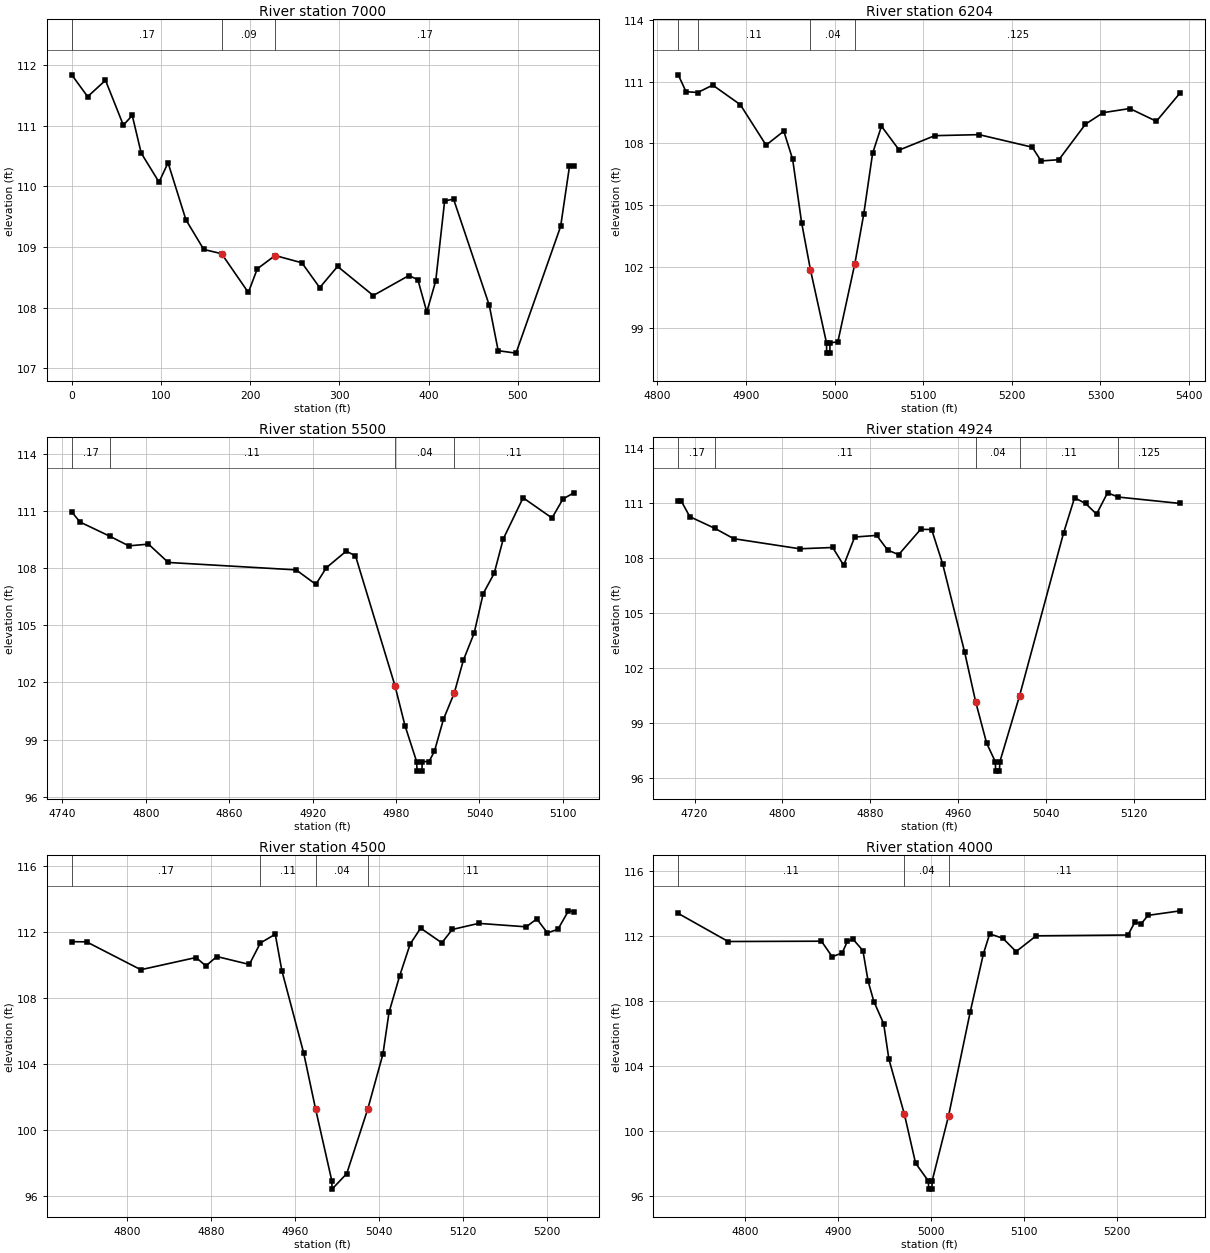
Type RM Length L Ch R = 1 ,7000    ,124,124,124
XS GIS Cut Line= 3
       3855375.7     10054792.66      3855199.57     10054791.11
      3854813.01     10054795.46
#Sta/Elev= 30
       0  111.84    17.8  111.48    37.8  111.75    57.8  111.01    67.8  111.17
    77.8  110.55    97.8  110.07   107.9  110.39   127.9  109.45   147.9  108.96
   167.9  108.89   197.9  108.25   207.9  108.64   227.9  108.86   257.9  108.74
   277.9  108.33   297.9  108.68   337.9   108.2   377.9  108.53   387.9  108.46
   397.9  107.93   407.9  108.44   417.9  109.76   427.9  109.79   467.9  108.04
   477.9  107.29   497.9  107.25   547.9  109.34   557.8  110.33   562.7  110.33
#Mann= 3 , 0 , 0
       0     .17       0   167.9     .09       0   227.9     .17       0
Bank Sta=167.9,227.9
XS Rating Curve= 0 ,0
Exp/Cntr=0.3,0.1

Type RM Length L Ch R = 1 ,6204    ,704,704,704
BEGIN DESCRIPTION:
Crystal Creek 012 12.0
END DESCRIPTION:
XS GIS Cut Line= 3
       3855366.6     10054681.29       3855191.3     10054667.41
      3854800.89     10054681.23
#Sta/Elev= 30
  4823.6  111.34  4832.4  110.52  4845.7  110.48  4862.5  110.84  4893.6  109.89
  4922.7  107.92  4942.7   108.6  4952.7  107.23  4962.8  104.15  4972.8  101.85
  4990.9    98.3  4991.1    97.8  4994.6    97.8  4994.9    98.3  5003.7   98.35
  5022.9  102.16  5032.9  104.56  5042.9  107.52  5052.9  108.84  5072.9  107.68
    5113  108.38    5163  108.43    5223  107.82    5233  107.15  5253.1  107.21
  5283.1  108.94  5303.1   109.5  5333.1   109.7  5363.1  109.08  5390.1  110.47
#Mann= 4 ,-1 , 0
  4823.6     .17       0  4845.7     .11       0  4972.8     .04       0
  5022.9    .125       0
Bank Sta=4972.8,5022.9
XS Rating Curve= 0 ,0
Exp/Cntr=0.3,0.1

Type RM Length L Ch R = 1 ,5500    ,576,576,576
BEGIN DESCRIPTION:
Crystal Creek 012 11.0
END DESCRIPTION:
XS GIS Cut Line= 3
      3855556.76     10054180.44      3855367.72     10054011.84
      3855298.99     10053928.67
#Sta/Elev= 30
  4746.7  110.94  4752.6  110.41  4773.9  109.67  4787.7  109.16  4801.9  109.25
  4816.1  108.29  4908.1   107.9  4922.3  107.14  4929.8  108.01  4944.1  108.88
  4950.8  108.64  4979.2  101.83  4986.4   99.74  4994.8   97.85  4995.1   97.35
  4998.6   97.35  4998.8   97.85  5003.7   97.85  5007.6   98.39  5014.1  100.07
  5021.9  101.45  5028.4  103.16  5036.2  104.59  5042.7  106.66  5050.6  107.72
  5057.1  109.52  5071.4  111.68  5092.2  110.62  5100.1  111.62  5107.9  111.94
#Mann= 4 ,-1 , 0
  4746.7     .17       0  4773.9     .11       0  4979.2     .04       0
  5021.9     .11       0
Bank Sta=4979.2,5021.9
XS Rating Curve= 0 ,0
Exp/Cntr=0.3,0.1

Type RM Length L Ch R = 1 ,4924    ,424,424,424
BEGIN DESCRIPTION:
Crystal Creek 012 10.0
END DESCRIPTION:
XS GIS Cut Line= 2
      3855868.68     10054081.56      3855867.59     10053624.86
#Sta/Elev= 30
  4705.2  111.11  4707.9  111.11  4715.7  110.25  4738.3  109.62  4755.7  109.05
  4815.7   108.5  4845.7  108.57  4855.7   107.6  4865.7  109.14  4885.7  109.23
  4895.7  108.43  4905.7  108.18  4925.7  109.56  4935.7  109.55  4945.7  107.68
  4965.7  102.87  4975.7  100.17  4985.7   97.91  4993.7   96.88  4993.9   96.38
  4997.4   96.38  4997.7   96.88  5015.7  100.49  5055.7  109.36  5065.7  111.28
  5075.7  110.97  5085.7  110.39  5095.7  111.55  5105.4  111.32  5161.9  110.97
#Mann= 5 ,-1 , 0
  4705.2     .17       0  4738.3     .11       0  4975.7     .04       0
  5015.7     .11       0  5105.4    .125       0
Bank Sta=4975.7,5015.7
XS Rating Curve= 0 ,0
Exp/Cntr=0.3,0.1

Type RM Length L Ch R = 1 ,4500    ,500,500,500
BEGIN DESCRIPTION:
Crystal Creek 012 9.0
END DESCRIPTION:
XS GIS Cut Line= 3
      3856213.74     10054134.68      3856278.19     10053890.24
       3856302.7     10053665.97
#Sta/Elev= 30
  4747.2  111.39  4761.3  111.38    4813  109.69  4865.6  110.43    4875  109.92
  4885.4  110.49  4916.4  110.01  4926.9  111.31  4941.1  111.84  4947.4  109.63
  4968.1  104.66 4979.45101.2661    4995   96.89  4995.2   96.39  5009.2   97.33
  5029.3  101.26  5043.7  104.58  5049.5  107.11  5059.5  109.29  5069.6  111.24
  5079.6  112.21  5099.8  111.32  5109.8  112.13    5135   112.5  5180.2  112.29
  5190.3  112.77  5200.4  111.92  5210.4  112.14  5220.5  113.26  5225.6   113.2
#Mann= 4 ,-1 , 0
  4747.2     .17       0  4926.9     .11       0 4979.45     .04       0
  5029.3     .11       0
Bank Sta=4979.45,5029.3
XS Rating Curve= 0 ,0
Exp/Cntr=0.3,0.1

Type RM Length L Ch R = 1 ,4000    ,500,500,500
BEGIN DESCRIPTION:
Crystal Creek 012 8.0
END DESCRIPTION:
XS GIS Cut Line= 3
       3856824.6     10054098.87      3856702.13     10053856.23
      3856504.22     10053675.37
#Sta/Elev= 30
  4728.2  113.39  4781.9  111.66  4882.2  111.68  4893.8  110.72  4904.5  110.96
  4910.1  111.67  4916.2   111.8  4926.8   111.1  4932.4  109.21  4938.6  107.96
  4949.1   106.6  4954.7  104.42  4971.4  101.02  4983.4   98.01  4997.2   96.91
  4997.5   96.41    5001   96.41  5001.2   96.91 5018.88100.9201  5042.2  107.33
  5056.4  110.91  5063.1  112.13  5077.3  111.86  5091.5  111.04  5113.1  112.01
  5211.8  112.06  5219.2  112.85    5226  112.75  5233.4  113.27  5268.1  113.55
#Mann= 3 , 0 , 0
  4728.2     .11       0  4971.4     .04       0 5018.88     .11       0
Bank Sta=4971.4,5018.88
XS Rating Curve= 0 ,0
Exp/Cntr=0.3,0.1

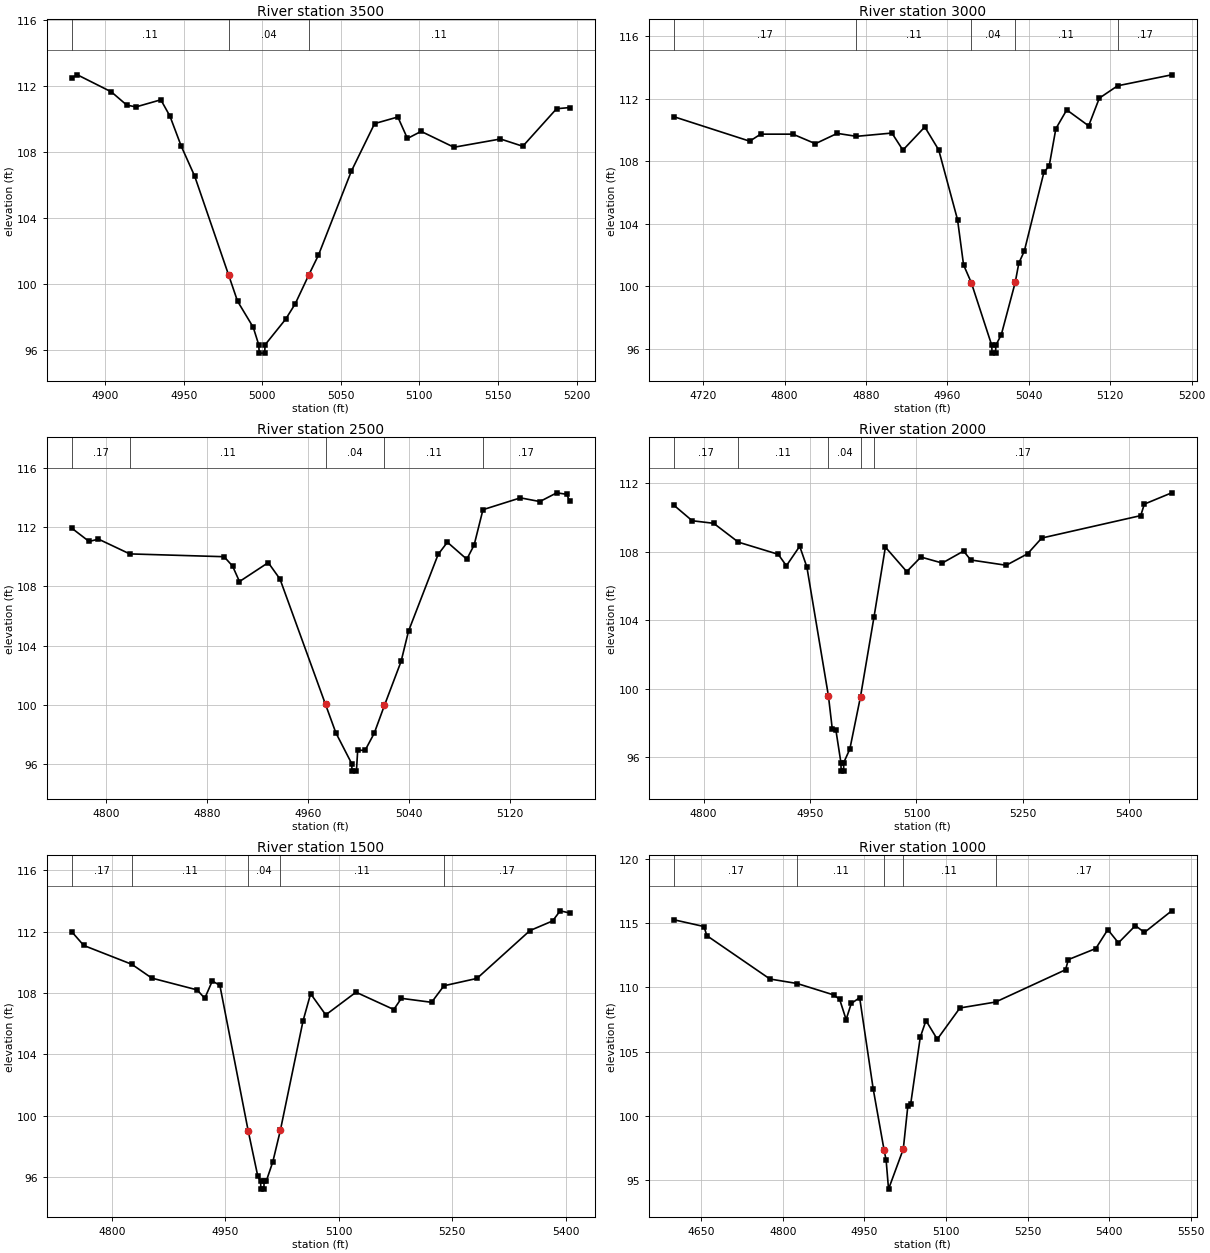
Type RM Length L Ch R = 1 ,3500    ,500,500,500
BEGIN DESCRIPTION:
Crystal Creek 012 7.0
END DESCRIPTION:
XS GIS Cut Line= 3
      3857062.25     10054131.48      3857123.01      10054026.5
      3857235.85     10053866.73
#Sta/Elev= 30
  4878.7  112.47  4882.4  112.66    4904  111.63  4913.8  110.83  4919.7  110.72
  4935.5  111.15  4941.3  110.16  4948.5  108.34    4957  106.54  4978.6  100.56
  4984.3   98.97  4994.3   97.39  4997.8   96.33  4998.1   95.83  5001.6   95.83
  5001.8   96.33  5014.9   97.88    5021   98.81  5029.7  100.57  5035.8  101.76
  5056.7  106.83  5071.5  109.71  5086.3  110.11  5092.4  108.81  5101.1  109.24
    5122  108.28  5151.6  108.78  5165.8  108.34  5187.3  110.61  5195.6  110.68
#Mann= 3 , 0 , 0
  4878.7     .11       0  4978.6     .04       0  5029.7     .11       0
Bank Sta=4978.6,5029.7
XS Rating Curve= 0 ,0
Exp/Cntr=0.3,0.1

Type RM Length L Ch R = 1 ,3000    ,500,500,500
BEGIN DESCRIPTION:
Crystal Creek 012 6.0
END DESCRIPTION:
XS GIS Cut Line= 3
      3857178.33     10054480.87      3857465.82     10054367.33
      3857633.98     10054302.29
#Sta/Elev= 30
  4690.9  110.85  4765.7  109.28  4776.4  109.73  4808.1  109.73  4830.2  109.12
  4851.7  109.78  4870.5  109.59  4905.4   109.8  4916.2  108.71  4937.7  110.19
  4951.4  108.72  4969.9  104.26  4975.8  101.38 4983.44100.2375  5003.5   96.24
  5003.8   95.74  5007.3   95.74  5007.5   96.24  5012.9   96.92 5026.56100.2537
  5030.1  101.49  5035.5  102.26  5054.7  107.28    5060  107.72  5066.5  110.08
  5077.2  111.28  5098.7  110.26  5109.2  112.03  5127.2  112.82  5180.3  113.52
#Mann= 5 ,-1 , 0
  4690.9     .17       0  4870.5     .11       0 4983.44     .04       0
 5026.56     .11       0  5127.2     .17       0
Bank Sta=4983.44,5026.56
XS Rating Curve= 0 ,0
Exp/Cntr=0.3,0.1

Type RM Length L Ch R = 1 ,2500    ,500,500,500
BEGIN DESCRIPTION:
Crystal Creek 012 5.0
END DESCRIPTION:
XS GIS Cut Line= 3
      3857577.68     10055010.33      3857675.24      10054804.7
      3857763.01     10054662.39
#Sta/Elev= 30
  4772.4  111.95  4786.3  111.04  4793.7   111.2  4818.5   110.2  4893.3  110.01
    4900  109.38  4905.5  108.33  4928.3  109.61  4937.6   108.5  4973.7  100.02
  4981.9    98.1  4994.5   96.01  4994.7   95.51  4998.2   95.51  4999.2   96.92
  5005.1   96.92  5012.3   98.07 5020.4599.96465  5033.6  102.93  5039.5  104.98
    5063  110.17  5070.3  110.99  5085.7  109.84  5091.5   110.8  5098.5  113.19
  5128.2  113.99  5143.6  113.74    5157  114.33  5164.9  114.23  5167.2  113.76
#Mann= 5 ,-1 , 0
  4772.4     .17       0  4818.5     .11       0  4973.7     .04       0
 5020.45     .11       0  5098.5     .17       0
Bank Sta=4973.7,5020.45
XS Rating Curve= 0 ,0
Exp/Cntr=0.3,0.1

Type RM Length L Ch R = 1 ,2000    ,500,500,500
BEGIN DESCRIPTION:
Crystal Creek 012 4.0
END DESCRIPTION:
XS GIS Cut Line= 3
      3857631.92     10055203.52      3857871.74     10055238.73
      3858330.67     10055268.62
#Sta/Elev= 30
  4757.6  110.73  4783.8  109.81  4814.1  109.66  4848.9  108.56  4905.1  107.85
  4916.6  107.18  4935.4  108.32  4945.5  107.11  4975.9   99.58  4981.3   97.66
  4986.3   97.62  4993.5   95.69  4993.8   95.19  4997.3   95.19  4997.5   95.69
  5006.1   96.48 5021.1599.54495  5040.2   104.2  5056.2  108.27  5086.3  106.84
  5106.3  107.69  5136.4  107.34  5166.5  108.04  5176.5  107.52  5226.6  107.21
  5256.7  107.88  5276.7   108.8  5416.3  110.11  5421.3  110.78  5459.9  111.44
#Mann= 5 ,-1 , 0
  4757.6     .17       0  4848.9     .11       0  4975.9     .04       0
 5021.15     .11       0  5040.2     .17       0
Bank Sta=4975.9,5021.15
XS Rating Curve= 0 ,0
Exp/Cntr=0.3,0.1

Type RM Length L Ch R = 1 ,1500    ,500,500,500
BEGIN DESCRIPTION:
Crystal Creek 012 3.0
END DESCRIPTION:
XS GIS Cut Line= 3
       3857591.8      10055735.2      3857845.28     10055738.03
      3858250.36     10055741.71
#Sta/Elev= 30
  4746.5  112.01  4762.6   111.1  4826.2  109.87  4852.6  108.97  4912.6   108.2
  4922.6  107.65  4932.6  108.78  4942.6   108.5 4980.0399.00888  4992.6   96.08
  4996.5    95.7  4996.8    95.2  5000.8    95.2  5001.1    95.7  5003.8    95.7
  5012.6   96.98  5022.6   99.04  5052.6  106.18  5062.6  107.95  5082.6  106.57
  5122.6  108.05  5172.6  106.92  5182.6  107.65  5222.6  107.39  5238.9  108.47
  5282.6  108.95  5352.6  112.07  5382.6   112.7  5392.6  113.36  5405.1  113.22
#Mann= 5 ,-1 , 0
  4746.5     .17       0  4826.2     .11       0 4980.03     .04       0
  5022.6     .11       0  5238.9     .17       0
Bank Sta=4980.03,5022.6
XS Rating Curve= 0 ,0
Exp/Cntr=0.3,0.1

Type RM Length L Ch R = 1 ,1000    ,150,150,150
BEGIN DESCRIPTION:
Crystal Creek 012 2.0
END DESCRIPTION:
XS GIS Cut Line= 3
      3857442.14     10056095.88      3857817.17     10056236.98
      3858311.89     10056379.72
#Sta/Elev= 30
  4599.3  115.25  4655.1  114.72  4660.4  114.01  4776.4  110.64  4826.5  110.29
  4893.9   109.4  4904.6  109.05  4916.4  107.49  4925.9  108.74  4941.3  109.19
  4966.2   102.1 4986.1197.37206    4990   96.55  4994.4   94.31  5021.5   97.42
  5029.8  100.74    5035  100.89  5052.7  106.11  5063.2  107.41    5084  105.96
  5125.6  108.39  5191.1  108.85  5319.8  111.36    5325  112.15  5375.4  113.01
  5397.5  114.48    5417  113.45  5448.2  114.79  5464.8  114.26  5514.9  115.94
#Mann= 5 ,-1 , 0
  4599.3     .17       0  4826.5     .11       0 4986.11     .04       0
  5021.5     .11       0  5191.1     .17       0
Bank Sta=4986.11,5021.5
XS Rating Curve= 0 ,0
Exp/Cntr=0.3,0.1

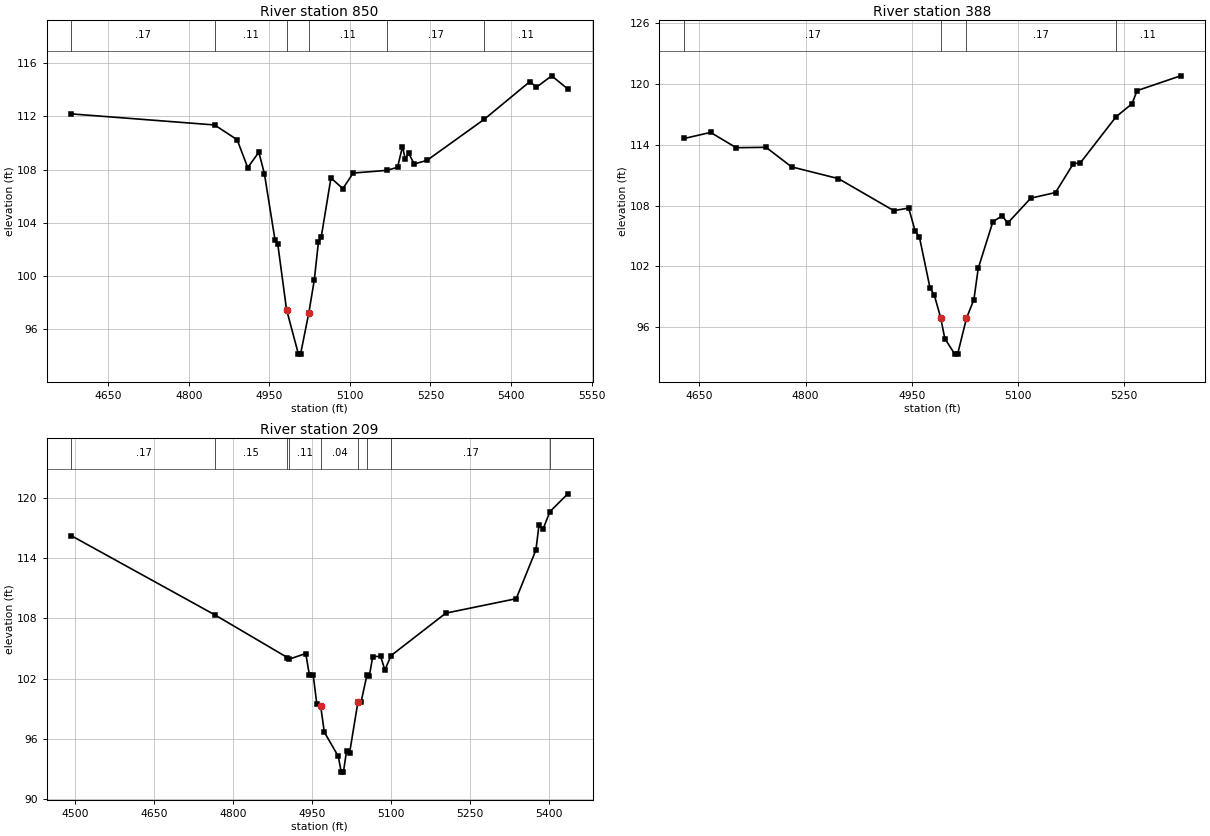
Type RM Length L Ch R = 1 ,850     ,462,462,462
BEGIN DESCRIPTION:
Mapping XS 1b18a99a
END DESCRIPTION:
XS GIS Cut Line= 2
      3857390.38     10056279.06      3858284.58     10056513.01
#Sta/Elev= 30
  4581.6  112.18  4848.2  111.35  4890.1  110.24  4909.8  108.15  4930.5   109.3
  4940.8   107.7  4960.6  102.72  4965.7  102.42  4982.1   97.48  5004.2   94.14
  5008.2   94.14  5023.5   97.22  5033.8   99.71  5041.4  102.53  5046.6  102.91
  5064.8  107.37    5087  106.57  5106.2  107.74  5168.8  107.94  5188.8  108.17
    5198  109.73  5203.1  108.81  5209.5  109.22  5219.9  108.42  5243.6  108.69
  5350.4  111.78  5435.4  114.61  5447.3  114.18  5475.8  115.04  5505.9  114.05
#Mann= 6 ,-1 , 0
  4581.6     .17       0  4848.2     .11       0  4982.1     .04       0
  5023.5     .11       0  5168.8     .17       0  5350.4     .11       0
Bank Sta=4982.1,5023.5
XS Rating Curve= 0 ,0
Exp/Cntr=0.3,0.1

Type RM Length L Ch R = 1 ,388     ,179,179,179
BEGIN DESCRIPTION:
Mapping XS 4b6162b2
END DESCRIPTION:
XS GIS Cut Line= 3
      3857385.23     10056633.25      3857692.51     10056836.36
      3858014.17     10056750.76
#Sta/Elev= 30
  4628.6  114.62  4665.8  115.22    4702  113.71  4744.1  113.75  4780.2  111.82
  4846.4  110.66  4924.6   107.5  4945.7  107.76  4954.8  105.48  4960.8  104.91
  4975.8   99.87  4981.8   99.19  4990.9   96.92  4996.7   94.88  5010.8   93.35
  5014.8   93.35 5027.3296.89677  5037.8   98.73  5043.9  101.81  5064.6  106.41
    5078     107  5085.3  106.26  5118.1  108.73  5153.1  109.29  5178.4  112.15
    5188   112.2  5238.5  116.75  5261.2  118.05  5268.3  119.34  5329.8   120.8
#Mann= 4 ,-1 , 0
  4628.6     .17       0  4990.9     .04       0 5027.32     .17       0
  5238.5     .11       0
Bank Sta=4990.9,5027.32
XS Rating Curve= 0 ,0
Exp/Cntr=0.3,0.1

Type RM Length L Ch R = 1 ,209     ,0,0,0
BEGIN DESCRIPTION:
Crystal Creek 012 1.0
END DESCRIPTION:
XS GIS Cut Line= 3
       3857347.1     10056644.07      3857691.27     10057015.13
      3858068.48     10056797.68
#Sta/Elev= 30
  4493.9  116.23  4766.8  108.33  4903.4  104.11  4905.9  103.93  4938.3  104.51
  4945.1  102.39  4952.5  102.33  4959.3   99.48  4966.6   99.27  4973.5   96.68
    5000   94.27  5005.6    92.7  5009.7    92.7  5015.8   94.84  5021.5   94.63
  5037.3   99.71  5043.1   99.65  5054.4  102.38  5058.9  102.27  5065.3  104.21
  5080.4  104.22  5088.4  102.86    5100   104.3    5204  108.53  5337.5  109.97
  5374.9  114.82  5380.6  117.26  5388.5  116.91  5401.3  118.63  5435.4  120.41
#Mann= 9 ,-1 , 0
  4493.9     .17       0  4766.8     .15       0  4903.4     .17       0
  4905.9     .11       0  4966.6     .04       0  5037.3     .11       0
  5054.4     .15       0    5100     .17       0  5401.3     .11       0
Bank Sta=4966.6,5037.3
XS Rating Curve= 0 ,0
Exp/Cntr=0.3,0.1

Chan Stop Cuts=-1
Use User Specified Reach Order=0
Composite Channel Slope=5

--- Crystal Creek 012.g10 (geometry) ---

Geom Title=Existing Conditions
Program Version=4.10

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
River Reach=Crystal Creek 01,Reach-1

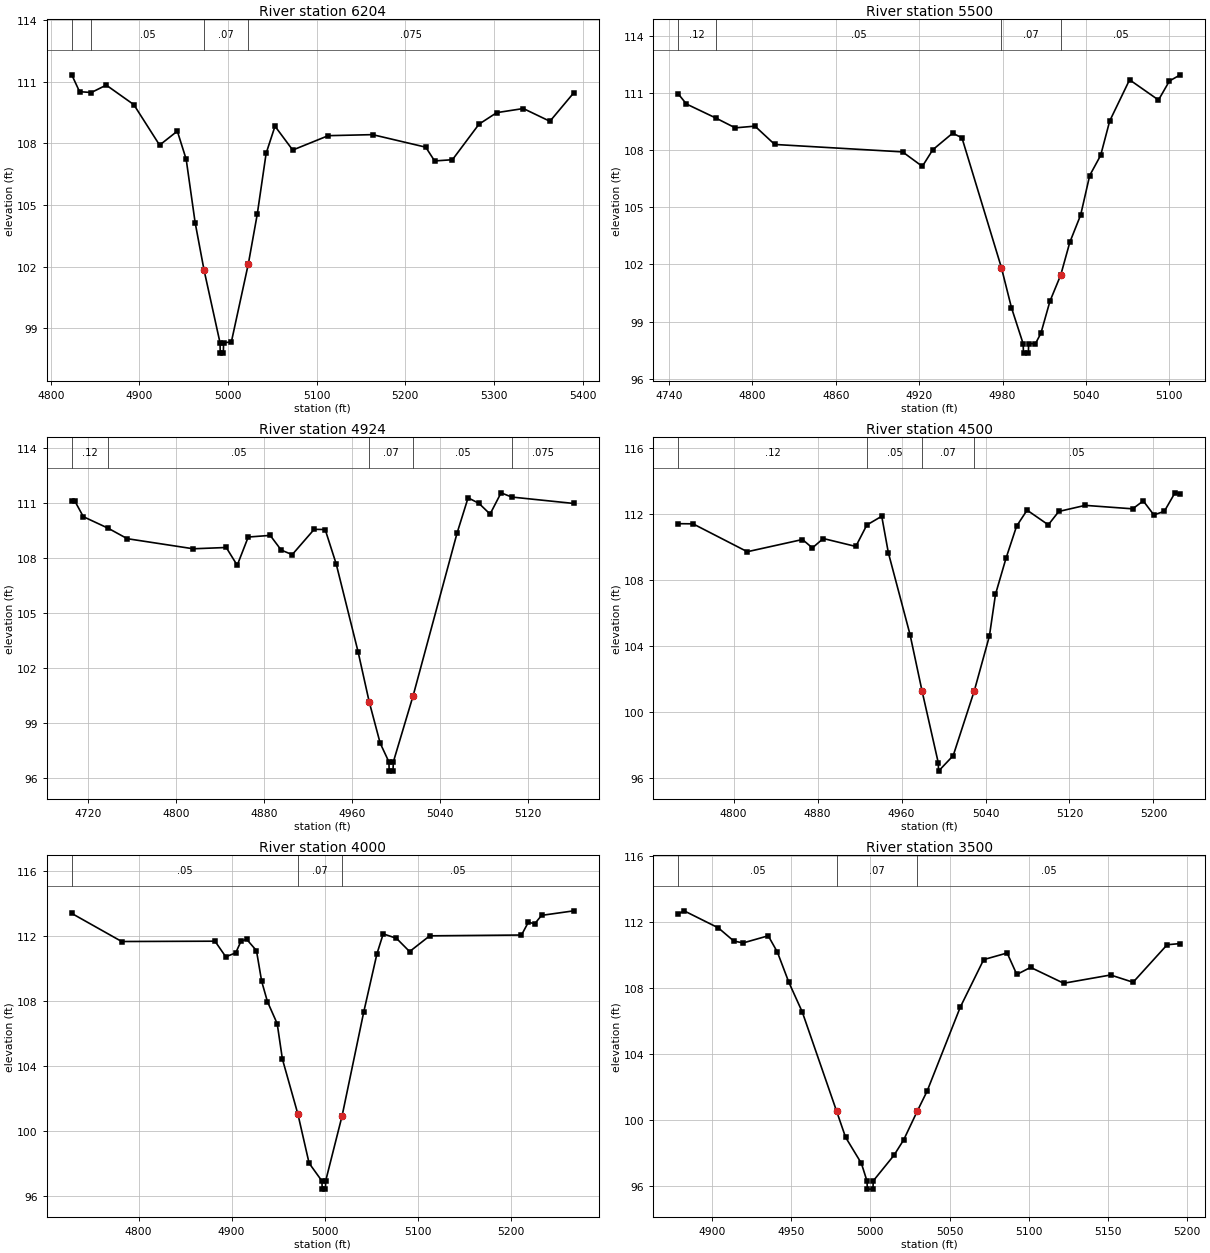
Type RM Length L Ch R = 1 ,6204    ,704,704,704
BEGIN DESCRIPTION:
Crystal Creek 012 12.0
END DESCRIPTION:
XS GIS Cut Line= 3
       3855366.6     10054681.29       3855191.3     10054667.41
      3854800.89     10054681.23
#Sta/Elev= 30
  4823.6  111.34  4832.4  110.52  4845.7  110.48  4862.5  110.84  4893.6  109.89
  4922.7  107.92  4942.7   108.6  4952.7  107.23  4962.8  104.15  4972.8  101.85
  4990.9    98.3  4991.1    97.8  4994.6    97.8  4994.9    98.3  5003.7   98.35
  5022.9  102.16  5032.9  104.56  5042.9  107.52  5052.9  108.84  5072.9  107.68
    5113  108.38    5163  108.43    5223  107.82    5233  107.15  5253.1  107.21
  5283.1  108.94  5303.1   109.5  5333.1   109.7  5363.1  109.08  5390.1  110.47
#Mann= 4 ,-1 , 0
  4823.6     .12       0  4845.7     .05       0  4972.8     .07       0
  5022.9    .075       0
Bank Sta=4972.8,5022.9
XS Rating Curve= 0 ,0
Exp/Cntr=0.3,0.1

Type RM Length L Ch R = 1 ,5500    ,576,576,576
BEGIN DESCRIPTION:
Crystal Creek 012 11.0
END DESCRIPTION:
XS GIS Cut Line= 3
      3855556.76     10054180.44      3855367.72     10054011.84
      3855298.99     10053928.67
#Sta/Elev= 30
  4746.7  110.94  4752.6  110.41  4773.9  109.67  4787.7  109.16  4801.9  109.25
  4816.1  108.29  4908.1   107.9  4922.3  107.14  4929.8  108.01  4944.1  108.88
  4950.8  108.64  4979.2  101.83  4986.4   99.74  4994.8   97.85  4995.1   97.35
  4998.6   97.35  4998.8   97.85  5003.7   97.85  5007.6   98.39  5014.1  100.07
  5021.9  101.45  5028.4  103.16  5036.2  104.59  5042.7  106.66  5050.6  107.72
  5057.1  109.52  5071.4  111.68  5092.2  110.62  5100.1  111.62  5107.9  111.94
#Mann= 4 ,-1 , 0
  4746.7     .12       0  4773.9     .05       0  4979.2     .07       0
  5021.9     .05       0
Bank Sta=4979.2,5021.9
XS Rating Curve= 0 ,0
Exp/Cntr=0.3,0.1

Type RM Length L Ch R = 1 ,4924    ,424,424,424
BEGIN DESCRIPTION:
Crystal Creek 012 10.0
END DESCRIPTION:
XS GIS Cut Line= 2
      3855868.68     10054081.56      3855867.59     10053624.86
#Sta/Elev= 30
  4705.2  111.11  4707.9  111.11  4715.7  110.25  4738.3  109.62  4755.7  109.05
  4815.7   108.5  4845.7  108.57  4855.7   107.6  4865.7  109.14  4885.7  109.23
  4895.7  108.43  4905.7  108.18  4925.7  109.56  4935.7  109.55  4945.7  107.68
  4965.7  102.87  4975.7  100.17  4985.7   97.91  4993.7   96.88  4993.9   96.38
  4997.4   96.38  4997.7   96.88  5015.7  100.49  5055.7  109.36  5065.7  111.28
  5075.7  110.97  5085.7  110.39  5095.7  111.55  5105.4  111.32  5161.9  110.97
#Mann= 5 ,-1 , 0
  4705.2     .12       0  4738.3     .05       0  4975.7     .07       0
  5015.7     .05       0  5105.4    .075       0
Bank Sta=4975.7,5015.7
XS Rating Curve= 0 ,0
Exp/Cntr=0.3,0.1

Type RM Length L Ch R = 1 ,4500    ,500,500,500
BEGIN DESCRIPTION:
Crystal Creek 012 9.0
END DESCRIPTION:
XS GIS Cut Line= 3
      3856213.74     10054134.68      3856278.19     10053890.24
       3856302.7     10053665.97
#Sta/Elev= 30
  4747.2  111.39  4761.3  111.38    4813  109.69  4865.6  110.43    4875  109.92
  4885.4  110.49  4916.4  110.01  4926.9  111.31  4941.1  111.84  4947.4  109.63
  4968.1  104.66 4979.45 101.266    4995   96.89  4995.2   96.39  5009.2   97.33
  5029.3  101.26  5043.7  104.58  5049.5  107.11  5059.5  109.29  5069.6  111.24
  5079.6  112.21  5099.8  111.32  5109.8  112.13    5135   112.5  5180.2  112.29
  5190.3  112.77  5200.4  111.92  5210.4  112.14  5220.5  113.26  5225.6   113.2
#Mann= 4 ,-1 , 0
  4747.2     .12       0  4926.9     .05       0 4979.45     .07       0
  5029.3     .05       0
Bank Sta=4979.45,5029.3
XS Rating Curve= 0 ,0
Exp/Cntr=0.3,0.1

Type RM Length L Ch R = 1 ,4000    ,500,500,500
BEGIN DESCRIPTION:
Crystal Creek 012 8.0
END DESCRIPTION:
XS GIS Cut Line= 3
       3856824.6     10054098.87      3856702.13     10053856.23
      3856504.22     10053675.37
#Sta/Elev= 30
  4728.2  113.39  4781.9  111.66  4882.2  111.68  4893.8  110.72  4904.5  110.96
  4910.1  111.67  4916.2   111.8  4926.8   111.1  4932.4  109.21  4938.6  107.96
  4949.1   106.6  4954.7  104.42  4971.4  101.02  4983.4   98.01  4997.2   96.91
  4997.5   96.41    5001   96.41  5001.2   96.91 5018.88  100.92  5042.2  107.33
  5056.4  110.91  5063.1  112.13  5077.3  111.86  5091.5  111.04  5113.1  112.01
  5211.8  112.06  5219.2  112.85    5226  112.75  5233.4  113.27  5268.1  113.55
#Mann= 3 , 0 , 0
  4728.2     .05       0  4971.4     .07       0 5018.88     .05       0
Bank Sta=4971.4,5018.88
XS Rating Curve= 0 ,0
Exp/Cntr=0.3,0.1

Type RM Length L Ch R = 1 ,3500    ,500,500,500
BEGIN DESCRIPTION:
Crystal Creek 012 7.0
END DESCRIPTION:
XS GIS Cut Line= 3
      3857062.25     10054131.48      3857123.01      10054026.5
      3857235.85     10053866.73
#Sta/Elev= 30
  4878.7  112.47  4882.4  112.66    4904  111.63  4913.8  110.83  4919.7  110.72
  4935.5  111.15  4941.3  110.16  4948.5  108.34    4957  106.54  4978.6  100.56
  4984.3   98.97  4994.3   97.39  4997.8   96.33  4998.1   95.83  5001.6   95.83
  5001.8   96.33  5014.9   97.88    5021   98.81  5029.7  100.57  5035.8  101.76
  5056.7  106.83  5071.5  109.71  5086.3  110.11  5092.4  108.81  5101.1  109.24
    5122  108.28  5151.6  108.78  5165.8  108.34  5187.3  110.61  5195.6  110.68
#Mann= 3 , 0 , 0
  4878.7     .05       0  4978.6     .07       0  5029.7     .05       0
Bank Sta=4978.6,5029.7
XS Rating Curve= 0 ,0
Exp/Cntr=0.3,0.1

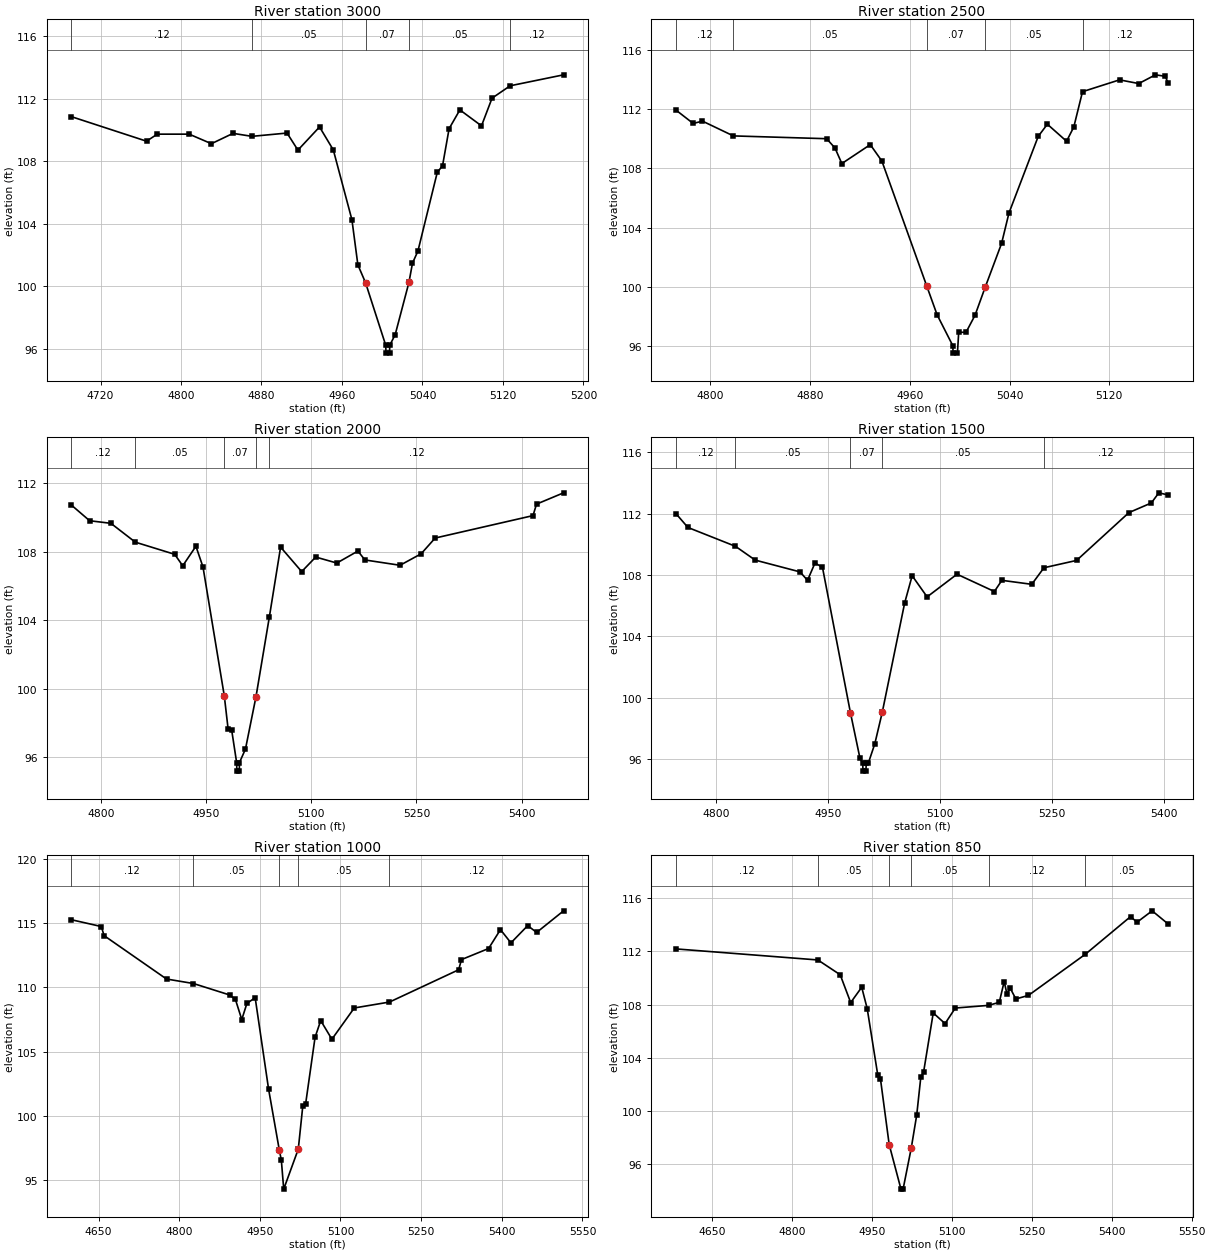
Type RM Length L Ch R = 1 ,3000    ,500,500,500
BEGIN DESCRIPTION:
Crystal Creek 012 6.0
END DESCRIPTION:
XS GIS Cut Line= 3
      3857178.33     10054480.87      3857465.82     10054367.33
      3857633.98     10054302.29
#Sta/Elev= 30
  4690.9  110.85  4765.7  109.28  4776.4  109.73  4808.1  109.73  4830.2  109.12
  4851.7  109.78  4870.5  109.59  4905.4   109.8  4916.2  108.71  4937.7  110.19
  4951.4  108.72  4969.9  104.26  4975.8  101.38 4983.44 100.238  5003.5   96.24
  5003.8   95.74  5007.3   95.74  5007.5   96.24  5012.9   96.92 5026.56 100.254
  5030.1  101.49  5035.5  102.26  5054.7  107.28    5060  107.72  5066.5  110.08
  5077.2  111.28  5098.7  110.26  5109.2  112.03  5127.2  112.82  5180.3  113.52
#Mann= 5 ,-1 , 0
  4690.9     .12       0  4870.5     .05       0 4983.44     .07       0
 5026.56     .05       0  5127.2     .12       0
Bank Sta=4983.44,5026.56
XS Rating Curve= 0 ,0
Exp/Cntr=0.3,0.1

Type RM Length L Ch R = 1 ,2500    ,500,500,500
BEGIN DESCRIPTION:
Crystal Creek 012 5.0
END DESCRIPTION:
XS GIS Cut Line= 3
      3857577.68     10055010.33      3857675.24      10054804.7
      3857763.01     10054662.39
#Sta/Elev= 30
  4772.4  111.95  4786.3  111.04  4793.7   111.2  4818.5   110.2  4893.3  110.01
    4900  109.38  4905.5  108.33  4928.3  109.61  4937.6   108.5  4973.7  100.02
  4981.9    98.1  4994.5   96.01  4994.7   95.51  4998.2   95.51  4999.2   96.92
  5005.1   96.92  5012.3   98.07 5020.45  99.965  5033.6  102.93  5039.5  104.98
    5063  110.17  5070.3  110.99  5085.7  109.84  5091.5   110.8  5098.5  113.19
  5128.2  113.99  5143.6  113.74    5157  114.33  5164.9  114.23  5167.2  113.76
#Mann= 5 ,-1 , 0
  4772.4     .12       0  4818.5     .05       0  4973.7     .07       0
 5020.45     .05       0  5098.5     .12       0
Bank Sta=4973.7,5020.45
XS Rating Curve= 0 ,0
Exp/Cntr=0.3,0.1

Type RM Length L Ch R = 1 ,2000    ,500,500,500
BEGIN DESCRIPTION:
Crystal Creek 012 4.0
END DESCRIPTION:
XS GIS Cut Line= 3
      3857631.92     10055203.52      3857871.74     10055238.73
      3858330.67     10055268.62
#Sta/Elev= 30
  4757.6  110.73  4783.8  109.81  4814.1  109.66  4848.9  108.56  4905.1  107.85
  4916.6  107.18  4935.4  108.32  4945.5  107.11  4975.9   99.58  4981.3   97.66
  4986.3   97.62  4993.5   95.69  4993.8   95.19  4997.3   95.19  4997.5   95.69
  5006.1   96.48 5021.15  99.545  5040.2   104.2  5056.2  108.27  5086.3  106.84
  5106.3  107.69  5136.4  107.34  5166.5  108.04  5176.5  107.52  5226.6  107.21
  5256.7  107.88  5276.7   108.8  5416.3  110.11  5421.3  110.78  5459.9  111.44
#Mann= 5 ,-1 , 0
  4757.6     .12       0  4848.9     .05       0  4975.9     .07       0
 5021.15     .05       0  5040.2     .12       0
Bank Sta=4975.9,5021.15
XS Rating Curve= 0 ,0
Exp/Cntr=0.3,0.1

Type RM Length L Ch R = 1 ,1500    ,500,500,500
BEGIN DESCRIPTION:
Crystal Creek 012 3.0
END DESCRIPTION:
XS GIS Cut Line= 3
       3857591.8      10055735.2      3857845.28     10055738.03
      3858250.36     10055741.71
#Sta/Elev= 30
  4746.5  112.01  4762.6   111.1  4826.2  109.87  4852.6  108.97  4912.6   108.2
  4922.6  107.65  4932.6  108.78  4942.6   108.5 4980.03  99.009  4992.6   96.08
  4996.5    95.7  4996.8    95.2  5000.8    95.2  5001.1    95.7  5003.8    95.7
  5012.6   96.98  5022.6   99.04  5052.6  106.18  5062.6  107.95  5082.6  106.57
  5122.6  108.05  5172.6  106.92  5182.6  107.65  5222.6  107.39  5238.9  108.47
  5282.6  108.95  5352.6  112.07  5382.6   112.7  5392.6  113.36  5405.1  113.22
#Mann= 5 ,-1 , 0
  4746.5     .12       0  4826.2     .05       0 4980.03     .07       0
  5022.6     .05       0  5238.9     .12       0
Bank Sta=4980.03,5022.6
XS Rating Curve= 0 ,0
Exp/Cntr=0.3,0.1

Type RM Length L Ch R = 1 ,1000    ,150,150,150
BEGIN DESCRIPTION:
Crystal Creek 012 2.0
END DESCRIPTION:
XS GIS Cut Line= 3
      3857442.14     10056095.88      3857817.17     10056236.98
      3858311.89     10056379.72
#Sta/Elev= 30
  4599.3  115.25  4655.1  114.72  4660.4  114.01  4776.4  110.64  4826.5  110.29
  4893.9   109.4  4904.6  109.05  4916.4  107.49  4925.9  108.74  4941.3  109.19
  4966.2   102.1 4986.11  97.372    4990   96.55  4994.4   94.31  5021.5   97.42
  5029.8  100.74    5035  100.89  5052.7  106.11  5063.2  107.41    5084  105.96
  5125.6  108.39  5191.1  108.85  5319.8  111.36    5325  112.15  5375.4  113.01
  5397.5  114.48    5417  113.45  5448.2  114.79  5464.8  114.26  5514.9  115.94
#Mann= 5 ,-1 , 0
  4599.3     .12       0  4826.5     .05       0 4986.11     .07       0
  5021.5     .05       0  5191.1     .12       0
Bank Sta=4986.11,5021.5
XS Rating Curve= 0 ,0
Exp/Cntr=0.3,0.1

Type RM Length L Ch R = 1 ,850     ,462,462,462
BEGIN DESCRIPTION:
Mapping XS 1b18a99a
END DESCRIPTION:
XS GIS Cut Line= 2
      3857390.38     10056279.06      3858284.58     10056513.01
#Sta/Elev= 30
  4581.6  112.18  4848.2  111.35  4890.1  110.24  4909.8  108.15  4930.5   109.3
  4940.8   107.7  4960.6  102.72  4965.7  102.42  4982.1   97.48  5004.2   94.14
  5008.2   94.14  5023.5   97.22  5033.8   99.71  5041.4  102.53  5046.6  102.91
  5064.8  107.37    5087  106.57  5106.2  107.74  5168.8  107.94  5188.8  108.17
    5198  109.73  5203.1  108.81  5209.5  109.22  5219.9  108.42  5243.6  108.69
  5350.4  111.78  5435.4  114.61  5447.3  114.18  5475.8  115.04  5505.9  114.05
#Mann= 6 ,-1 , 0
  4581.6     .12       0  4848.2     .05       0  4982.1     .07       0
  5023.5     .05       0  5168.8     .12       0  5350.4     .05       0
Bank Sta=4982.1,5023.5
XS Rating Curve= 0 ,0
Exp/Cntr=0.3,0.1

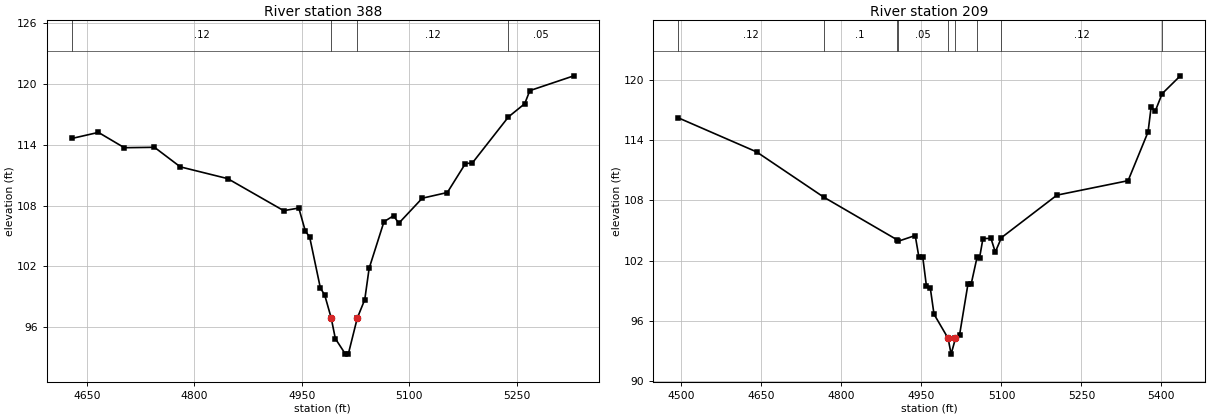
Type RM Length L Ch R = 1 ,388     ,179,179,179
BEGIN DESCRIPTION:
Mapping XS 4b6162b2
END DESCRIPTION:
XS GIS Cut Line= 3
      3857385.23     10056633.25      3857692.51     10056836.36
      3858014.17     10056750.76
#Sta/Elev= 30
  4628.6  114.62  4665.8  115.22    4702  113.71  4744.1  113.75  4780.2  111.82
  4846.4  110.66  4924.6   107.5  4945.7  107.76  4954.8  105.48  4960.8  104.91
  4975.8   99.87  4981.8   99.19  4990.9   96.92  4996.7   94.88  5010.8   93.35
  5014.8   93.35 5027.32  96.897  5037.8   98.73  5043.9  101.81  5064.6  106.41
    5078     107  5085.3  106.26  5118.1  108.73  5153.1  109.29  5178.4  112.15
    5188   112.2  5238.5  116.75  5261.2  118.05  5268.3  119.34  5329.8   120.8
#Mann= 4 ,-1 , 0
  4628.6     .12       0  4990.9     .07       0 5027.32     .12       0
  5238.5     .05       0
Bank Sta=4990.9,5027.32
XS Rating Curve= 0 ,0
Exp/Cntr=0.3,0.1

Type RM Length L Ch R = 1 ,209     ,0,0,0
BEGIN DESCRIPTION:
Crystal Creek 012 1.0
END DESCRIPTION:
XS GIS Cut Line= 3
       3857347.1     10056644.07      3857691.27     10057015.13
      3858068.48     10056797.68
#Sta/Elev= 30
  4493.9  116.23  4640.7  112.84  4766.8  108.33  4903.4  104.11  4905.9  103.93
  4938.3  104.51  4945.1  102.39  4952.5  102.33  4959.3   99.48  4966.6   99.27
  4973.5   96.68    5000   94.27  5005.6    92.7  5013.8  94.274  5021.5   94.63
  5037.3   99.71  5043.1   99.65  5054.4  102.38  5058.9  102.27  5065.3  104.21
  5080.4  104.22  5088.4  102.86    5100   104.3    5204  108.53  5337.5  109.97
  5374.9  114.82  5380.6  117.26  5388.5  116.91  5401.3  118.63  5435.4  120.41
#Mann= 9 ,-1 , 0
  4493.9     .12       0  4766.8      .1       0  4903.4     .12       0
  4905.9     .05       0    5000     .07       0  5013.8     .05       0
  5054.4      .1       0    5100     .12       0  5401.3     .05       0
Bank Sta=5000,5013.8
XS Rating Curve= 0 ,0
Exp/Cntr=0.3,0.1