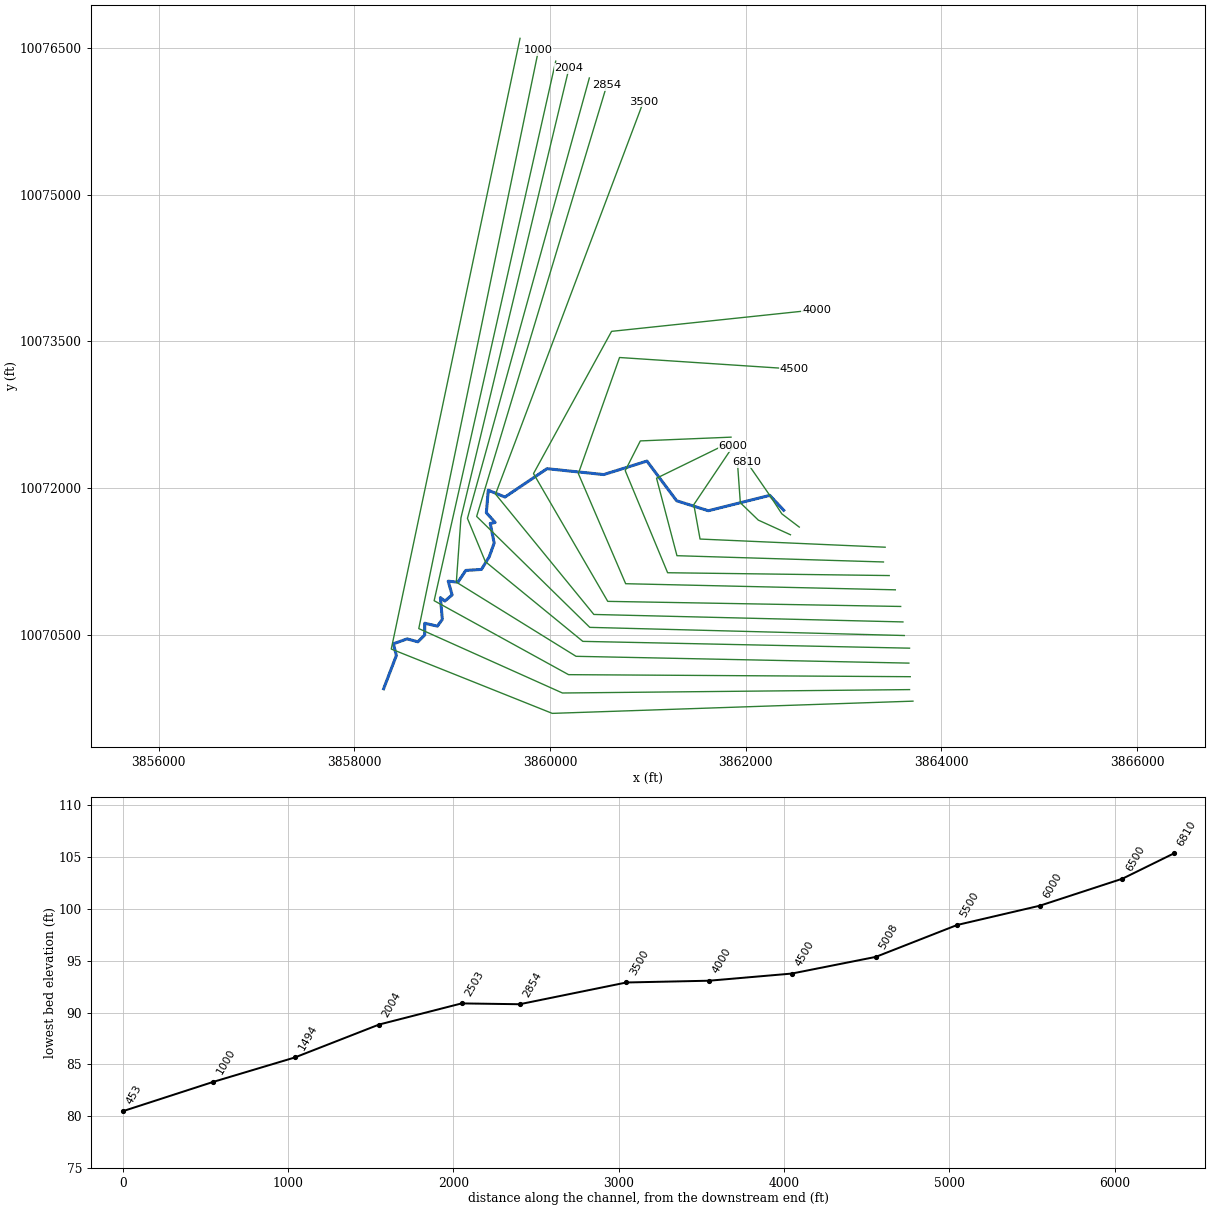
--- Crystal Creek 013.prj (project) ---

Proj Title=Crystal Creek 013 Base Level Engineering
Current Plan=p01
Default Exp/Contr=0.3,0.1
English Units
Geom File=g01
Flow File=f01
Flow File=f02
Plan File=p01
Y Axis Title=Elevation
X Axis Title(PF)=Main Channel Distance
X Axis Title(XS)=Station
BEGIN DESCRIPTION:
Crystal Creek 013
END DESCRIPTION:
DSS Export Rating Curves= 0
DSS Export Rating Curve Sorted= 0
DSS Export Volume Flow Curves= 0
DXF OffsetX= 0
DXF OffsetY= 0
DXF ScaleX= 1
DXF ScaleY= 10

--- Crystal Creek 013.p01 (plan) ---

Plan Title=Multiple Run
Short Identifier=Multiple
Geom File=g01
Flow File=f01
Subcritical Flow
K Sum by GR= 0
Std Step Tol= 0.01
Critical Tol= 0.01
Num of Std Step Trials= 20
Max Error Tol= 0.3
Flow Tol Ratio= 0.001
Split Flow NTrial= 30
Split Flow Tol= 0.02
Split Flow Ratio= 0.02
Log Output Level= 0
Friction Slope Method= 1
Unsteady Friction Slope Method= 2
Unsteady Bridges Friction Slope Method= 1
Parabolic Critical Depth
Global Vel Dist=  1 , 1 , 1
Global Log Level= 0
CheckData=True
Encroach Param= -1, 0, 0, 0
BEGIN DESCRIPTION:
Multiple Run
END DESCRIPTION:

--- Crystal Creek 013.f01 (steady flow) ---

Flow Title=Multiple
Program Version=4.10
Number of Profiles= 7
Profile Names=10-year,25-year,50-year,1pct_min,100-year,1pct_plu,500-year
River Rch & RM=Crystal Creek 01,Reach-1         ,6810
    1041    1441    1977     891    2691    8127    5157
River Rch & RM=Crystal Creek 01,Reach-1         ,2854
    1047    1442    1972     885    2674    8075    5084
Boundary for River Rch & Prof#=Crystal Creek 01,Reach-1         , 1
Up Type= 0
Dn Type= 3
Dn Slope=0.005
Boundary for River Rch & Prof#=Crystal Creek 01,Reach-1         , 2
Up Type= 0
Dn Type= 3
Dn Slope=0.005
Boundary for River Rch & Prof#=Crystal Creek 01,Reach-1         , 3
Up Type= 0
Dn Type= 3
Dn Slope=0.005
Boundary for River Rch & Prof#=Crystal Creek 01,Reach-1         , 4
Up Type= 0
Dn Type= 3
Dn Slope=0.005
Boundary for River Rch & Prof#=Crystal Creek 01,Reach-1         , 5
Up Type= 0
Dn Type= 3
Dn Slope=0.005
Boundary for River Rch & Prof#=Crystal Creek 01,Reach-1         , 6
Up Type= 0
Dn Type= 3
Dn Slope=0.005
Boundary for River Rch & Prof#=Crystal Creek 01,Reach-1         , 7
Up Type= 0
Dn Type= 3
Dn Slope=0.005
DSS Import GetInterval= 0
DSS Import GetPeak= 0
DSS Import FillOption= 0

--- Crystal Creek 013.f02 (steady flow) ---

Flow Title=Orig_BLE_Flow
Program Version=4.10
Number of Profiles= 7
Profile Names=10-year,25-year,50-year,1pct_min,100-year,1pct_plu,500-year
River Rch & RM=Crystal Creek 01,Reach-1         ,6810
    1041    1413    1719     686    2070    6253    2998
River Rch & RM=Crystal Creek 01,Reach-1         ,2854
    1047    1414    1715     681    2057    6212    2956
Boundary for River Rch & Prof#=Crystal Creek 01,Reach-1         , 1
Up Type= 0
Dn Type= 3
Dn Slope=0.005
Boundary for River Rch & Prof#=Crystal Creek 01,Reach-1         , 2
Up Type= 0
Dn Type= 3
Dn Slope=0.005
Boundary for River Rch & Prof#=Crystal Creek 01,Reach-1         , 3
Up Type= 0
Dn Type= 3
Dn Slope=0.005
Boundary for River Rch & Prof#=Crystal Creek 01,Reach-1         , 4
Up Type= 0
Dn Type= 3
Dn Slope=0.005
Boundary for River Rch & Prof#=Crystal Creek 01,Reach-1         , 5
Up Type= 0
Dn Type= 3
Dn Slope=0.005
Boundary for River Rch & Prof#=Crystal Creek 01,Reach-1         , 6
Up Type= 0
Dn Type= 3
Dn Slope=0.005
Boundary for River Rch & Prof#=Crystal Creek 01,Reach-1         , 7
Up Type= 0
Dn Type= 3
Dn Slope=0.005
DSS Import GetInterval= 0
DSS Import GetPeak= 0
DSS Import FillOption= 0

--- Crystal Creek 013.g01 (geometry) ---

Geom Title=Existing Conditions
Program Version=4.10

River Reach=Crystal Creek 01,Reach-1
Reach XY= 30
      3862388.24     10071772.04      3862246.05     10071924.13
      3861617.99       10071767.      3861293.55     10071868.99
      3860990.08      10072274.7      3860548.24     10072136.86
      3859968.24     10072196.86      3859538.24     10071906.86
      3859368.24     10071976.86      3859348.24     10071746.86
      3859438.24     10071646.86      3859388.24     10071636.86
      3859428.24     10071436.86      3859378.24     10071296.86
      3859298.24     10071166.86      3859138.24     10071156.86
      3859058.24     10071036.86      3858958.24     10071046.86
      3858998.24     10070906.86       3858925.2     10070843.83
      3858878.73     10070878.26      3858898.24     10070656.86
      3858848.24     10070586.86      3858718.24     10070616.86
      3858718.24     10070496.86      3858648.24     10070426.86
      3858538.24     10070456.86      3858398.24     10070406.86
      3858428.24     10070286.86      3858298.24     10069946.86

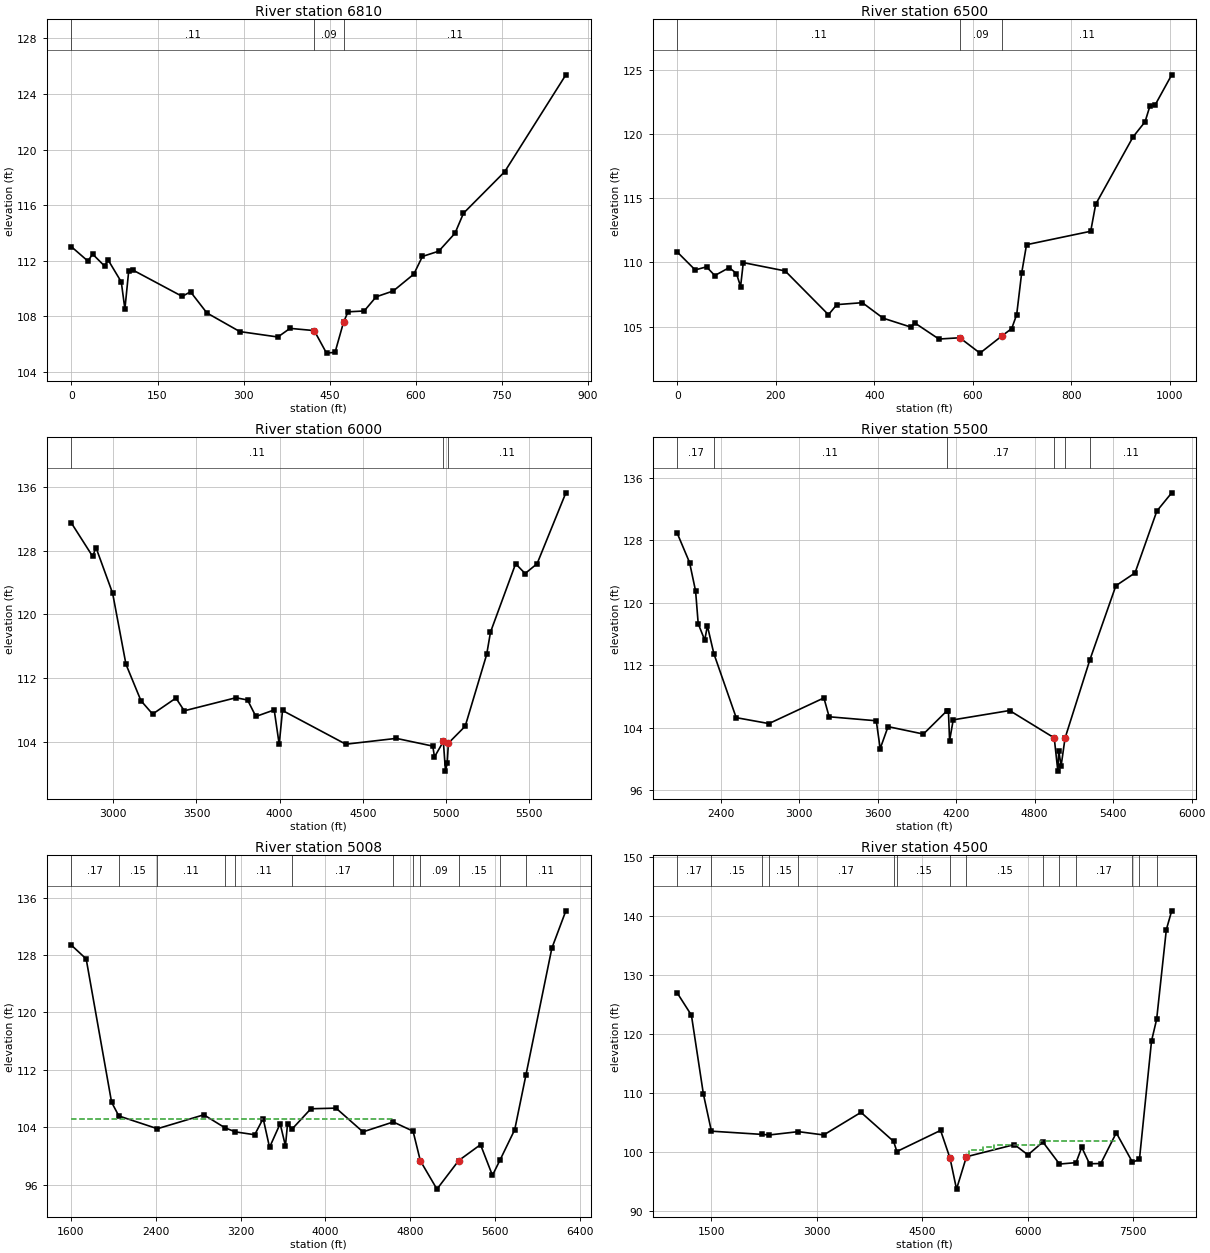
Type RM Length L Ch R = 1 ,6810    ,311,311,311
XS GIS Cut Line= 4
      3862547.37     10071599.95      3862369.14     10071735.36
      3862246.05     10071924.13      3862011.08     10072264.57
#Sta/Elev= 30
       0  113.01    28.7  111.98      37  112.48    57.8  111.62    64.1  112.05
    86.9  110.48    93.2  108.53    99.9  111.29   107.7  111.32     193  109.44
   207.5  109.77     236  108.25   293.3  106.91   359.7  106.52   380.8  107.14
     423  106.98   444.4  105.36   459.3  105.42   474.1  107.59   481.9  108.33
     510  108.39   530.9  109.41   560.7  109.83   596.5  111.04   611.4  112.31
   639.9  112.69   668.2  113.98     683  115.42   754.7   118.4   861.3  125.37
#Mann= 3 , 0 , 0
       0     .11       0     423     .09       0   474.1     .11       0
Bank Sta=423,474.1
XS Rating Curve= 0 ,0
Exp/Cntr=0.3,0.1

Type RM Length L Ch R = 1 ,6500    ,500,500,500
XS GIS Cut Line= 4
      3862457.23     10071521.51      3862128.59     10071671.27
      3861944.93     10071848.78      3861917.33     10072235.06
#Sta/Elev= 30
       0  110.82    36.4  109.42    59.5  109.66    76.2  108.98   105.6   109.6
   120.2  109.14   128.6  108.12   134.1  109.99   219.1  109.34     307  105.92
     324  106.71   375.8  106.86     418  105.65   474.6  104.95   481.8  105.29
   531.2  104.02   573.6  104.12   614.6  102.92     659  104.26     679  104.84
   689.1  105.93   699.1  109.15   709.1  111.39   839.4  112.44   849.5  114.55
   925.5  119.82   949.7  120.99   959.7  122.24   969.8  122.28  1003.8  124.66
#Mann= 3 , 0 , 0
       0     .11       0   573.6     .09       0     659     .11       0
Bank Sta=573.6,659
XS Rating Curve= 0 ,0
Exp/Cntr=0.3,0.1

Type RM Length L Ch R = 1 ,6000    ,500,500,500
BEGIN DESCRIPTION:
Crystal Creek 013 12.0
END DESCRIPTION:
XS GIS Cut Line= 4
      3863425.55      10071394.2      3861533.18     10071477.53
      3861469.48     10071829.41       3861870.9     10072427.13
#Sta/Elev= 30
  2748.2  131.45    2876  127.26    2896  128.37  2996.1  122.63  3076.2  113.72
  3166.3  109.15  3236.4  107.47  3376.5  109.48  3426.6  107.88  3736.9  109.52
  3806.9  109.24    3857  107.17  3967.1  107.99  3997.1  103.68  4017.1  107.92
  4397.5  103.69  4701.1  104.42  4920.1  103.45  4930.5  102.09  4983.7  104.03
  4996.6  100.31    5007  101.36    5014  103.82  5115.1  105.95  5244.1  114.95
    5267  117.75  5418.1  126.34  5475.1  125.11  5547.1  126.34    5720  135.24
#Mann= 3 , 0 , 0
  2748.2     .11       0  4983.7     .09       0    5014     .11       0
#XS Ineff= 2 , 0
       0  4017.1  107.92               0
Permanent Ineff=
       F       F
Bank Sta=4983.7,5014
XS Rating Curve= 0 ,0
Exp/Cntr=0.3,0.1

Type RM Length L Ch R = 1 ,5500    ,492,492,492
BEGIN DESCRIPTION:
Crystal Creek 013 11.0
END DESCRIPTION:
XS GIS Cut Line= 4
      3863408.09     10071243.24      3861297.07     10071307.39
      3861088.39     10072099.48      3861849.85     10072471.53
#Sta/Elev= 30
  2068.9  128.87  2163.1  125.13  2209.2  121.48  2229.2   117.3  2279.2   115.2
  2299.2  117.04  2348.5  113.49  2519.3  105.29  2769.5  104.53  3189.7  107.81
  3229.7   105.4  3589.8  104.89  3619.9  101.33  3679.9  104.14    3950  103.19
  4128.4  106.14  4141.2  106.17  4150.1  102.34    4178  105.01  4608.7   106.2
  4949.9   102.7  4977.4   98.45  4984.3  101.05  5002.5   99.13  5032.5  102.67
  5221.3  112.64  5420.9  122.16  5567.2   123.8    5734  131.71  5847.5  134.04
#Mann= 6 ,-1 , 0
  2068.9     .17       0  2348.5     .11       0  4128.4     .17       0
  4949.9     .09       0  5032.5     .17       0  5221.3     .11       0
#XS Ineff= 2 , 0
       0  4608.7   106.2               0
Permanent Ineff=
       F       F
Bank Sta=4949.9,5032.5
XS Rating Curve= 0 ,0
Exp/Cntr=0.3,0.1

Type RM Length L Ch R = 1 ,5008    ,508,508,508
BEGIN DESCRIPTION:
Crystal Creek 013 10.0
END DESCRIPTION:
XS GIS Cut Line= 5
      3863467.05     10071104.36      3861201.59      10071133.2
      3860768.24     10072176.86      3860922.51     10072480.86
      3861849.91     10072519.29
#Sta/Elev= 30
  1604.3  129.37  1743.8  127.46  1983.5  107.48  2051.8  105.57  2415.8  103.79
  2853.6  105.73  3052.9  103.92  3151.6  103.35  3333.6  102.95  3413.6  105.21
  3473.7  101.19  3573.7  104.49  3623.7  101.39  3643.7  104.51  3682.8  103.69
  3863.7  106.57  4100.9  106.66  4354.9  103.35  4640.7  104.73  4827.6  103.45
  4896.3   99.32    5053   95.37  5258.299.35243  5464.1  101.57  5576.4   97.29
  5648.2   99.43  5786.6  103.65  5891.7  111.22  6136.9  128.95  6269.1  134.16
#Mann= 12 ,-1 , 0
  1604.3     .17       0  2051.8     .15       0  2415.8     .11       0
  3052.9     .15       0  3151.6     .11       0  3682.8     .17       0
  4640.7     .15       0  4827.6     .17       0  4896.3     .09       0
  5258.2     .15       0  5648.2     .17       0  5891.7     .11       0
#XS Ineff= 2 , 0
       0  4626.9  105.18               0
Permanent Ineff=
       F       F
Bank Sta=4896.3,5258.2
XS Rating Curve= 0 ,0
Exp/Cntr=0.3,0.1

Type RM Length L Ch R = 1 ,4500    ,500,500,500
BEGIN DESCRIPTION:
Crystal Creek 013 9.0
END DESCRIPTION:
XS GIS Cut Line= 5
      3863529.53     10070958.52      3860772.62     10071021.02
      3860289.08     10072146.86      3860710.12     10073333.52
      3862493.89     10073215.53
#Sta/Elev= 30
  1017.1  126.93  1218.8  123.17  1388.9  109.84  1502.8  103.56  2227.3  103.01
    2326  102.92  2739.5  103.48  3099.3  102.92  3629.4  106.74  4093.5  101.83
  4139.4  100.12  4761.1  103.69  4895.7   98.97  4987.6   93.76  5128.7   99.24
  5810.9  101.29  6002.7   99.55  6215.7  101.73  6451.5      98  6686.8   98.24
    6768  100.83  6878.2   98.05  7038.6   98.09    7259  103.28  7489.3    98.3
  7588.4   98.82  7760.1  118.82  7832.8  122.48  7970.6  137.65  8046.8  140.82
#Mann= 15 ,-1 , 0
  1017.1     .17       0  1502.8     .15       0  2227.3     .11       0
    2326     .15       0  2739.5     .17       0  4093.5     .11       0
  4139.4     .15       0  4895.7     .09       0  5128.7     .15       0
  6215.7     .17       0  6451.5     .15       0  6686.8     .17       0
  7489.3     .15       0  7588.4     .17       0  7832.8     .11       0
#XS Ineff= 6 ,-1
  4761.1  3795.3  103.69  5164.9  5370.3   100.3  5370.3  5519.4  100.81
  5519.4  6177.3  101.17  6177.3    7259  101.85    7259  7649.9  103.28
Permanent Ineff=
       F       F       F       F       F       F
Bank Sta=4895.7,5128.7
XS Rating Curve= 0 ,0
Exp/Cntr=0.3,0.1

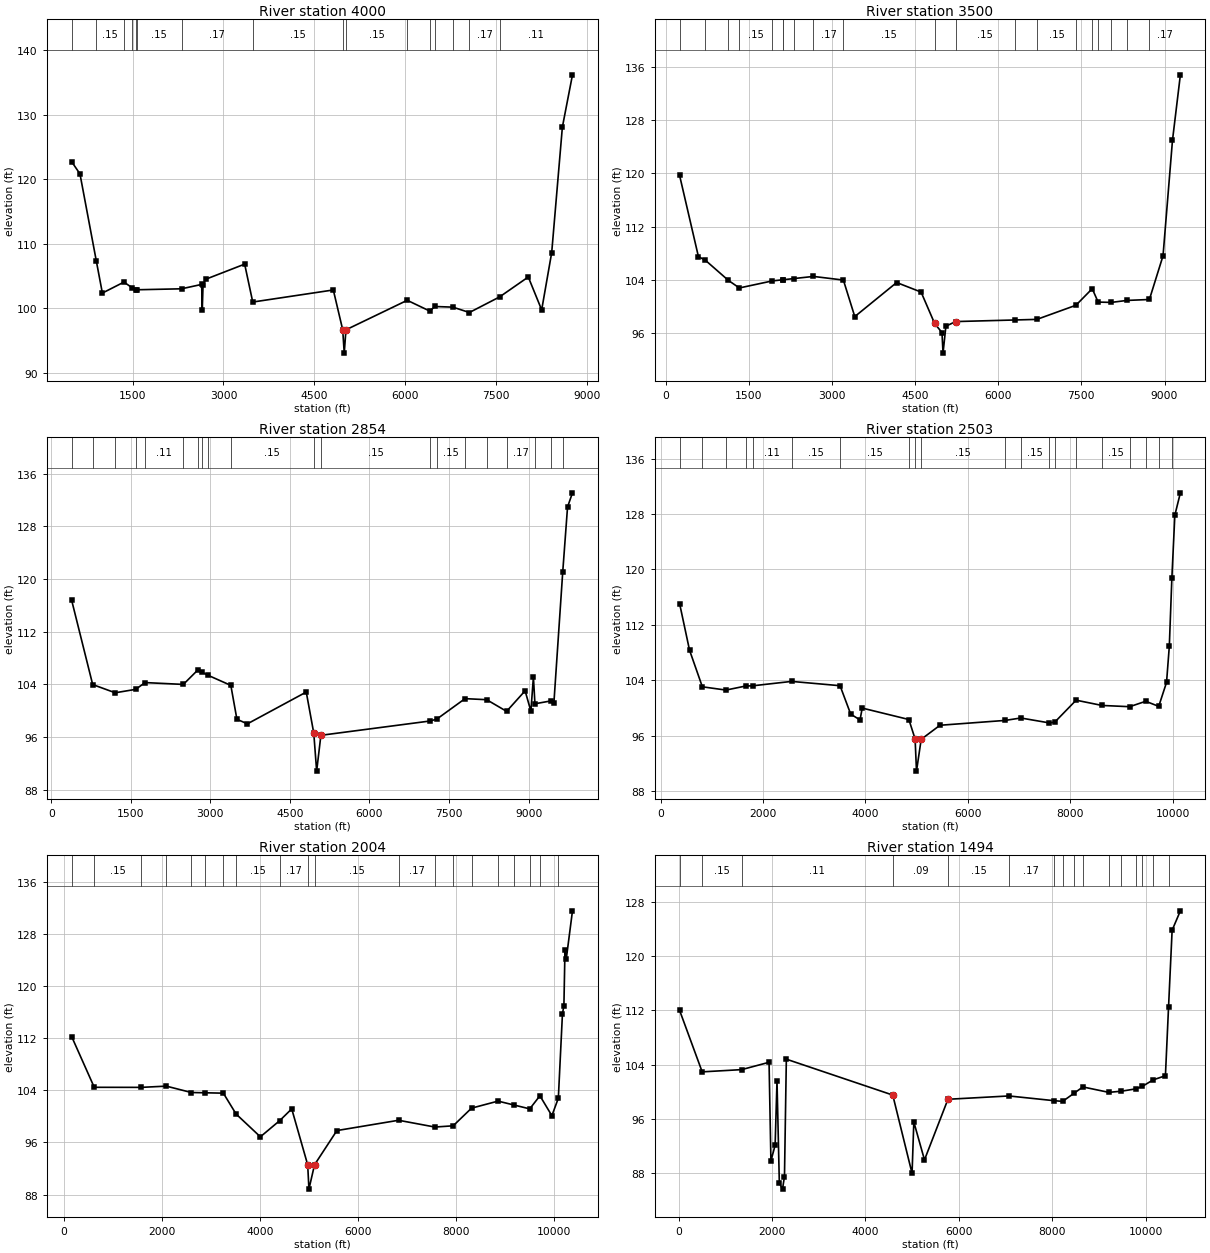
Type RM Length L Ch R = 1 ,4000    ,500,500,500
BEGIN DESCRIPTION:
Crystal Creek 013 8.0
END DESCRIPTION:
XS GIS Cut Line= 5
      3863584.25     10070788.38      3860589.46     10070840.47
      3859830.51     10072146.86      3860628.53     10073600.88
      3862723.86     10073822.13
#Sta/Elev= 30
   493.9   122.7   630.3  120.82     900  107.36  1000.4  102.37  1357.1  104.07
  1493.1  103.18  1555.6  102.78  1569.8  102.88  2308.3  103.03  2640.6  103.71
  2650.6   99.82  2663.5  103.65  2710.6  104.52  3350.7  106.85  3484.2  100.98
  4815.1  102.85 4970.4796.67746  4995.5   93.07  5023.8   96.68  6036.2  101.25
  6409.1   99.58  6493.1  100.29  6789.5  100.19  7062.8   99.36  7561.3  101.77
  8035.6  104.86  8256.8   99.76  8422.5  108.65  8598.7  128.07  8765.6  136.16
#Mann= 16 ,-1 , 0
   493.9     .17       0     900     .15       0  1357.1     .11       0
  1493.1     .15       0  1555.6     .11       0  1569.8     .15       0
  2308.3     .17       0  3484.2     .15       0 4970.47     .09       0
  5023.8     .15       0  6036.2     .17       0  6409.1     .15       0
  6493.1     .17       0  6789.5     .15       0  7062.8     .17       0
  7561.3     .11       0
Bank Sta=4970.47,5023.8
XS Rating Curve= 0 ,0
Exp/Cntr=0.3,0.1

Type RM Length L Ch R = 1 ,3500    ,646,646,646
BEGIN DESCRIPTION:
Crystal Creek 013 7.0
END DESCRIPTION:
XS GIS Cut Line= 4
      3863607.21     10070630.24      3860447.46     10070706.63
      3859442.34     10071936.86      3860953.72     10075947.86
#Sta/Elev= 30
   250.7   119.7   590.2  107.46   715.7  106.91  1131.3  103.87  1328.8  102.73
  1921.3  103.79  2116.5  103.97  2118.8  103.97  2316.4  104.15  2666.2  104.47
  3205.8  103.92  3411.4   98.41    4167  103.55  4607.8  102.11 4852.3897.37112
  4984.7      96  5003.9    92.9  5055.4   96.96  5231.3   97.66  6299.3    97.9
  6697.2   97.99  7401.5  100.12  7695.8  102.62  7802.5   100.6    8039  100.55
  8322.2  100.85  8727.4  100.99  8973.2  107.58  9143.8     125  9286.3  134.88
#Mann= 20 ,-1 , 0
   250.7     .17       0   715.7     .15       0  1131.3     .11       0
  1328.8     .15       0  1921.3     .11       0  2116.5     .15       0
  2118.8     .17       0  2316.4     .11       0  2666.2     .17       0
  3205.8     .15       0 4852.38     .09       0  5231.3     .15       0
  6299.3     .17       0  6697.2     .15       0  7401.5     .17       0
  7695.8     .11       0  7802.5     .15       0    8039     .17       0
  8322.2     .15       0  8727.4     .17       0
Bank Sta=4852.38,5231.3
XS Rating Curve= 0 ,0
Exp/Cntr=0.3,0.1

Type RM Length L Ch R = 1 ,2854    ,351,351,351
BEGIN DESCRIPTION:
Crystal Creek 013 6.0
END DESCRIPTION:
XS GIS Cut Line= 4
       3863621.1     10070491.35       3860405.8     10070574.69
       3859249.2      10071708.8      3860579.37     10076116.21
#Sta/Elev= 30
   386.5  116.72   781.9  103.95  1206.3   102.7  1592.2  103.22  1769.6  104.25
  2490.8  103.97  2761.1  106.14  2843.9  105.82  2950.2  105.38  3386.3  103.82
  3500.8   98.68  3697.9   97.98    4808  102.81  4949.5   96.58    5004    90.8
  5083.9   96.24    7148   98.42  7270.3   98.71  7801.6  101.81  8209.2  101.65
  8584.5   99.88  8933.3     103  9042.7    99.9  9089.9  105.11  9118.8  101.03
  9430.9  101.48  9476.4  101.19  9642.2  120.98  9733.5  130.92  9826.5  133.07
#Mann= 20 ,-1 , 0
   386.5     .17       0   781.9     .15       0  1206.3     .11       0
  1592.2     .15       0  1769.6     .11       0  2490.8     .15       0
  2761.1     .17       0  2843.9     .11       0  2950.2     .17       0
  3386.3     .15       0  4949.5     .09       0  5083.9     .15       0
    7148     .17       0  7270.3     .15       0  7801.6     .17       0
  8209.2     .15       0  8584.5     .17       0  9118.8     .15       0
  9430.9     .17       0  9642.2     .11       0
Bank Sta=4949.5,5083.9
XS Rating Curve= 0 ,0
Exp/Cntr=0.3,0.1

Type RM Length L Ch R = 1 ,2503    ,499,499,499
BEGIN DESCRIPTION:
Crystal Creek 013 5.0
END DESCRIPTION:
XS GIS Cut Line= 5
      3863675.01     10070362.01       3860334.7     10070431.46
      3859338.24     10071246.86      3859155.01     10071688.75
      3860401.33     10076191.48
#Sta/Elev= 30
   371.4  115.06   565.2  108.34   815.7  103.05  1276.5  102.58  1659.1  103.16
  1803.1   103.2    2558  103.83  3504.7  103.21  3712.4   99.11  3894.6   98.27
  3937.6   99.98  4848.3   98.33 4970.3195.52258  4997.3   90.88  5089.1   95.47
  5455.9    97.5  6729.3    98.2  7034.3   98.55  7592.3   97.84  7697.4   97.95
  8114.5  101.12  8619.8  100.36  9159.6  100.18    9473  100.96  9727.6  100.23
  9880.2  103.69  9934.2  108.89  9984.6  118.81 10042.3  127.82 10150.4  131.05
#Mann= 20 ,-1 , 0
   371.4     .11       0   815.7     .15       0  1276.5     .11       0
  1659.1     .15       0  1803.1     .11       0    2558     .15       0
  3504.7     .15       0  4848.3     .17       0 4970.31     .09       0
  5089.1     .15       0  6729.3     .17       0  7034.3     .15       0
  7592.3     .17       0  7697.4     .15       0  8114.5     .17       0
  8619.8     .15       0  9159.6     .17       0    9473     .15       0
  9727.6     .17       0  9984.6     .11       0
Bank Sta=4970.31,5089.1
XS Rating Curve= 0 ,0
Exp/Cntr=0.3,0.1

Type RM Length L Ch R = 1 ,2004    ,510,510,510
BEGIN DESCRIPTION:
Crystal Creek 013 4.0
END DESCRIPTION:
XS GIS Cut Line= 5
      3863668.08     10070209.23      3860265.26     10070278.68
      3859041.53     10071036.86      3859088.69     10071693.65
      3860192.91      10076290.1
#Sta/Elev= 30
   156.9  112.24   617.5  104.47  1575.9  104.46    2090  104.65  2600.6  103.67
  2880.9  103.63  3254.4  103.57  3514.5  100.37  4010.7   96.87  4407.8   99.37
  4651.1  101.16  4977.2   92.57  5002.5   88.84 5116.4992.57378  5573.8   97.83
  6833.4   99.41    7575   98.37  7948.7   98.56  8323.8  101.27  8864.9  102.35
  9192.3  101.75  9512.8  101.16  9720.4  103.17    9965  100.11 10096.8   102.8
   10181  115.78 10210.5  116.97 10232.4  125.54 10257.6   124.1 10385.7  131.56
#Mann= 20 ,-1 , 0
   156.9     .11       0   617.5     .15       0  1575.9     .11       0
    2090     .15       0  2600.6     .17       0  2880.9     .15       0
  3254.4     .17       0  3514.5     .15       0  4407.8     .17       0
  4977.2     .09       0 5116.49     .15       0  6833.4     .17       0
    7575     .15       0  7948.7     .15       0  8323.8     .17       0
  8864.9     .15       0  9192.3     .15       0  9512.8     .17       0
  9720.4     .15       0 10096.8     .11       0
Bank Sta=4977.2,5116.49
XS Rating Curve= 0 ,0
Exp/Cntr=0.3,0.1

Type RM Length L Ch R = 1 ,1494    ,494,494,494
BEGIN DESCRIPTION:
Crystal Creek 013 3.0
END DESCRIPTION:
XS GIS Cut Line= 4
      3863681.95     10070070.34      3860188.87     10070091.18
      3858814.66      10070847.4      3860057.57     10076363.32
#Sta/Elev= 30
    22.3     112   505.4  102.94  1350.1  103.27  1936.4  104.35  1976.4   89.82
  2066.4   92.13  2106.4  101.61  2156.4   86.57  2224.3   85.66  2266.4   87.52
  2306.4  104.81  4583.6   99.52  4996.5   87.98  5034.4   95.56  5262.4   89.97
  5764.3    98.9  7069.2   99.39  8026.3    98.7  8218.5   98.59  8467.3   99.81
  8651.7  100.72  9206.3   99.92  9475.9  100.09  9789.5  100.44  9923.7   100.8
 10155.7  101.76 10418.1  102.37 10485.2  112.51 10561.6  123.81 10738.2  126.67
#Mann= 16 ,-1 , 0
    22.3     .11       0   505.4     .15       0  1350.1     .11       0
  4583.6     .09       0  5764.3     .15       0  7069.2     .17       0
  8026.3     .15       0  8218.5     .17       0  8467.3     .15       0
  8651.7     .17       0  9206.3     .15       0  9475.9     .17       0
  9789.5     .15       0  9923.7     .17       0 10155.7     .15       0
 10485.2     .11       0
Bank Sta=4583.6,5764.3
XS Rating Curve= 0 ,0
Exp/Cntr=0.3,0.1

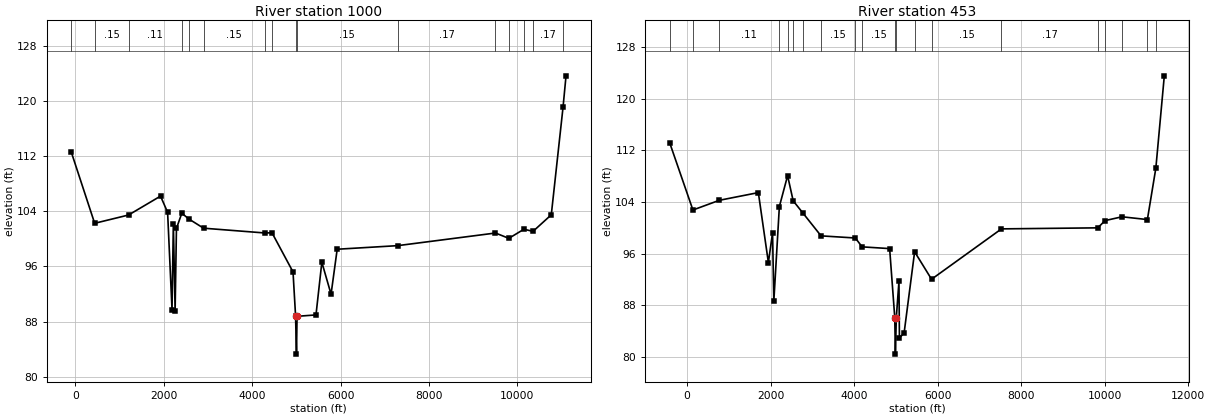
Type RM Length L Ch R = 1 ,1000    ,547,547,547
BEGIN DESCRIPTION:
Crystal Creek 013 2.0
END DESCRIPTION:
XS GIS Cut Line= 4
      3863675.01      10069938.4      3860126.37     10069903.68
      3858657.55     10070562.22      3859880.49     10076472.72
#Sta/Elev= 30
     -92  112.53   434.3  102.26  1201.1  103.46  1925.3   106.2  2085.3  103.85
  2185.2   89.76  2215.3  102.17  2255.3   89.57  2285.3  101.51  2406.4  103.72
  2569.5  102.87  2899.5  101.55  4280.4  100.86  4448.3  100.88  4923.7   95.21
  4981.1   88.87  5002.1    83.3 5014.4588.78028  5443.2   88.98  5575.9   96.62
  5784.4   91.98  5923.1    98.5  7291.6   99.02  9505.8  100.85  9807.7  100.08
 10149.9   101.4 10355.1  101.09 10768.5  103.49 11034.5  119.08 11102.2  123.63
#Mann= 16 ,-1 , 0
     -92     .11       0   434.3     .15       0  1201.1     .11       0
  2406.4     .15       0  2569.5     .17       0  2899.5     .15       0
  4280.4     .17       0  4448.3     .15       0  4981.1     .09       0
 5014.45     .15       0  7291.6     .17       0  9505.8     .15       0
  9807.7     .17       0 10149.9     .15       0 10355.1     .17       0
 11034.5     .11       0
Bank Sta=4981.1,5014.45
XS Rating Curve= 0 ,0
Exp/Cntr=0.3,0.1

Type RM Length L Ch R = 1 ,453     ,0,0,0
BEGIN DESCRIPTION:
Crystal Creek 013 1.0
END DESCRIPTION:
XS GIS Cut Line= 4
      3863709.74     10069820.35       3860022.2     10069695.35
      3858376.33     10070353.21      3859692.76      10076596.6
#Sta/Elev= 30
    -417  113.16   139.3  102.76   771.5  104.26  1706.1  105.45  1946.2   94.64
  2046.3   99.24  2076.3   88.61  2209.2  103.29  2406.4  108.07  2539.8  104.18
  2766.8  102.34  3207.4   98.76  4028.7   98.43  4189.8   97.06  4849.6   96.79
 4972.1686.13118  4987.4   80.47 5009.2386.13448  5072.6   91.72  5083.8   82.97
  5196.2   83.75  5447.7    96.3    5853   92.05    7527   99.84  9833.6     100
 10007.2  101.12 10412.5  101.71 11020.4  101.28 11223.1  109.23 11425.8  123.51
#Mann= 20 ,-1 , 0
    -417     .11       0   139.3     .15       0   771.5     .11       0
  2209.2     .15       0  2406.4     .17       0  2539.8     .11       0
  2766.8     .17       0  3207.4     .15       0  4028.7     .17       0
  4189.8     .15       0 4972.16     .09       0 5009.23     .15       0
  5447.7     .17       0    5853     .15       0    7527     .17       0
  9833.6     .15       0 10007.2     .11       0 10412.5     .11       0
 11020.4     .17       0 11223.1     .11       0
Bank Sta=4972.16,5009.23
XS Rating Curve= 0 ,0
Exp/Cntr=0.3,0.1

Chan Stop Cuts=-1
Use User Specified Reach Order=0
Composite Channel Slope=5

--- Crystal Creek 013.g10 (geometry) ---

Geom Title=Existing Conditions
Program Version=4.10

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
River Reach=Crystal Creek 01,Reach-1

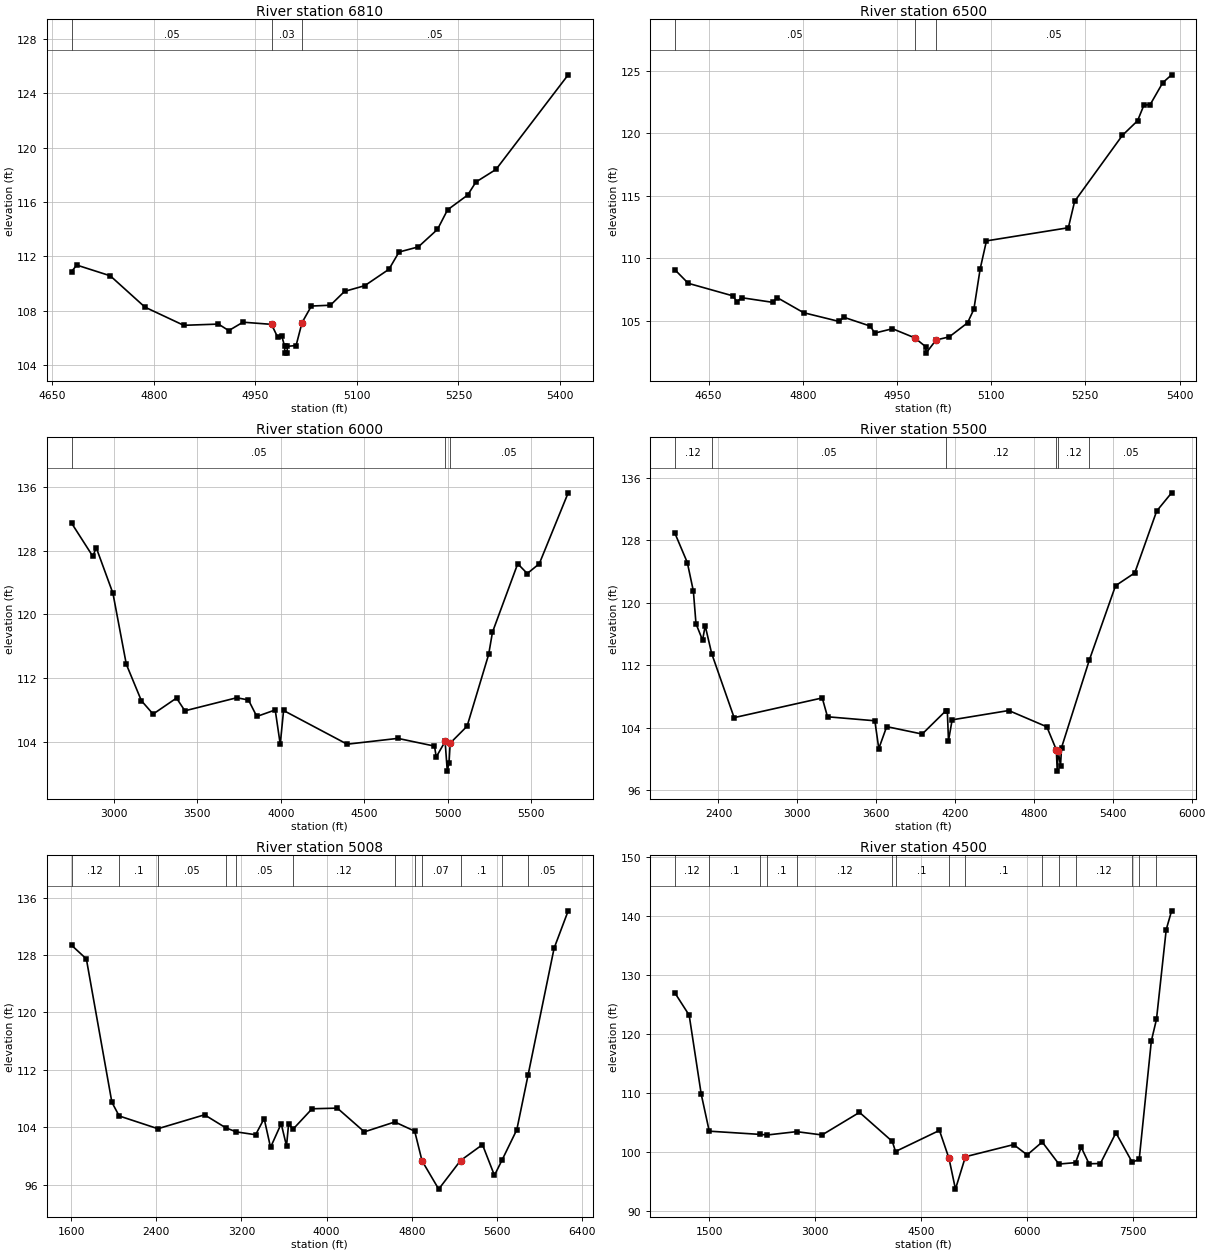
Type RM Length L Ch R = 1 ,6810    ,310,310,310
BEGIN DESCRIPTION:
Crystal Creek 013 14.0
END DESCRIPTION:
XS GIS Cut Line= 3
      3862421.77     10071654.66      3862246.05     10071924.13
      3862011.96     10072263.29
#Sta/Elev= 30
  4678.3  110.86    4686  111.35  4735.5  110.56  4786.8  108.25  4844.1  106.91
  4895.4     107  4910.6  106.52  4931.7  107.14  4973.8  106.98    4983  106.02
    4989  106.11  4993.2  105.36  4993.4  104.86  4996.9  104.86  4997.2  105.36
  5010.1  105.42  5018.9  107.11  5032.7  108.33  5060.8  108.39  5081.7  109.41
  5111.5  109.83  5147.3  111.04  5162.2  112.31  5190.7  112.69    5219  113.98
  5233.9  115.42  5263.6  116.51  5275.8  117.47  5305.5   118.4  5412.1  125.37
#Mann= 3 , 0 , 0
  4678.3     .05       0  4973.8     .03       0  5018.9     .05       0
Bank Sta=4973.8,5018.9
XS Rating Curve= 0 ,0
Exp/Cntr=0.3,0.1

Type RM Length L Ch R = 1 ,6500    ,500,500,500
BEGIN DESCRIPTION:
Crystal Creek 013 13.0
END DESCRIPTION:
XS GIS Cut Line= 3
      3862235.06     10071568.36      3861944.93     10071848.78
      3861917.33      10072235.1
#Sta/Elev= 30
  4596.5  109.08  4617.7     108  4688.5     107  4695.4  106.53  4702.6  106.85
    4752  106.48  4759.2  106.86  4801.4  105.65    4858  104.95  4865.2  105.29
  4907.6  104.58  4914.6  104.02  4942.9  104.37  4978.4  103.64    4996  102.92
  4996.3  102.42  5012.3  103.47  5033.3  103.72  5062.4  104.84  5072.5  105.93
  5082.5  109.15  5092.5  111.39  5222.9  112.44  5232.9  114.55  5308.9  119.82
  5333.1  120.99  5343.2  122.24  5353.2  122.28  5373.2  124.03  5387.3  124.66
#Mann= 3 , 0 , 0
  4596.5     .05       0  4978.4     .03       0  5012.3     .05       0
Bank Sta=4978.4,5012.3
XS Rating Curve= 0 ,0
Exp/Cntr=0.3,0.1

Type RM Length L Ch R = 1 ,6000    ,500,500,500
BEGIN DESCRIPTION:
Crystal Creek 013 12.0
END DESCRIPTION:
XS GIS Cut Line= 4
      3863425.55      10071394.2      3861533.18     10071477.53
      3861469.48     10071829.41       3861870.9     10072427.13
#Sta/Elev= 30
  2748.2  131.45    2876  127.26    2896  128.37  2996.1  122.63  3076.2  113.72
  3166.3  109.15  3236.4  107.47  3376.5  109.48  3426.6  107.88  3736.9  109.52
  3806.9  109.24    3857  107.17  3967.1  107.99  3997.1  103.68  4017.1  107.92
  4397.5  103.69  4701.1  104.42  4920.1  103.45  4930.5  102.09  4983.7  104.03
  4996.6  100.31    5007  101.36    5014  103.82  5115.1  105.95  5244.1  114.95
    5267  117.75  5418.1  126.34  5475.1  125.11  5547.1  126.34    5720  135.24
#Mann= 3 , 0 , 0
  2748.2     .05       0  4983.7     .07       0    5014     .05       0
Bank Sta=4983.7,5014
XS Rating Curve= 0 ,0
Exp/Cntr=0.3,0.1

Type RM Length L Ch R = 1 ,5500    ,492,492,492
BEGIN DESCRIPTION:
Crystal Creek 013 11.0
END DESCRIPTION:
XS GIS Cut Line= 4
      3863408.09     10071243.24      3861297.07     10071307.39
      3861088.39     10072099.48      3861849.85     10072471.53
#Sta/Elev= 30
  2068.9  128.87  2163.1  125.13  2209.2  121.48  2229.2   117.3  2279.2   115.2
  2299.2  117.04  2348.5  113.49  2519.3  105.29  3189.7  107.81  3229.7   105.4
  3589.8  104.89  3619.9  101.33  3679.9  104.14    3950  103.19  4128.4  106.14
  4141.2  106.17  4150.1  102.34    4178  105.01  4608.7   106.2  4898.2  104.12
  4970.6  101.18  4977.4   98.45  4984.3  101.05  5002.5   99.13    5010  101.45
  5221.3  112.64  5420.9  122.16  5567.2   123.8    5734  131.71  5847.5  134.04
#Mann= 6 ,-1 , 0
  2068.9     .12       0  2348.5     .05       0  4128.4     .12       0
  4970.6     .07       0  4984.3     .12       0  5221.3     .05       0
Bank Sta=4970.6,4984.3
XS Rating Curve= 0 ,0
Exp/Cntr=0.3,0.1

Type RM Length L Ch R = 1 ,5008    ,508,508,508
BEGIN DESCRIPTION:
Crystal Creek 013 10.0
END DESCRIPTION:
XS GIS Cut Line= 5
      3863467.05     10071104.36      3861201.59      10071133.2
      3860768.24     10072176.86      3860922.51     10072480.86
      3861849.91     10072519.29
#Sta/Elev= 30
  1604.3  129.37  1743.8  127.46  1983.5  107.48  2051.8  105.57  2415.8  103.79
  2853.6  105.73  3052.9  103.92  3151.6  103.35  3333.6  102.95  3413.6  105.21
  3473.7  101.19  3573.7  104.49  3623.7  101.39  3643.7  104.51  3682.8  103.69
  3863.7  106.57  4100.9  106.66  4354.9  103.35  4640.7  104.73  4827.6  103.45
  4896.3   99.32    5053   95.37  5258.2  99.352  5464.1  101.57  5576.4   97.29
  5648.2   99.43  5786.6  103.65  5891.7  111.22  6136.9  128.95  6269.1  134.16
#Mann= 12 ,-1 , 0
  1604.3     .12       0  2051.8      .1       0  2415.8     .05       0
  3052.9      .1       0  3151.6     .05       0  3682.8     .12       0
  4640.7      .1       0  4827.6     .12       0  4896.3     .07       0
  5258.2      .1       0  5648.2     .12       0  5891.7     .05       0
Bank Sta=4896.3,5258.2
XS Rating Curve= 0 ,0
Exp/Cntr=0.3,0.1

Type RM Length L Ch R = 1 ,4500    ,500,500,500
BEGIN DESCRIPTION:
Crystal Creek 013 9.0
END DESCRIPTION:
XS GIS Cut Line= 5
      3863529.53     10070958.52      3860772.62     10071021.02
      3860289.08     10072146.86      3860710.12     10073333.52
      3862493.89     10073215.53
#Sta/Elev= 30
  1017.1  126.93  1218.8  123.17  1388.9  109.84  1502.8  103.56  2227.3  103.01
    2326  102.92  2739.5  103.48  3099.3  102.92  3629.4  106.74  4093.5  101.83
  4139.4  100.12  4761.1  103.69  4895.7   98.97  4987.6   93.76  5128.7   99.24
  5810.9  101.29  6002.7   99.55  6215.7  101.73  6451.5      98  6686.8   98.24
    6768  100.83  6878.2   98.05  7038.6   98.09    7259  103.28  7489.3    98.3
  7588.4   98.82  7760.1  118.82  7832.8  122.48  7970.6  137.65  8046.8  140.82
#Mann= 15 ,-1 , 0
  1017.1     .12       0  1502.8      .1       0  2227.3     .05       0
    2326      .1       0  2739.5     .12       0  4093.5     .05       0
  4139.4      .1       0  4895.7     .07       0  5128.7      .1       0
  6215.7     .12       0  6451.5      .1       0  6686.8     .12       0
  7489.3      .1       0  7588.4     .12       0  7832.8     .05       0
Bank Sta=4895.7,5128.7
XS Rating Curve= 0 ,0
Exp/Cntr=0.3,0.1

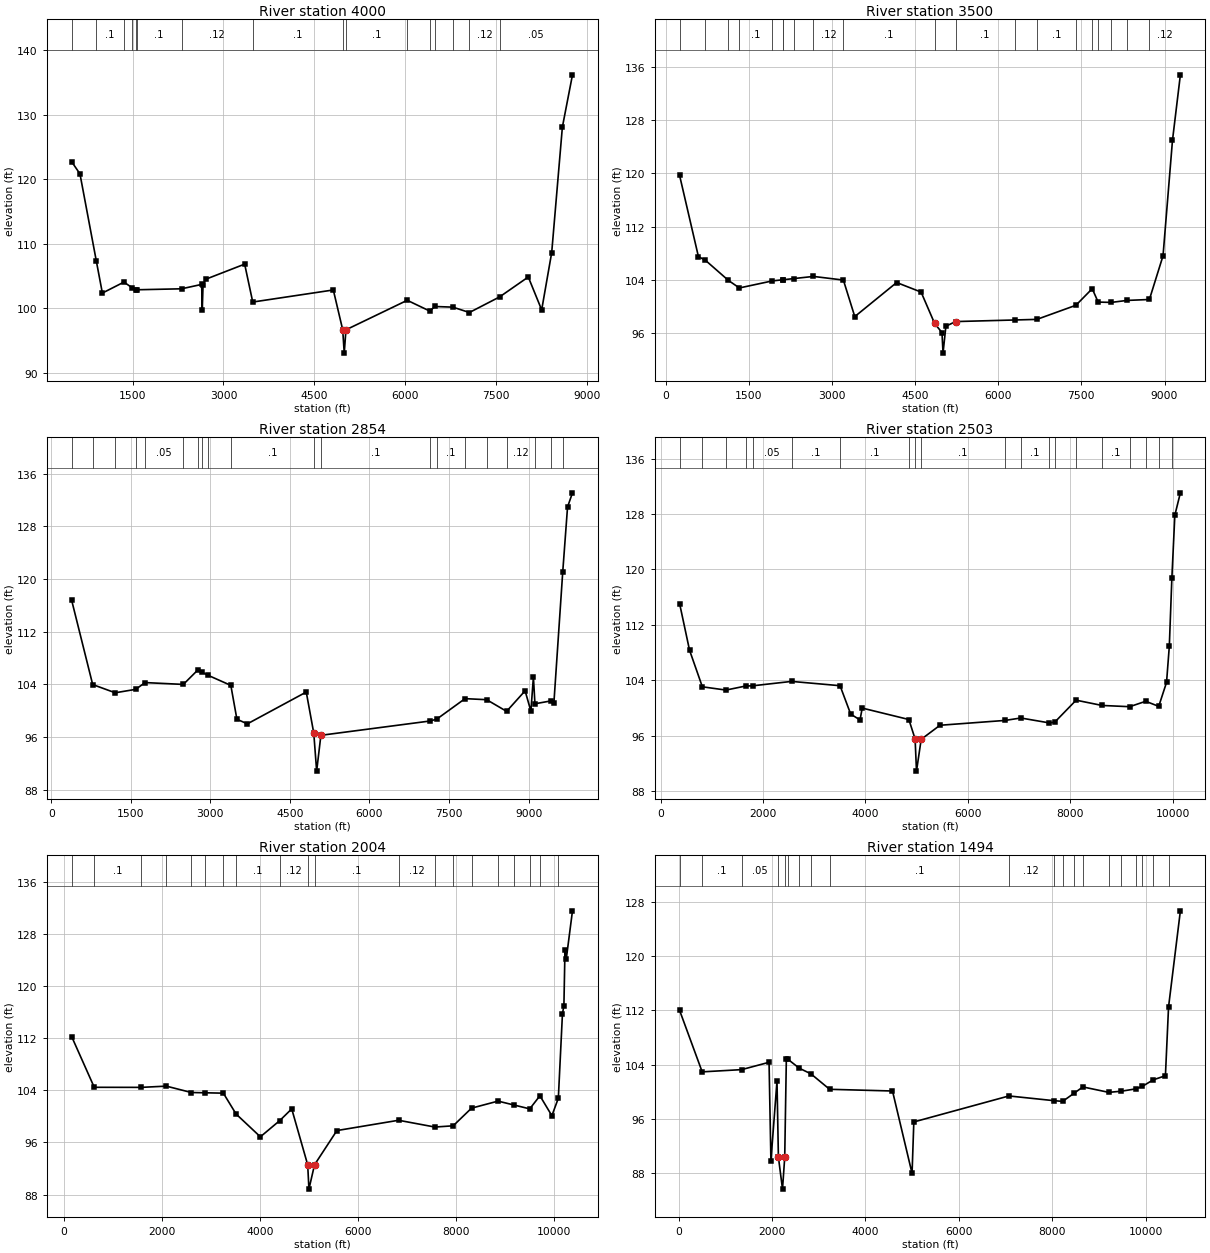
Type RM Length L Ch R = 1 ,4000    ,500,500,500
BEGIN DESCRIPTION:
Crystal Creek 013 8.0
END DESCRIPTION:
XS GIS Cut Line= 5
      3863584.25     10070788.38      3860589.46     10070840.47
      3859830.51     10072146.86      3860628.53     10073600.88
      3862723.86     10073822.13
#Sta/Elev= 30
   493.9   122.7   630.3  120.82     900  107.36  1000.4  102.37  1357.1  104.07
  1493.1  103.18  1555.6  102.78  1569.8  102.88  2308.3  103.03  2640.6  103.71
  2650.6   99.82  2663.5  103.65  2710.6  104.52  3350.7  106.85  3484.2  100.98
  4815.1  102.85 4970.47  96.677  4995.5   93.07  5023.8   96.68  6036.2  101.25
  6409.1   99.58  6493.1  100.29  6789.5  100.19  7062.8   99.36  7561.3  101.77
  8035.6  104.86  8256.8   99.76  8422.5  108.65  8598.7  128.07  8765.6  136.16
#Mann= 16 ,-1 , 0
   493.9     .12       0     900      .1       0  1357.1     .05       0
  1493.1      .1       0  1555.6     .05       0  1569.8      .1       0
  2308.3     .12       0  3484.2      .1       0 4970.47     .07       0
  5023.8      .1       0  6036.2     .12       0  6409.1      .1       0
  6493.1     .12       0  6789.5      .1       0  7062.8     .12       0
  7561.3     .05       0
Bank Sta=4970.47,5023.8
XS Rating Curve= 0 ,0
Exp/Cntr=0.3,0.1

Type RM Length L Ch R = 1 ,3500    ,646,646,646
BEGIN DESCRIPTION:
Crystal Creek 013 7.0
END DESCRIPTION:
XS GIS Cut Line= 4
      3863607.21     10070630.24      3860447.46     10070706.63
      3859442.34     10071936.86      3860953.72     10075947.86
#Sta/Elev= 30
   250.7   119.7   590.2  107.46   715.7  106.91  1131.3  103.87  1328.8  102.73
  1921.3  103.79  2116.5  103.97  2118.8  103.97  2316.4  104.15  2666.2  104.47
  3205.8  103.92  3411.4   98.41    4167  103.55  4607.8  102.11 4852.38  97.371
  4984.7      96  5003.9    92.9  5055.4   96.96  5231.3   97.66  6299.3    97.9
  6697.2   97.99  7401.5  100.12  7695.8  102.62  7802.5   100.6    8039  100.55
  8322.2  100.85  8727.4  100.99  8973.2  107.58  9143.8     125  9286.3  134.88
#Mann= 20 ,-1 , 0
   250.7     .12       0   715.7      .1       0  1131.3     .05       0
  1328.8      .1       0  1921.3     .05       0  2116.5      .1       0
  2118.8     .12       0  2316.4     .05       0  2666.2     .12       0
  3205.8      .1       0 4852.38     .07       0  5231.3      .1       0
  6299.3     .12       0  6697.2      .1       0  7401.5     .12       0
  7695.8     .05       0  7802.5      .1       0    8039     .12       0
  8322.2      .1       0  8727.4     .12       0
Bank Sta=4852.38,5231.3
XS Rating Curve= 0 ,0
Exp/Cntr=0.3,0.1

Type RM Length L Ch R = 1 ,2854    ,351,351,351
BEGIN DESCRIPTION:
Crystal Creek 013 6.0
END DESCRIPTION:
XS GIS Cut Line= 4
       3863621.1     10070491.35       3860405.8     10070574.69
       3859249.2      10071708.8      3860579.37     10076116.21
#Sta/Elev= 30
   386.5  116.72   781.9  103.95  1206.3   102.7  1592.2  103.22  1769.6  104.25
  2490.8  103.97  2761.1  106.14  2843.9  105.82  2950.2  105.38  3386.3  103.82
  3500.8   98.68  3697.9   97.98    4808  102.81  4949.5   96.58    5004    90.8
  5083.9   96.24    7148   98.42  7270.3   98.71  7801.6  101.81  8209.2  101.65
  8584.5   99.88  8933.3     103  9042.7    99.9  9089.9  105.11  9118.8  101.03
  9430.9  101.48  9476.4  101.19  9642.2  120.98  9733.5  130.92  9826.5  133.07
#Mann= 20 ,-1 , 0
   386.5     .12       0   781.9      .1       0  1206.3     .05       0
  1592.2      .1       0  1769.6     .05       0  2490.8      .1       0
  2761.1     .12       0  2843.9     .05       0  2950.2     .12       0
  3386.3      .1       0  4949.5     .07       0  5083.9      .1       0
    7148     .12       0  7270.3      .1       0  7801.6     .12       0
  8209.2      .1       0  8584.5     .12       0  9118.8      .1       0
  9430.9     .12       0  9642.2     .05       0
Bank Sta=4949.5,5083.9
XS Rating Curve= 0 ,0
Exp/Cntr=0.3,0.1

Type RM Length L Ch R = 1 ,2503    ,499,499,499
BEGIN DESCRIPTION:
Crystal Creek 013 5.0
END DESCRIPTION:
XS GIS Cut Line= 5
      3863675.01     10070362.01       3860334.7     10070431.46
      3859338.24     10071246.86      3859155.01     10071688.75
      3860401.33     10076191.48
#Sta/Elev= 30
   371.4  115.06   565.2  108.34   815.7  103.05  1276.5  102.58  1659.1  103.16
  1803.1   103.2    2558  103.83  3504.7  103.21  3712.4   99.11  3894.6   98.27
  3937.6   99.98  4848.3   98.33 4970.31  95.523  4997.3   90.88  5089.1   95.47
  5455.9    97.5  6729.3    98.2  7034.3   98.55  7592.3   97.84  7697.4   97.95
  8114.5  101.12  8619.8  100.36  9159.6  100.18    9473  100.96  9727.6  100.23
  9880.2  103.69  9934.2  108.89  9984.6  118.81 10042.3  127.82 10150.4  131.05
#Mann= 20 ,-1 , 0
   371.4     .05       0   815.7      .1       0  1276.5     .05       0
  1659.1      .1       0  1803.1     .05       0    2558      .1       0
  3504.7      .1       0  4848.3     .12       0 4970.31     .07       0
  5089.1      .1       0  6729.3     .12       0  7034.3      .1       0
  7592.3     .12       0  7697.4      .1       0  8114.5     .12       0
  8619.8      .1       0  9159.6     .12       0    9473      .1       0
  9727.6     .12       0  9984.6     .05       0
Bank Sta=4970.31,5089.1
XS Rating Curve= 0 ,0
Exp/Cntr=0.3,0.1

Type RM Length L Ch R = 1 ,2004    ,510,510,510
BEGIN DESCRIPTION:
Crystal Creek 013 4.0
END DESCRIPTION:
XS GIS Cut Line= 5
      3863668.08     10070209.23      3860265.26     10070278.68
      3859041.53     10071036.86      3859088.69     10071693.65
      3860192.91      10076290.1
#Sta/Elev= 30
   156.9  112.24   617.5  104.47  1575.9  104.46    2090  104.65  2600.6  103.67
  2880.9  103.63  3254.4  103.57  3514.5  100.37  4010.7   96.87  4407.8   99.37
  4651.1  101.16  4977.2   92.57  5002.5   88.84 5116.49  92.574  5573.8   97.83
  6833.4   99.41    7575   98.37  7948.7   98.56  8323.8  101.27  8864.9  102.35
  9192.3  101.75  9512.8  101.16  9720.4  103.17    9965  100.11 10096.8   102.8
   10181  115.78 10210.5  116.97 10232.4  125.54 10257.6   124.1 10385.7  131.56
#Mann= 20 ,-1 , 0
   156.9     .05       0   617.5      .1       0  1575.9     .05       0
    2090      .1       0  2600.6     .12       0  2880.9      .1       0
  3254.4     .12       0  3514.5      .1       0  4407.8     .12       0
  4977.2     .07       0 5116.49      .1       0  6833.4     .12       0
    7575      .1       0  7948.7      .1       0  8323.8     .12       0
  8864.9      .1       0  9192.3      .1       0  9512.8     .12       0
  9720.4      .1       0 10096.8     .05       0
Bank Sta=4977.2,5116.49
XS Rating Curve= 0 ,0
Exp/Cntr=0.3,0.1

Type RM Length L Ch R = 1 ,1494    ,494,494,494
BEGIN DESCRIPTION:
Crystal Creek 013 3.0
END DESCRIPTION:
XS GIS Cut Line= 4
      3863681.95     10070070.34      3860188.87     10070091.18
      3858814.66      10070847.4      3860057.57     10076363.32
#Sta/Elev= 30
    22.3     112   505.4  102.94  1350.1  103.27  1936.4  104.35  1976.4   89.82
  2106.4  101.61  2136.4   90.39  2224.3   85.66 2271.61  90.328  2306.4  104.81
  2340.5  104.79  2585.1  103.47  2830.1  102.66  3232.6  100.37  4577.9  100.12
  4996.5   87.98  5034.4   95.56  7069.2   99.39  8026.3    98.7  8218.5   98.59
  8467.3   99.81  8651.7  100.72  9206.3   99.92  9475.9  100.09  9789.5  100.44
  9923.7   100.8 10155.7  101.76 10418.1  102.37 10485.2  112.51 10738.2  126.67
#Mann= 20 ,-1 , 0
    22.3     .05       0   505.4      .1       0  1350.1     .05       0
  2136.4     .07       0 2271.61     .05       0  2340.5      .1       0
  2585.1     .12       0  2830.1     .12       0  3232.6      .1       0
  7069.2     .12       0  8026.3      .1       0  8218.5     .12       0
  8467.3      .1       0  8651.7     .12       0  9206.3      .1       0
  9475.9     .12       0  9789.5      .1       0  9923.7     .12       0
 10155.7      .1       0 10485.2     .05       0
Bank Sta=2136.4,2271.61
XS Rating Curve= 0 ,0
Exp/Cntr=0.3,0.1

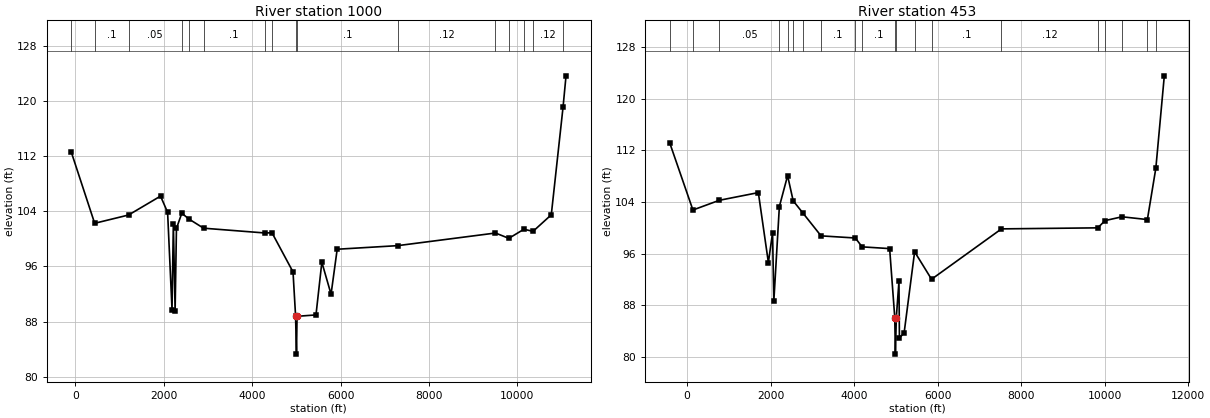
Type RM Length L Ch R = 1 ,1000    ,547,547,547
BEGIN DESCRIPTION:
Crystal Creek 013 2.0
END DESCRIPTION:
XS GIS Cut Line= 4
      3863675.01      10069938.4      3860126.37     10069903.68
      3858657.55     10070562.22      3859880.49     10076472.72
#Sta/Elev= 30
     -92  112.53   434.3  102.26  1201.1  103.46  1925.3   106.2  2085.3  103.85
  2185.2   89.76  2215.3  102.17  2255.3   89.57  2285.3  101.51  2406.4  103.72
  2569.5  102.87  2899.5  101.55  4280.4  100.86  4448.3  100.88  4923.7   95.21
  4981.1   88.87  5002.1    83.3 5014.45   88.78  5443.2   88.98  5575.9   96.62
  5784.4   91.98  5923.1    98.5  7291.6   99.02  9505.8  100.85  9807.7  100.08
 10149.9   101.4 10355.1  101.09 10768.5  103.49 11034.5  119.08 11102.2  123.63
#Mann= 16 ,-1 , 0
     -92     .05       0   434.3      .1       0  1201.1     .05       0
  2406.4      .1       0  2569.5     .12       0  2899.5      .1       0
  4280.4     .12       0  4448.3      .1       0  4981.1     .07       0
 5014.45      .1       0  7291.6     .12       0  9505.8      .1       0
  9807.7     .12       0 10149.9      .1       0 10355.1     .12       0
 11034.5     .05       0
Bank Sta=4981.1,5014.45
XS Rating Curve= 0 ,0
Exp/Cntr=0.3,0.1

Type RM Length L Ch R = 1 ,453     ,0,0,0
BEGIN DESCRIPTION:
Crystal Creek 013 1.0
END DESCRIPTION:
XS GIS Cut Line= 4
      3863709.74     10069820.35       3860022.2     10069695.35
      3858376.33     10070353.21      3859692.76      10076596.6
#Sta/Elev= 30
    -417  113.16   139.3  102.76   771.5  104.26  1706.1  105.45  1946.2   94.64
  2046.3   99.24  2076.3   88.61  2209.2  103.29  2406.4  108.07  2539.8  104.18
  2766.8  102.34  3207.4   98.76  4028.7   98.43  4189.8   97.06  4849.6   96.79
 4972.16  86.131  4987.4   80.47 5009.23  86.134  5072.6   91.72  5083.8   82.97
  5196.2   83.75  5447.7    96.3    5853   92.05    7527   99.84  9833.6     100
 10007.2  101.12 10412.5  101.71 11020.4  101.28 11223.1  109.23 11425.8  123.51
#Mann= 20 ,-1 , 0
    -417     .05       0   139.3      .1       0   771.5     .05       0
  2209.2      .1       0  2406.4     .12       0  2539.8     .05       0
  2766.8     .12       0  3207.4      .1       0  4028.7     .12       0
  4189.8      .1       0 4972.16     .07       0 5009.23      .1       0
  5447.7     .12       0    5853      .1       0    7527     .12       0
  9833.6      .1       0 10007.2     .05       0 10412.5     .05       0
 11020.4     .12       0 11223.1     .05       0
Bank Sta=4972.16,5009.23
XS Rating Curve= 0 ,0
Exp/Cntr=0.3,0.1