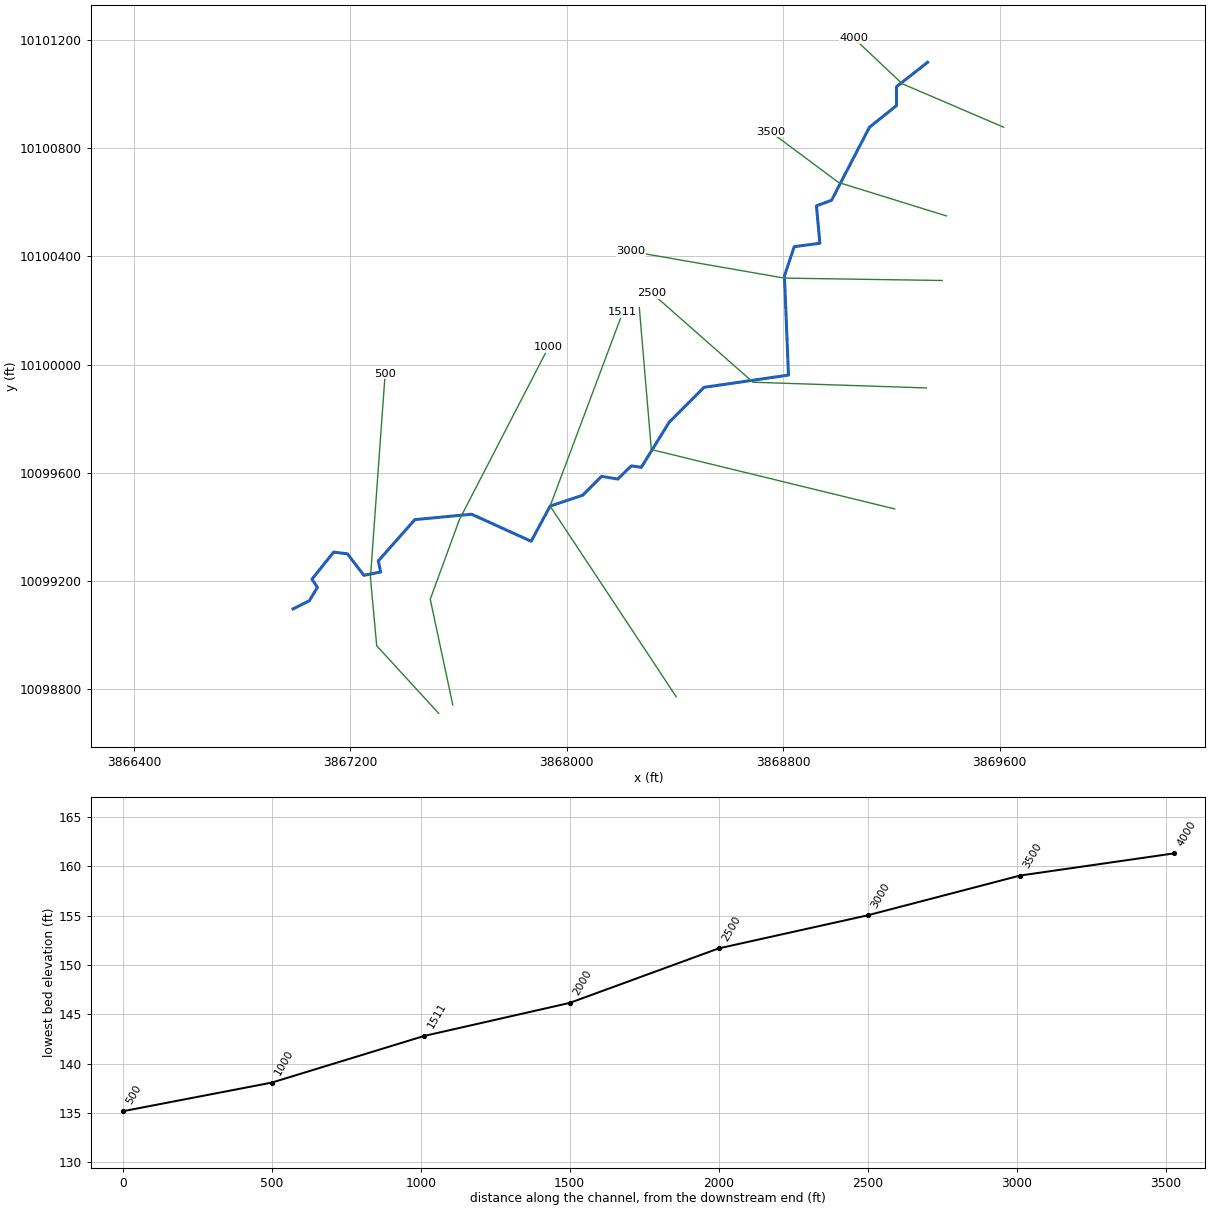
--- Crystal Creek 015.prj (project) ---

Proj Title=Crystal Creek 015 Base Level Engineering
Current Plan=p01
Default Exp/Contr=0.3,0.1
English Units
Geom File=g01
Flow File=f01
Flow File=f02
Plan File=p01
Y Axis Title=Elevation
X Axis Title(PF)=Main Channel Distance
X Axis Title(XS)=Station
BEGIN DESCRIPTION:
Crystal Creek 015
END DESCRIPTION:
DSS Export Rating Curves= 0
DSS Export Rating Curve Sorted= 0
DSS Export Volume Flow Curves= 0
DXF OffsetX= 0
DXF OffsetY= 0
DXF ScaleX= 1
DXF ScaleY= 10

--- Crystal Creek 015.p01 (plan) ---

Plan Title=Multiple Run
Short Identifier=Multiple
Geom File=g01
Flow File=f01
Subcritical Flow
K Sum by GR= 0
Std Step Tol= 0.01
Critical Tol= 0.01
Num of Std Step Trials= 20
Max Error Tol= 0.3
Flow Tol Ratio= 0.001
Split Flow NTrial= 30
Split Flow Tol= 0.02
Split Flow Ratio= 0.02
Log Output Level= 0
Friction Slope Method= 1
Unsteady Friction Slope Method= 2
Unsteady Bridges Friction Slope Method= 1
Parabolic Critical Depth
Global Vel Dist=  1 , 1 , 1
Global Log Level= 0
CheckData=True
Encroach Param= -1, 0, 0, 0
BEGIN DESCRIPTION:
Multiple Run
END DESCRIPTION:

--- Crystal Creek 015.f01 (steady flow) ---

Flow Title=Multiple
Program Version=4.10
Number of Profiles= 7
Profile Names=10-year,25-year,50-year,1pct_min,100-year,1pct_plu,500-year
River Rch & RM=Crystal Creek 01,Reach-1         ,4000
     276     351     453     194     585    1767    1004
Boundary for River Rch & Prof#=Crystal Creek 01,Reach-1         , 1
Up Type= 0
Dn Type= 3
Dn Slope=0.006
Boundary for River Rch & Prof#=Crystal Creek 01,Reach-1         , 2
Up Type= 0
Dn Type= 3
Dn Slope=0.006
Boundary for River Rch & Prof#=Crystal Creek 01,Reach-1         , 3
Up Type= 0
Dn Type= 3
Dn Slope=0.006
Boundary for River Rch & Prof#=Crystal Creek 01,Reach-1         , 4
Up Type= 0
Dn Type= 3
Dn Slope=0.006
Boundary for River Rch & Prof#=Crystal Creek 01,Reach-1         , 5
Up Type= 0
Dn Type= 3
Dn Slope=0.006
Boundary for River Rch & Prof#=Crystal Creek 01,Reach-1         , 6
Up Type= 0
Dn Type= 3
Dn Slope=0.006
Boundary for River Rch & Prof#=Crystal Creek 01,Reach-1         , 7
Up Type= 0
Dn Type= 3
Dn Slope=0.006
DSS Import GetInterval= 0
DSS Import GetPeak= 0
DSS Import FillOption= 0

--- Crystal Creek 015.f02 (steady flow) ---

Flow Title=Orig_BLE_Flow
Program Version=4.10
Number of Profiles= 7
Profile Names=10-year,25-year,50-year,1pct_min,100-year,1pct_plu,500-year
River Rch & RM=Crystal Creek 01,Reach-1         ,4000
     276     344     394     149     450    1360     584
Boundary for River Rch & Prof#=Crystal Creek 01,Reach-1         , 1
Up Type= 0
Dn Type= 3
Dn Slope=0.006
Boundary for River Rch & Prof#=Crystal Creek 01,Reach-1         , 2
Up Type= 0
Dn Type= 3
Dn Slope=0.006
Boundary for River Rch & Prof#=Crystal Creek 01,Reach-1         , 3
Up Type= 0
Dn Type= 3
Dn Slope=0.006
Boundary for River Rch & Prof#=Crystal Creek 01,Reach-1         , 4
Up Type= 0
Dn Type= 3
Dn Slope=0.006
Boundary for River Rch & Prof#=Crystal Creek 01,Reach-1         , 5
Up Type= 0
Dn Type= 3
Dn Slope=0.006
Boundary for River Rch & Prof#=Crystal Creek 01,Reach-1         , 6
Up Type= 0
Dn Type= 3
Dn Slope=0.006
Boundary for River Rch & Prof#=Crystal Creek 01,Reach-1         , 7
Up Type= 0
Dn Type= 3
Dn Slope=0.006
DSS Import GetInterval= 0
DSS Import GetPeak= 0
DSS Import FillOption= 0

--- Crystal Creek 015.g01 (geometry) ---

Geom Title=Existing Conditions
Program Version=4.10

River Reach=Crystal Creek 01,Reach-1
Reach XY= 30
      3869333.24     10101116.86      3869218.24     10101026.86
      3869218.24     10100956.86      3869118.24     10100876.86
      3868978.24     10100606.86      3868922.48     10100586.77
       3868935.2      10100448.3      3868840.14     10100435.57
      3868804.21     10100327.79      3868819.18     10099961.01
      3868507.21     10099915.83      3868378.24     10099786.86
      3868275.28     10099620.23      3868238.24     10099625.36
      3868188.24     10099576.86      3868128.24     10099586.86
      3868058.24     10099516.86      3867938.24     10099476.86
      3867868.24     10099346.86      3867648.24     10099446.86
      3867438.24     10099426.86      3867303.28     10099274.33
      3867311.96     10099233.41      3867249.97     10099221.02
      3867189.22     10099300.36      3867138.24     10099306.86
      3867058.24     10099206.86      3867078.24     10099176.86
      3867048.24     10099126.86      3866988.24     10099096.86

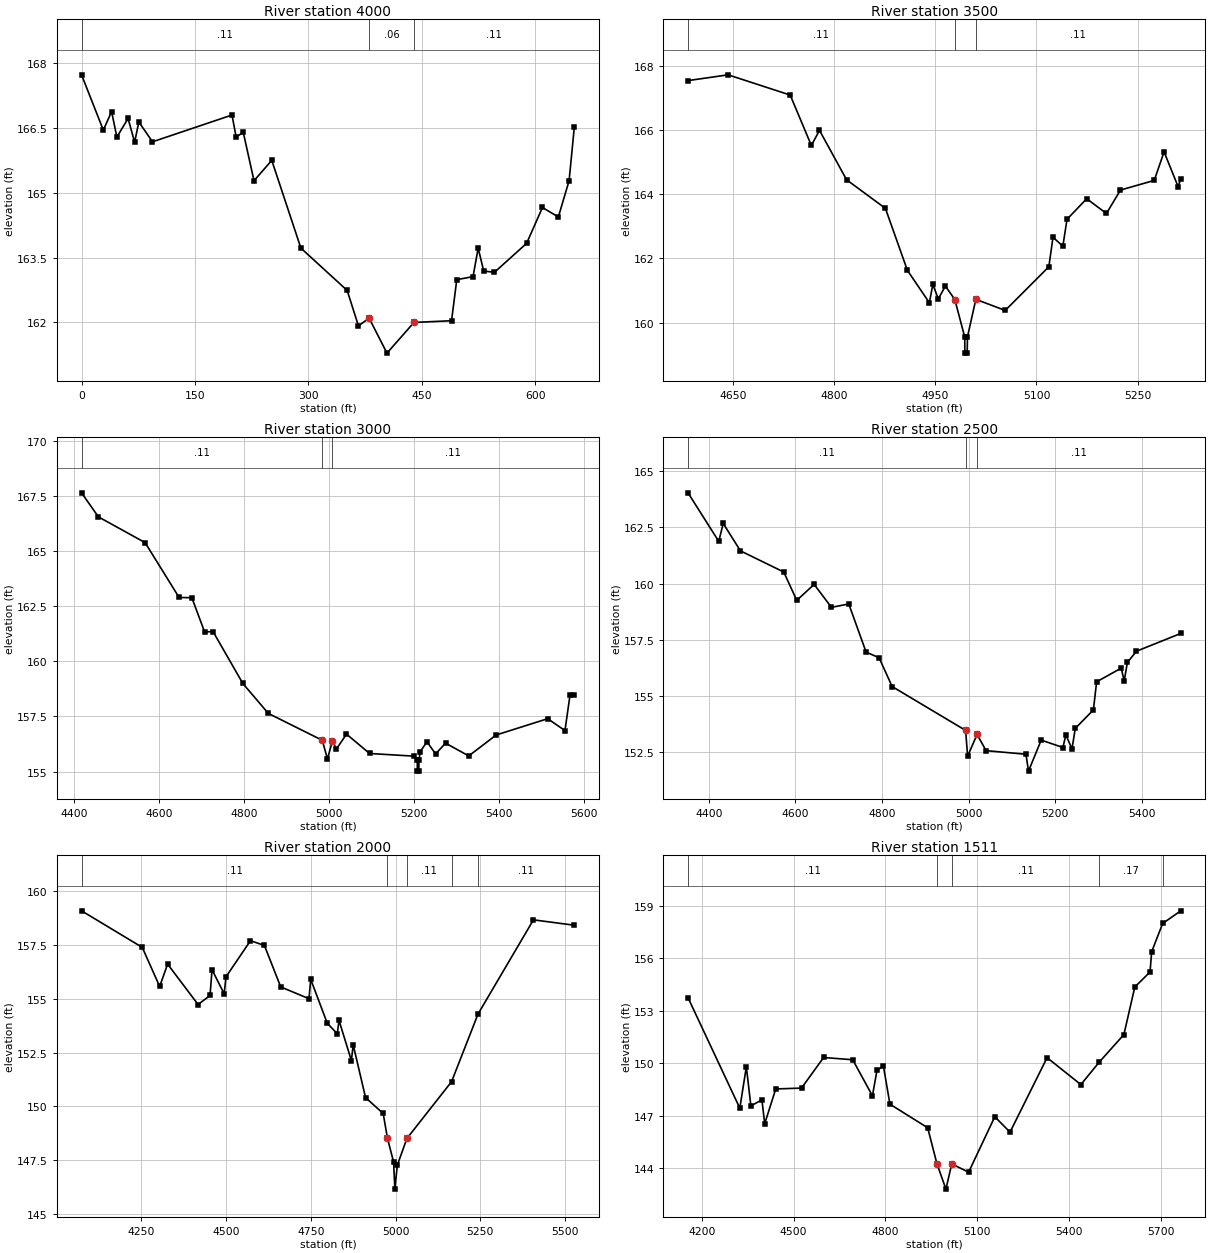
Type RM Length L Ch R = 1 ,4000    ,516,516,516
XS GIS Cut Line= 3
      3869614.33     10100877.07       3869239.3     10101037.93
      3869061.66      10101205.6
#Sta/Elev= 30
       0  167.73    28.8  166.45    39.7  166.88    46.7  166.29    61.5  166.72
    70.2  166.17    75.7  166.64    93.8  166.18   198.9   166.8   204.4  166.29
   213.8   166.4     228  165.28   251.5  165.75     290  163.72   351.2  162.74
   366.1  161.92   380.2   162.1   403.8  161.29   439.5     162   489.2  162.04
   496.1  162.99   517.6  163.06   524.4  163.72   531.7  163.19   545.9  163.16
   588.4  163.83   609.4  164.66   630.4  164.44   644.6  165.28   651.5  166.52
#Mann= 3 , 0 , 0
       0     .11       0   380.2     .06       0   439.5     .11       0
Bank Sta=380.2,439.5
XS Rating Curve= 0 ,0
Exp/Cntr=0.3,0.1

Type RM Length L Ch R = 1 ,3500    ,512,512,512
BEGIN DESCRIPTION:
Crystal Creek 015 7.0
END DESCRIPTION:
XS GIS Cut Line= 3
      3869402.65      10100549.4      3869004.24     10100672.87
      3868752.29     10100860.43
#Sta/Elev= 30
  4582.9  167.54  4642.4  167.72  4734.5  167.09  4765.9  165.52    4778  165.99
  4818.2  164.45  4875.8  163.56  4908.4  161.63    4941  160.62  4946.2  161.19
  4954.3  160.74  4964.8  161.14  4978.8  160.72  4993.5  159.55  4993.7  159.05
  4997.2  159.05  4997.5  159.55    5010160.7257  5053.6  160.38  5118.3  161.74
  5124.5  162.66  5139.1  162.38  5145.3  163.22  5174.5  163.86  5203.8   163.4
  5224.6  164.13  5274.7  164.43  5289.3  165.32  5310.1  164.24  5314.1  164.47
#Mann= 3 , 0 , 0
  4582.9     .11       0  4978.8     .06       0    5010     .11       0
Bank Sta=4978.8,5010
XS Rating Curve= 0 ,0
Exp/Cntr=0.3,0.1

Type RM Length L Ch R = 1 ,3000    ,500,500,500
BEGIN DESCRIPTION:
Crystal Creek 015 6.0
END DESCRIPTION:
XS GIS Cut Line= 3
      3869387.45     10100310.69      3868804.61     10100319.39
      3868236.17     10100418.41
#Sta/Elev= 30
  4417.1  167.65  4456.7  166.56  4566.7  165.39  4646.7   162.9  4676.7  162.89
  4706.7  161.34  4726.7  161.35  4796.7     159  4856.7  157.64 4983.83156.4185
  4995.9  155.57  5007.6156.3923    5017  156.02  5040.7   156.7  5095.2  155.82
  5199.7   155.7  5207.3  155.52  5207.5  155.02    5211  155.02  5211.3  155.52
  5214.4  155.91  5230.2  156.35  5250.5   155.8  5273.9  156.29  5328.5  155.71
  5393.1  156.66  5514.4   157.4    5555  156.86  5566.8  158.46    5577  158.46
#Mann= 3 , 0 , 0
  4417.1     .11       0 4983.83     .06       0  5007.6     .11       0
Bank Sta=4983.83,5007.6
XS Rating Curve= 0 ,0
Exp/Cntr=0.3,0.1

Type RM Length L Ch R = 1 ,2500    ,500,500,500
BEGIN DESCRIPTION:
Crystal Creek 015 5.0
END DESCRIPTION:
XS GIS Cut Line= 3
      3869328.85     10099913.56      3868688.15     10099934.68
      3868315.35     10100262.98
#Sta/Elev= 30
  4352.2  164.04  4423.2  161.88  4433.4  162.68  4473.3  161.46  4573.3  160.52
  4603.3  159.26  4643.4  159.97  4683.4  158.95  4723.4   159.1  4763.4  156.96
  4793.4  156.71  4823.5  155.43  4993.2  153.48  4997.8  152.33  5019.6   153.3
  5040.5  152.58  5132.5  152.42  5138.4  151.67  5167.7  153.05  5217.9  152.72
  5224.6  153.28  5238.8  152.66  5246.4  153.57  5288.2  154.39  5295.7  155.64
  5352.6  156.25  5359.3  155.67  5366.7   156.5  5387.7     157    5490  157.79
#Mann= 3 , 0 , 0
  4352.2     .11       0  4993.2     .06       0  5019.6     .11       0
Bank Sta=4993.2,5019.6
XS Rating Curve= 0 ,0
Exp/Cntr=0.3,0.1

Type RM Length L Ch R = 1 ,2000    ,489,489,489
BEGIN DESCRIPTION:
Crystal Creek 015 4.0
END DESCRIPTION:
XS GIS Cut Line= 3
      3869211.62     10099466.51      3868312.29     10099685.88
      3868267.85      10100211.1
#Sta/Elev= 30
  4074.3   159.1  4253.2   157.4  4304.6  155.58    4328  156.62  4417.9  154.74
  4453.1  155.16    4459  156.36  4494.7  155.24  4500.2  156.03  4572.3  157.71
  4613.4  157.49  4661.5  155.56  4744.9  155.01    4750  155.91  4798.7  153.87
  4828.2  153.38  4833.4     154  4869.9  152.13  4875.1  152.87  4911.6  150.41
  4963.6  149.67 4976.14148.5205  4994.3  147.41    4998  146.15  5005.2  147.26
 5033.52148.5072  5165.2  151.15  5243.3   154.3  5406.6  158.68  5527.1  158.43
#Mann= 5 ,-1 , 0
  4074.3     .11       0 4976.14     .09       0 5033.52     .11       0
  5165.2     .17       0  5243.3     .11       0
#XS Ineff= 2 , 0
       0                  5111.2       0  149.94
Permanent Ineff=
       F       F
Bank Sta=4976.14,5033.52
XS Rating Curve= 0 ,0
Exp/Cntr=0.3,0.1

Type RM Length L Ch R = 1 ,1511    ,511,511,511
BEGIN DESCRIPTION:
Crystal Creek 015 3.0
END DESCRIPTION:
XS GIS Cut Line= 3
      3868404.36     10098772.06      3867938.24     10099476.86
      3868206.86     10100193.47
#Sta/Elev= 30
    4155  153.75  4324.3  147.43  4345.6   149.8  4360.4  147.56  4396.5  147.91
  4405.6  146.54  4441.6  148.53  4525.9  148.58  4598.1  150.33  4693.3   150.2
  4757.6  148.14  4772.7  149.61  4793.7  149.83  4814.8  147.66  4938.2  146.31
  4968.3  144.26  4997.8   142.8  5016.8  144.24    5072  143.77  5157.5  146.94
  5207.3  146.06  5328.4  150.32  5438.8  148.78  5498.6  150.06  5579.4  151.64
    5615  154.36  5664.8  155.22  5670.2  156.38  5706.2     158  5765.3  158.72
#Mann= 5 ,-1 , 0
    4155     .11       0  4968.3     .09       0  5016.8     .11       0
  5498.6     .17       0  5706.2     .11       0
Bank Sta=4968.3,5016.8
XS Rating Curve= 0 ,0
Exp/Cntr=0.3,0.1

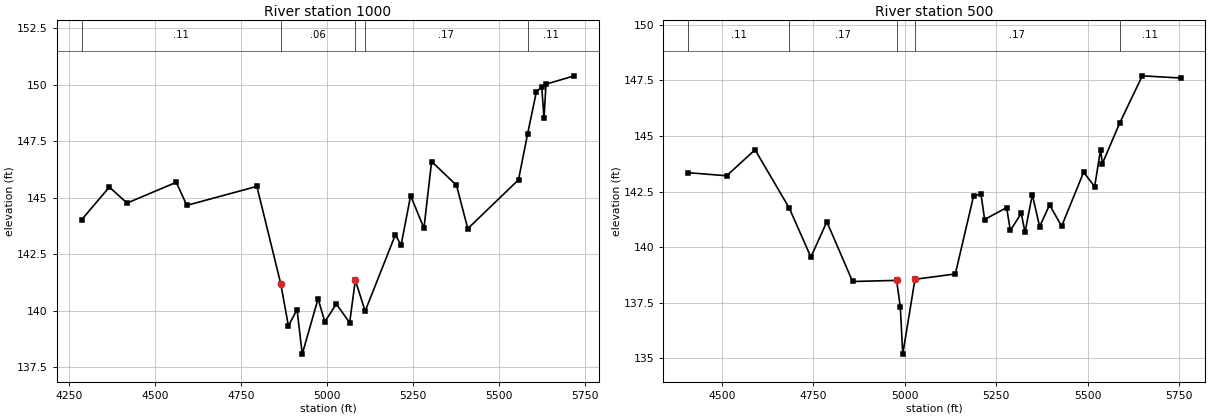
Type RM Length L Ch R = 1 ,1000    ,500,500,500
BEGIN DESCRIPTION:
Crystal Creek 015 2.0
END DESCRIPTION:
XS GIS Cut Line= 4
      3867578.57     10098742.06      3867495.23     10099132.69
      3867602.98     10099426.86      3867932.74     10100064.99
#Sta/Elev= 30
  4287.3  144.02  4368.1  145.47  4419.2  144.76  4562.4  145.68    4593  144.66
  4796.5   145.5    4866  141.18    4888  139.33  4913.2  140.05  4928.2  138.08
  4974.2  140.53  4993.8  139.51  5027.2   140.3  5065.9  139.47  5082.4  141.35
  5110.9  139.98  5198.7  143.36  5215.3   142.9    5243  145.09  5281.7  143.65
  5303.9   146.6  5376.2  145.55    5409  143.63  5556.3  145.79  5582.7  147.82
  5608.3  149.69  5623.8  149.89  5630.4  148.51  5636.1  150.02  5718.3  150.39
#Mann= 5 ,-1 , 0
  4287.3     .11       0    4866     .06       0  5082.4     .11       0
  5110.9     .17       0  5582.7     .11       0
#XS Ineff= 2 , 0
       0                  5082.4       0  141.35
Permanent Ineff=
       F       F
Bank Sta=4866,5082.4
XS Rating Curve= 0 ,0
Exp/Cntr=0.3,0.1

Type RM Length L Ch R = 1 ,500     ,0,0,0
BEGIN DESCRIPTION:
Crystal Creek 015 1.0
END DESCRIPTION:
XS GIS Cut Line= 4
      3867526.45     10098710.85      3867297.32     10098960.82
      3867274.16     10099212.95      3867328.56     10099965.99
#Sta/Elev= 30
  4407.7  143.35  4513.2  143.21  4590.9  144.38  4684.6  141.75  4743.6  139.55
  4787.2  141.14  4857.5  138.45    4978   138.5  4988.1   137.3  4994.8  135.18
  5028.2  138.55  5138.5  138.79  5188.6  142.31  5208.7  142.38  5218.7  141.24
  5278.8  141.78  5288.9  140.75  5318.9  141.52    5329  140.66    5349  142.36
  5369.1  140.92  5396.2   141.9  5429.2  140.94  5489.4  143.37  5519.5  142.72
  5535.7  144.39  5540.7  143.76  5587.6  145.57  5649.8  147.71    5755  147.61
#Mann= 5 ,-1 , 0
  4407.7     .11       0  4684.6     .17       0    4978     .09       0
  5028.2     .17       0  5587.6     .11       0
#XS Ineff= 2 , 0
       0  4787.2  141.14               0
Permanent Ineff=
       F       F
Bank Sta=4978,5028.2
XS Rating Curve= 0 ,0
Exp/Cntr=0.3,0.1

Chan Stop Cuts=-1
Use User Specified Reach Order=0
Composite Channel Slope=5

--- Crystal Creek 015.g10 (geometry) ---

Geom Title=Existing Conditions
Program Version=4.10

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
River Reach=Crystal Creek 01,Reach-1

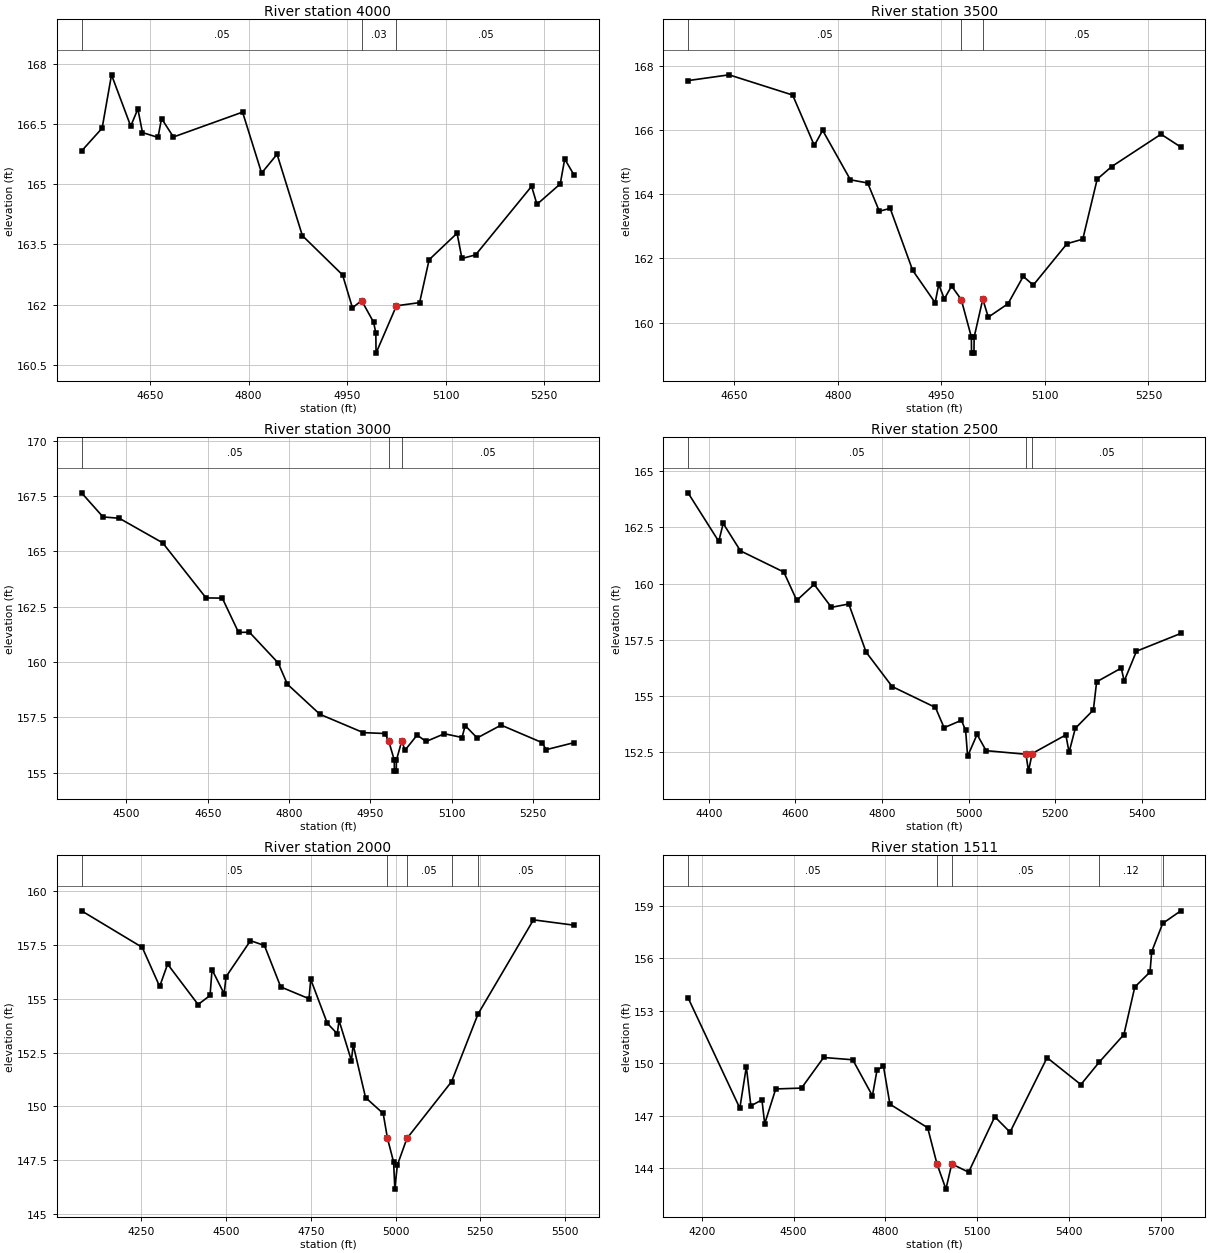
Type RM Length L Ch R = 1 ,4000    ,500,500,500
BEGIN DESCRIPTION:
Crystal Creek 015 8.0
END DESCRIPTION:
XS GIS Cut Line= 3
      3869656.63     10100858.92       3869239.3     10101037.93
      3869059.52      10101272.7
#Sta/Elev= 30
  4545.9  165.83  4577.2   166.4  4591.5  167.73  4620.7  166.45  4631.6  166.88
  4638.6  166.29  4662.2  166.17  4667.6  166.64  4685.7  166.18  4790.9   166.8
  4819.9  165.28  4843.4  165.75  4881.9  163.72  4943.1  162.74  4958.1  161.92
  4972.1   162.1  4990.3  161.56  4993.7  161.29    4994  160.79    5025  161.97
  5060.3  162.05  5074.8  163.12  5117.3  163.78  5124.7  163.15  5145.5  163.24
  5230.7  164.95  5238.9   164.5  5274.3  165.01  5281.1  165.63  5295.7  165.22
#Mann= 3 , 0 , 0
  4545.9     .05       0  4972.1     .03       0    5025     .05       0
Bank Sta=4972.1,5025
XS Rating Curve= 0 ,0
Exp/Cntr=0.3,0.1

Type RM Length L Ch R = 1 ,3500    ,500,500,500
BEGIN DESCRIPTION:
Crystal Creek 015 7.0
END DESCRIPTION:
XS GIS Cut Line= 3
      3869402.65      10100549.4      3869004.24     10100672.87
      3868834.05     10100916.15
#Sta/Elev= 30
  4582.9  167.54  4642.4  167.72  4734.5  167.09  4765.9  165.52    4778  165.99
  4818.2  164.45  4843.2  164.35  4860.1  163.47  4875.8  163.56  4908.4  161.63
    4941  160.62  4946.2  161.19  4954.3  160.74  4964.8  161.14  4978.8  160.72
  4993.5  159.55  4993.7  159.05  4997.2  159.05  4997.5  159.55    5010  160.73
    5018  160.17  5046.6  160.59  5068.6  161.44  5083.2  161.17  5132.1  162.46
  5154.9   162.6  5175.8  164.47  5196.7  164.86  5268.3  165.87  5296.9  165.47
#Mann= 3 , 0 , 0
  4582.9     .05       0  4978.8     .03       0    5010     .05       0
Bank Sta=4978.8,5010
XS Rating Curve= 0 ,0
Exp/Cntr=0.3,0.1

Type RM Length L Ch R = 1 ,3000    ,500,500,500
BEGIN DESCRIPTION:
Crystal Creek 015 6.0
END DESCRIPTION:
XS GIS Cut Line= 3
      3869387.45     10100310.69      3868804.61     10100319.39
      3868515.03     10100469.11
#Sta/Elev= 30
  4417.1  167.65  4456.7  166.56  4486.7   166.5  4566.7  165.39  4646.7   162.9
  4676.7  162.89  4706.7  161.34  4726.7  161.35  4779.8  159.96  4796.7     159
  4856.7  157.64  4936.8  156.81  4976.8  156.77 4983.83 156.419  4993.9  155.57
  4994.1  155.07  4997.6  155.07  4997.9  155.57  5007.6  156.42  5013.9  156.02
    5036   156.7  5052.6  156.41  5086.4  156.76    5119  156.59  5124.6  157.13
  5146.8  156.57    5191  157.15  5266.5  156.36    5274  156.04    5326  156.36
#Mann= 3 , 0 , 0
  4417.1     .05       0 4983.83     .03       0  5007.6     .05       0
Bank Sta=4983.83,5007.6
XS Rating Curve= 0 ,0
Exp/Cntr=0.3,0.1

Type RM Length L Ch R = 1 ,2500    ,500,500,500
BEGIN DESCRIPTION:
Crystal Creek 015 5.0
END DESCRIPTION:
XS GIS Cut Line= 3
      3869328.85     10099913.56      3868688.15     10099934.68
      3868315.35     10100262.98
#Sta/Elev= 30
  4352.2  164.04  4423.2  161.88  4433.4  162.68  4473.3  161.46  4573.3  160.52
  4603.3  159.26  4643.4  159.97  4683.4  158.95  4723.4   159.1  4763.4  156.96
  4823.5  155.43  4923.5   154.5  4943.5   153.6  4983.5  153.93  4993.2  153.48
  4997.8  152.33  5019.6   153.3  5040.5  152.58  5132.5  152.42  5138.4  151.67
  5146.8  152.45  5224.6  153.28  5232.1  152.51  5246.4  153.57  5288.2  154.39
  5295.7  155.64  5352.6  156.25  5359.3  155.67  5387.7     157    5490  157.79
#Mann= 3 , 0 , 0
  4352.2     .05       0  5132.5     .03       0  5146.8     .05       0
Bank Sta=5132.5,5146.8
XS Rating Curve= 0 ,0
Exp/Cntr=0.3,0.1

Type RM Length L Ch R = 1 ,2000    ,489,489,489
BEGIN DESCRIPTION:
Crystal Creek 015 4.0
END DESCRIPTION:
XS GIS Cut Line= 3
      3869211.62     10099466.51      3868312.29     10099685.88
      3868267.85      10100211.1
#Sta/Elev= 30
  4074.3   159.1  4253.2   157.4  4304.6  155.58    4328  156.62  4417.9  154.74
  4453.1  155.16    4459  156.36  4494.7  155.24  4500.2  156.03  4572.3  157.71
  4613.4  157.49  4661.5  155.56  4744.9  155.01    4750  155.91  4798.7  153.87
  4828.2  153.38  4833.4     154  4869.9  152.13  4875.1  152.87  4911.6  150.41
  4963.6  149.67 4976.14 148.521  4994.3  147.41    4998  146.15  5005.2  147.26
 5033.52 148.507  5165.2  151.15  5243.3   154.3  5406.6  158.68  5527.1  158.43
#Mann= 5 ,-1 , 0
  4074.3     .05       0 4976.14     .07       0 5033.52     .05       0
  5165.2     .12       0  5243.3     .05       0
Bank Sta=4976.14,5033.52
XS Rating Curve= 0 ,0
Exp/Cntr=0.3,0.1

Type RM Length L Ch R = 1 ,1511    ,511,511,511
BEGIN DESCRIPTION:
Crystal Creek 015 3.0
END DESCRIPTION:
XS GIS Cut Line= 3
      3868404.36     10098772.06      3867938.24     10099476.86
      3868206.86     10100193.47
#Sta/Elev= 30
    4155  153.75  4324.3  147.43  4345.6   149.8  4360.4  147.56  4396.5  147.91
  4405.6  146.54  4441.6  148.53  4525.9  148.58  4598.1  150.33  4693.3   150.2
  4757.6  148.14  4772.7  149.61  4793.7  149.83  4814.8  147.66  4938.2  146.31
  4968.3  144.26  4997.8   142.8  5016.8  144.24    5072  143.77  5157.5  146.94
  5207.3  146.06  5328.4  150.32  5438.8  148.78  5498.6  150.06  5579.4  151.64
    5615  154.36  5664.8  155.22  5670.2  156.38  5706.2     158  5765.3  158.72
#Mann= 5 ,-1 , 0
    4155     .05       0  4968.3     .07       0  5016.8     .05       0
  5498.6     .12       0  5706.2     .05       0
Bank Sta=4968.3,5016.8
XS Rating Curve= 0 ,0
Exp/Cntr=0.3,0.1

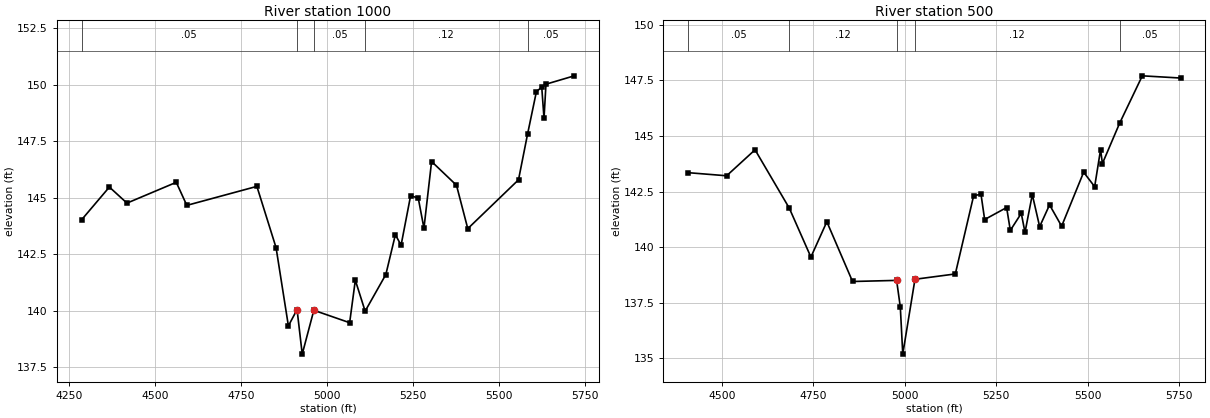
Type RM Length L Ch R = 1 ,1000    ,500,500,500
BEGIN DESCRIPTION:
Crystal Creek 015 2.0
END DESCRIPTION:
XS GIS Cut Line= 4
      3867578.57     10098742.06      3867495.23     10099132.69
      3867602.98     10099426.86      3867932.74     10100064.99
#Sta/Elev= 30
  4287.3  144.02  4368.1  145.47  4419.2  144.76  4562.4  145.68    4593  144.66
  4796.5   145.5  4852.2  142.79    4888  139.33  4913.2  140.05  4928.2  138.08
  4961.9  140.02  5065.9  139.47  5082.4  141.35  5110.9  139.98    5171   141.6
  5198.7  143.36  5215.3   142.9    5243  145.09  5265.2  144.98  5281.7  143.65
  5303.9   146.6  5376.2  145.55    5409  143.63  5556.3  145.79  5582.7  147.82
  5608.3  149.69  5623.8  149.89  5630.4  148.51  5636.1  150.02  5718.3  150.39
#Mann= 5 ,-1 , 0
  4287.3     .05       0  4913.2    .037       0  4961.9     .05       0
  5110.9     .12       0  5582.7     .05       0
Bank Sta=4913.2,4961.9
XS Rating Curve= 0 ,0
Exp/Cntr=0.3,0.1

Type RM Length L Ch R = 1 ,500     ,0,0,0
BEGIN DESCRIPTION:
Crystal Creek 015 1.0
END DESCRIPTION:
XS GIS Cut Line= 4
      3867526.45     10098710.85      3867297.32     10098960.82
      3867274.16     10099212.95      3867328.56     10099965.99
#Sta/Elev= 30
  4407.7  143.35  4513.2  143.21  4590.9  144.38  4684.6  141.75  4743.6  139.55
  4787.2  141.14  4857.5  138.45    4978   138.5  4988.1   137.3  4994.8  135.18
  5028.2  138.55  5138.5  138.79  5188.6  142.31  5208.7  142.38  5218.7  141.24
  5278.8  141.78  5288.9  140.75  5318.9  141.52    5329  140.66    5349  142.36
  5369.1  140.92  5396.2   141.9  5429.2  140.94  5489.4  143.37  5519.5  142.72
  5535.7  144.39  5540.7  143.76  5587.6  145.57  5649.8  147.71    5755  147.61
#Mann= 5 ,-1 , 0
  4407.7     .05       0  4684.6     .12       0    4978     .07       0
  5028.2     .12       0  5587.6     .05       0
Bank Sta=4978,5028.2
XS Rating Curve= 0 ,0
Exp/Cntr=0.3,0.1