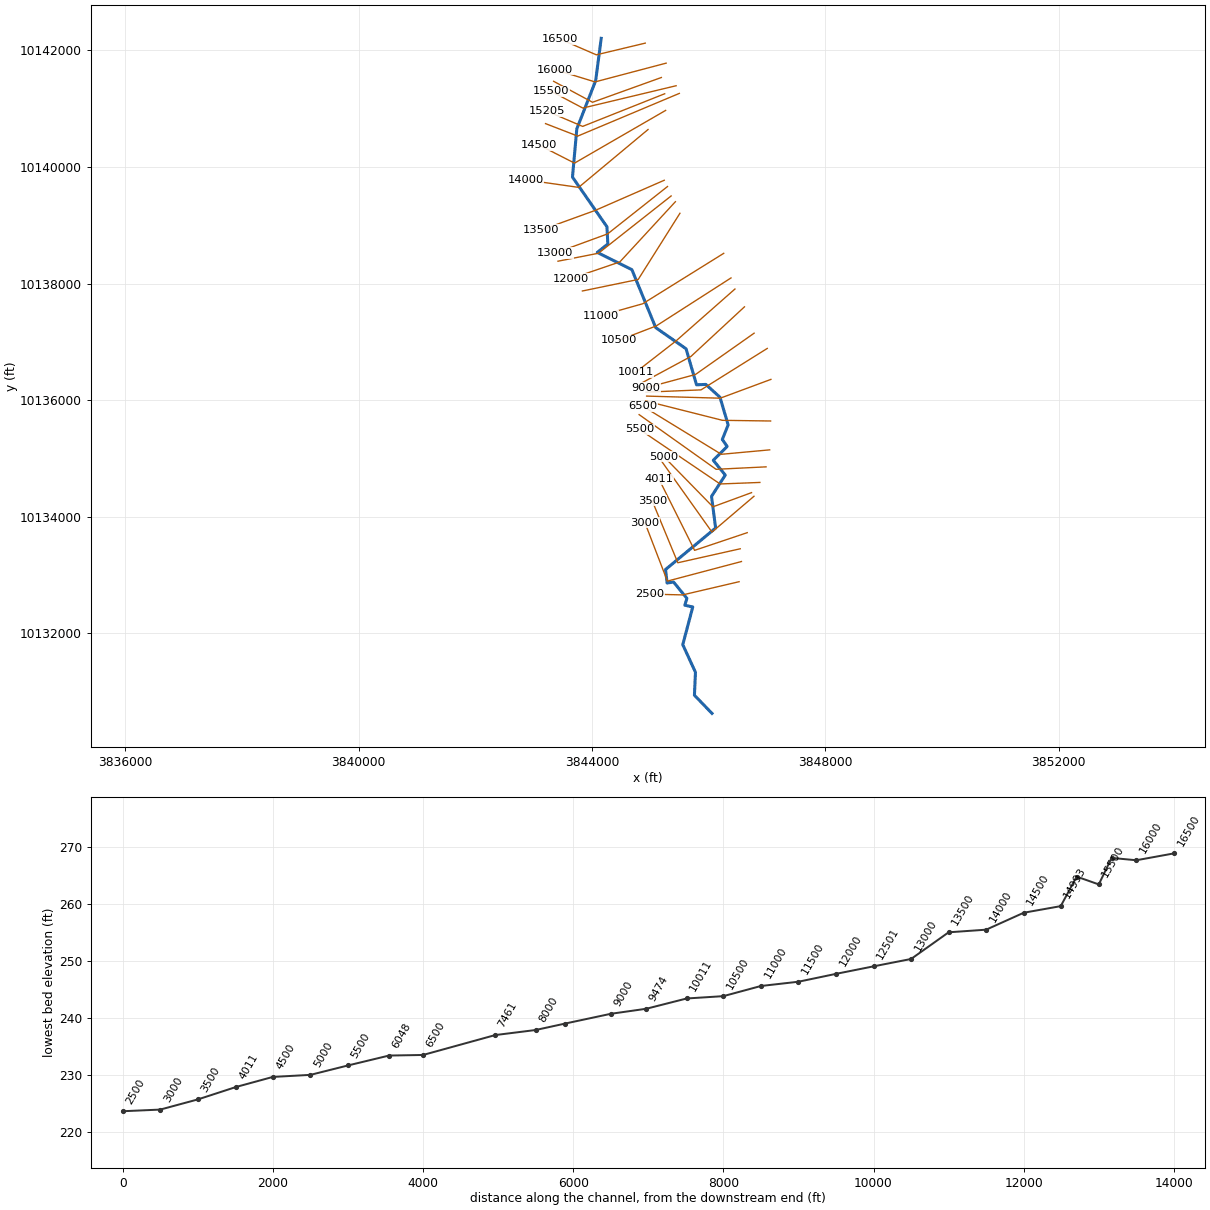
--- Crystal Creek 024.prj (project) ---

Proj Title=Crystal Creek 024 Base Level Engineering
Current Plan=p01
Default Exp/Contr=0.3,0.1
English Units
Geom File=g01
Flow File=f01
Flow File=f02
Plan File=p01
Y Axis Title=Elevation
X Axis Title(PF)=Main Channel Distance
X Axis Title(XS)=Station
BEGIN DESCRIPTION:
Crystal Creek 024
END DESCRIPTION:
DSS Export Rating Curves= 0
DSS Export Rating Curve Sorted= 0
DSS Export Volume Flow Curves= 0
DXF OffsetX= 0
DXF OffsetY= 0
DXF ScaleX= 1
DXF ScaleY= 10

--- Crystal Creek 024.p01 (plan) ---

Plan Title=Multiple Run
Short Identifier=Multiple
Geom File=g01
Flow File=f01
Subcritical Flow
K Sum by GR= 0
Std Step Tol= 0.01
Critical Tol= 0.01
Num of Std Step Trials= 20
Max Error Tol= 0.3
Flow Tol Ratio= 0.001
Split Flow NTrial= 30
Split Flow Tol= 0.02
Split Flow Ratio= 0.02
Log Output Level= 0
Friction Slope Method= 1
Unsteady Friction Slope Method= 2
Unsteady Bridges Friction Slope Method= 1
Parabolic Critical Depth
Global Vel Dist=  1 , 1 , 1
Global Log Level= 0
CheckData=True
Encroach Param= -1, 0, 0, 0
BEGIN DESCRIPTION:
Multiple Run
END DESCRIPTION:

--- Crystal Creek 024.f01 (steady flow) ---

Flow Title=Multiple
Program Version=4.10
Number of Profiles= 7
Profile Names=10-year,25-year,50-year,1pct_min,100-year,1pct_plu,500-year
River Rch & RM=Crystal Creek 02,Reach-1         ,16500
     627     836    1119     492    1486    4488    2709
River Rch & RM=Crystal Creek 02,Reach-1         ,9000
     795    1075    1450     643    1942    5865    3598
Boundary for River Rch & Prof#=Crystal Creek 02,Reach-1         , 1
Up Type= 0
Dn Type= 3
Dn Slope=0.006
Boundary for River Rch & Prof#=Crystal Creek 02,Reach-1         , 2
Up Type= 0
Dn Type= 3
Dn Slope=0.006
Boundary for River Rch & Prof#=Crystal Creek 02,Reach-1         , 3
Up Type= 0
Dn Type= 3
Dn Slope=0.006
Boundary for River Rch & Prof#=Crystal Creek 02,Reach-1         , 4
Up Type= 0
Dn Type= 3
Dn Slope=0.006
Boundary for River Rch & Prof#=Crystal Creek 02,Reach-1         , 5
Up Type= 0
Dn Type= 3
Dn Slope=0.006
Boundary for River Rch & Prof#=Crystal Creek 02,Reach-1         , 6
Up Type= 0
Dn Type= 3
Dn Slope=0.006
Boundary for River Rch & Prof#=Crystal Creek 02,Reach-1         , 7
Up Type= 0
Dn Type= 3
Dn Slope=0.006
DSS Import GetInterval= 0
DSS Import GetPeak= 0
DSS Import FillOption= 0

--- Crystal Creek 024.f02 (steady flow) ---

Flow Title=Orig_BLE_Flow
Program Version=4.10
Number of Profiles= 7
Profile Names=10-year,25-year,50-year,1pct_min,100-year,1pct_plu,500-year
River Rch & RM=Crystal Creek 02,Reach-1         ,16500
     627     820     973     378    1143    3451    1575
River Rch & RM=Crystal Creek 02,Reach-1         ,9000
     795    1054    1261     495    1494    4511    2092
Boundary for River Rch & Prof#=Crystal Creek 02,Reach-1         , 1
Up Type= 0
Dn Type= 3
Dn Slope=0.006
Boundary for River Rch & Prof#=Crystal Creek 02,Reach-1         , 2
Up Type= 0
Dn Type= 3
Dn Slope=0.006
Boundary for River Rch & Prof#=Crystal Creek 02,Reach-1         , 3
Up Type= 0
Dn Type= 3
Dn Slope=0.006
Boundary for River Rch & Prof#=Crystal Creek 02,Reach-1         , 4
Up Type= 0
Dn Type= 3
Dn Slope=0.006
Boundary for River Rch & Prof#=Crystal Creek 02,Reach-1         , 5
Up Type= 0
Dn Type= 3
Dn Slope=0.006
Boundary for River Rch & Prof#=Crystal Creek 02,Reach-1         , 6
Up Type= 0
Dn Type= 3
Dn Slope=0.006
Boundary for River Rch & Prof#=Crystal Creek 02,Reach-1         , 7
Up Type= 0
Dn Type= 3
Dn Slope=0.006
DSS Import GetInterval= 0
DSS Import GetPeak= 0
DSS Import FillOption= 0

--- Crystal Creek 024.g01 (geometry) ---

Geom Title=Existing Conditions
Program Version=4.10

River Reach=Crystal Creek 02,Reach-1
Reach XY= 30
       3844158.2     10142207.66       3844063.1     10141481.48
      3843739.71      10140654.1      3843665.85     10139827.19
      3844256.53     10138975.22      3844271.77     10138680.39
      3844090.74       10138536.      3844684.15     10138239.81
      3845091.83     10137246.04      3845612.65     10136882.61
      3845791.52     10136264.83      3845951.17     10136272.01
      3846193.39     10136051.88      3846334.03     10135577.93
      3846233.33     10135327.97      3846316.43     10135207.71
      3846078.55     10134970.86      3846284.24     10134716.94
       3846048.7     10134351.64      3846118.95     10133808.73
      3845260.76     10133097.14      3845287.28     10132865.37
      3845397.97     10132882.67      3845626.44     10132602.35
      3845591.64     10132484.73      3845727.26     10132454.57
      3845555.89     10131807.89      3845773.39     10131334.98
      3845755.91     10130940.78      3846056.25     10130629.73

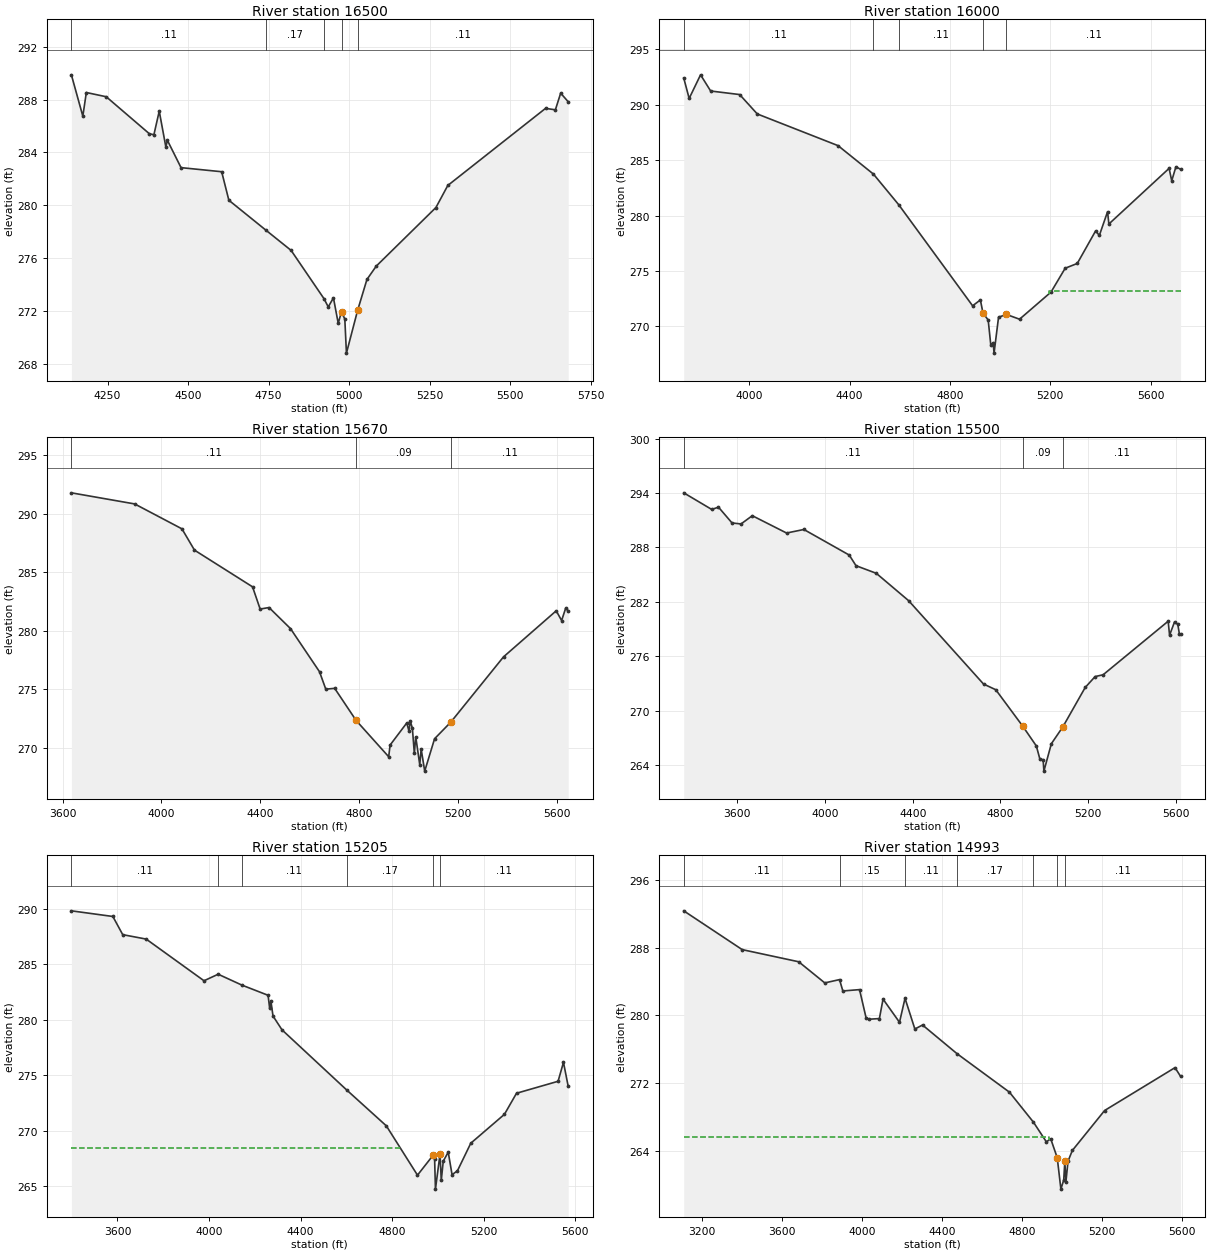
Type RM Length L Ch R = 1 ,16500   ,500,500,500
BEGIN DESCRIPTION:
Crystal Creek 024 32.0
END DESCRIPTION:
XS GIS Cut Line= 3
      3844913.02     10142125.36      3844074.57     10141924.82
      3843451.35     10142195.35
#Sta/Elev= 30
  4137.9  289.87  4173.4  286.74  4184.3  288.53    4246  288.21  4379.7  285.41
  4393.9  285.33  4410.5  287.12  4430.9  284.42    4436   284.9  4478.1  282.84
  4604.2  282.53  4626.5  280.37  4742.6  278.08  4819.7  276.57  4921.5  272.92
  4934.9  272.29    4951  272.98  4965.8  271.05  4976.1  271.94  4986.3  271.36
  4991.3  268.79    5026  272.03  5054.9  274.37  5083.8  275.38    5269  279.82
  5305.8  281.49  5609.1  287.33  5639.6  287.22    5656  288.48  5679.4  287.83
#Mann= 5 ,-1 , 0
  4137.9     .11       0  4742.6     .17       0  4921.5     .11       0
  4976.1     .09       0    5026     .11       0
Bank Sta=4976.1,5026
XS Rating Curve= 0 ,0
Exp/Cntr=0.3,0.1

Type RM Length L Ch R = 1 ,16000   ,330,330,330
BEGIN DESCRIPTION:
Crystal Creek 024 31.0
END DESCRIPTION:
XS GIS Cut Line= 3
      3845271.19     10141782.26       3844052.1     10141460.26
      3843364.13     10141671.27
#Sta/Elev= 30
  3739.1  292.41  3760.7  290.57  3806.1   292.7  3846.4  291.24    3962  290.92
  4032.2  289.17  4354.3  286.31  4495.4  283.74  4596.4  280.97  4890.6  271.86
  4921.6  272.39    4932   271.2  4952.7  270.58    4963  268.34  4972.7  268.53
  4976.1  267.59    4994  270.83  5025.4  271.08  5077.7  270.65  5203.2   273.1
  5259.6  275.25  5307.8  275.68    5381  278.62  5395.8  278.21  5428.6  280.35
  5433.8  279.24  5673.9  284.26  5684.3  283.14    5701   284.4  5719.6  284.18
#Mann= 5 ,-1 , 0
  3739.1     .11       0  4495.4     .17       0  4596.4     .11       0
    4932     .09       0  5025.4     .11       0
#XS Ineff= 2 , 0
       0                  5194.1       0  273.24
Permanent Ineff=
       F       F
Bank Sta=4932,5025.4
XS Rating Curve= 0 ,0
Exp/Cntr=0.3,0.1

Type RM Length L Ch R = 1 ,15670   ,170,170,170
BEGIN DESCRIPTION:
Mapping XS 911f145d
END DESCRIPTION:
XS GIS Cut Line= 3
      3845188.88     10141535.74       3844009.2     10141111.27
       3843342.7     10141470.56
#Sta/Elev= 30
  3635.9   291.8  3892.1  290.85  4083.4  288.72  4134.1   286.9  4369.2  283.76
  4399.9  281.86  4435.9  281.99  4522.7  280.19  4640.2   276.5  4665.6  275.01
  4701.6  275.08  4788.5  272.33  4920.2  269.23  4925.9  270.23  4993.4  272.12
  5002.1  271.44  5007.8  272.27  5016.1  271.66    5024  269.52  5029.7  270.94
  5045.9  268.55  5051.6  269.89    5066     268  5105.9  270.77  5171.6  272.19
  5384.9  277.77  5598.2  281.71  5620.1  280.88  5636.3  281.92  5646.8  281.72
#Mann= 3 , 0 , 0
  3635.9     .11       0  4788.5     .09       0  5171.6     .11       0
Bank Sta=4788.5,5171.6
XS Rating Curve= 0 ,0
Exp/Cntr=0.3,0.1

Type RM Length L Ch R = 1 ,15500   ,295,295,295
BEGIN DESCRIPTION:
Crystal Creek 024 30.0
END DESCRIPTION:
XS GIS Cut Line= 3
      3845441.98     10141394.53      3843842.66     10141011.71
      3843293.51     10141302.94
#Sta/Elev= 30
  3355.5  294.02  3483.1  292.19    3514  292.44  3575.7   290.7  3616.8  290.59
  3668.2   291.5  3824.5  289.59  3903.5  289.98  4110.4  287.16  4141.2  285.99
  4233.8  285.15  4381.4  282.13  4722.8  272.95  4778.7  272.32  4902.1  268.29
  4963.8  266.12  4980.2  264.65  4994.7  264.61  4998.2  263.35  5032.2  266.37
  5084.7  268.23  5186.6  272.57  5231.8  273.77  5268.4  273.97    5565  279.87
  5571.4  278.33    5594  279.79    5609  279.52  5616.3  278.45  5621.6  278.45
#Mann= 3 , 0 , 0
  3355.5     .11       0  4902.1     .09       0  5084.7     .11       0
Bank Sta=4902.1,5084.7
XS Rating Curve= 0 ,0
Exp/Cntr=0.3,0.1

Type RM Length L Ch R = 1 ,15205   ,212,212,212
BEGIN DESCRIPTION:
Mapping XS cc6617fc
END DESCRIPTION:
XS GIS Cut Line= 3
      3845246.18      10141257.1      3843839.93     10140697.21
      3843235.75     10140955.02
#Sta/Elev= 30
  3398.6  289.83  3579.8  289.32  3622.9  287.68  3725.4  287.28    3978  283.52
  4039.9  284.11  4143.4  283.13  4257.9  282.21  4264.9  281.02  4270.2   281.7
  4279.4  280.34  4318.8  279.09  4600.6  273.68  4774.5  270.43  4910.6  265.98
  4979.7   267.8  4985.5  267.41  4989.1  264.72  5009.1  267.89  5014.5   265.5
  5023.2  267.24  5044.9  268.06  5061.7  266.02  5085.3  266.38  5143.4  268.86
  5290.5  271.47  5343.2  273.37  5524.8  274.45  5548.4  276.16  5569.1  273.99
#Mann= 6 ,-1 , 0
  3398.6     .11       0  4039.9     .15       0  4143.4     .11       0
  4600.6     .17       0  4979.7     .09       0  5009.1     .11       0
#XS Ineff= 2 , 0
       0  4839.3  268.41               0
Permanent Ineff=
       F       F
Bank Sta=4979.7,5009.1
XS Rating Curve= 0 ,0
Exp/Cntr=0.3,0.1

Type RM Length L Ch R = 1 ,14993   ,493,493,493
BEGIN DESCRIPTION:
Crystal Creek 024 29.0
END DESCRIPTION:
XS GIS Cut Line= 3
      3845497.05     10141263.36      3843755.81     10140530.95
      3843203.84     10140744.94
#Sta/Elev= 30
    3111  292.32    3403  287.75  3685.1  286.32  3815.3  283.83    3889  284.22
  3905.5  282.88  3988.9  283.04  4021.4  279.73  4035.1  279.55    4088  279.63
  4106.3  281.92  4188.4  279.19    4216  282.02  4265.1   278.4  4303.5  278.87
  4475.3   275.5  4737.4  270.96  4857.2  267.43  4921.8  265.11  4943.5  265.47
  4976.1  263.24  4994.4  259.54  5008.5  260.62    5014   262.8  5019.4   260.4
    5030  262.83  5051.4  264.09  5212.7   268.8  5564.2  273.85    5592  272.82
#Mann= 7 ,-1 , 0
    3111     .11       0    3889     .15       0    4216     .11       0
  4475.3     .17       0  4857.2     .11       0  4976.1     .07       0
    5014     .11       0
#XS Ineff= 2 , 0
       0  4936.7  265.65               0
Permanent Ineff=
       F       F
Bank Sta=4976.1,5014
XS Rating Curve= 0 ,0
Exp/Cntr=0.3,0.1

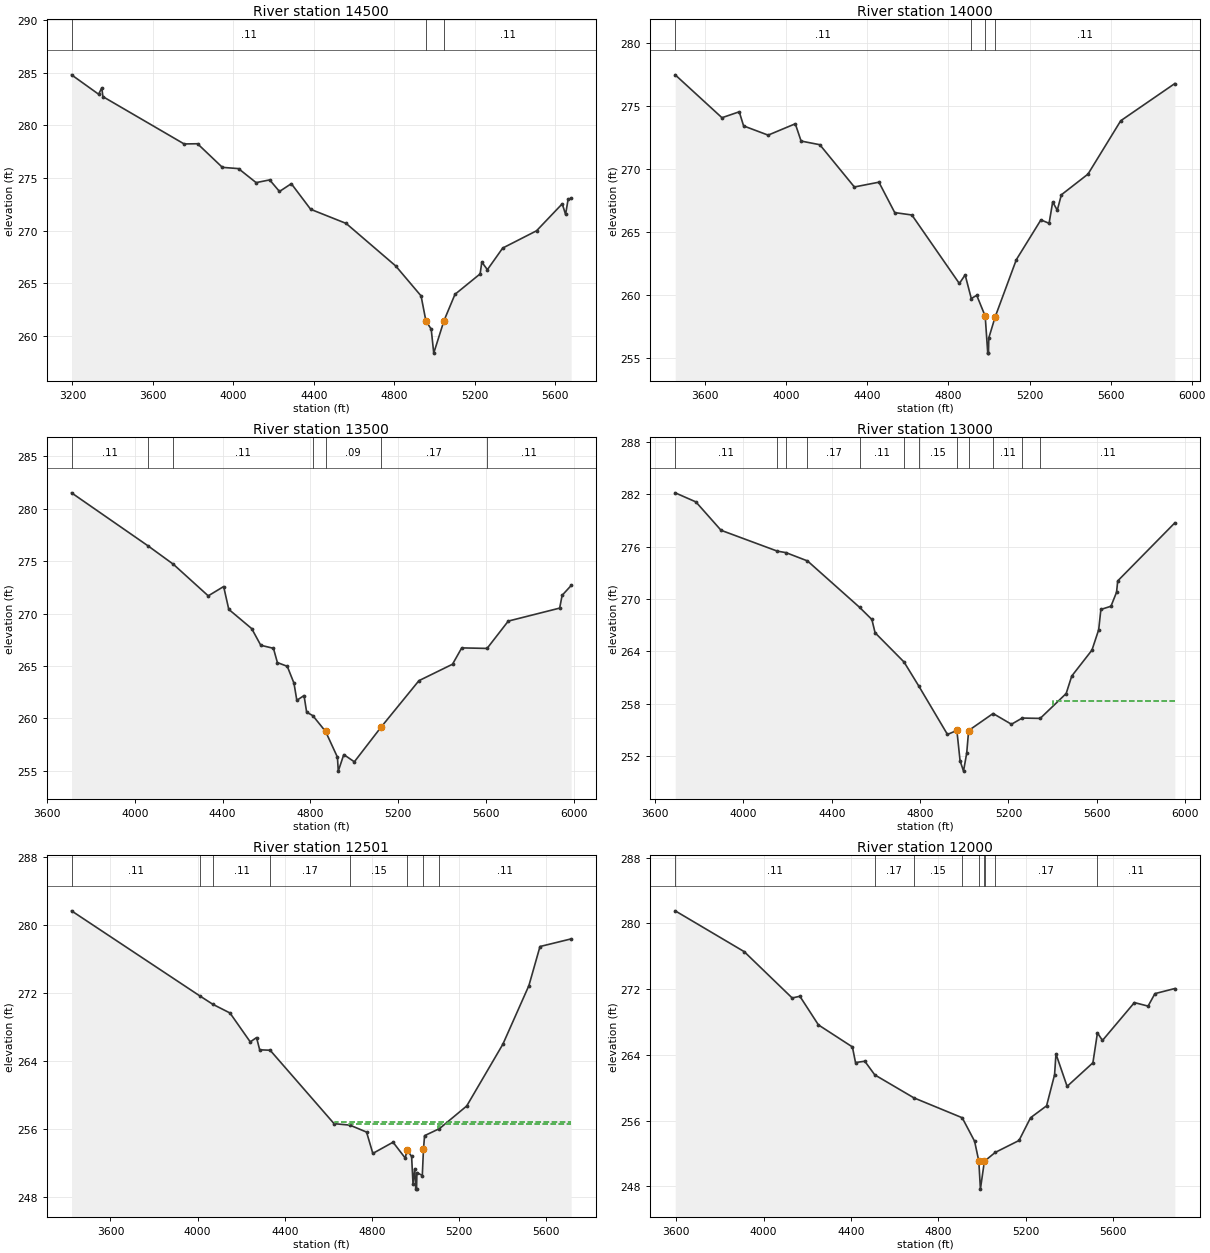
Type RM Length L Ch R = 1 ,14500   ,500,500,500
BEGIN DESCRIPTION:
Crystal Creek 024 28.0
END DESCRIPTION:
XS GIS Cut Line= 3
      3845262.65     10140971.68      3843700.75     10140067.57
      3843094.49     10140376.86
#Sta/Elev= 30
  3195.3  284.79    3330  282.95  3345.7  283.55  3351.5  282.72  3755.5  278.23
  3822.1  278.25  3945.6  276.01  4025.9  275.89  4113.6  274.56  4180.9  274.82
  4229.7  273.72  4288.6  274.46  4384.7  272.03  4561.2  270.69    4808  266.65
    4934  263.81 4957.99261.4434  4984.5  260.65    4997  258.38  5048.2  261.47
  5102.7  263.96  5227.8   265.9  5236.1  267.02  5263.9   266.3    5340  268.35
  5508.4  269.99  5636.2  272.55  5652.8  271.54  5665.6     273  5680.6  273.06
#Mann= 3 , 0 , 0
  3195.3     .11       0 4957.99     .06       0  5048.2     .11       0
#XS Ineff= 2 , 0
       0  4925.7  263.83               0
Permanent Ineff=
       F       F
Bank Sta=4957.99,5048.2
XS Rating Curve= 0 ,0
Exp/Cntr=0.3,0.1

Type RM Length L Ch R = 1 ,14000   ,500,500,500
BEGIN DESCRIPTION:
Crystal Creek 024 27.0
END DESCRIPTION:
XS GIS Cut Line= 3
      3844960.56     10140643.55      3843771.42     10139651.52
      3842863.54     10139780.54
#Sta/Elev= 30
  3451.4  277.47  3682.2  274.07  3767.5  274.54    3789  273.42    3910  272.69
  4044.1  273.59  4072.7  272.22  4165.1  271.93  4335.6  268.58  4456.7  268.96
  4534.8  266.55  4619.4  266.36  4853.6  260.93  4882.3  261.61  4912.5  259.74
  4939.5  259.99  4981.2  258.34  4993.8  255.41  4997.3  255.41  4999.1  256.62
  5030.6  258.29  5134.9  262.82  5256.1  265.97  5296.5   265.7  5314.2  267.39
  5336.9  266.74  5357.1  267.96  5488.4   269.6    5650  273.83    5917  276.78
#Mann= 4 ,-1 , 0
  3451.4     .11       0  4912.5     .15       0  4981.2     .09       0
  5030.6     .11       0
#XS Ineff= 2 , 0
       0  4882.3  261.61               0
Permanent Ineff=
       F       F
Bank Sta=4981.2,5030.6
XS Rating Curve= 0 ,0
Exp/Cntr=0.3,0.1

Type RM Length L Ch R = 1 ,13500   ,500,500,500
BEGIN DESCRIPTION:
Crystal Creek 024 26.0
END DESCRIPTION:
XS GIS Cut Line= 3
      3845238.55     10139773.58      3844057.73     10139257.18
      3843129.12     10138919.79
#Sta/Elev= 30
  3711.2  281.53  4060.2  276.46  4175.1  274.71  4334.2  271.69  4404.4  272.58
  4427.8   270.4  4532.3  268.56  4573.6  266.97  4631.3  266.68  4649.3  265.32
  4694.3  264.96  4724.9  263.35  4737.9  261.71  4770.7  262.17  4782.6  260.58
  4810.7  260.25  4868.9  258.74    4923  256.28  4926.7  254.95  4951.8  256.53
    5000  255.84  5121.3  259.14  5294.3  263.59  5447.3  265.16  5489.3  266.72
  5604.8  266.67  5701.4  269.28  5935.6  270.52  5946.8  271.74    5988  272.68
#Mann= 7 ,-1 , 0
  3711.2     .11       0  4060.2     .17       0  4175.1     .11       0
  4810.7     .15       0  4868.9     .09       0  5121.3     .17       0
  5604.8     .11       0
Bank Sta=4868.9,5121.3
XS Rating Curve= 0 ,0
Exp/Cntr=0.3,0.1

Type RM Length L Ch R = 1 ,13000   ,499,499,499
BEGIN DESCRIPTION:
Crystal Creek 024 25.0
END DESCRIPTION:
XS GIS Cut Line= 3
      3845294.15     10139665.97      3844268.28     10138854.04
      3843373.59     10138525.82
#Sta/Elev= 30
  3691.7  282.15  3785.4  281.11  3899.2  277.86    4154  275.47    4193   275.3
  4290.4  274.35  4525.9  269.04  4581.9  267.64  4596.4  266.12  4727.4  262.77
  4794.1  260.02    4924  254.47  4966.6  254.93    4981  251.46  4996.6  250.27
  5011.1  252.34  5019.8  254.92  5130.4  256.87  5213.5  255.64  5262.4  256.35
  5343.7  256.31  5461.2  259.16  5486.4  261.16  5577.9  264.13  5608.4  266.47
  5618.3  268.79    5664  269.16  5689.2  270.76  5694.5  272.06    5953  278.71
#Mann= 12 ,-1 , 0
  3691.7     .11       0    4154     .17       0    4193     .11       0
  4290.4     .17       0  4525.9     .11       0  4727.4     .17       0
  4794.1     .15       0  4966.6     .09       0  5019.8     .15       0
  5130.4     .11       0  5262.4     .17       0  5343.7     .11       0
#XS Ineff= 2 , 0
       0                  5400.2       0  258.27
Permanent Ineff=
       F       F
Bank Sta=4966.6,5019.8
XS Rating Curve= 0 ,0
Exp/Cntr=0.3,0.1

Type RM Length L Ch R = 1 ,12501   ,501,501,501
BEGIN DESCRIPTION:
Crystal Creek 024 24.0
END DESCRIPTION:
XS GIS Cut Line= 3
      3845356.59     10139504.47      3844110.85     10138521.65
      3843417.43     10138385.05
#Sta/Elev= 30
  3421.1  281.72  4009.5  271.72    4070  270.72  4148.5   269.7  4241.5   266.3
  4270.4  266.81  4284.8  265.37  4332.8  265.32  4626.3  256.68  4698.9  256.51
  4775.4  255.69  4804.2  253.18    4897   254.5  4953.3  252.62  4960.7  253.62
  4982.2  252.82  4988.6  249.63  4996.6  251.39  5001.3  248.98  5004.8  248.98
  5006.6  250.93  5031.3  250.58  5036.6  253.66  5041.7  255.27  5110.2   256.1
  5235.1  258.76  5401.1  266.03  5520.5  272.92  5571.5  277.52  5714.6  278.42
#Mann= 8 ,-1 , 0
  3421.1     .11       0  4009.5     .17       0    4070     .11       0
  4332.8     .17       0  4698.9     .15       0  4960.7     .09       0
  5036.6     .15       0  5110.2     .11       0
#XS Ineff= 3 ,-1
  4632.7  4618.2   256.9  4696.8  4632.7  256.67  5102.6    5123  256.35
Permanent Ineff=
       F       F       F
Bank Sta=4960.7,5036.6
XS Rating Curve= 0 ,0
Exp/Cntr=0.3,0.1

Type RM Length L Ch R = 1 ,12000   ,500,500,500
BEGIN DESCRIPTION:
Crystal Creek 024 23.0
END DESCRIPTION:
XS GIS Cut Line= 3
      3845429.51     10139405.51       3844477.2     10138372.76
      3843643.12     10138087.84
#Sta/Elev= 30
  3595.2  281.54    3911  276.57  4130.5  270.93  4165.7  271.14  4250.7  267.65
  4406.1  264.97  4420.3  263.07  4462.8  263.23  4508.4  261.57  4687.6  258.77
  4908.5  256.35  4965.2  253.49  4984.5251.0708  4991.8  247.66  5009.9  251.03
  5012.7  251.11  5059.7  252.13  5168.4  253.58  5221.2  256.35  5294.5   257.8
  5331.1  261.58  5337.5  264.12  5388.5  260.17  5506.5  263.04  5527.3  266.68
  5550.3  265.76  5696.4  270.37    5759  269.94  5790.3  271.46  5881.4  272.08
#Mann= 9 ,-1 , 0
  3595.2     .11       0  4508.4     .17       0  4687.6     .15       0
  4908.5     .17       0  4984.5     .09       0  5009.9     .17       0
  5012.7     .15       0  5059.7     .17       0  5527.3     .11       0
Bank Sta=4984.5,5009.9
XS Rating Curve= 0 ,0
Exp/Cntr=0.3,0.1

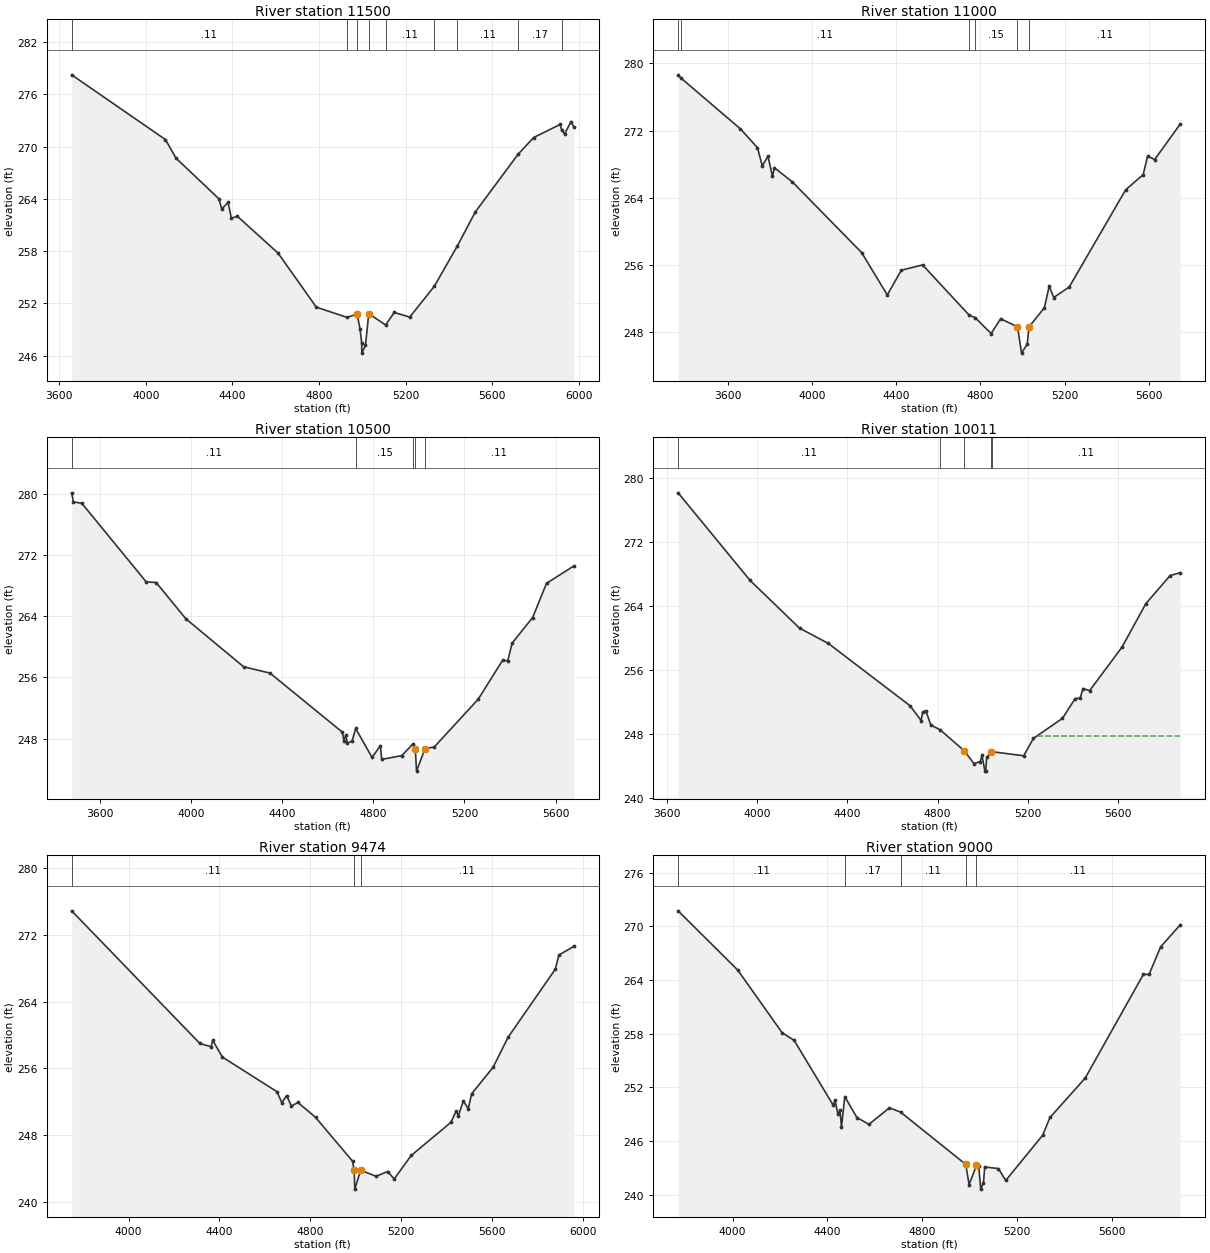
Type RM Length L Ch R = 1 ,11500   ,500,500,500
BEGIN DESCRIPTION:
Crystal Creek 024 22.0
END DESCRIPTION:
XS GIS Cut Line= 3
      3845507.64     10139207.59      3844792.29     10138072.02
      3843835.81     10137874.29
#Sta/Elev= 30
  3657.9  278.25  4091.1  270.81  4140.1  268.67  4337.8  264.01  4351.1  262.83
  4380.2   263.6  4395.5  261.77  4422.6  262.01  4611.1  257.77  4787.5  251.56
    4929  250.39  4975.9  250.75  4989.3  249.08  4997.1  247.45  4997.7  246.28
  5014.7  247.19  5029.7  250.82  5107.6  249.51  5147.5  250.95    5219  250.42
  5332.5  253.96  5438.3  258.57  5521.8   262.5  5719.8  269.14  5790.8  271.04
  5913.4  272.55  5919.8  271.94  5933.8  271.45  5963.6  272.88  5976.7  272.28
#Mann= 9 ,-1 , 0
  3657.9     .11       0    4929     .15       0  4975.9     .09       0
  5029.7     .15       0  5107.6     .11       0  5332.5     .17       0
  5438.3     .11       0  5719.8     .17       0  5919.8     .11       0
Bank Sta=4975.9,5029.7
XS Rating Curve= 0 ,0
Exp/Cntr=0.3,0.1

Type RM Length L Ch R = 1 ,11000   ,500,500,500
BEGIN DESCRIPTION:
Crystal Creek 024 21.0
END DESCRIPTION:
XS GIS Cut Line= 3
      3846257.69     10138520.13      3844869.23     10137655.07
      3844148.27      10137452.4
#Sta/Elev= 30
  3364.1  278.65  3376.5  278.29  3659.9  272.22  3740.9  269.98  3763.8  267.82
  3790.9  268.96  3812.1  266.56  3821.6  267.59  3906.5  265.91  4235.8  257.49
  4357.3  252.46  4424.3   255.4  4524.9  256.03  4747.8  250.01    4774  249.77
  4850.6  247.86  4895.6  249.62  4975.7  248.66  4995.2  245.53  5022.2  246.62
  5030.3  248.65  5103.6  250.94  5126.1  253.49  5148.1  252.15  5221.4   253.4
  5489.6  264.97  5572.7  266.78  5593.5  268.97  5627.2  268.57  5748.9   272.8
#Mann= 6 ,-1 , 0
  3364.1     .17       0  3376.5     .11       0  4747.8     .17       0
    4774     .15       0  4975.7     .09       0  5030.3     .11       0
Bank Sta=4975.7,5030.3
XS Rating Curve= 0 ,0
Exp/Cntr=0.3,0.1

Type RM Length L Ch R = 1 ,10500   ,489,489,489
BEGIN DESCRIPTION:
Crystal Creek 024 20.0
END DESCRIPTION:
XS GIS Cut Line= 3
       3846382.7     10138098.26      3845100.82     10137274.76
      3844465.98     10137030.53
#Sta/Elev= 30
  3476.4  280.09  3484.3  278.89  3520.6  278.74  3803.1  268.48  3847.6  268.37
  3977.7  263.64    4231  257.38  4346.9  256.55  4664.7  248.83  4670.7  247.73
  4679.9  248.46  4685.8  247.42  4706.9  247.67  4722.7  249.32  4794.8  245.53
  4831.1  247.07  4837.1  245.29  4924.9  245.77    4975  247.33  4984.4246.6767
  4989.9  243.75  5027.1   246.7  5067.5   246.9  5260.3  253.13  5367.5  258.22
  5390.3  258.17  5409.5  260.47  5499.5  263.81  5560.3  268.27  5680.2  270.54
#Mann= 5 ,-1 , 0
  3476.4     .11       0  4722.7     .15       0    4975     .11       0
  4984.4     .09       0  5027.1     .11       0
#XS Ineff= 2 , 0
       0  4722.7  249.32               0
Permanent Ineff=
       F       F
Bank Sta=4984.4,5027.1
XS Rating Curve= 0 ,0
Exp/Cntr=0.3,0.1

Type RM Length L Ch R = 1 ,10011   ,537,537,537
BEGIN DESCRIPTION:
Crystal Creek 024 19.0
END DESCRIPTION:
XS GIS Cut Line= 3
      3846450.22     10137908.25      3845438.08     10137015.96
      3844747.26     10136478.46
#Sta/Elev= 30
  3650.7  278.14  3969.3  267.19  4188.5  261.22  4316.6   259.3    4678  251.52
  4727.3  249.67    4734  250.73  4748.2  250.89    4770  249.11  4810.7  248.52
  4918.9  245.87  4960.7  244.29  4989.2  244.54  4996.7  245.34  5009.6  243.34
  5013.1  243.34  5017.7  245.05  5038.5  245.78    5041  245.77  5181.5  245.26
  5224.9  247.44  5353.4  249.94  5409.5  252.42  5431.1  252.45  5444.8  253.66
  5473.8  253.41  5616.7  258.83  5722.6  264.28  5830.3   267.8  5875.3  268.15
#Mann= 5 ,-1 , 0
  3650.7     .11       0  4810.7     .15       0  4918.9     .09       0
  5038.5     .15       0    5041     .11       0
#XS Ineff= 2 , 0
       0                  5239.4       0  247.75
Permanent Ineff=
       F       F
Bank Sta=4918.9,5038.5
XS Rating Curve= 0 ,0
Exp/Cntr=0.3,0.1

Type RM Length L Ch R = 1 ,9474    ,474,474,474
BEGIN DESCRIPTION:
Crystal Creek 024 18.0
END DESCRIPTION:
XS GIS Cut Line= 3
      3846613.37     10137602.73      3845696.55     10136752.17
      3844852.13     10136296.54
#Sta/Elev= 30
  3749.4  274.88  4313.6  258.99    4363   258.6  4370.3  259.37  4412.3  257.37
  4653.2  253.21  4674.2   251.9  4695.8  252.74  4716.7  251.49  4745.1  251.92
  4822.8  250.14  4985.5  244.89  4992.8  243.79  4995.4  241.54  5021.2   243.8
  5089.4  243.08  5139.9  243.65    5169  242.76  5243.7  245.57  5418.9  249.55
  5441.7   250.9  5451.2  250.32  5473.1   252.1    5495  251.18  5509.8  252.96
  5604.5  256.15  5670.1  259.73  5877.7  267.88  5893.9  269.59  5959.5  270.62
#Mann= 3 , 0 , 0
  3749.4     .11       0  4992.8     .09       0  5021.2     .11       0
Bank Sta=4992.8,5021.2
XS Rating Curve= 0 ,0
Exp/Cntr=0.3,0.1

Type RM Length L Ch R = 1 ,9000    ,604,604,604
BEGIN DESCRIPTION:
Crystal Creek 024 17.0
END DESCRIPTION:
XS GIS Cut Line= 3
      3846778.47      10137150.3      3845773.68     10136442.25
      3844917.86     10136211.07
#Sta/Elev= 30
  3770.8  271.73  4021.8  265.12    4209  258.12  4259.5  257.27  4423.3  250.06
  4431.9  250.55  4444.4     249  4452.9  249.47    4459  247.58    4473  250.97
  4524.3  248.64  4574.8  247.89    4661  249.73  4708.1  249.25  4982.7  243.41
  4996.7  241.16  5027.8   243.3  5037.1  243.26  5045.7  240.65  5057.3  241.37
  5062.5  243.12    5120  242.95  5151.1  241.62  5306.4  246.66  5337.5  248.65
  5485.8  253.05  5731.1  264.64  5754.7  264.62  5803.6   267.7  5886.5  270.18
#Mann= 5 ,-1 , 0
  3770.8     .11       0    4473     .17       0  4708.1     .11       0
  4982.7     .09       0  5027.8     .11       0
Bank Sta=4982.7,5027.8
XS Rating Curve= 0 ,0
Exp/Cntr=0.3,0.1

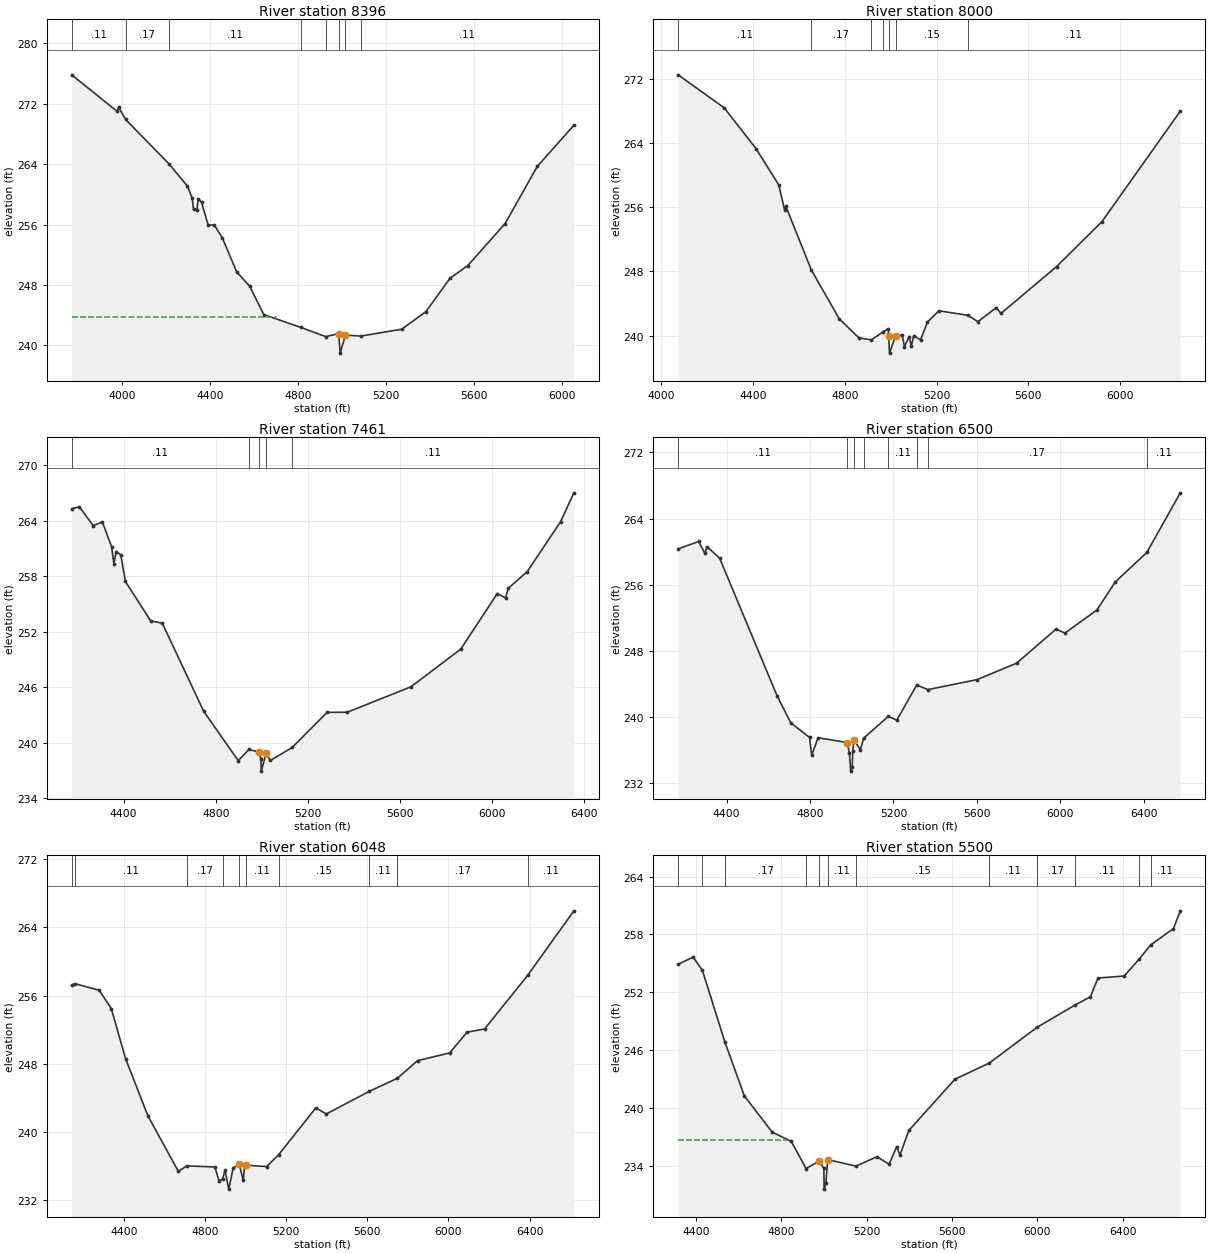
Type RM Length L Ch R = 1 ,8396    ,396,396,396
BEGIN DESCRIPTION:
Crystal Creek 024 16.0
END DESCRIPTION:
XS GIS Cut Line= 3
      3847004.01     10136889.21      3845868.69     10136178.25
      3844925.85     10136139.21
#Sta/Elev= 30
  3769.4  275.84    3977  270.98  3982.9  271.55  4014.8  269.92  4211.8  264.04
  4295.8  261.09  4317.6  259.47  4323.5  257.99  4338.8  257.96  4344.7  259.41
  4360.1  258.94  4390.2  255.91  4417.8  255.94  4454.4  254.23    4520  249.71
    4579  247.81    4643  244.05  4810.8  242.37  4924.6  241.14  4983.6  241.54
  4990.2  238.95  5014.3  241.34  5083.9  241.21  5269.9  242.12    5380  244.45
  5490.1  248.89  5570.2  250.55  5740.3  256.13  5886.1  263.69  6052.6  269.15
#Mann= 8 ,-1 , 0
  3769.4     .11       0  4014.8     .17       0  4211.8     .11       0
  4810.8     .17       0  4924.6     .15       0  4983.6     .09       0
  5014.3     .15       0  5083.9     .11       0
#XS Ineff= 2 , 0
       0  4700.7  243.75               0
Permanent Ineff=
       F       F
Bank Sta=4983.6,5014.3
XS Rating Curve= 0 ,0
Exp/Cntr=0.3,0.1

Type RM Length L Ch R = 1 ,8000    ,539,539,539
BEGIN DESCRIPTION:
Crystal Creek 024 15.0
END DESCRIPTION:
XS GIS Cut Line= 3
      3847066.52     10136357.96      3846198.14     10136035.56
      3844936.35      10136071.5
#Sta/Elev= 30
  4073.7  272.52  4274.9   268.4  4413.6   263.3  4512.5  258.78  4537.6  255.68
  4542.9  256.15  4653.6  248.22  4776.3  242.07  4861.6  239.72    4916  239.46
  4964.9  240.43  4989.6  240.86 4991.41 239.955    4995  237.81  5021.6  239.99
  5050.3  240.03  5060.3  238.63  5080.3  239.88  5090.3  238.71  5100.3  239.98
  5130.3  239.46  5160.4  241.69  5210.4  243.09  5335.5  242.53  5380.4  241.73
  5460.5  243.49  5480.5  242.76  5722.9   248.6  5920.7  254.21  6262.3  267.99
#Mann= 7 ,-1 , 0
  4073.7     .11       0  4653.6     .17       0    4916     .11       0
  4964.9     .15       0 4991.41     .09       0  5021.6     .15       0
  5335.5     .11       0
#XS Ineff= 2 ,-1
  5210.4  5460.5  243.09  5460.5  5560.5  243.49
Permanent Ineff=
       F       F
Bank Sta=4991.41,5021.6
XS Rating Curve= 0 ,0
Exp/Cntr=0.3,0.1

Type RM Length L Ch R = 1 ,7461    ,961,961,961
BEGIN DESCRIPTION:
Crystal Creek 024 14.0
END DESCRIPTION:
XS GIS Cut Line= 3
      3847061.28     10135644.42      3846235.76     10135656.06
      3844921.81     10135987.89
#Sta/Elev= 30
  4174.4   265.3  4207.8  265.53  4267.8  263.48  4307.8  263.87  4347.8   261.2
  4357.8  259.37  4367.8  260.68  4387.8  260.31  4407.8  257.44  4517.9  253.17
  4567.9  252.93  4747.9  243.39  4897.9  238.05  4943.8  239.26  4987.9  238.99
  4996.5  238.22  4998.1  236.92  5018.5  238.84  5037.4  238.07  5131.8  239.48
  5283.7  243.28    5371  243.29  5647.6  246.04  5864.2  250.12  6022.6  256.13
  6058.5  255.66  6070.5   256.7    6153  258.51  6297.4   263.9  6355.2  267.03
#Mann= 5 ,-1 , 0
  4174.4     .11       0  4943.8     .15       0  4987.9     .09       0
  5018.5     .15       0  5131.8     .11       0
Bank Sta=4987.9,5018.5
XS Rating Curve= 0 ,0
Exp/Cntr=0.3,0.1

Type RM Length L Ch R = 1 ,6500    ,452,452,452
BEGIN DESCRIPTION:
Crystal Creek 024 13.0
END DESCRIPTION:
XS GIS Cut Line= 3
      3847045.69     10135149.63      3846216.99     10135073.35
      3844873.76     10135896.52
#Sta/Elev= 30
  4167.8  260.32    4266  261.22  4296.2  259.79  4306.2  260.59  4366.5  259.22
  4642.8  242.51  4707.9  239.27  4798.3   237.5  4808.3  235.35  4838.5  237.47
  4979.1  236.89  4989.1  235.58  4995.2  233.43  5002.4  233.93    5005  235.88
  5010.9  237.19  5041.8  236.02  5057.1  237.41  5175.6  240.06  5215.8  239.59
  5311.9  243.85  5365.2   243.3  5600.7   244.5  5790.3  246.49  5979.8  250.62
  6022.4  250.14  6175.2  252.92  6264.1  256.34  6415.1   259.9  6575.4  267.11
#Mann= 8 ,-1 , 0
  4167.8     .11       0  4979.1     .09       0  5010.9     .11       0
  5057.1     .15       0  5175.6     .11       0  5311.9     .15       0
  5365.2     .17       0  6415.1     .11       0
#XS Ineff= 2 , 0
       0                  5142.4       0   238.9
Permanent Ineff=
       F       F
Bank Sta=4979.1,5010.9
XS Rating Curve= 0 ,0
Exp/Cntr=0.3,0.1

Type RM Length L Ch R = 1 ,6048    ,548,548,548
BEGIN DESCRIPTION:
Crystal Creek 024 12.0
END DESCRIPTION:
XS GIS Cut Line= 3
      3846983.17     10134857.96       3846126.7     10134815.93
      3844807.87     10135753.77
#Sta/Elev= 30
  4142.5  257.22  4158.7   257.4    4278  256.63  4338.1  254.48  4408.1  248.63
  4518.3  241.92  4668.5  235.41  4709.9  236.05  4848.7  235.93  4868.7  234.31
  4886.7  234.52  4898.7  235.58  4916.9  233.33  4938.8  235.81  4968.8  236.22
  4988.8  234.35  4995.4  236.14  5002.5  236.14  5103.3  235.97  5162.8  237.36
  5346.8  242.86  5397.3  242.13  5609.4  244.78    5748  246.31  5848.6  248.39
    6006  249.28  6092.1  251.72  6178.2  252.09    6392  258.41  6618.3  265.93
#Mann= 10 ,-1 , 0
  4142.5     .17       0  4158.7     .11       0  4709.9     .17       0
  4886.7     .11       0  4968.8     .09       0  5002.5     .11       0
  5162.8     .15       0  5609.4     .11       0    5748     .17       0
    6392     .11       0
Bank Sta=4968.8,5002.5
XS Rating Curve= 0 ,0
Exp/Cntr=0.3,0.1

Type RM Length L Ch R = 1 ,5500    ,500,500,500
BEGIN DESCRIPTION:
Crystal Creek 024 11.0
END DESCRIPTION:
XS GIS Cut Line= 3
      3846878.15      10134590.6      3846195.45     10134564.37
      3844812.54     10135501.81
#Sta/Elev= 30
  4316.8  254.91  4387.1  255.65  4430.6  254.28  4536.6  246.81  4627.3  241.26
  4757.4  237.51  4847.5  236.53  4916.7  233.72  4977.6   234.5    5000  233.74
  5001.2  231.59  5009.2  232.19    5018  234.65  5150.6  233.98  5248.6  234.95
  5305.6  234.18  5341.5  235.99  5356.5  235.12  5398.5  237.68  5614.1  242.98
  5775.9  244.67  5999.8  248.38  6178.7   250.7    6249  251.53    6285  253.48
  6407.7  253.69  6476.6  255.41  6531.2   256.9  6638.4  258.61  6670.7  260.45
#Mann= 12 ,-1 , 0
  4316.8     .17       0  4430.6     .11       0  4536.6     .17       0
  4916.7     .11       0  4977.6     .09       0    5018     .11       0
  5150.6     .15       0  5775.9     .11       0  5999.8     .17       0
  6178.7     .11       0  6476.6     .17       0  6531.2     .11       0
#XS Ineff= 2 , 0
       0  4837.5  236.72               0
Permanent Ineff=
       F       F
Bank Sta=4977.6,5018
XS Rating Curve= 0 ,0
Exp/Cntr=0.3,0.1

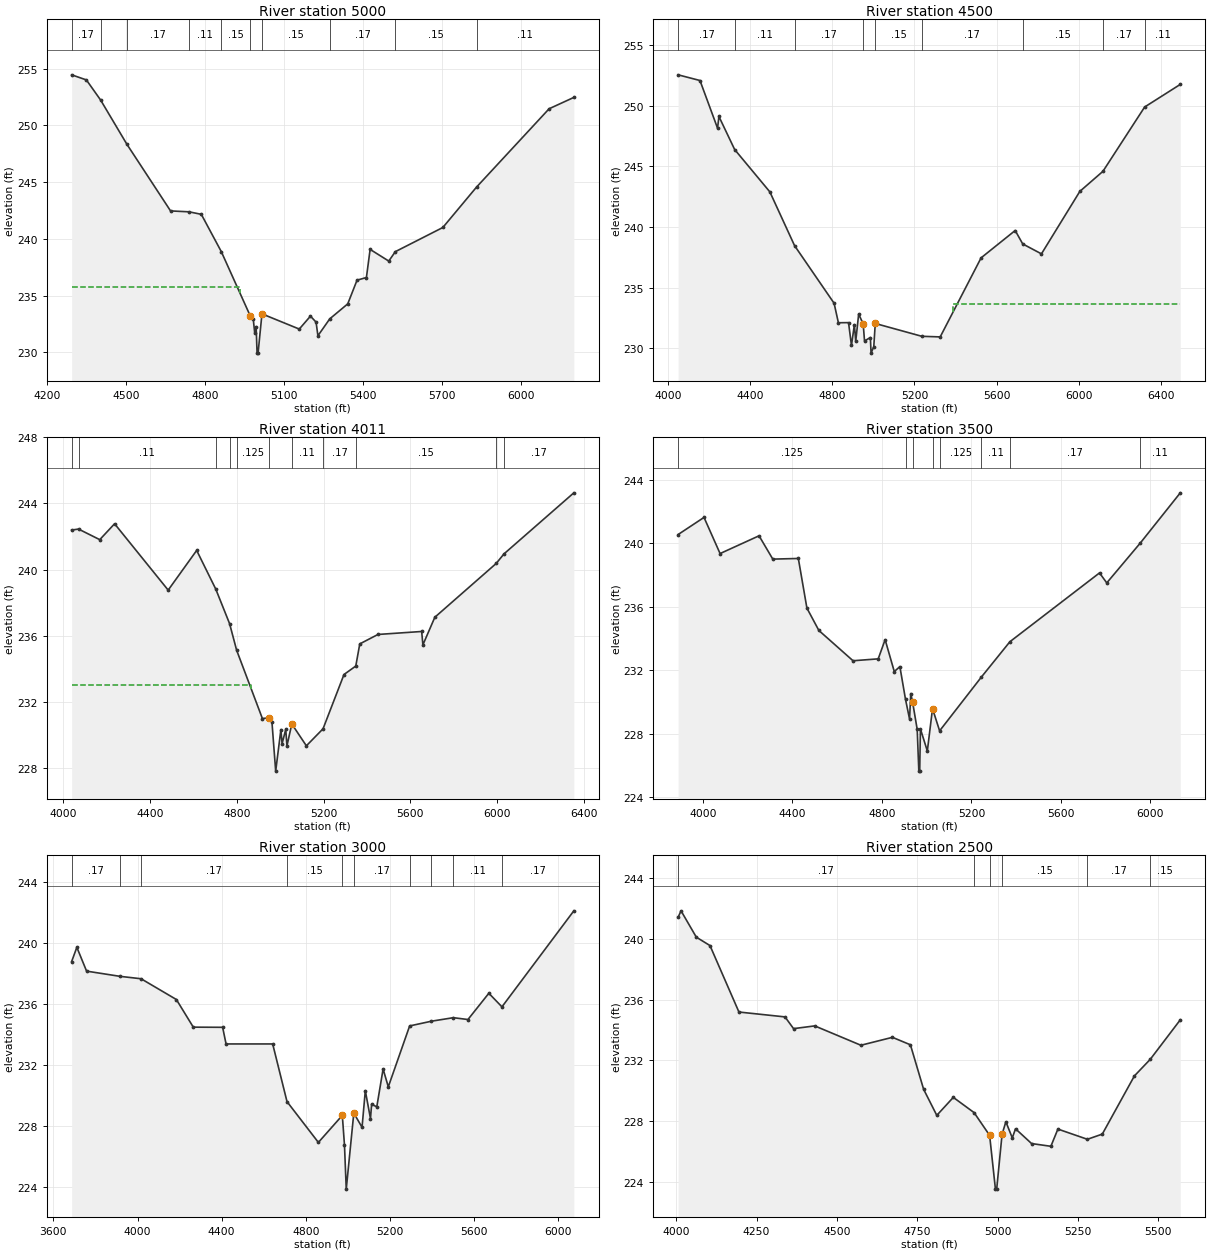
Type RM Length L Ch R = 1 ,5000    ,500,500,500
BEGIN DESCRIPTION:
Crystal Creek 024 10.0
END DESCRIPTION:
XS GIS Cut Line= 3
      3846734.48     10134415.68      3846072.49     10134172.32
      3845234.49     10135030.27
#Sta/Elev= 30
  4294.7  254.46  4350.6  254.01  4404.5  252.24    4504  248.35  4669.8  242.47
  4739.9  242.39  4786.4  242.17  4862.1  238.89    4973  233.17  4983.6  232.91
    4989  231.72  4994.4  232.28  4997.9  229.94  5001.7  229.94  5016.5   233.4
    5158  232.06  5200.4   233.2  5221.7  232.67  5228.7  231.47  5273.6  232.96
  5341.8  234.28  5377.1  236.37  5412.6   236.6  5426.7  239.08  5497.4  238.05
  5522.3  238.88  5702.5  241.01  5830.3  244.57  6105.5  251.47  6199.3  252.47
#Mann= 10 ,-1 , 0
  4294.7     .17       0  4404.5     .11       0    4504     .17       0
  4739.9     .11       0  4862.1     .15       0    4973     .09       0
  5016.5     .15       0  5273.6     .17       0  5522.3     .15       0
  5830.3     .11       0
#XS Ineff= 2 , 0
       0  4933.4  235.74               0
Permanent Ineff=
       F       F
Bank Sta=4973,5016.5
XS Rating Curve= 0 ,0
Exp/Cntr=0.3,0.1

Type RM Length L Ch R = 1 ,4500    ,489,489,489
BEGIN DESCRIPTION:
Crystal Creek 024 9.0
END DESCRIPTION:
XS GIS Cut Line= 3
      3846776.17      10134353.2      3846056.31     10133739.42
      3845187.64     10134962.53
#Sta/Elev= 30
  4049.1  252.57  4155.6   252.1  4241.2  248.16  4247.8  249.13  4324.5   246.4
    4496   242.9  4616.3  238.46  4808.9   233.7  4829.8  232.09  4879.2   232.1
  4893.5  230.22  4907.7  231.93  4914.3  230.57  4928.6  232.81  4950.6  231.99
  4957.1  230.59  4985.7  230.87  4988.9  229.58  5002.2  230.11  5009.4  232.03
  5236.2  230.97  5325.7  230.92  5524.9  237.45    5691  239.71  5727.7   238.6
  5818.9  237.78  6005.9  242.94  6118.5   244.6  6321.6  249.91  6495.3  251.78
#Mann= 9 ,-1 , 0
  4049.1     .17       0  4324.5     .11       0  4616.3     .17       0
  4950.6     .09       0  5009.4     .15       0  5236.2     .17       0
  5727.7     .15       0  6118.5     .17       0  6321.6     .11       0
#XS Ineff= 2 , 0
       0  4808.9   233.7  5389.6       0  233.62
Permanent Ineff=
       F       F
Bank Sta=4950.6,5009.4
XS Rating Curve= 0 ,0
Exp/Cntr=0.3,0.1

Type RM Length L Ch R = 1 ,4011    ,511,511,511
BEGIN DESCRIPTION:
Crystal Creek 024 8.0
END DESCRIPTION:
XS GIS Cut Line= 3
      3846660.73     10133728.96      3845758.57     10133425.71
      3845150.02     10134644.01
#Sta/Elev= 30
  4039.4  242.39  4071.1  242.45  4168.9  241.81  4237.2  242.77  4484.1  238.76
  4615.4  241.16  4703.4  238.82  4767.1  236.73  4799.4  235.13  4918.1     231
  4949.7  231.04  4962.1   230.8  4979.4  227.82  5003.4  230.33  5008.9  229.48
  5025.7  230.34  5031.3  229.35  5053.7  230.67  5120.8  229.35  5197.6  230.38
  5294.1  233.66  5348.4  234.17  5366.8  235.51  5450.7  236.08    5652  236.26
  5657.6  235.45  5712.6  237.12  5995.2  240.37  6031.2  240.95    6353  244.64
#Mann= 11 ,-1 , 0
  4039.4     .17       0  4071.1     .11       0  4703.4     .17       0
  4767.1     .11       0  4799.4    .125       0  4949.7     .09       0
  5053.7     .11       0  5197.6     .17       0  5348.4     .15       0
  5995.2     .11       0  6031.2     .17       0
#XS Ineff= 2 , 0
       0  4867.5  233.05               0
Permanent Ineff=
       F       F
Bank Sta=4949.7,5053.7
XS Rating Curve= 0 ,0
Exp/Cntr=0.3,0.1

Type RM Length L Ch R = 1 ,3500    ,500,500,500
BEGIN DESCRIPTION:
Crystal Creek 024 7.0
END DESCRIPTION:
XS GIS Cut Line= 3
      3846540.88      10133452.9      3845471.24     10133213.03
      3845032.39     10134274.92
#Sta/Elev= 30
  3888.7  240.55  4004.5  241.63  4076.3  239.35  4250.5  240.47    4312     239
  4426.2  239.04  4464.5  235.91    4518   234.5  4670.7  232.59  4783.3  232.71
  4814.2  233.92  4855.1  231.91  4880.2  232.22  4905.4  230.15  4923.5  228.91
  4928.7  230.52  4937.1  229.98  4957.6  228.26  4964.9  225.63  4968.8  225.63
    4972  228.29  5002.9   226.9  5026.1  229.57  5057.8  228.17    5245  231.57
    5372  233.79  5772.7  238.13  5805.1   237.5  5954.8  240.01  6133.9  243.18
#Mann= 8 ,-1 , 0
  3888.7    .125       0  4905.4     .11       0  4937.1     .09       0
  5026.1     .11       0  5057.8    .125       0    5245     .11       0
    5372     .17       0  5954.8     .11       0
#XS Ineff= 2 , 0
       0  4880.2  232.22               0
Permanent Ineff=
       F       F
Bank Sta=4937.1,5026.1
XS Rating Curve= 0 ,0
Exp/Cntr=0.3,0.1

Type RM Length L Ch R = 1 ,3000    ,500,500,500
BEGIN DESCRIPTION:
Crystal Creek 024 6.0
END DESCRIPTION:
XS GIS Cut Line= 3
      3846561.74     10133234.16      3845292.39     10132898.05
      3844906.97     10133900.94
#Sta/Elev= 30
  3686.9  238.76  3711.6  239.69  3757.9  238.13    3916  237.79    4017  237.63
  4184.8  236.27  4265.2  234.46  4404.7  234.45    4421  233.36  4642.6  233.36
  4710.8  229.58  4859.9  226.91  4973.7  228.68    4984  226.73  4992.4  223.85
  5028.3  228.83  5067.5   227.9    5083   230.3  5107.6  228.47    5113  229.41
  5137.6  229.24  5167.6  231.72  5192.3  230.55  5293.8  234.54  5397.6  234.85
  5501.4  235.08    5571  234.96  5670.3  236.68  5732.6  235.79  6074.4  242.08
#Mann= 10 ,-1 , 0
  3686.9     .17       0    3916    .125       0    4017     .17       0
  4710.8     .15       0  4973.7     .09       0  5028.3     .17       0
  5293.8     .11       0  5397.6    .125       0  5501.4     .11       0
  5732.6     .17       0
#XS Ineff= 2 , 0
       0                  5167.6       0  231.72
Permanent Ineff=
       F       F
Bank Sta=4973.7,5028.3
XS Rating Curve= 0 ,0
Exp/Cntr=0.3,0.1

Type RM Length L Ch R = 1 ,2500    ,500,500,500
BEGIN DESCRIPTION:
Crystal Creek 024 5.0
END DESCRIPTION:
XS GIS Cut Line= 3
      3846521.83      10132888.1      3845553.76     10132661.65
      3844985.12     10132675.27
#Sta/Elev= 30
  4005.8   241.4  4014.9  241.82  4062.5  240.09    4105  239.54  4195.1  235.18
  4338.5  234.86  4365.1  234.09    4431  234.27  4574.7     233  4672.8  233.52
  4728.8  233.03  4769.9  230.11  4810.9   228.4  4862.3  229.58    4927  228.58
  4975.3  227.09  4993.4  223.56  4997.3  223.56  5014.1227.1634  5025.9  227.98
  5045.9  226.92  5055.9  227.52  5105.9  226.55    5166  226.37  5187.8   227.5
  5279.6  226.83    5326  227.17    5426  230.99  5475.4  232.08  5568.8  234.67
#Mann= 6 ,-1 , 0
  4005.8     .17       0    4927     .15       0  4975.3     .09       0
  5014.1     .15       0  5279.6     .17       0  5475.4     .15       0
#XS Ineff= 2 , 0
       0  4862.3  229.58               0
Permanent Ineff=
       F       F
Bank Sta=4975.3,5014.1
XS Rating Curve= 0 ,0
Exp/Cntr=0.3,0.1