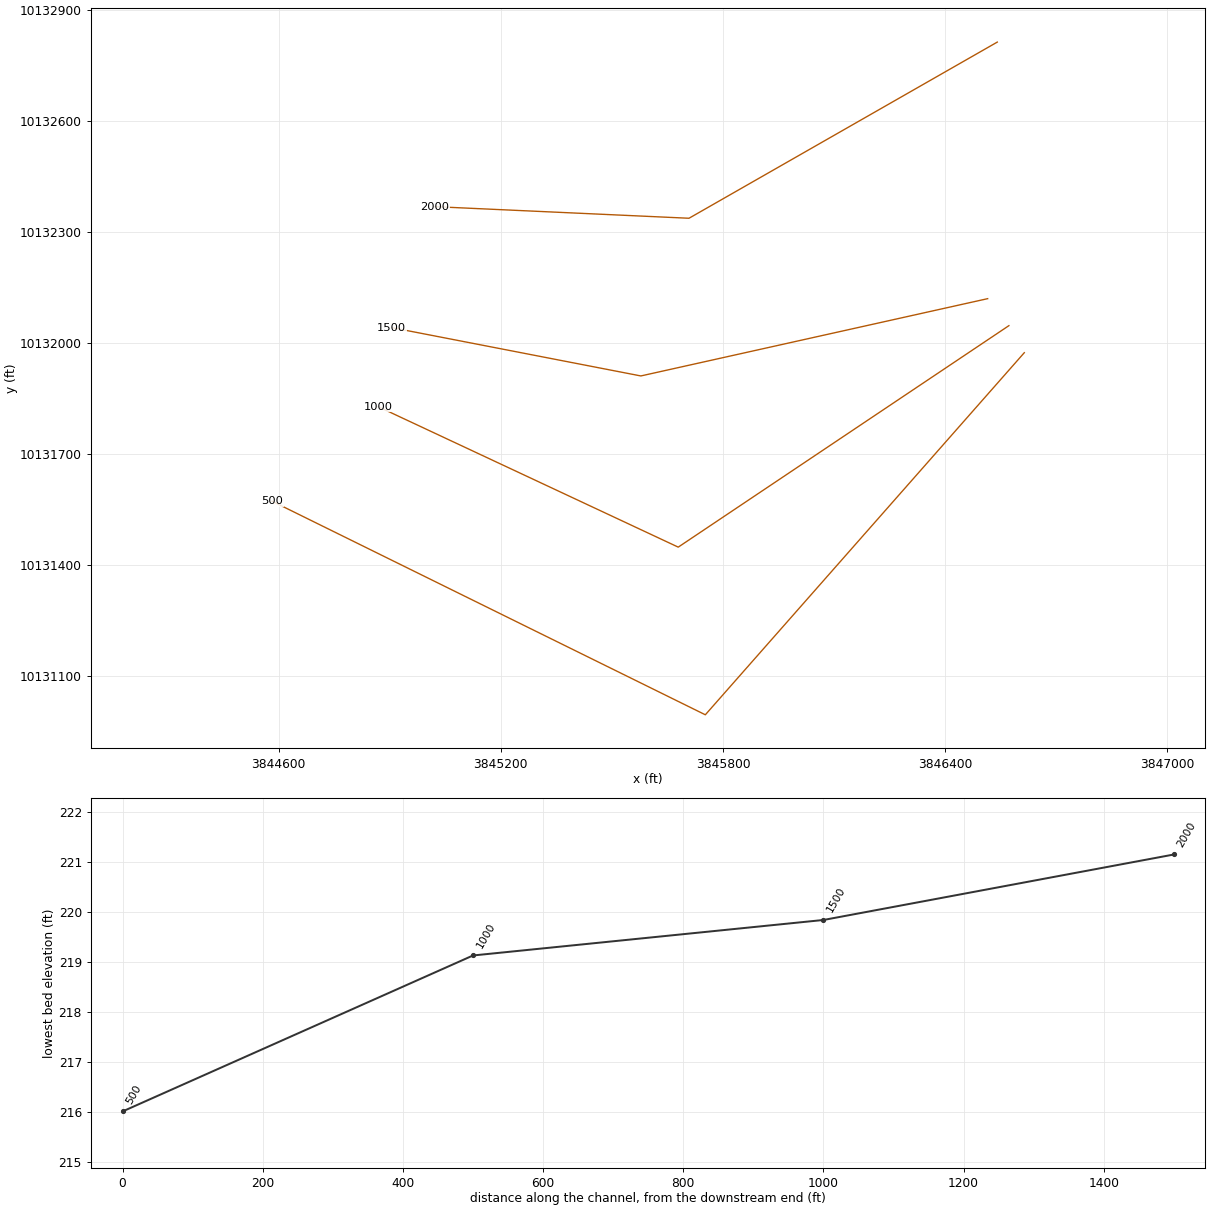
HEC-RAS study Crystal Creek 024.prj: Crystal Creek 024 Base Level Engineering

--- Crystal Creek 024.g01 (geometry) --- (continued)

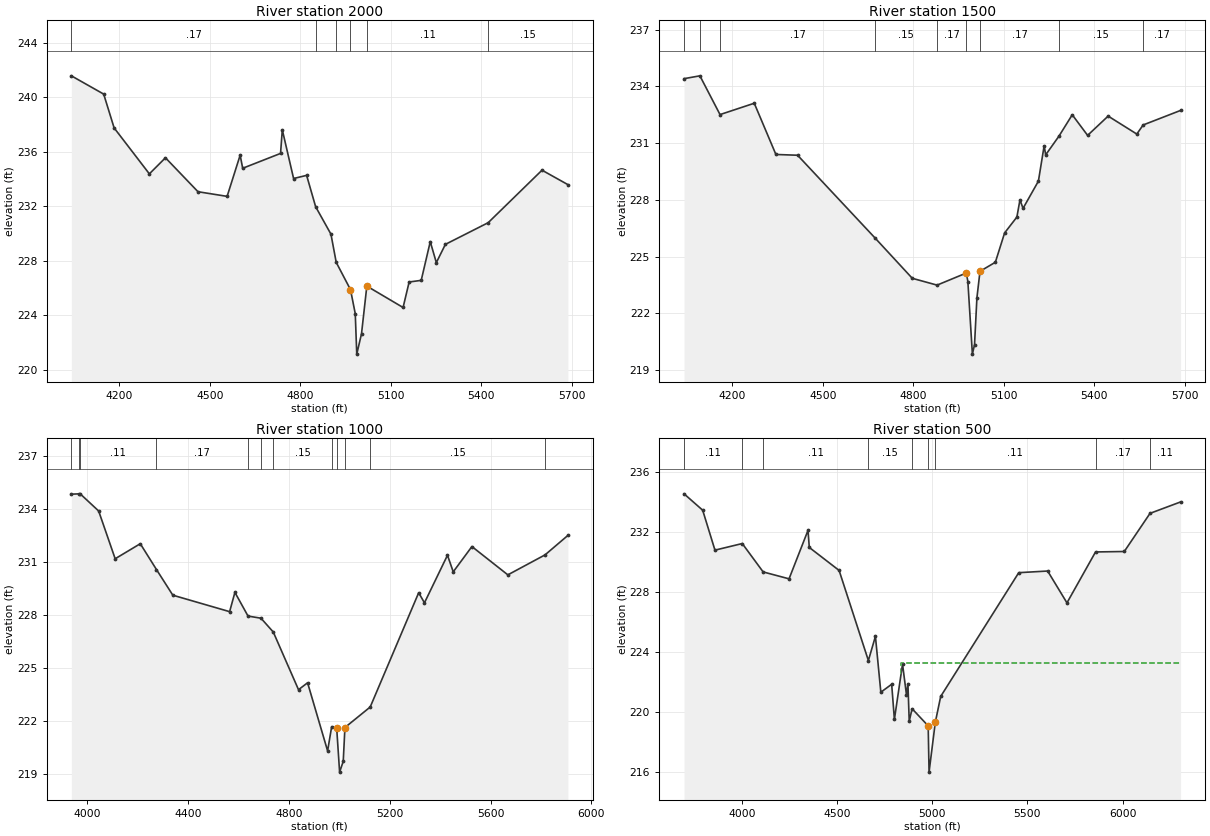
Type RM Length L Ch R = 1 ,2000    ,500,500,500
BEGIN DESCRIPTION:
Crystal Creek 024 4.0
END DESCRIPTION:
XS GIS Cut Line= 3
      3846540.87     10132812.26      3845708.35     10132336.64
      3845022.17     10132367.95
#Sta/Elev= 30
  4041.2  241.56  4148.3  240.22  4182.9  237.74  4299.7  234.37    4353  235.55
  4460.9  233.06  4557.4  232.72  4600.6  235.74    4609  234.78  4734.5  235.87
  4740.3   237.6  4777.7  234.03  4820.9  234.26  4850.8  231.96  4901.5  229.95
    4919  227.88  4966.3  225.88  4982.1  224.12  4987.1  221.15  5002.8  222.64
  5020.5  226.14  5140.6  224.57  5160.7  226.44  5200.7  226.56  5230.7   229.4
  5250.8  227.86  5280.8   229.2  5422.7  230.79  5601.1  234.64  5686.9  233.58
#Mann= 6 ,-1 , 0
  4041.2     .17       0  4850.8     .15       0    4919     .11       0
  4966.3     .09       0  5020.5     .11       0  5422.7     .15       0
#XS Ineff= 2 , 0
       0                  5230.7       0   229.4
Permanent Ineff=
       F       F
Bank Sta=4966.3,5020.5
XS Rating Curve= 0 ,0
Exp/Cntr=0.3,0.1

Type RM Length L Ch R = 1 ,1500    ,500,500,500
BEGIN DESCRIPTION:
Crystal Creek 024 3.0
END DESCRIPTION:
XS GIS Cut Line= 3
      3846514.91     10132119.59      3845578.37     10131910.92
      3844905.51     10132041.45
#Sta/Elev= 30
  4040.5  234.41    4093  234.56  4159.7  232.51  4273.1  233.11  4344.8   230.4
  4416.6  230.36  4673.4  225.98  4796.6  223.85  4878.7  223.49  4975.6  224.13
  4980.7  223.68  4995.7  219.84  5002.8  220.34  5010.7  222.82  5020.9  224.22
  5071.8   224.7  5102.4  226.25  5143.1  227.09  5153.3     228  5163.5  227.55
  5214.4  228.99  5233.4  230.86  5238.5  230.38  5282.5  231.37  5326.5   232.5
  5377.4  231.41  5445.4  232.43  5540.4  231.48  5561.3  231.96  5685.4  232.73
#Mann= 9 ,-1 , 0
  4040.5     .17       0    4093     .11       0  4159.7     .17       0
  4673.4     .15       0  4878.7     .17       0  4975.6     .09       0
  5020.9     .17       0  5282.5     .15       0  5561.3     .17       0
#XS Ineff= 2 , 0
       0  4612.4  226.87               0
Permanent Ineff=
       F       F
Bank Sta=4975.6,5020.9
XS Rating Curve= 0 ,0
Exp/Cntr=0.3,0.1

Type RM Length L Ch R = 1 ,1000    ,500,500,500
BEGIN DESCRIPTION:
Crystal Creek 024 2.0
END DESCRIPTION:
XS GIS Cut Line= 3
      3846572.19     10132046.68      3845679.28     10131448.74
      3844869.03     10131827.91
#Sta/Elev= 30
  3937.6  234.84  3969.1  234.86  3973.3  234.85  4045.8  233.89  4111.3  231.19
  4210.9  232.04  4275.1  230.58    4340  229.13  4565.2   228.2  4586.2  229.29
  4638.2  227.95  4689.5  227.83  4738.3  227.05  4838.4  223.79  4874.4  224.18
  4953.8  220.33  4969.9   221.7  4989.9   221.6  5001.4  219.13  5015.8  219.74
 5022.51221.6515  5122.7  222.81    5315  229.27  5337.9   228.7  5429.2  231.39
    5452  230.45  5526.1  231.88  5668.6  230.28  5816.2  231.41  5906.8  232.51
#Mann= 12 ,-1 , 0
  3937.6     .11       0  3969.1     .17       0  3973.3     .11       0
  4275.1     .17       0  4638.2     .15       0  4689.5     .17       0
  4738.3     .15       0  4969.9     .17       0  4989.9     .09       0
 5022.51     .17       0  5122.7     .15       0  5816.2     .17       0
Bank Sta=4989.9,5022.51
XS Rating Curve= 0 ,0
Exp/Cntr=0.3,0.1

Type RM Length L Ch R = 1 ,500     ,0,0,0
BEGIN DESCRIPTION:
Crystal Creek 024 1.0
END DESCRIPTION:
XS GIS Cut Line= 3
       3846613.8     10131973.71      3845752.45     10130996.15
       3844582.7     10131572.64
#Sta/Elev= 30
  3697.1  234.54  3794.9  233.45  3859.4  230.79  4002.8  231.23  4112.4  229.34
  4248.4  228.88    4348  232.11  4354.7  230.97  4511.2  229.44  4664.9  223.44
  4701.9  225.05  4730.3  221.33  4787.2  221.86  4801.5  219.52  4844.2   223.2
    4865  221.15  4872.6   221.9  4879.3   219.4  4894.5  220.23  4978.9  219.09
  4983.5  216.01  5016.3  219.33  5044.6  221.05  5454.4  229.29  5606.1   229.4
  5707.5  227.28  5857.6  230.67  6008.5   230.7  6143.7  233.24  6304.1     234
#Mann= 9 ,-1 , 0
  3697.1     .11       0  4002.8     .17       0  4112.4     .11       0
  4664.9     .15       0  4894.5     .11       0  4978.9     .09       0
  5016.3     .11       0  5857.6     .17       0  6143.7     .11       0
#XS Ineff= 3 ,-1
  4872.6  4836.6   221.9  4836.6  4709.4  223.26  5095.1  5127.8  222.05
Permanent Ineff=
       F       F       F
Bank Sta=4978.9,5016.3
XS Rating Curve= 0 ,0
Exp/Cntr=0.3,0.1

Chan Stop Cuts=-1
Use User Specified Reach Order=0
Composite Channel Slope=5

--- Crystal Creek 024.g10 (geometry) ---

Geom Title=Existing Conditions
Program Version=4.10

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
River Reach=Crystal Creek 02,Reach-1

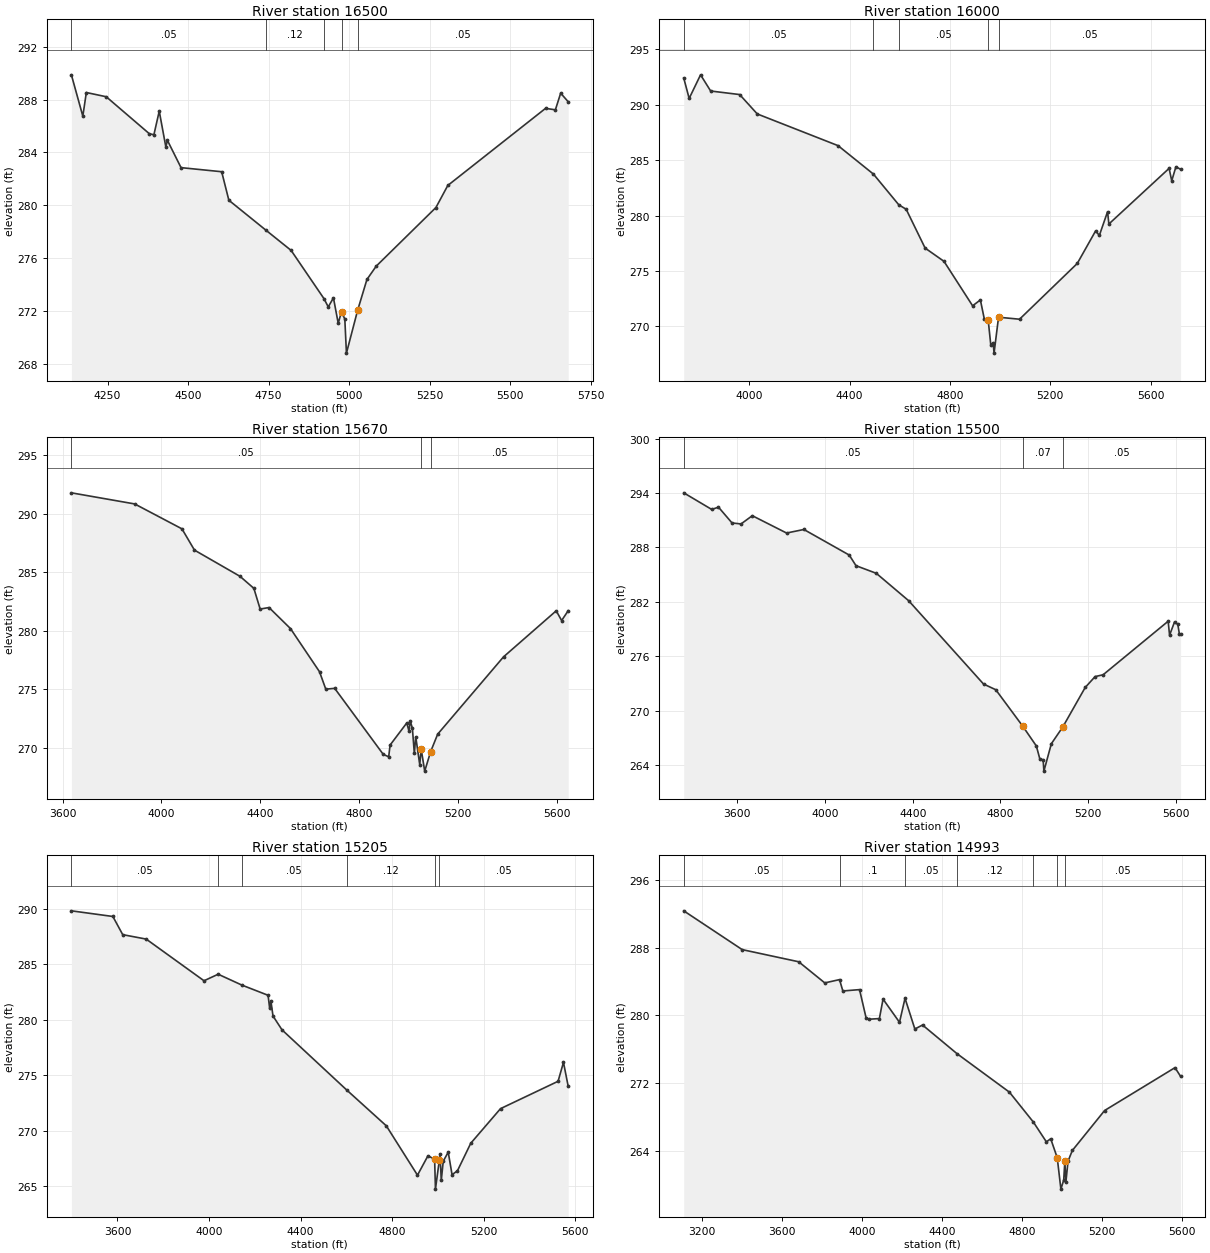
Type RM Length L Ch R = 1 ,16500   ,500,500,500
BEGIN DESCRIPTION:
Crystal Creek 024 32.0
END DESCRIPTION:
XS GIS Cut Line= 3
      3844913.02     10142125.36      3844074.57     10141924.82
      3843451.35     10142195.35
#Sta/Elev= 30
  4137.9  289.87  4173.4  286.74  4184.3  288.53    4246  288.21  4379.7  285.41
  4393.9  285.33  4410.5  287.12  4430.9  284.42    4436   284.9  4478.1  282.84
  4604.2  282.53  4626.5  280.37  4742.6  278.08  4819.7  276.57  4921.5  272.92
  4934.9  272.29    4951  272.98  4965.8  271.05  4976.1  271.94  4986.3  271.36
  4991.3  268.79    5026  272.03  5054.9  274.37  5083.8  275.38    5269  279.82
  5305.8  281.49  5609.1  287.33  5639.6  287.22    5656  288.48  5679.4  287.83
#Mann= 5 ,-1 , 0
  4137.9     .05       0  4742.6     .12       0  4921.5     .05       0
  4976.1     .07       0    5026     .05       0
Bank Sta=4976.1,5026
XS Rating Curve= 0 ,0
Exp/Cntr=0.3,0.1

Type RM Length L Ch R = 1 ,16000   ,330,330,330
BEGIN DESCRIPTION:
Crystal Creek 024 31.0
END DESCRIPTION:
XS GIS Cut Line= 3
      3845271.19     10141782.26       3844052.1     10141460.26
      3843364.13     10141671.27
#Sta/Elev= 30
  3739.1  292.41  3760.7  290.57  3806.1   292.7  3846.4  291.24    3962  290.92
  4032.2  289.17  4354.3  286.31  4495.4  283.74  4596.4  280.97  4625.8  280.57
  4701.2  277.07  4776.6  275.87  4890.6  271.86  4921.6  272.39  4937.6  270.63
  4952.7  270.58    4963  268.34  4972.7  268.53  4976.1  267.59    4994  270.83
  5077.7  270.65  5307.8  275.68    5381  278.62  5395.8  278.21  5428.6  280.35
  5433.8  279.24  5673.9  284.26  5684.3  283.14    5701   284.4  5719.6  284.18
#Mann= 5 ,-1 , 0
  3739.1     .05       0  4495.4     .12       0  4596.4     .05       0
  4952.7     .07       0    4994     .05       0
Bank Sta=4952.7,4994
XS Rating Curve= 0 ,0
Exp/Cntr=0.3,0.1

Type RM Length L Ch R = 1 ,15670   ,170,170,170
BEGIN DESCRIPTION:
Mapping XS 911f145d
END DESCRIPTION:
XS GIS Cut Line= 3
      3845188.88     10141535.74       3844009.2     10141111.27
       3843342.7     10141470.56
#Sta/Elev= 30
  3635.9   291.8  3892.1  290.85  4083.4  288.72  4134.1   286.9  4318.4  284.66
  4374.5  283.63  4399.9  281.86  4435.9  281.99  4522.7  280.19  4640.2   276.5
  4665.6  275.01  4701.6  275.08  4898.3  269.43  4920.2  269.23  4925.9  270.23
  4993.4  272.12  5002.1  271.44  5007.8  272.27  5016.1  271.66    5024  269.52
  5029.7  270.94  5045.9  268.55  5051.6  269.89    5066     268  5089.7  269.65
  5118.4  271.16  5384.9  277.77  5598.2  281.71  5620.1  280.88  5646.8  281.72
#Mann= 3 , 0 , 0
  3635.9     .05       0  5051.6     .07       0  5089.7     .05       0
Bank Sta=5051.6,5089.7
XS Rating Curve= 0 ,0
Exp/Cntr=0.3,0.1

Type RM Length L Ch R = 1 ,15500   ,295,295,295
BEGIN DESCRIPTION:
Crystal Creek 024 30.0
END DESCRIPTION:
XS GIS Cut Line= 3
      3845441.98     10141394.53      3843842.66     10141011.71
      3843293.51     10141302.94
#Sta/Elev= 30
  3355.5  294.02  3483.1  292.19    3514  292.44  3575.7   290.7  3616.8  290.59
  3668.2   291.5  3824.5  289.59  3903.5  289.98  4110.4  287.16  4141.2  285.99
  4233.8  285.15  4381.4  282.13  4722.8  272.95  4778.7  272.32  4902.1  268.29
  4963.8  266.12  4980.2  264.65  4994.7  264.61  4998.2  263.35  5032.2  266.37
  5084.7  268.23  5186.6  272.57  5231.8  273.77  5268.4  273.97    5565  279.87
  5571.4  278.33    5594  279.79    5609  279.52  5616.3  278.45  5621.6  278.45
#Mann= 3 , 0 , 0
  3355.5     .05       0  4902.1     .07       0  5084.7     .05       0
Bank Sta=4902.1,5084.7
XS Rating Curve= 0 ,0
Exp/Cntr=0.3,0.1

Type RM Length L Ch R = 1 ,15205   ,212,212,212
BEGIN DESCRIPTION:
Mapping XS cc6617fc
END DESCRIPTION:
XS GIS Cut Line= 3
      3845246.18      10141257.1      3843839.93     10140697.21
      3843235.75     10140955.02
#Sta/Elev= 30
  3398.6  289.83  3579.8  289.32  3622.9  287.68  3725.4  287.28    3978  283.52
  4039.9  284.11  4143.4  283.13  4257.9  282.21  4264.9  281.02  4270.2   281.7
  4279.4  280.34  4318.8  279.09  4600.6  273.68  4774.5  270.43  4910.6  265.98
  4956.4  267.73  4985.5  267.41  4989.1  264.72 5006.14 267.349  5009.1  267.89
  5014.5   265.5  5023.2  267.24  5044.9  268.06  5061.7  266.02  5085.3  266.38
  5143.4  268.86  5273.3  271.98  5524.8  274.45  5548.4  276.16  5569.1  273.99
#Mann= 6 ,-1 , 0
  3398.6     .05       0  4039.9      .1       0  4143.4     .05       0
  4600.6     .12       0  4985.5     .07       0 5006.14     .05       0
Bank Sta=4985.5,5006.14
XS Rating Curve= 0 ,0
Exp/Cntr=0.3,0.1

Type RM Length L Ch R = 1 ,14993   ,493,493,493
BEGIN DESCRIPTION:
Crystal Creek 024 29.0
END DESCRIPTION:
XS GIS Cut Line= 3
      3845497.05     10141263.36      3843755.81     10140530.95
      3843203.84     10140744.94
#Sta/Elev= 30
    3111  292.32    3403  287.75  3685.1  286.32  3815.3  283.83    3889  284.22
  3905.5  282.88  3988.9  283.04  4021.4  279.73  4035.1  279.55    4088  279.63
  4106.3  281.92  4188.4  279.19    4216  282.02  4265.1   278.4  4303.5  278.87
  4475.3   275.5  4737.4  270.96  4857.2  267.43  4921.8  265.11  4943.5  265.47
  4976.1  263.24  4994.4  259.54  5008.5  260.62    5014   262.8  5019.4   260.4
    5030  262.83  5051.4  264.09  5212.7   268.8  5564.2  273.85    5592  272.82
#Mann= 7 ,-1 , 0
    3111     .05       0    3889      .1       0    4216     .05       0
  4475.3     .12       0  4857.2     .05       0  4976.1     .05       0
    5014     .05       0
Bank Sta=4976.1,5014
XS Rating Curve= 0 ,0
Exp/Cntr=0.3,0.1

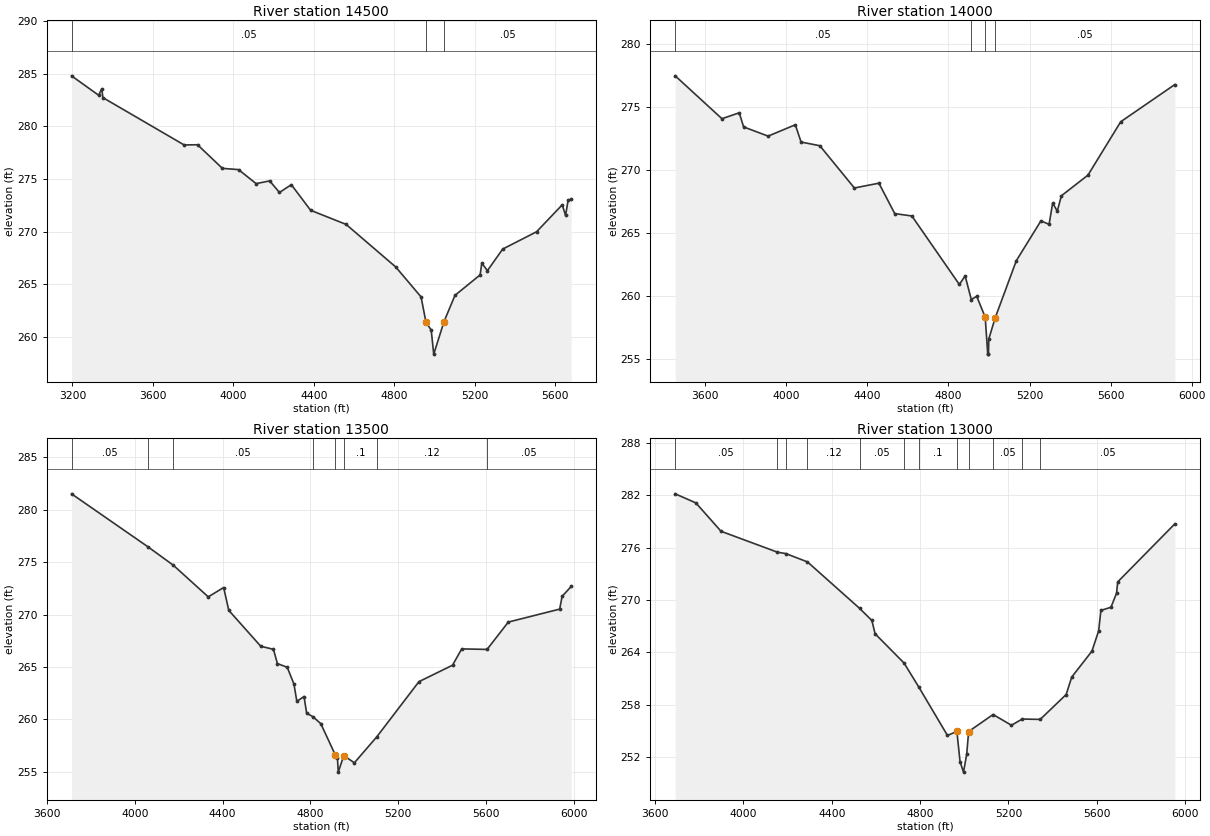
Type RM Length L Ch R = 1 ,14500   ,500,500,500
BEGIN DESCRIPTION:
Crystal Creek 024 28.0
END DESCRIPTION:
XS GIS Cut Line= 3
      3845262.65     10140971.68      3843700.75     10140067.57
      3843094.49     10140376.86
#Sta/Elev= 30
  3195.3  284.79    3330  282.95  3345.7  283.55  3351.5  282.72  3755.5  278.23
  3822.1  278.25  3945.6  276.01  4025.9  275.89  4113.6  274.56  4180.9  274.82
  4229.7  273.72  4288.6  274.46  4384.7  272.03  4561.2  270.69    4808  266.65
    4934  263.81 4957.99 261.443  4984.5  260.65    4997  258.38  5048.2  261.47
  5102.7  263.96  5227.8   265.9  5236.1  267.02  5263.9   266.3    5340  268.35
  5508.4  269.99  5636.2  272.55  5652.8  271.54  5665.6     273  5680.6  273.06
#Mann= 3 , 0 , 0
  3195.3     .05       0 4957.99     .03       0  5048.2     .05       0
Bank Sta=4957.99,5048.2
XS Rating Curve= 0 ,0
Exp/Cntr=0.3,0.1

Type RM Length L Ch R = 1 ,14000   ,500,500,500
BEGIN DESCRIPTION:
Crystal Creek 024 27.0
END DESCRIPTION:
XS GIS Cut Line= 3
      3844960.56     10140643.55      3843771.42     10139651.52
      3842863.54     10139780.54
#Sta/Elev= 30
  3451.4  277.47  3682.2  274.07  3767.5  274.54    3789  273.42    3910  272.69
  4044.1  273.59  4072.7  272.22  4165.1  271.93  4335.6  268.58  4456.7  268.96
  4534.8  266.55  4619.4  266.36  4853.6  260.93  4882.3  261.61  4912.5  259.74
  4939.5  259.99  4981.2  258.34  4993.8  255.41  4997.3  255.41  4999.1  256.62
  5030.6  258.29  5134.9  262.82  5256.1  265.97  5296.5   265.7  5314.2  267.39
  5336.9  266.74  5357.1  267.96  5488.4   269.6    5650  273.83    5917  276.78
#Mann= 4 ,-1 , 0
  3451.4     .05       0  4912.5      .1       0  4981.2     .07       0
  5030.6     .05       0
Bank Sta=4981.2,5030.6
XS Rating Curve= 0 ,0
Exp/Cntr=0.3,0.1

Type RM Length L Ch R = 1 ,13500   ,500,500,500
BEGIN DESCRIPTION:
Crystal Creek 024 26.0
END DESCRIPTION:
XS GIS Cut Line= 3
      3845238.55     10139773.58      3844057.73     10139257.18
      3843129.12     10138919.79
#Sta/Elev= 30
  3711.2  281.53  4060.2  276.46  4175.1  274.71  4334.2  271.69  4404.4  272.58
  4427.8   270.4  4573.6  266.97  4631.3  266.68  4649.3  265.32  4694.3  264.96
  4724.9  263.35  4737.9  261.71  4770.7  262.17  4782.6  260.58  4810.7  260.25
  4847.1  259.58  4912.6  256.62    4923  256.28  4926.7  254.95  4951.8  256.53
    5000  255.84  5102.2  258.32  5294.3  263.59  5447.3  265.16  5489.3  266.72
  5604.8  266.67  5701.4  269.28  5935.6  270.52  5946.8  271.74    5988  272.68
#Mann= 8 ,-1 , 0
  3711.2     .05       0  4060.2     .12       0  4175.1     .05       0
  4810.7      .1       0  4912.6     .07       0  4951.8      .1       0
  5102.2     .12       0  5604.8     .05       0
Bank Sta=4912.6,4951.8
XS Rating Curve= 0 ,0
Exp/Cntr=0.3,0.1

Type RM Length L Ch R = 1 ,13000   ,499,499,499
BEGIN DESCRIPTION:
Crystal Creek 024 25.0
END DESCRIPTION:
XS GIS Cut Line= 3
      3845294.15     10139665.97      3844268.28     10138854.04
      3843373.59     10138525.82
#Sta/Elev= 30
  3691.7  282.15  3785.4  281.11  3899.2  277.86    4154  275.47    4193   275.3
  4290.4  274.35  4525.9  269.04  4581.9  267.64  4596.4  266.12  4727.4  262.77
  4794.1  260.02    4924  254.47  4966.6  254.93    4981  251.46  4996.6  250.27
  5011.1  252.34  5019.8  254.92  5130.4  256.87  5213.5  255.64  5262.4  256.35
  5343.7  256.31  5461.2  259.16  5486.4  261.16  5577.9  264.13  5608.4  266.47
  5618.3  268.79    5664  269.16  5689.2  270.76  5694.5  272.06    5953  278.71
#Mann= 12 ,-1 , 0
  3691.7     .05       0    4154     .12       0    4193     .05       0
  4290.4     .12       0  4525.9     .05       0  4727.4     .12       0
  4794.1      .1       0  4966.6     .07       0  5019.8      .1       0
  5130.4     .05       0  5262.4     .12       0  5343.7     .05       0
Bank Sta=4966.6,5019.8
XS Rating Curve= 0 ,0
Exp/Cntr=0.3,0.1