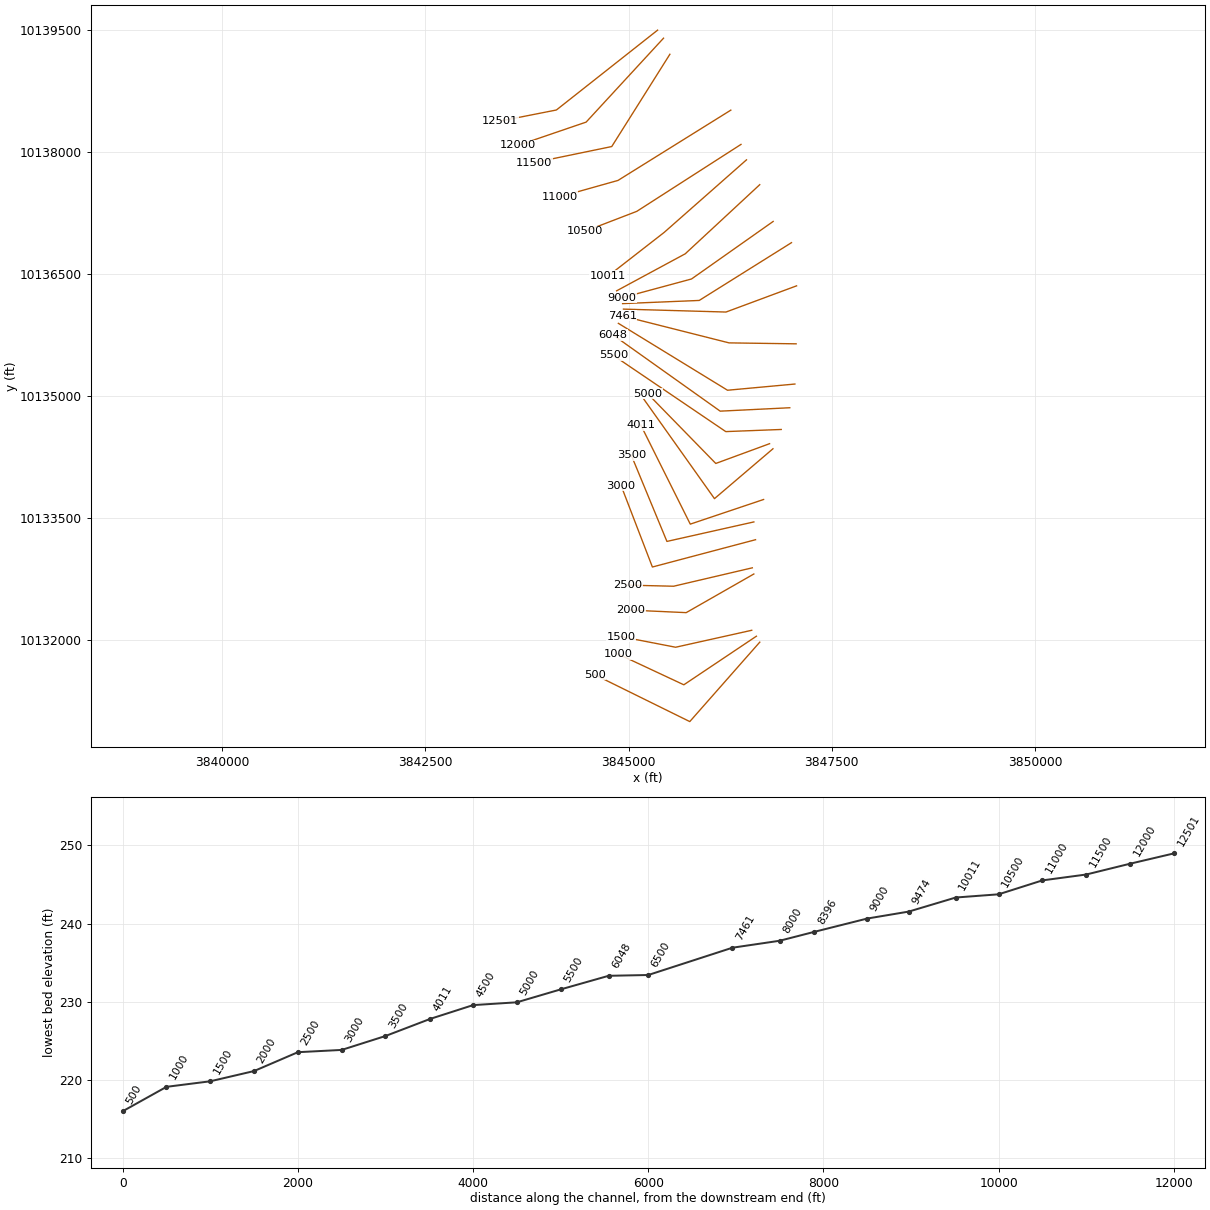
HEC-RAS study Crystal Creek 024.prj: Crystal Creek 024 Base Level Engineering

--- Crystal Creek 024.g10 (geometry) --- (continued)

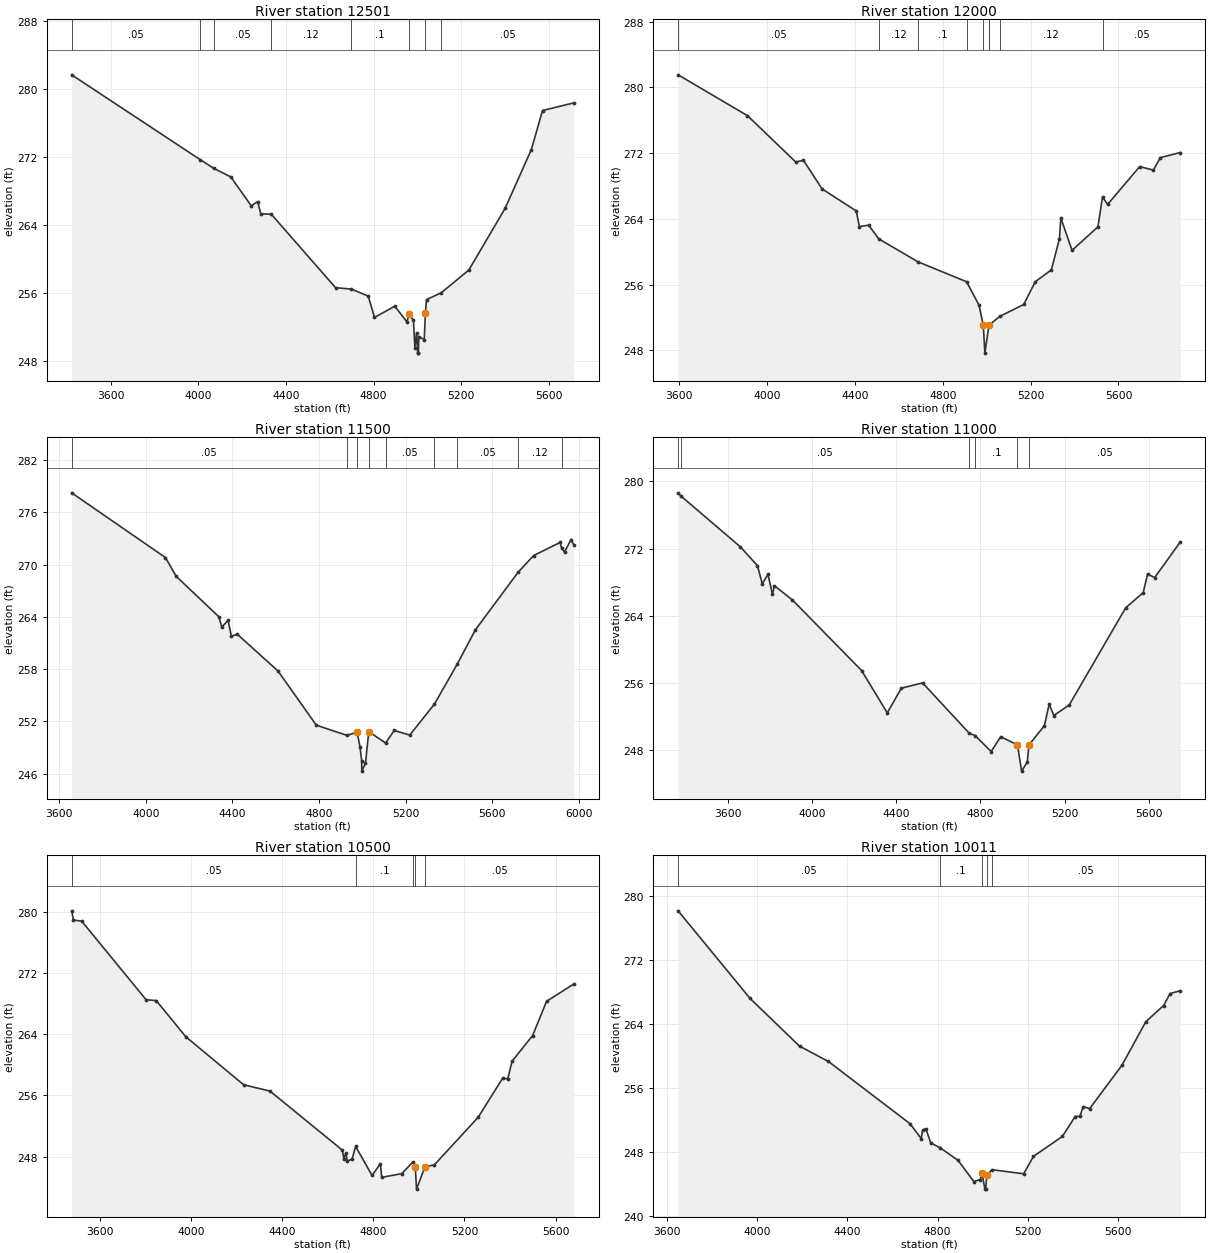
Type RM Length L Ch R = 1 ,12501   ,501,501,501
BEGIN DESCRIPTION:
Crystal Creek 024 24.0
END DESCRIPTION:
XS GIS Cut Line= 3
      3845356.59     10139504.47      3844110.85     10138521.65
      3843417.43     10138385.05
#Sta/Elev= 30
  3421.1  281.72  4009.5  271.72    4070  270.72  4148.5   269.7  4241.5   266.3
  4270.4  266.81  4284.8  265.37  4332.8  265.32  4626.3  256.68  4698.9  256.51
  4775.4  255.69  4804.2  253.18    4897   254.5  4953.3  252.62  4960.7  253.62
  4982.2  252.82  4988.6  249.63  4996.6  251.39  5001.3  248.98  5004.8  248.98
  5006.6  250.93  5031.3  250.58  5036.6  253.66  5041.7  255.27  5110.2   256.1
  5235.1  258.76  5401.1  266.03  5520.5  272.92  5571.5  277.52  5714.6  278.42
#Mann= 8 ,-1 , 0
  3421.1     .05       0  4009.5     .12       0    4070     .05       0
  4332.8     .12       0  4698.9      .1       0  4960.7     .07       0
  5036.6      .1       0  5110.2     .05       0
Bank Sta=4960.7,5036.6
XS Rating Curve= 0 ,0
Exp/Cntr=0.3,0.1

Type RM Length L Ch R = 1 ,12000   ,500,500,500
BEGIN DESCRIPTION:
Crystal Creek 024 23.0
END DESCRIPTION:
XS GIS Cut Line= 3
      3845429.51     10139405.51       3844477.2     10138372.76
      3843643.12     10138087.84
#Sta/Elev= 30
  3595.2  281.54    3911  276.57  4130.5  270.93  4165.7  271.14  4250.7  267.65
  4406.1  264.97  4420.3  263.07  4462.8  263.23  4508.4  261.57  4687.6  258.77
  4908.5  256.35  4965.2  253.49  4984.5 251.071  4991.8  247.66  5009.9  251.03
  5012.7  251.11  5059.7  252.13  5168.4  253.58  5221.2  256.35  5294.5   257.8
  5331.1  261.58  5337.5  264.12  5388.5  260.17  5506.5  263.04  5527.3  266.68
  5550.3  265.76  5696.4  270.37    5759  269.94  5790.3  271.46  5881.4  272.08
#Mann= 9 ,-1 , 0
  3595.2     .05       0  4508.4     .12       0  4687.6      .1       0
  4908.5     .12       0  4984.5     .07       0  5009.9     .12       0
  5012.7      .1       0  5059.7     .12       0  5527.3     .05       0
Bank Sta=4984.5,5009.9
XS Rating Curve= 0 ,0
Exp/Cntr=0.3,0.1

Type RM Length L Ch R = 1 ,11500   ,500,500,500
BEGIN DESCRIPTION:
Crystal Creek 024 22.0
END DESCRIPTION:
XS GIS Cut Line= 3
      3845507.64     10139207.59      3844792.29     10138072.02
      3843835.81     10137874.29
#Sta/Elev= 30
  3657.9  278.25  4091.1  270.81  4140.1  268.67  4337.8  264.01  4351.1  262.83
  4380.2   263.6  4395.5  261.77  4422.6  262.01  4611.1  257.77  4787.5  251.56
    4929  250.39  4975.9  250.75  4989.3  249.08  4997.1  247.45  4997.7  246.28
  5014.7  247.19  5029.7  250.82  5107.6  249.51  5147.5  250.95    5219  250.42
  5332.5  253.96  5438.3  258.57  5521.8   262.5  5719.8  269.14  5790.8  271.04
  5913.4  272.55  5919.8  271.94  5933.8  271.45  5963.6  272.88  5976.7  272.28
#Mann= 9 ,-1 , 0
  3657.9     .05       0    4929      .1       0  4975.9     .07       0
  5029.7      .1       0  5107.6     .05       0  5332.5     .12       0
  5438.3     .05       0  5719.8     .12       0  5919.8     .05       0
Bank Sta=4975.9,5029.7
XS Rating Curve= 0 ,0
Exp/Cntr=0.3,0.1

Type RM Length L Ch R = 1 ,11000   ,500,500,500
BEGIN DESCRIPTION:
Crystal Creek 024 21.0
END DESCRIPTION:
XS GIS Cut Line= 3
      3846257.69     10138520.13      3844869.23     10137655.07
      3844148.27      10137452.4
#Sta/Elev= 30
  3364.1  278.65  3376.5  278.29  3659.9  272.22  3740.9  269.98  3763.8  267.82
  3790.9  268.96  3812.1  266.56  3821.6  267.59  3906.5  265.91  4235.8  257.49
  4357.3  252.46  4424.3   255.4  4524.9  256.03  4747.8  250.01    4774  249.77
  4850.6  247.86  4895.6  249.62  4975.7  248.66  4995.2  245.53  5022.2  246.62
  5030.3  248.65  5103.6  250.94  5126.1  253.49  5148.1  252.15  5221.4   253.4
  5489.6  264.97  5572.7  266.78  5593.5  268.97  5627.2  268.57  5748.9   272.8
#Mann= 6 ,-1 , 0
  3364.1     .12       0  3376.5     .05       0  4747.8     .12       0
    4774      .1       0  4975.7     .07       0  5030.3     .05       0
Bank Sta=4975.7,5030.3
XS Rating Curve= 0 ,0
Exp/Cntr=0.3,0.1

Type RM Length L Ch R = 1 ,10500   ,489,489,489
BEGIN DESCRIPTION:
Crystal Creek 024 20.0
END DESCRIPTION:
XS GIS Cut Line= 3
       3846382.7     10138098.26      3845100.82     10137274.76
      3844465.98     10137030.53
#Sta/Elev= 30
  3476.4  280.09  3484.3  278.89  3520.6  278.74  3803.1  268.48  3847.6  268.37
  3977.7  263.64    4231  257.38  4346.9  256.55  4664.7  248.83  4670.7  247.73
  4679.9  248.46  4685.8  247.42  4706.9  247.67  4722.7  249.32  4794.8  245.53
  4831.1  247.07  4837.1  245.29  4924.9  245.77    4975  247.33  4984.4 246.677
  4989.9  243.75  5027.1   246.7  5067.5   246.9  5260.3  253.13  5367.5  258.22
  5390.3  258.17  5409.5  260.47  5499.5  263.81  5560.3  268.27  5680.2  270.54
#Mann= 5 ,-1 , 0
  3476.4     .05       0  4722.7      .1       0    4975     .05       0
  4984.4     .07       0  5027.1     .05       0
Bank Sta=4984.4,5027.1
XS Rating Curve= 0 ,0
Exp/Cntr=0.3,0.1

Type RM Length L Ch R = 1 ,10011   ,537,537,537
BEGIN DESCRIPTION:
Crystal Creek 024 19.0
END DESCRIPTION:
XS GIS Cut Line= 3
      3846450.22     10137908.25      3845438.08     10137015.96
      3844747.26     10136478.46
#Sta/Elev= 30
  3650.7  278.14  3969.3  267.19  4188.5  261.22  4316.6   259.3    4678  251.52
  4727.3  249.67    4734  250.73  4748.2  250.89    4770  249.11  4810.7  248.52
  4890.5  246.95  4960.7  244.29  4989.2  244.54  4996.7  245.34  5009.6  243.34
  5013.1  243.34  5017.7  245.05    5041  245.77  5181.5  245.26  5224.9  247.44
  5353.4  249.94  5409.5  252.42  5431.1  252.45  5444.8  253.66  5473.8  253.41
  5616.7  258.83  5722.6  264.28  5801.3   266.3  5830.3   267.8  5875.3  268.15
#Mann= 5 ,-1 , 0
  3650.7     .05       0  4810.7      .1       0  4996.7     .07       0
  5017.7      .1       0    5041     .05       0
Bank Sta=4996.7,5017.7
XS Rating Curve= 0 ,0
Exp/Cntr=0.3,0.1

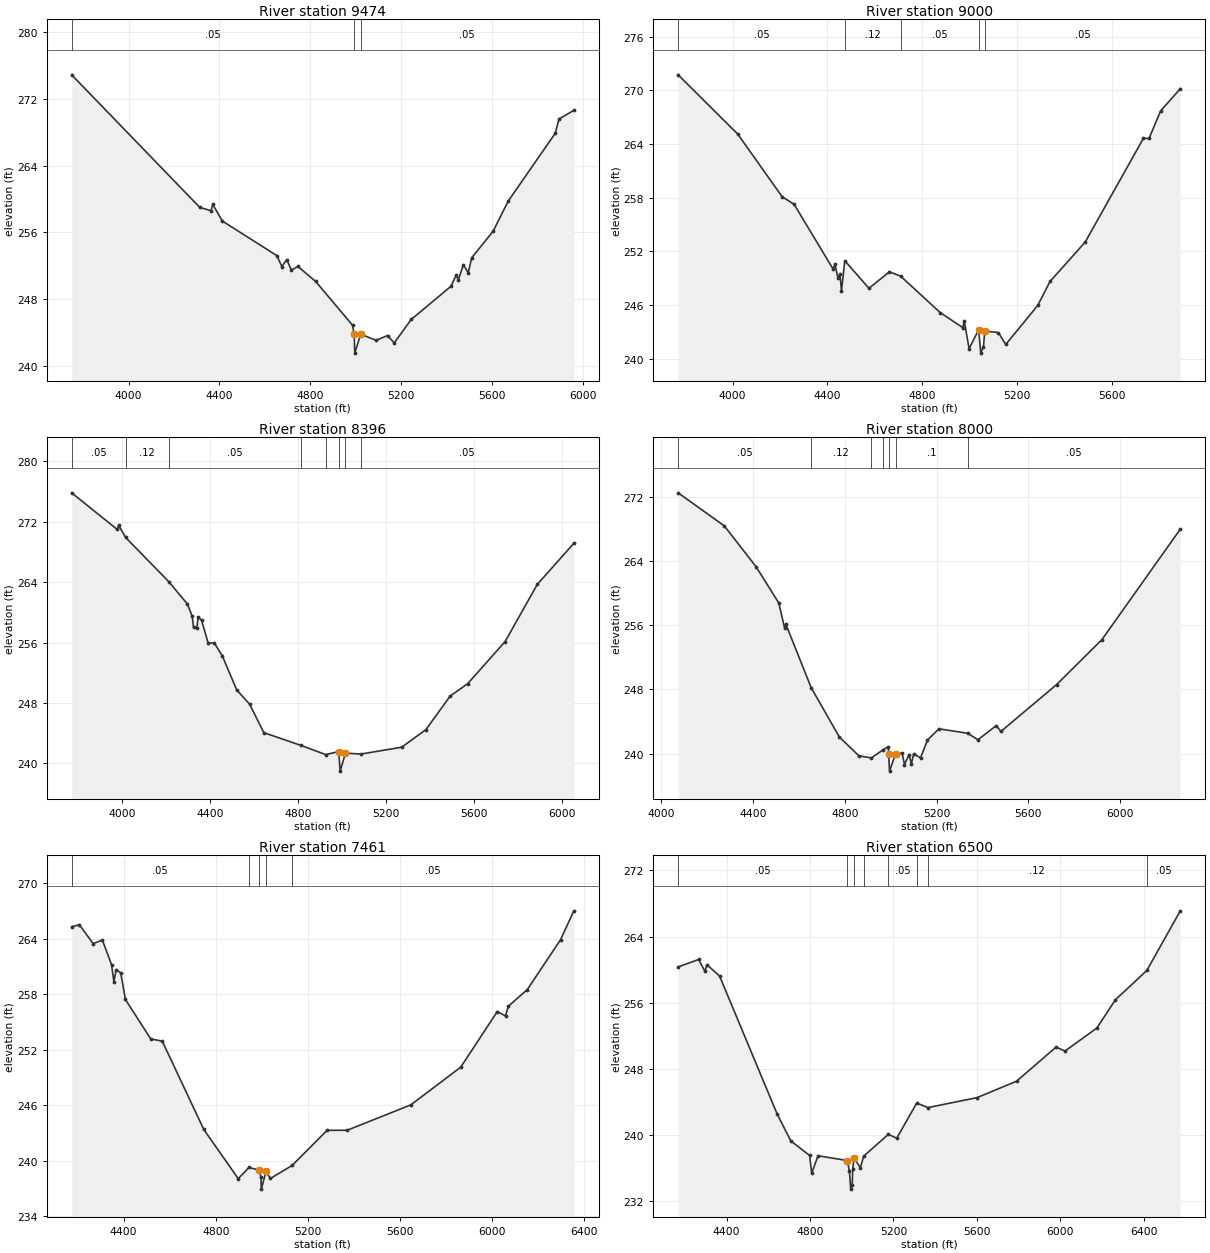
Type RM Length L Ch R = 1 ,9474    ,474,474,474
BEGIN DESCRIPTION:
Crystal Creek 024 18.0
END DESCRIPTION:
XS GIS Cut Line= 3
      3846613.37     10137602.73      3845696.55     10136752.17
      3844852.13     10136296.54
#Sta/Elev= 30
  3749.4  274.88  4313.6  258.99    4363   258.6  4370.3  259.37  4412.3  257.37
  4653.2  253.21  4674.2   251.9  4695.8  252.74  4716.7  251.49  4745.1  251.92
  4822.8  250.14  4985.5  244.89  4992.8  243.79  4995.4  241.54  5021.2   243.8
  5089.4  243.08  5139.9  243.65    5169  242.76  5243.7  245.57  5418.9  249.55
  5441.7   250.9  5451.2  250.32  5473.1   252.1    5495  251.18  5509.8  252.96
  5604.5  256.15  5670.1  259.73  5877.7  267.88  5893.9  269.59  5959.5  270.62
#Mann= 3 , 0 , 0
  3749.4     .05       0  4992.8     .07       0  5021.2     .05       0
Bank Sta=4992.8,5021.2
XS Rating Curve= 0 ,0
Exp/Cntr=0.3,0.1

Type RM Length L Ch R = 1 ,9000    ,604,604,604
BEGIN DESCRIPTION:
Crystal Creek 024 17.0
END DESCRIPTION:
XS GIS Cut Line= 3
      3846778.47      10137150.3      3845773.68     10136442.25
      3844917.86     10136211.07
#Sta/Elev= 30
  3770.8  271.73  4021.8  265.12    4209  258.12  4259.5  257.27  4423.3  250.06
  4431.9  250.55  4444.4     249  4452.9  249.47    4459  247.58    4473  250.97
  4574.8  247.89    4661  249.73  4708.1  249.25  4875.3  245.17  4970.2   243.5
  4976.3  244.24  4996.7  241.16  5037.1  243.26  5045.7  240.65  5057.3  241.37
  5062.5  243.12    5120  242.95  5151.1  241.62  5285.7  245.97  5337.5  248.65
  5485.8  253.05  5731.1  264.64  5754.7  264.62  5803.6   267.7  5886.5  270.18
#Mann= 5 ,-1 , 0
  3770.8     .05       0    4473     .12       0  4708.1     .05       0
  5037.1     .07       0  5062.5     .05       0
Bank Sta=5037.1,5062.5
XS Rating Curve= 0 ,0
Exp/Cntr=0.3,0.1

Type RM Length L Ch R = 1 ,8396    ,396,396,396
BEGIN DESCRIPTION:
Crystal Creek 024 16.0
END DESCRIPTION:
XS GIS Cut Line= 3
      3847004.01     10136889.21      3845868.69     10136178.25
      3844925.85     10136139.21
#Sta/Elev= 30
  3769.4  275.84    3977  270.98  3982.9  271.55  4014.8  269.92  4211.8  264.04
  4295.8  261.09  4317.6  259.47  4323.5  257.99  4338.8  257.96  4344.7  259.41
  4360.1  258.94  4390.2  255.91  4417.8  255.94  4454.4  254.23    4520  249.71
    4579  247.81    4643  244.05  4810.8  242.37  4924.6  241.14  4983.6  241.54
  4990.2  238.95  5014.3  241.34  5083.9  241.21  5269.9  242.12    5380  244.45
  5490.1  248.89  5570.2  250.55  5740.3  256.13  5886.1  263.69  6052.6  269.15
#Mann= 8 ,-1 , 0
  3769.4     .05       0  4014.8     .12       0  4211.8     .05       0
  4810.8     .12       0  4924.6      .1       0  4983.6     .07       0
  5014.3      .1       0  5083.9     .05       0
Bank Sta=4983.6,5014.3
XS Rating Curve= 0 ,0
Exp/Cntr=0.3,0.1

Type RM Length L Ch R = 1 ,8000    ,539,539,539
BEGIN DESCRIPTION:
Crystal Creek 024 15.0
END DESCRIPTION:
XS GIS Cut Line= 3
      3847066.52     10136357.96      3846198.14     10136035.56
      3844936.35      10136071.5
#Sta/Elev= 30
  4073.7  272.52  4274.9   268.4  4413.6   263.3  4512.5  258.78  4537.6  255.68
  4542.9  256.15  4653.6  248.22  4776.3  242.07  4861.6  239.72    4916  239.46
  4964.9  240.43  4989.6  240.86 4991.41 239.955    4995  237.81  5021.6  239.99
  5050.3  240.03  5060.3  238.63  5080.3  239.88  5090.3  238.71  5100.3  239.98
  5130.3  239.46  5160.4  241.69  5210.4  243.09  5335.5  242.53  5380.4  241.73
  5460.5  243.49  5480.5  242.76  5722.9   248.6  5920.7  254.21  6262.3  267.99
#Mann= 7 ,-1 , 0
  4073.7     .05       0  4653.6     .12       0    4916     .05       0
  4964.9      .1       0 4991.41     .07       0  5021.6      .1       0
  5335.5     .05       0
Bank Sta=4991.41,5021.6
XS Rating Curve= 0 ,0
Exp/Cntr=0.3,0.1

Type RM Length L Ch R = 1 ,7461    ,961,961,961
BEGIN DESCRIPTION:
Crystal Creek 024 14.0
END DESCRIPTION:
XS GIS Cut Line= 3
      3847061.28     10135644.42      3846235.76     10135656.06
      3844921.81     10135987.89
#Sta/Elev= 30
  4174.4   265.3  4207.8  265.53  4267.8  263.48  4307.8  263.87  4347.8   261.2
  4357.8  259.37  4367.8  260.68  4387.8  260.31  4407.8  257.44  4517.9  253.17
  4567.9  252.93  4747.9  243.39  4897.9  238.05  4943.8  239.26  4987.9  238.99
  4996.5  238.22  4998.1  236.92  5018.5  238.84  5037.4  238.07  5131.8  239.48
  5283.7  243.28    5371  243.29  5647.6  246.04  5864.2  250.12  6022.6  256.13
  6058.5  255.66  6070.5   256.7    6153  258.51  6297.4   263.9  6355.2  267.03
#Mann= 5 ,-1 , 0
  4174.4     .05       0  4943.8      .1       0  4987.9     .07       0
  5018.5      .1       0  5131.8     .05       0
Bank Sta=4987.9,5018.5
XS Rating Curve= 0 ,0
Exp/Cntr=0.3,0.1

Type RM Length L Ch R = 1 ,6500    ,452,452,452
BEGIN DESCRIPTION:
Crystal Creek 024 13.0
END DESCRIPTION:
XS GIS Cut Line= 3
      3847045.69     10135149.63      3846216.99     10135073.35
      3844873.76     10135896.52
#Sta/Elev= 30
  4167.8  260.32    4266  261.22  4296.2  259.79  4306.2  260.59  4366.5  259.22
  4642.8  242.51  4707.9  239.27  4798.3   237.5  4808.3  235.35  4838.5  237.47
  4979.1  236.89  4989.1  235.58  4995.2  233.43  5002.4  233.93    5005  235.88
  5010.9  237.19  5041.8  236.02  5057.1  237.41  5175.6  240.06  5215.8  239.59
  5311.9  243.85  5365.2   243.3  5600.7   244.5  5790.3  246.49  5979.8  250.62
  6022.4  250.14  6175.2  252.92  6264.1  256.34  6415.1   259.9  6575.4  267.11
#Mann= 8 ,-1 , 0
  4167.8     .05       0  4979.1     .07       0  5010.9     .05       0
  5057.1      .1       0  5175.6     .05       0  5311.9      .1       0
  5365.2     .12       0  6415.1     .05       0
Bank Sta=4979.1,5010.9
XS Rating Curve= 0 ,0
Exp/Cntr=0.3,0.1

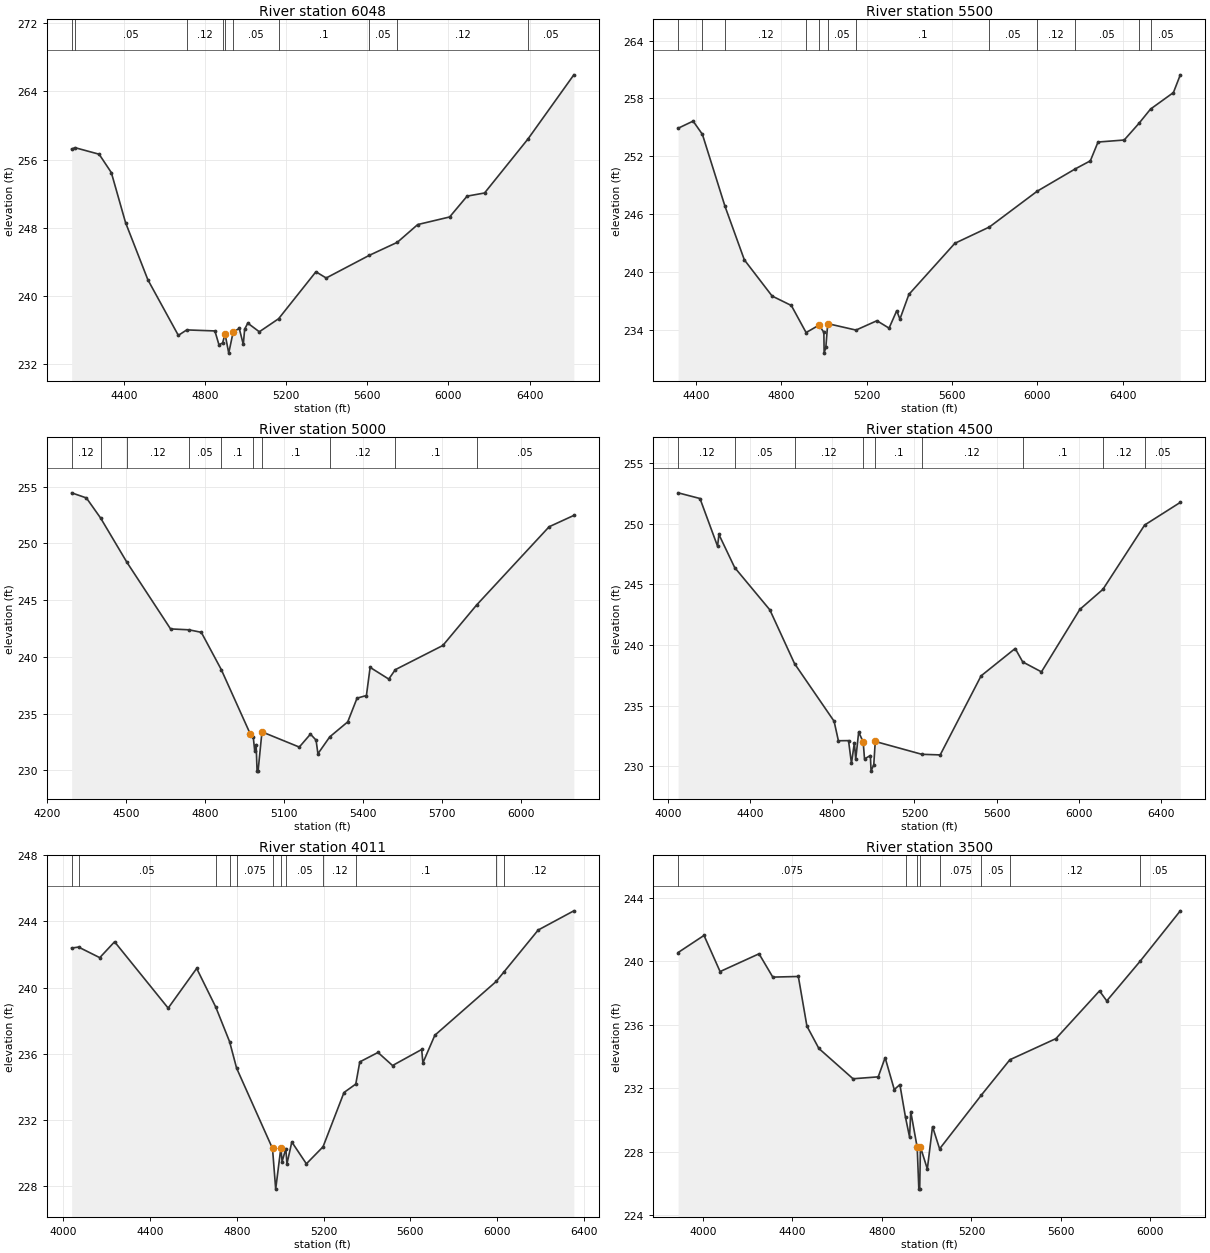
Type RM Length L Ch R = 1 ,6048    ,548,548,548
BEGIN DESCRIPTION:
Crystal Creek 024 12.0
END DESCRIPTION:
XS GIS Cut Line= 3
      3846983.17     10134857.96       3846126.7     10134815.93
      3844807.87     10135753.77
#Sta/Elev= 30
  4142.5  257.22  4158.7   257.4    4278  256.63  4338.1  254.48  4408.1  248.63
  4518.3  241.92  4668.5  235.41  4709.9  236.05  4848.7  235.93  4868.7  234.31
  4886.7  234.52  4898.7  235.58  4916.9  233.33  4938.8  235.81  4968.8  236.22
  4988.8  234.35  4995.4  236.14  5010.9  236.84  5067.7  235.83  5162.8  237.36
  5346.8  242.86  5397.3  242.13  5609.4  244.78    5748  246.31  5848.6  248.39
    6006  249.28  6092.1  251.72  6178.2  252.09    6392  258.41  6618.3  265.93
#Mann= 10 ,-1 , 0
  4142.5     .12       0  4158.7     .05       0  4709.9     .12       0
  4886.7     .05       0  4898.7     .07       0  4938.8     .05       0
  5162.8      .1       0  5609.4     .05       0    5748     .12       0
    6392     .05       0
Bank Sta=4898.7,4938.8
XS Rating Curve= 0 ,0
Exp/Cntr=0.3,0.1

Type RM Length L Ch R = 1 ,5500    ,500,500,500
BEGIN DESCRIPTION:
Crystal Creek 024 11.0
END DESCRIPTION:
XS GIS Cut Line= 3
      3846878.15      10134590.6      3846195.45     10134564.37
      3844812.54     10135501.81
#Sta/Elev= 30
  4316.8  254.91  4387.1  255.65  4430.6  254.28  4536.6  246.81  4627.3  241.26
  4757.4  237.51  4847.5  236.53  4916.7  233.72  4977.6   234.5    5000  233.74
  5001.2  231.59  5009.2  232.19    5018  234.65  5150.6  233.98  5248.6  234.95
  5305.6  234.18  5341.5  235.99  5356.5  235.12  5398.5  237.68  5614.1  242.98
  5775.9  244.67  5999.8  248.38  6178.7   250.7    6249  251.53    6285  253.48
  6407.7  253.69  6476.6  255.41  6531.2   256.9  6638.4  258.61  6670.7  260.45
#Mann= 12 ,-1 , 0
  4316.8     .12       0  4430.6     .05       0  4536.6     .12       0
  4916.7     .05       0  4977.6     .07       0    5018     .05       0
  5150.6      .1       0  5775.9     .05       0  5999.8     .12       0
  6178.7     .05       0  6476.6     .12       0  6531.2     .05       0
Bank Sta=4977.6,5018
XS Rating Curve= 0 ,0
Exp/Cntr=0.3,0.1

Type RM Length L Ch R = 1 ,5000    ,500,500,500
BEGIN DESCRIPTION:
Crystal Creek 024 10.0
END DESCRIPTION:
XS GIS Cut Line= 3
      3846734.48     10134415.68      3846072.49     10134172.32
      3845234.49     10135030.27
#Sta/Elev= 30
  4294.7  254.46  4350.6  254.01  4404.5  252.24    4504  248.35  4669.8  242.47
  4739.9  242.39  4786.4  242.17  4862.1  238.89    4973  233.17  4983.6  232.91
    4989  231.72  4994.4  232.28  4997.9  229.94  5001.7  229.94  5016.5   233.4
    5158  232.06  5200.4   233.2  5221.7  232.67  5228.7  231.47  5273.6  232.96
  5341.8  234.28  5377.1  236.37  5412.6   236.6  5426.7  239.08  5497.4  238.05
  5522.3  238.88  5702.5  241.01  5830.3  244.57  6105.5  251.47  6199.3  252.47
#Mann= 10 ,-1 , 0
  4294.7     .12       0  4404.5     .05       0    4504     .12       0
  4739.9     .05       0  4862.1      .1       0  4983.6     .07       0
  5016.5      .1       0  5273.6     .12       0  5522.3      .1       0
  5830.3     .05       0
Bank Sta=4973,5016.5
XS Rating Curve= 0 ,0
Exp/Cntr=0.3,0.1

Type RM Length L Ch R = 1 ,4500    ,489,489,489
BEGIN DESCRIPTION:
Crystal Creek 024 9.0
END DESCRIPTION:
XS GIS Cut Line= 3
      3846776.17      10134353.2      3846056.31     10133739.42
      3845187.64     10134962.53
#Sta/Elev= 30
  4049.1  252.57  4155.6   252.1  4241.2  248.16  4247.8  249.13  4324.5   246.4
    4496   242.9  4616.3  238.46  4808.9   233.7  4829.8  232.09  4879.2   232.1
  4893.5  230.22  4907.7  231.93  4914.3  230.57  4928.6  232.81  4950.6  231.99
  4957.1  230.59  4985.7  230.87  4988.9  229.58  5002.2  230.11  5009.4  232.03
  5236.2  230.97  5325.7  230.92  5524.9  237.45    5691  239.71  5727.7   238.6
  5818.9  237.78  6005.9  242.94  6118.5   244.6  6321.6  249.91  6495.3  251.78
#Mann= 9 ,-1 , 0
  4049.1     .12       0  4324.5     .05       0  4616.3     .12       0
  4950.6     .07       0  5009.4      .1       0  5236.2     .12       0
  5727.7      .1       0  6118.5     .12       0  6321.6     .05       0
Bank Sta=4950.6,5009.4
XS Rating Curve= 0 ,0
Exp/Cntr=0.3,0.1

Type RM Length L Ch R = 1 ,4011    ,511,511,511
BEGIN DESCRIPTION:
Crystal Creek 024 8.0
END DESCRIPTION:
XS GIS Cut Line= 3
      3846660.73     10133728.96      3845758.57     10133425.71
      3845150.02     10134644.01
#Sta/Elev= 30
  4039.4  242.39  4071.1  242.45  4168.9  241.81  4237.2  242.77  4484.1  238.76
  4615.4  241.16  4703.4  238.82  4767.1  236.73  4799.4  235.13 4964.78 230.276
  4979.4  227.82  5003.4  230.33  5008.9  229.48  5026.1  230.27  5031.3  229.35
  5053.7  230.67  5120.8  229.35  5197.6  230.38  5294.1  233.66  5348.4  234.17
  5366.8  235.51  5450.7  236.08  5517.8  235.29    5652  236.26  5657.6  235.45
  5712.6  237.12  5995.2  240.37  6031.2  240.95  6188.8  243.48    6353  244.64
#Mann= 12 ,-1 , 0
  4039.4     .12       0  4071.1     .05       0  4703.4     .12       0
  4767.1     .05       0  4799.4    .075       0 4964.78     .07       0
  5003.4    .075       0  5026.1     .05       0  5197.6     .12       0
  5348.4      .1       0  5995.2     .05       0  6031.2     .12       0
Bank Sta=4964.78,5003.4
XS Rating Curve= 0 ,0
Exp/Cntr=0.3,0.1

Type RM Length L Ch R = 1 ,3500    ,500,500,500
BEGIN DESCRIPTION:
Crystal Creek 024 7.0
END DESCRIPTION:
XS GIS Cut Line= 3
      3846540.88      10133452.9      3845471.24     10133213.03
      3845032.39     10134274.92
#Sta/Elev= 30
  3888.7  240.55  4004.5  241.63  4076.3  239.35  4250.5  240.47    4312     239
  4426.2  239.04  4464.5  235.91    4518   234.5  4670.7  232.59  4783.3  232.71
  4814.2  233.92  4855.1  231.91  4880.2  232.22  4905.4  230.15  4923.5  228.91
  4928.7  230.52  4957.6  228.26  4964.9  225.63  4968.8  225.63    4972  228.29
  5002.9   226.9  5026.1  229.57  5057.8  228.17    5245  231.57    5372  233.79
  5577.7  235.12  5772.7  238.13  5805.1   237.5  5954.8  240.01  6133.9  243.18
#Mann= 8 ,-1 , 0
  3888.7    .075       0  4905.4     .05       0  4957.6     .07       0
    4972     .05       0  5057.8    .075       0    5245     .05       0
    5372     .12       0  5954.8     .05       0
Bank Sta=4957.6,4972
XS Rating Curve= 0 ,0
Exp/Cntr=0.3,0.1

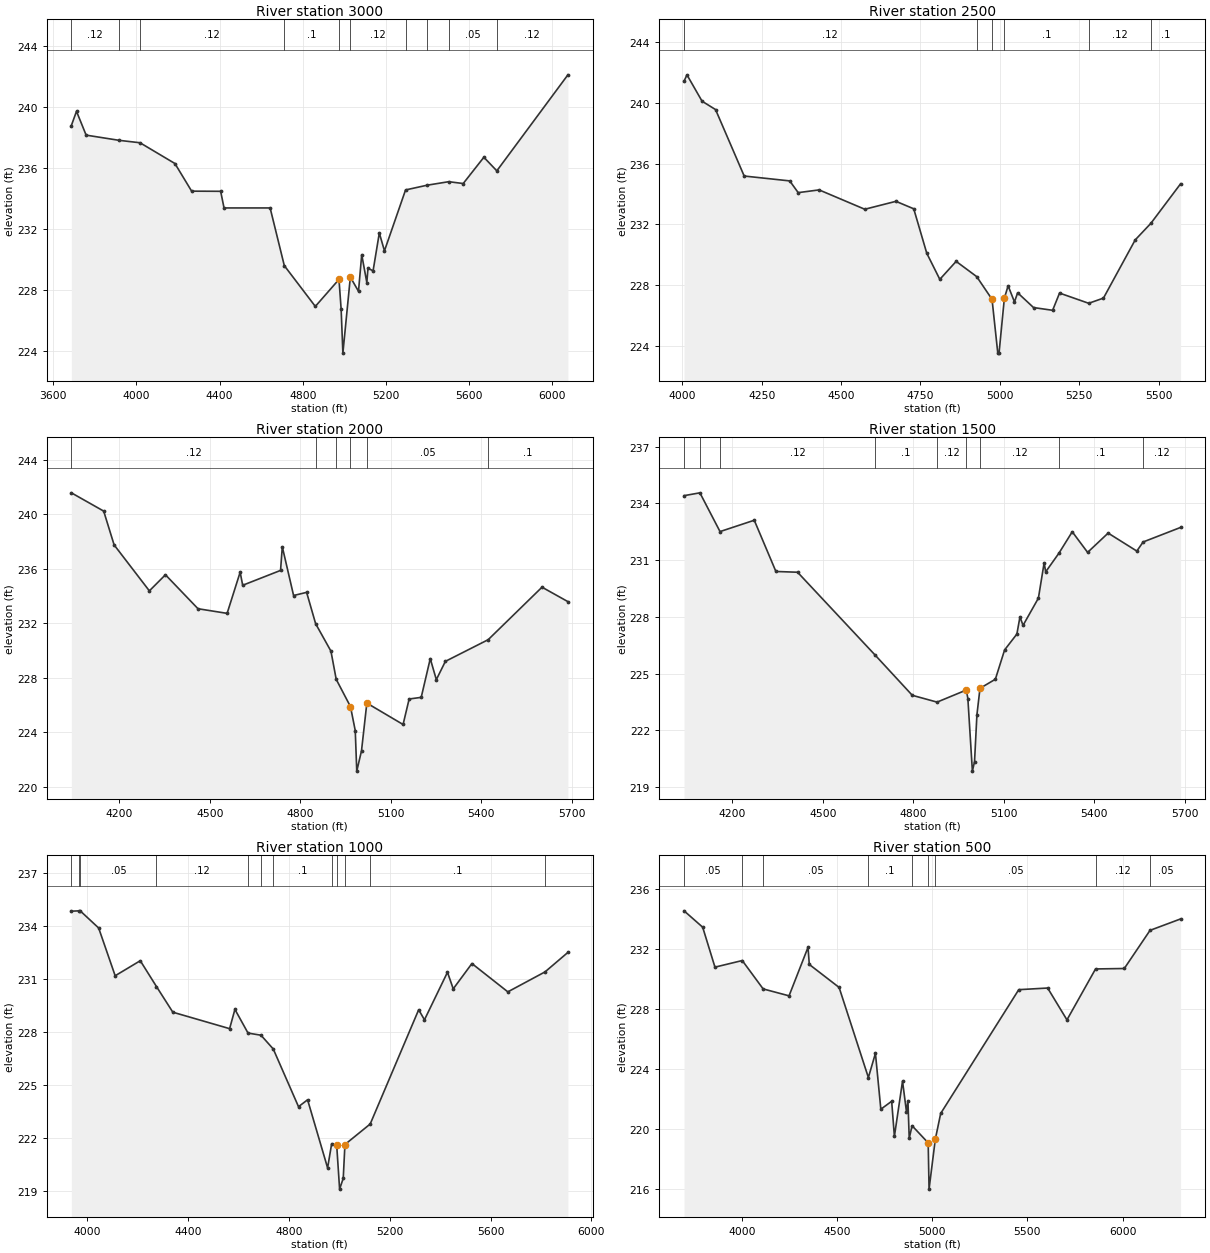
Type RM Length L Ch R = 1 ,3000    ,500,500,500
BEGIN DESCRIPTION:
Crystal Creek 024 6.0
END DESCRIPTION:
XS GIS Cut Line= 3
      3846561.74     10133234.16      3845292.39     10132898.05
      3844906.97     10133900.94
#Sta/Elev= 30
  3686.9  238.76  3711.6  239.69  3757.9  238.13    3916  237.79    4017  237.63
  4184.8  236.27  4265.2  234.46  4404.7  234.45    4421  233.36  4642.6  233.36
  4710.8  229.58  4859.9  226.91  4973.7  228.68    4984  226.73  4992.4  223.85
  5028.3  228.83  5067.5   227.9    5083   230.3  5107.6  228.47    5113  229.41
  5137.6  229.24  5167.6  231.72  5192.3  230.55  5293.8  234.54  5397.6  234.85
  5501.4  235.08    5571  234.96  5670.3  236.68  5732.6  235.79  6074.4  242.08
#Mann= 10 ,-1 , 0
  3686.9     .12       0    3916    .075       0    4017     .12       0
  4710.8      .1       0  4973.7     .07       0  5028.3     .12       0
  5293.8     .05       0  5397.6    .075       0  5501.4     .05       0
  5732.6     .12       0
Bank Sta=4973.7,5028.3
XS Rating Curve= 0 ,0
Exp/Cntr=0.3,0.1

Type RM Length L Ch R = 1 ,2500    ,500,500,500
BEGIN DESCRIPTION:
Crystal Creek 024 5.0
END DESCRIPTION:
XS GIS Cut Line= 3
      3846521.83      10132888.1      3845553.76     10132661.65
      3844985.12     10132675.27
#Sta/Elev= 30
  4005.8   241.4  4014.9  241.82  4062.5  240.09    4105  239.54  4195.1  235.18
  4338.5  234.86  4365.1  234.09    4431  234.27  4574.7     233  4672.8  233.52
  4728.8  233.03  4769.9  230.11  4810.9   228.4  4862.3  229.58    4927  228.58
  4975.3  227.09  4993.4  223.56  4997.3  223.56  5014.1 227.163  5025.9  227.98
  5045.9  226.92  5055.9  227.52  5105.9  226.55    5166  226.37  5187.8   227.5
  5279.6  226.83    5326  227.17    5426  230.99  5475.4  232.08  5568.8  234.67
#Mann= 6 ,-1 , 0
  4005.8     .12       0    4927      .1       0  4975.3     .07       0
  5014.1      .1       0  5279.6     .12       0  5475.4      .1       0
Bank Sta=4975.3,5014.1
XS Rating Curve= 0 ,0
Exp/Cntr=0.3,0.1

Type RM Length L Ch R = 1 ,2000    ,500,500,500
BEGIN DESCRIPTION:
Crystal Creek 024 4.0
END DESCRIPTION:
XS GIS Cut Line= 3
      3846540.87     10132812.26      3845708.35     10132336.64
      3845022.17     10132367.95
#Sta/Elev= 30
  4041.2  241.56  4148.3  240.22  4182.9  237.74  4299.7  234.37    4353  235.55
  4460.9  233.06  4557.4  232.72  4600.6  235.74    4609  234.78  4734.5  235.87
  4740.3   237.6  4777.7  234.03  4820.9  234.26  4850.8  231.96  4901.5  229.95
    4919  227.88  4966.3  225.88  4982.1  224.12  4987.1  221.15  5002.8  222.64
  5020.5  226.14  5140.6  224.57  5160.7  226.44  5200.7  226.56  5230.7   229.4
  5250.8  227.86  5280.8   229.2  5422.7  230.79  5601.1  234.64  5686.9  233.58
#Mann= 6 ,-1 , 0
  4041.2     .12       0  4850.8      .1       0    4919     .05       0
  4966.3     .07       0  5020.5     .05       0  5422.7      .1       0
Bank Sta=4966.3,5020.5
XS Rating Curve= 0 ,0
Exp/Cntr=0.3,0.1

Type RM Length L Ch R = 1 ,1500    ,500,500,500
BEGIN DESCRIPTION:
Crystal Creek 024 3.0
END DESCRIPTION:
XS GIS Cut Line= 3
      3846514.91     10132119.59      3845578.37     10131910.92
      3844905.51     10132041.45
#Sta/Elev= 30
  4040.5  234.41    4093  234.56  4159.7  232.51  4273.1  233.11  4344.8   230.4
  4416.6  230.36  4673.4  225.98  4796.6  223.85  4878.7  223.49  4975.6  224.13
  4980.7  223.68  4995.7  219.84  5002.8  220.34  5010.7  222.82  5020.9  224.22
  5071.8   224.7  5102.4  226.25  5143.1  227.09  5153.3     228  5163.5  227.55
  5214.4  228.99  5233.4  230.86  5238.5  230.38  5282.5  231.37  5326.5   232.5
  5377.4  231.41  5445.4  232.43  5540.4  231.48  5561.3  231.96  5685.4  232.73
#Mann= 9 ,-1 , 0
  4040.5     .12       0    4093     .05       0  4159.7     .12       0
  4673.4      .1       0  4878.7     .12       0  4975.6     .07       0
  5020.9     .12       0  5282.5      .1       0  5561.3     .12       0
Bank Sta=4975.6,5020.9
XS Rating Curve= 0 ,0
Exp/Cntr=0.3,0.1

Type RM Length L Ch R = 1 ,1000    ,500,500,500
BEGIN DESCRIPTION:
Crystal Creek 024 2.0
END DESCRIPTION:
XS GIS Cut Line= 3
      3846572.19     10132046.68      3845679.28     10131448.74
      3844869.03     10131827.91
#Sta/Elev= 30
  3937.6  234.84  3969.1  234.86  3973.3  234.85  4045.8  233.89  4111.3  231.19
  4210.9  232.04  4275.1  230.58    4340  229.13  4565.2   228.2  4586.2  229.29
  4638.2  227.95  4689.5  227.83  4738.3  227.05  4838.4  223.79  4874.4  224.18
  4953.8  220.33  4969.9   221.7  4989.9   221.6  5001.4  219.13  5015.8  219.74
 5022.51 221.652  5122.7  222.81    5315  229.27  5337.9   228.7  5429.2  231.39
    5452  230.45  5526.1  231.88  5668.6  230.28  5816.2  231.41  5906.8  232.51
#Mann= 12 ,-1 , 0
  3937.6     .05       0  3969.1     .12       0  3973.3     .05       0
  4275.1     .12       0  4638.2      .1       0  4689.5     .12       0
  4738.3      .1       0  4969.9     .12       0  4989.9     .07       0
 5022.51     .12       0  5122.7      .1       0  5816.2     .12       0
Bank Sta=4989.9,5022.51
XS Rating Curve= 0 ,0
Exp/Cntr=0.3,0.1

Type RM Length L Ch R = 1 ,500     ,0,0,0
BEGIN DESCRIPTION:
Crystal Creek 024 1.0
END DESCRIPTION:
XS GIS Cut Line= 3
       3846613.8     10131973.71      3845752.45     10130996.15
       3844582.7     10131572.64
#Sta/Elev= 30
  3697.1  234.54  3794.9  233.45  3859.4  230.79  4002.8  231.23  4112.4  229.34
  4248.4  228.88    4348  232.11  4354.7  230.97  4511.2  229.44  4664.9  223.44
  4701.9  225.05  4730.3  221.33  4787.2  221.86  4801.5  219.52  4844.2   223.2
    4865  221.15  4872.6   221.9  4879.3   219.4  4894.5  220.23  4978.9  219.09
  4983.5  216.01  5016.3  219.33  5044.6  221.05  5454.4  229.29  5606.1   229.4
  5707.5  227.28  5857.6  230.67  6008.5   230.7  6143.7  233.24  6304.1     234
#Mann= 9 ,-1 , 0
  3697.1     .05       0  4002.8     .12       0  4112.4     .05       0
  4664.9      .1       0  4894.5     .05       0  4978.9     .07       0
  5016.3     .05       0  5857.6     .12       0  6143.7     .05       0
Bank Sta=4978.9,5016.3
XS Rating Curve= 0 ,0
Exp/Cntr=0.3,0.1