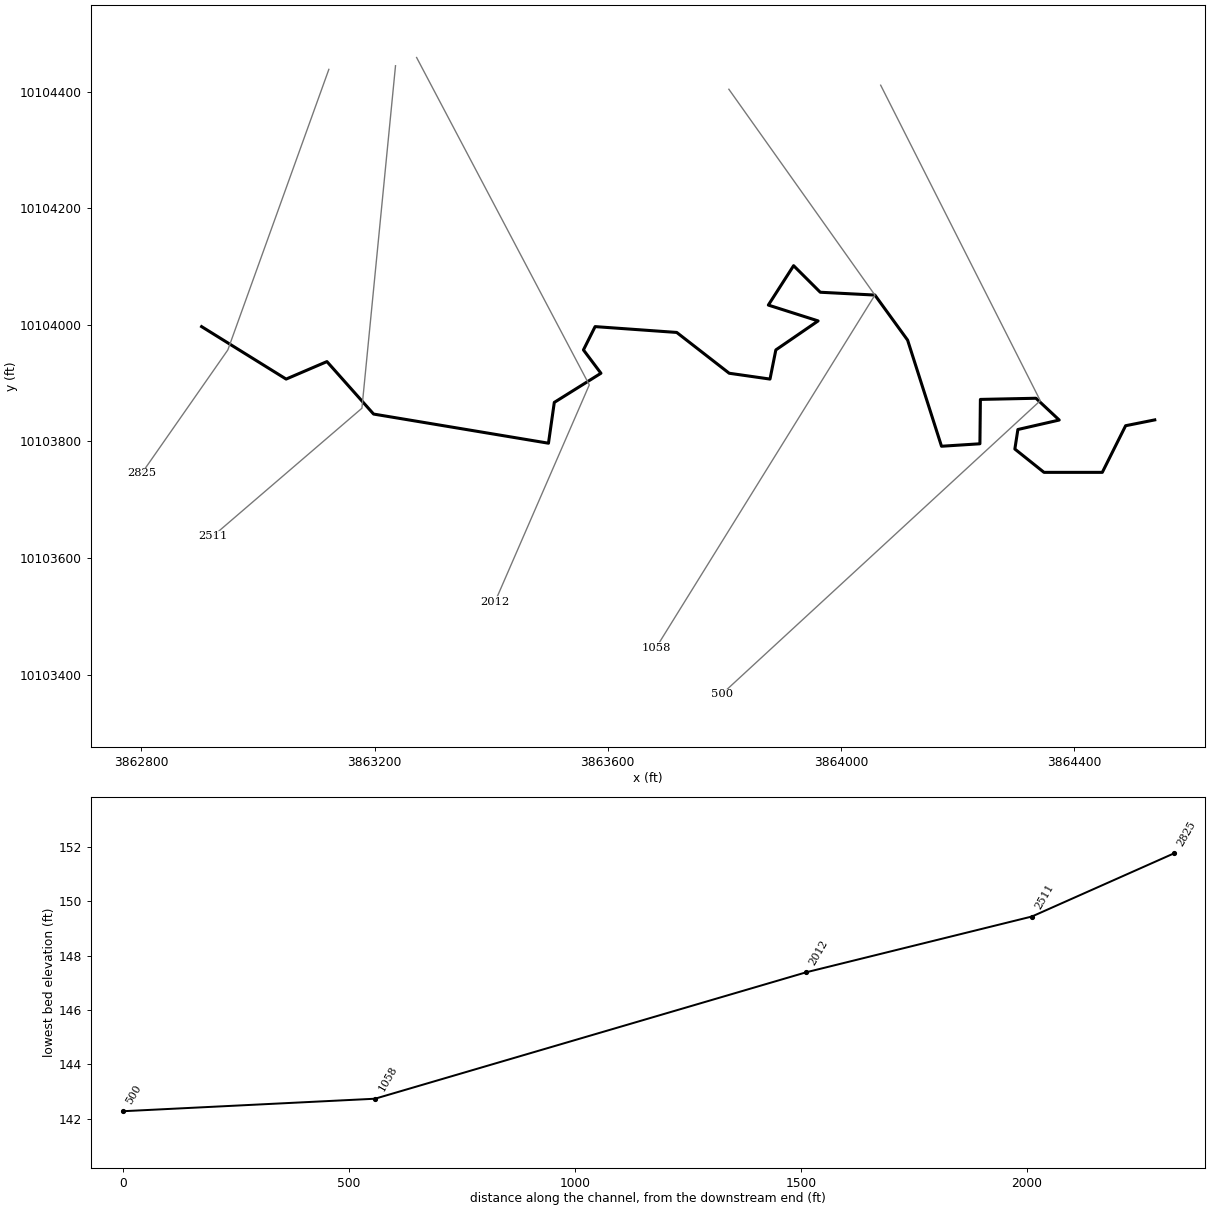
--- Crystal Creek 027.prj (project) ---

Proj Title=Crystal Creek 027 Base Level Engineering
Current Plan=p01
Default Exp/Contr=0.3,0.1
English Units
Geom File=g01
Flow File=f01
Flow File=f02
Plan File=p01
Y Axis Title=Elevation
X Axis Title(PF)=Main Channel Distance
X Axis Title(XS)=Station
BEGIN DESCRIPTION:
Crystal Creek 027
END DESCRIPTION:
DSS Export Rating Curves= 0
DSS Export Rating Curve Sorted= 0
DSS Export Volume Flow Curves= 0
DXF OffsetX= 0
DXF OffsetY= 0
DXF ScaleX= 1
DXF ScaleY= 10

--- Crystal Creek 027.p01 (plan) ---

Plan Title=Multiple Run
Short Identifier=Multiple
Geom File=g01
Flow File=f01
Subcritical Flow
K Sum by GR= 0
Std Step Tol= 0.01
Critical Tol= 0.01
Num of Std Step Trials= 20
Max Error Tol= 0.3
Flow Tol Ratio= 0.001
Split Flow NTrial= 30
Split Flow Tol= 0.02
Split Flow Ratio= 0.02
Log Output Level= 0
Friction Slope Method= 1
Unsteady Friction Slope Method= 2
Unsteady Bridges Friction Slope Method= 1
Parabolic Critical Depth
Global Vel Dist=  1 , 1 , 1
Global Log Level= 0
CheckData=True
Encroach Param= -1, 0, 0, 0
BEGIN DESCRIPTION:
Multiple Run
END DESCRIPTION:

--- Crystal Creek 027.f01 (steady flow) ---

Flow Title=Multiple
Program Version=4.10
Number of Profiles= 7
Profile Names=10-year,25-year,50-year,1pct_min,100-year,1pct_plu,500-year
River Rch & RM=Crystal Creek 02,Reach-1         ,2825
     501     663     883     387    1170    3533    2119
Boundary for River Rch & Prof#=Crystal Creek 02,Reach-1         , 1
Up Type= 0
Dn Type= 3
Dn Slope=0.005
Boundary for River Rch & Prof#=Crystal Creek 02,Reach-1         , 2
Up Type= 0
Dn Type= 3
Dn Slope=0.005
Boundary for River Rch & Prof#=Crystal Creek 02,Reach-1         , 3
Up Type= 0
Dn Type= 3
Dn Slope=0.005
Boundary for River Rch & Prof#=Crystal Creek 02,Reach-1         , 4
Up Type= 0
Dn Type= 3
Dn Slope=0.005
Boundary for River Rch & Prof#=Crystal Creek 02,Reach-1         , 5
Up Type= 0
Dn Type= 3
Dn Slope=0.005
Boundary for River Rch & Prof#=Crystal Creek 02,Reach-1         , 6
Up Type= 0
Dn Type= 3
Dn Slope=0.005
Boundary for River Rch & Prof#=Crystal Creek 02,Reach-1         , 7
Up Type= 0
Dn Type= 3
Dn Slope=0.005
DSS Import GetInterval= 0
DSS Import GetPeak= 0
DSS Import FillOption= 0

--- Crystal Creek 027.f02 (steady flow) ---

Flow Title=Orig_BLE_Flow
Program Version=4.10
Number of Profiles= 7
Profile Names=10-year,25-year,50-year,1pct_min,100-year,1pct_plu,500-year
River Rch & RM=Crystal Creek 02,Reach-1         ,2825
     501     650     768     298     900    2718    1232
Boundary for River Rch & Prof#=Crystal Creek 02,Reach-1         , 1
Up Type= 0
Dn Type= 3
Dn Slope=0.005
Boundary for River Rch & Prof#=Crystal Creek 02,Reach-1         , 2
Up Type= 0
Dn Type= 3
Dn Slope=0.005
Boundary for River Rch & Prof#=Crystal Creek 02,Reach-1         , 3
Up Type= 0
Dn Type= 3
Dn Slope=0.005
Boundary for River Rch & Prof#=Crystal Creek 02,Reach-1         , 4
Up Type= 0
Dn Type= 3
Dn Slope=0.005
Boundary for River Rch & Prof#=Crystal Creek 02,Reach-1         , 5
Up Type= 0
Dn Type= 3
Dn Slope=0.005
Boundary for River Rch & Prof#=Crystal Creek 02,Reach-1         , 6
Up Type= 0
Dn Type= 3
Dn Slope=0.005
Boundary for River Rch & Prof#=Crystal Creek 02,Reach-1         , 7
Up Type= 0
Dn Type= 3
Dn Slope=0.005
DSS Import GetInterval= 0
DSS Import GetPeak= 0
DSS Import FillOption= 0

--- Crystal Creek 027.g01 (geometry) ---

Geom Title=Existing Conditions
Program Version=4.10

River Reach=Crystal Creek 02,Reach-1
Reach XY= 30
      3862903.24     10103996.86      3863048.24     10103906.86
      3863118.24     10103936.86      3863198.24     10103846.86
      3863498.24     10103796.86      3863508.24     10103866.86
      3863588.24     10103916.86      3863558.24     10103956.86
      3863578.24     10103996.86      3863718.24     10103986.86
      3863808.24     10103916.86      3863878.24     10103906.86
      3863888.24     10103956.86      3863960.78     10104006.65
      3863875.39     10104033.79      3863918.72     10104101.39
      3863964.45     10104055.81      3864058.18     10104050.97
      3864114.27     10103973.68      3864172.44     10103791.65
      3864238.31     10103795.87      3864239.13     10103871.98
      3864334.45     10103873.96      3864374.36     10103836.61
      3864303.43     10103820.36      3864298.24     10103786.86
      3864348.24     10103746.86      3864448.24     10103746.86
      3864488.24     10103826.86      3864538.24     10103836.86

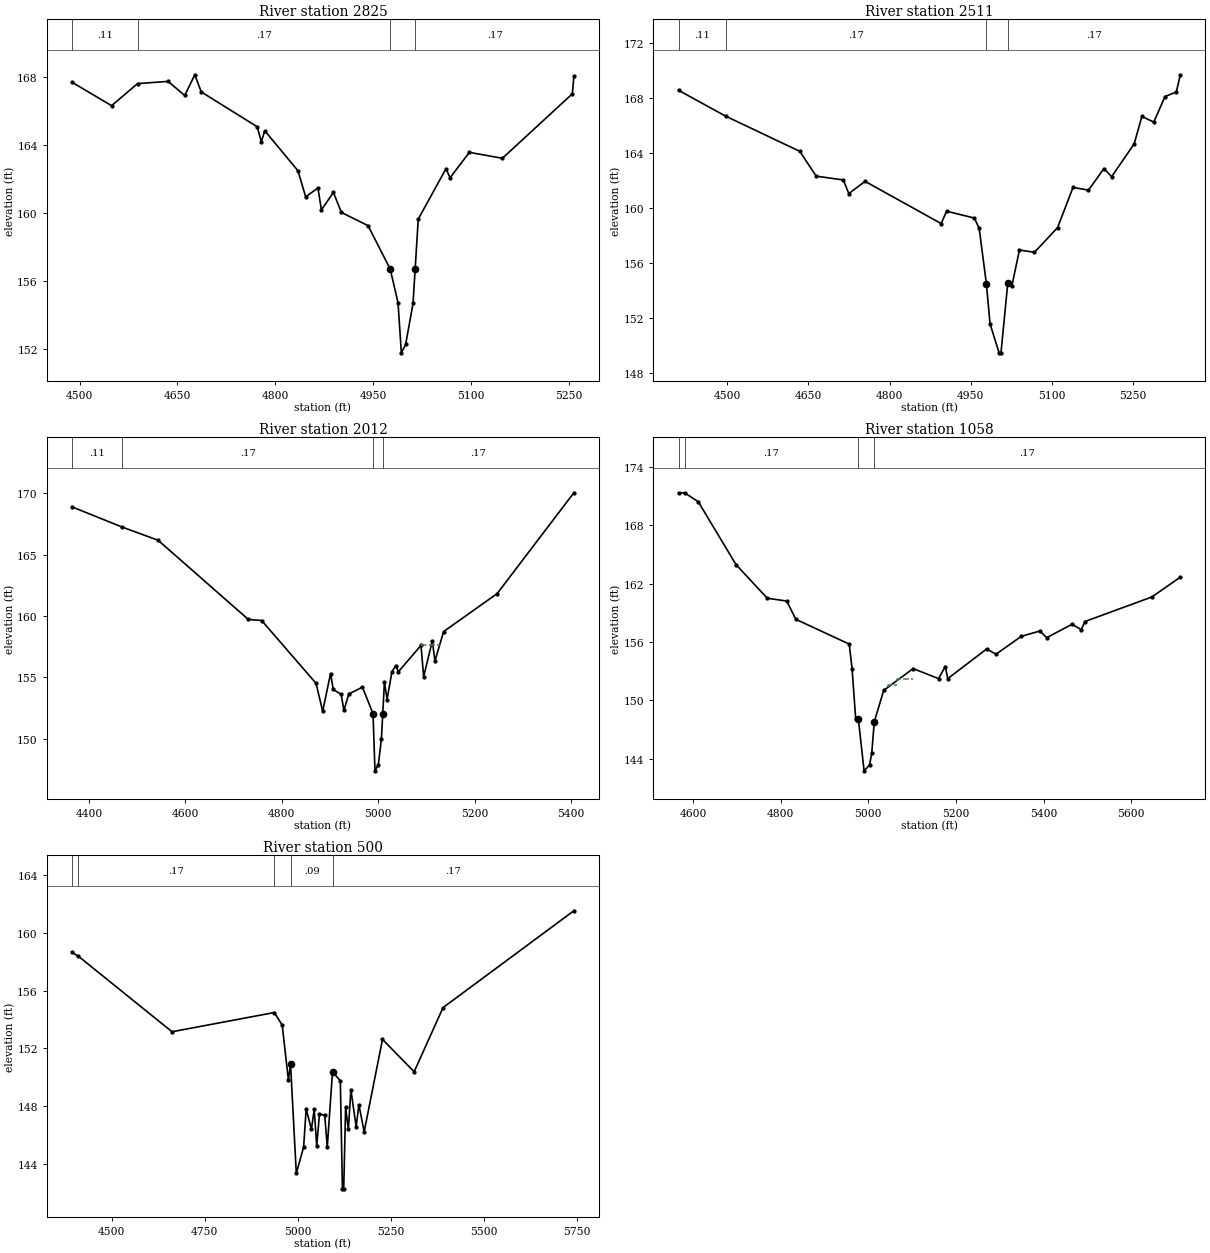
Type RM Length L Ch R = 1 ,2825    ,314,314,314
BEGIN DESCRIPTION:
Crystal Creek 027 4.0
END DESCRIPTION:
XS GIS Cut Line= 3
      3863121.52     10104438.12      3862948.24     10103956.86
      3862800.69     10103745.34
#Sta/Elev= 30
  4488.5   167.7  4549.1  166.32  4588.9  167.62  4635.8  167.75  4661.2  166.92
  4676.7  168.14  4686.6  167.13  4772.3  165.08  4778.7   164.2    4784  164.84
  4834.8  162.49  4846.7  160.95  4865.5  161.47  4870.8  160.18  4889.2  161.21
  4901.5  160.03  4942.4  159.25 4976.33156.6906  4988.3  154.71  4993.4  151.76
    5000  152.26  5011.3  154.67 5014.59156.7139  5019.3  159.64  5061.9  162.61
    5068  162.07  5097.7  163.57  5148.3  163.22  5255.6  167.02  5257.9  168.04
#Mann= 4 ,-1 , 0
  4488.5     .11       0  4588.9     .17       0 4976.33     .09       0
 5014.59     .17       0
Bank Sta=4976.33,5014.59
XS Rating Curve= 0 ,0
Exp/Cntr=0.3,0.1

Type RM Length L Ch R = 1 ,2511    ,499,499,499
BEGIN DESCRIPTION:
Mapping XS 258d8b98
END DESCRIPTION:
XS GIS Cut Line= 3
      3863235.87     10104444.34      3863178.24     10103856.86
      3862922.18     10103636.99
#Sta/Elev= 30
  4409.7  168.53  4496.9  166.65    4634  164.09  4664.2  162.29  4714.4  162.01
  4724.5  161.02  4754.6  161.91  4895.3  158.84  4905.3  159.74  4956.7  159.24
  4965.6  158.49    4979154.4345  4985.7  151.54  5002.4  149.44  5005.9  149.44
  5018.4  154.49  5026.1  154.31    5040  156.92  5067.8  156.75  5110.6  158.55
  5139.1  161.47  5167.7  161.27  5196.2  162.84  5210.5  162.25  5252.2  164.64
  5266.4  166.63  5288.4  166.22  5309.2  168.08  5330.1  168.41  5337.5  169.66
#Mann= 4 ,-1 , 0
  4409.7     .11       0  4496.9     .17       0    4979     .09       0
  5018.4     .17       0
Bank Sta=4979,5018.4
XS Rating Curve= 0 ,0
Exp/Cntr=0.3,0.1

Type RM Length L Ch R = 1 ,2012    ,954,954,954
BEGIN DESCRIPTION:
Crystal Creek 027 3.0
END DESCRIPTION:
XS GIS Cut Line= 3
      3863272.05     10104458.44      3863568.24     10103896.86
      3863406.69     10103525.15
#Sta/Elev= 30
  4365.1   168.9  4468.6  167.26  4543.5  166.18  4730.4  159.73  4758.1  159.64
  4870.9  154.52  4884.6  152.24  4900.9  155.32  4906.6  154.02    4923  153.62
  4928.6  152.31  4938.7  153.65    4967  154.21    4989  152.04    4993  147.39
    5000  147.89  5006.3  149.96  5009.1152.0312  5012.6  154.62  5018.1   153.2
  5028.1  155.45  5036.1  155.97  5041.5  155.46  5088.4  157.61  5093.9  155.07
  5111.9  157.97  5117.3  156.34  5135.3  158.74  5246.2  161.83  5405.3  170.05
#Mann= 4 ,-1 , 0
  4365.1     .11       0  4468.6     .17       0    4989     .09       0
  5009.1     .17       0
#XS Ineff= 3 ,-1
  4900.9  4818.5  155.32  5036.1  5088.4  155.97  5088.4  5126.3  157.61
Permanent Ineff=
       F       F       F
Bank Sta=4989,5009.1
XS Rating Curve= 0 ,0
Exp/Cntr=0.3,0.1

Type RM Length L Ch R = 1 ,1058    ,558,558,558
BEGIN DESCRIPTION:
Crystal Creek 027 2.0
END DESCRIPTION:
XS GIS Cut Line= 3
      3863807.66     10104404.02      3864058.18     10104050.97
      3863682.74     10103445.88
#Sta/Elev= 30
  4567.1  171.33  4580.8  171.35  4612.1  170.43  4698.2  163.96  4769.6   160.5
  4813.9  160.21  4834.8  158.33  4956.6  155.78  4963.1  153.26  4971.4  148.05
  4977.5  148.05  4990.5  142.74  5002.9  143.34  5007.9  144.53  5013.8   147.8
  5035.2  151.01  5102.4  153.26  5160.3  152.23  5175.7  153.47  5181.5  152.23
  5270.2  155.28  5291.4  154.74  5349.3  156.58  5391.8  157.13  5407.2  156.44
    5465  157.82  5486.3  157.26  5494.2   158.1  5647.2  160.63  5712.1  162.67
#Mann= 4 ,-1 , 0
  4567.1     .11       0  4580.8     .17       0  4977.5     .09       0
  5013.8     .17       0
#XS Ineff= 2 ,-1
  5044.6  5065.8  151.57  5065.8  5102.4  152.23
Permanent Ineff=
       F       F
Bank Sta=4977.5,5013.8
XS Rating Curve= 0 ,0
Exp/Cntr=0.3,0.1

Type RM Length L Ch R = 1 ,500     ,0,0,0
BEGIN DESCRIPTION:
Crystal Creek 027 1.0
END DESCRIPTION:
XS GIS Cut Line= 3
      3864068.07     10104410.97      3864341.86     10103869.78
      3863795.57     10103366.34
#Sta/Elev= 30
  4393.5  158.64  4410.7  158.37  4662.3  153.15  4937.4  154.48  4958.6  153.61
  4975.3   149.8  4980.9  150.93  4996.5  143.35  5016.2  145.17    5023   147.8
  5037.2   146.4  5044.6  147.78  5051.4  145.24  5058.8  147.47    5073  147.36
  5079.8  145.17  5093.9  150.39  5114.9  149.75  5120.5  142.28    5124  142.28
  5129.1  147.91  5136.5   146.4  5143.3  149.15  5157.4  146.57  5164.8   148.1
    5179  146.23  5228.3  152.62  5313.4  150.38  5391.1  154.82  5742.9  161.52
#Mann= 5 ,-1 , 0
  4393.5     .11       0  4410.7     .17       0  4937.4     .15       0
  4980.9     .09       0  5093.9     .17       0
#XS Ineff= 2 , 0
       0  4980.9  150.93  5093.9       0  150.39
Permanent Ineff=
       F       F
Bank Sta=4980.9,5093.9
XS Rating Curve= 0 ,0
Exp/Cntr=0.3,0.1

Chan Stop Cuts=-1
Use User Specified Reach Order=0
Composite Channel Slope=5

--- Crystal Creek 027.g10 (geometry) ---

Geom Title=Existing Conditions
Program Version=4.10

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
River Reach=Crystal Creek 02,Reach-1

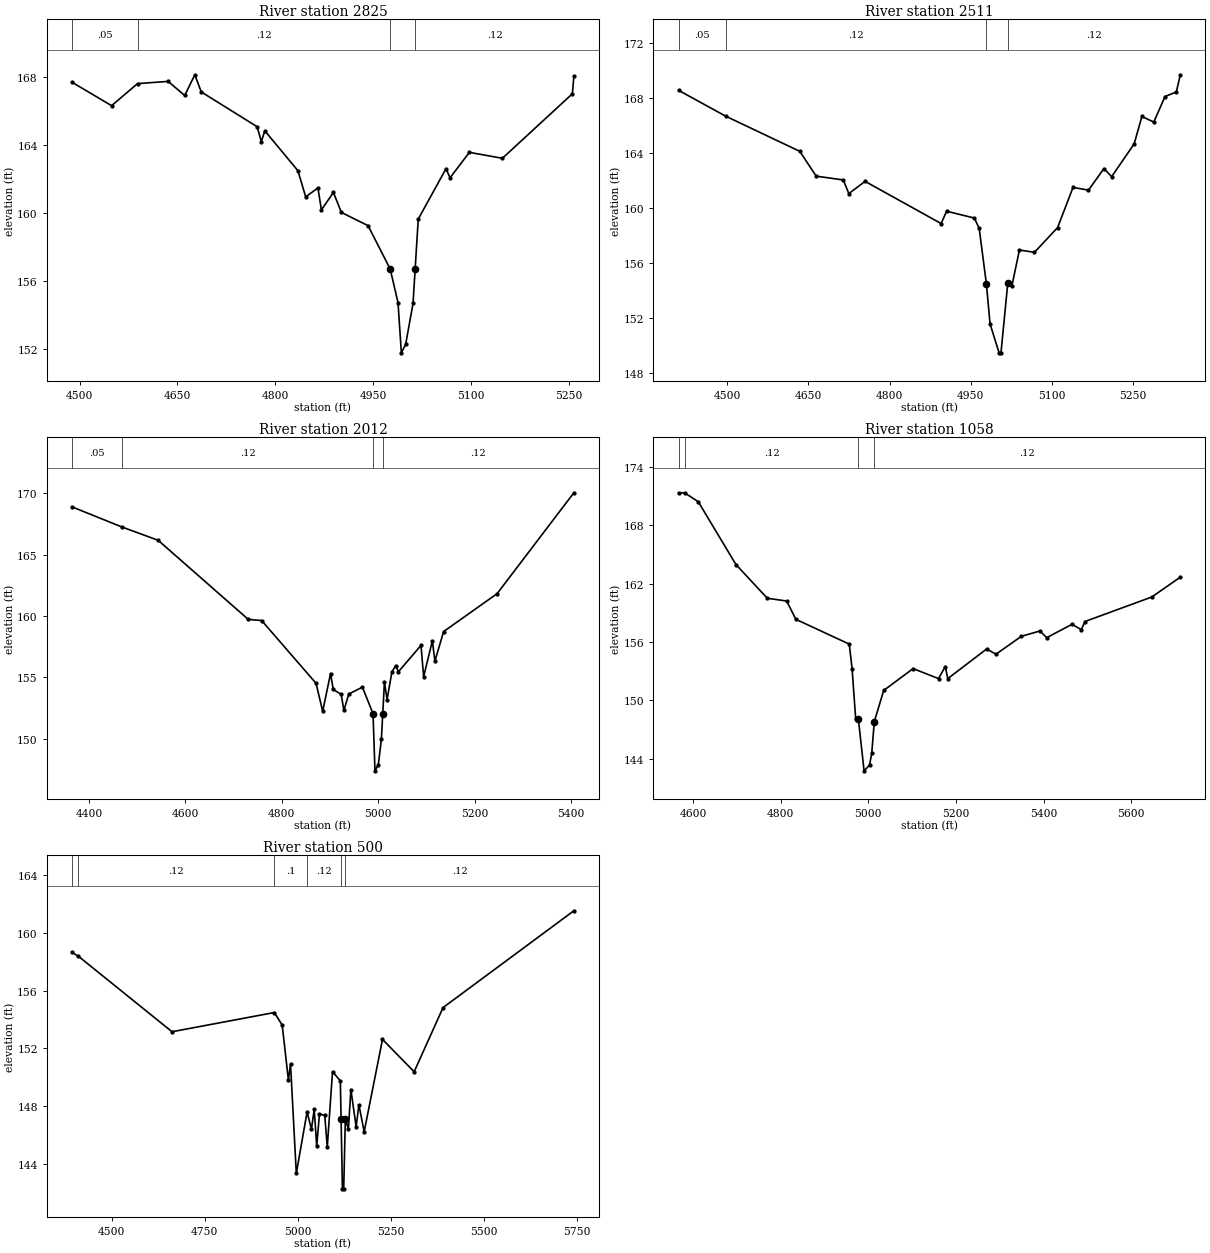
Type RM Length L Ch R = 1 ,2825    ,314,314,314
BEGIN DESCRIPTION:
Crystal Creek 027 4.0
END DESCRIPTION:
XS GIS Cut Line= 3
      3863121.52     10104438.12      3862948.24     10103956.86
      3862800.69     10103745.34
#Sta/Elev= 30
  4488.5   167.7  4549.1  166.32  4588.9  167.62  4635.8  167.75  4661.2  166.92
  4676.7  168.14  4686.6  167.13  4772.3  165.08  4778.7   164.2    4784  164.84
  4834.8  162.49  4846.7  160.95  4865.5  161.47  4870.8  160.18  4889.2  161.21
  4901.5  160.03  4942.4  159.25 4976.33 156.691  4988.3  154.71  4993.4  151.76
    5000  152.26  5011.3  154.67 5014.59 156.714  5019.3  159.64  5061.9  162.61
    5068  162.07  5097.7  163.57  5148.3  163.22  5255.6  167.02  5257.9  168.04
#Mann= 4 ,-1 , 0
  4488.5     .05       0  4588.9     .12       0 4976.33     .07       0
 5014.59     .12       0
Bank Sta=4976.33,5014.59
XS Rating Curve= 0 ,0
Exp/Cntr=0.3,0.1

Type RM Length L Ch R = 1 ,2511    ,499,499,499
BEGIN DESCRIPTION:
Mapping XS 258d8b98
END DESCRIPTION:
XS GIS Cut Line= 3
      3863235.87     10104444.34      3863178.24     10103856.86
      3862922.18     10103636.99
#Sta/Elev= 30
  4409.7  168.53  4496.9  166.65    4634  164.09  4664.2  162.29  4714.4  162.01
  4724.5  161.02  4754.6  161.91  4895.3  158.84  4905.3  159.74  4956.7  159.24
  4965.6  158.49    4979 154.435  4985.7  151.54  5002.4  149.44  5005.9  149.44
  5018.4  154.49  5026.1  154.31    5040  156.92  5067.8  156.75  5110.6  158.55
  5139.1  161.47  5167.7  161.27  5196.2  162.84  5210.5  162.25  5252.2  164.64
  5266.4  166.63  5288.4  166.22  5309.2  168.08  5330.1  168.41  5337.5  169.66
#Mann= 4 ,-1 , 0
  4409.7     .05       0  4496.9     .12       0    4979     .07       0
  5018.4     .12       0
Bank Sta=4979,5018.4
XS Rating Curve= 0 ,0
Exp/Cntr=0.3,0.1

Type RM Length L Ch R = 1 ,2012    ,954,954,954
BEGIN DESCRIPTION:
Crystal Creek 027 3.0
END DESCRIPTION:
XS GIS Cut Line= 3
      3863272.05     10104458.44      3863568.24     10103896.86
      3863406.69     10103525.15
#Sta/Elev= 30
  4365.1   168.9  4468.6  167.26  4543.5  166.18  4730.4  159.73  4758.1  159.64
  4870.9  154.52  4884.6  152.24  4900.9  155.32  4906.6  154.02    4923  153.62
  4928.6  152.31  4938.7  153.65    4967  154.21    4989  152.04    4993  147.39
    5000  147.89  5006.3  149.96  5009.1 152.031  5012.6  154.62  5018.1   153.2
  5028.1  155.45  5036.1  155.97  5041.5  155.46  5088.4  157.61  5093.9  155.07
  5111.9  157.97  5117.3  156.34  5135.3  158.74  5246.2  161.83  5405.3  170.05
#Mann= 4 ,-1 , 0
  4365.1     .05       0  4468.6     .12       0    4989     .07       0
  5009.1     .12       0
Bank Sta=4989,5009.1
XS Rating Curve= 0 ,0
Exp/Cntr=0.3,0.1

Type RM Length L Ch R = 1 ,1058    ,558,558,558
BEGIN DESCRIPTION:
Crystal Creek 027 2.0
END DESCRIPTION:
XS GIS Cut Line= 3
      3863807.66     10104404.02      3864058.18     10104050.97
      3863682.74     10103445.88
#Sta/Elev= 30
  4567.1  171.33  4580.8  171.35  4612.1  170.43  4698.2  163.96  4769.6   160.5
  4813.9  160.21  4834.8  158.33  4956.6  155.78  4963.1  153.26  4971.4  148.05
  4977.5  148.05  4990.5  142.74  5002.9  143.34  5007.9  144.53  5013.8   147.8
  5035.2  151.01  5102.4  153.26  5160.3  152.23  5175.7  153.47  5181.5  152.23
  5270.2  155.28  5291.4  154.74  5349.3  156.58  5391.8  157.13  5407.2  156.44
    5465  157.82  5486.3  157.26  5494.2   158.1  5647.2  160.63  5712.1  162.67
#Mann= 4 ,-1 , 0
  4567.1     .05       0  4580.8     .12       0  4977.5     .07       0
  5013.8     .12       0
Bank Sta=4977.5,5013.8
XS Rating Curve= 0 ,0
Exp/Cntr=0.3,0.1

Type RM Length L Ch R = 1 ,500     ,0,0,0
BEGIN DESCRIPTION:
Crystal Creek 027 1.0
END DESCRIPTION:
XS GIS Cut Line= 3
      3864068.07     10104410.97      3864341.86     10103869.78
      3863795.57     10103366.34
#Sta/Elev= 30
  4393.5  158.64  4410.7  158.37  4662.3  153.15  4937.4  154.48  4958.6  153.61
  4975.3   149.8  4980.9  150.93  4996.5  143.35  5025.5   147.6  5037.2   146.4
  5044.6  147.78  5051.4  145.24  5058.8  147.47    5073  147.36  5079.8  145.17
  5093.9  150.39  5114.9  149.75 5116.93 147.129  5120.5  142.28    5124  142.28
 5128.37  147.13  5136.5   146.4  5143.3  149.15  5157.4  146.57  5164.8   148.1
    5179  146.23  5228.3  152.62  5313.4  150.38  5391.1  154.82  5742.9  161.52
#Mann= 6 ,-1 , 0
  4393.5     .05       0  4410.7     .12       0  4937.4      .1       0
  5025.5     .12       0 5116.93     .07       0 5128.37     .12       0
Bank Sta=5116.93,5128.37
XS Rating Curve= 0 ,0
Exp/Cntr=0.3,0.1