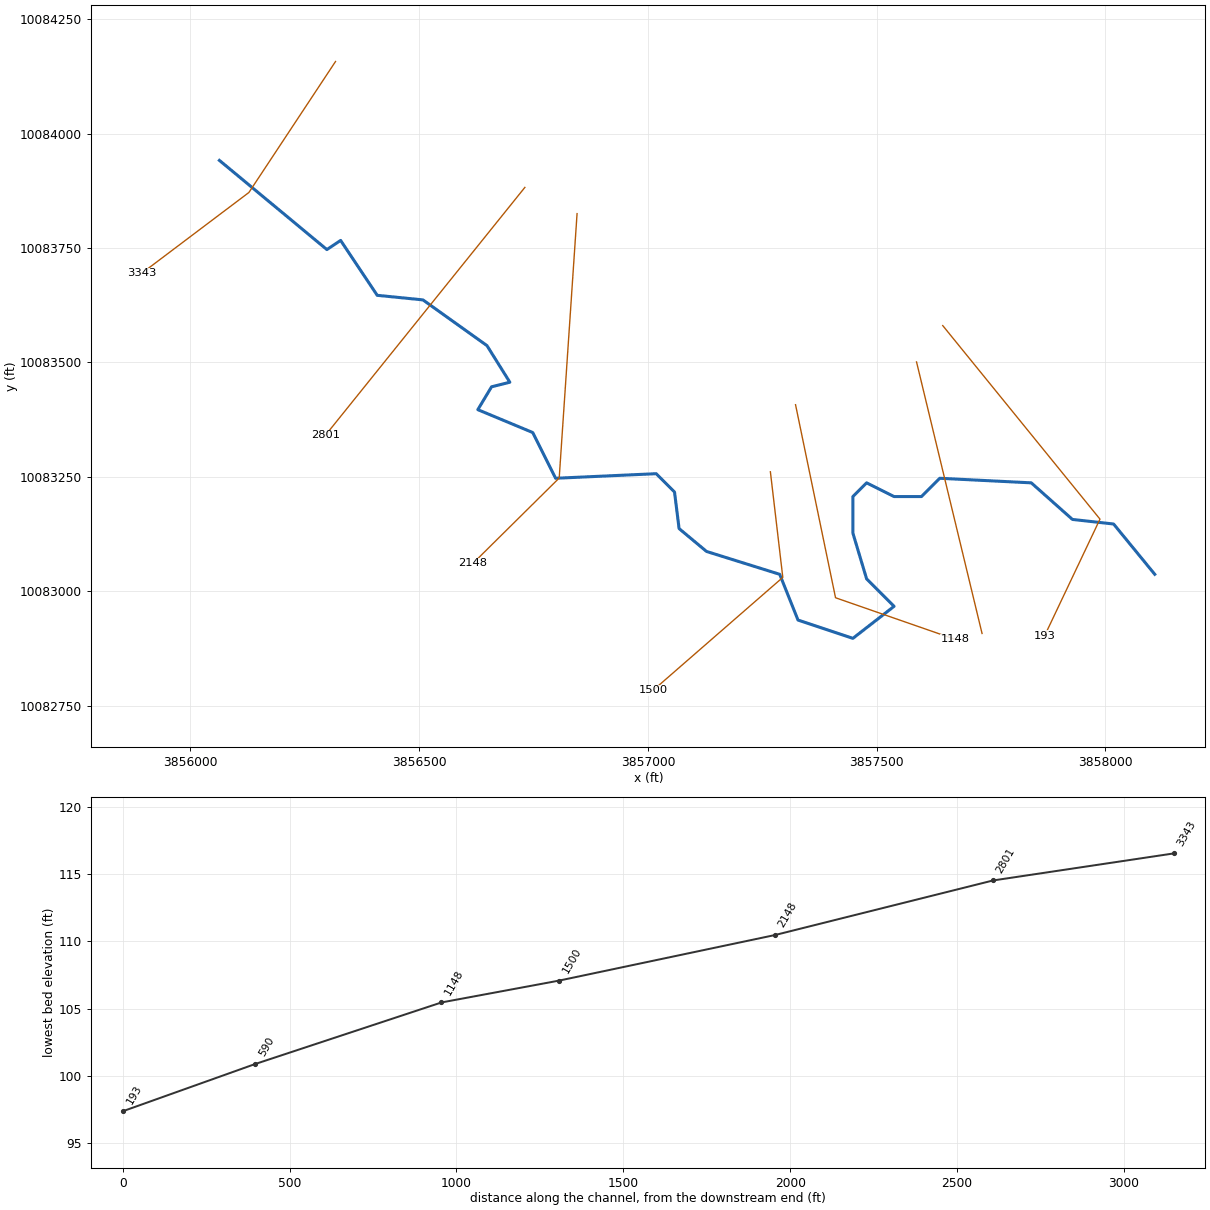
--- Crystal Creek 033.prj (project) ---

Proj Title=Crystal Creek 033 Base Level Engineering
Current Plan=p01
Default Exp/Contr=0.3,0.1
English Units
Geom File=g01
Flow File=f01
Flow File=f02
Plan File=p01
Y Axis Title=Elevation
X Axis Title(PF)=Main Channel Distance
X Axis Title(XS)=Station
BEGIN DESCRIPTION:
Crystal Creek 033
END DESCRIPTION:
DSS Export Rating Curves= 0
DSS Export Rating Curve Sorted= 0
DSS Export Volume Flow Curves= 0
DXF OffsetX= 0
DXF OffsetY= 0
DXF ScaleX= 1
DXF ScaleY= 10

--- Crystal Creek 033.p01 (plan) ---

Plan Title=Multiple Run
Short Identifier=Multiple
Geom File=g01
Flow File=f01
Subcritical Flow
K Sum by GR= 0
Std Step Tol= 0.01
Critical Tol= 0.01
Num of Std Step Trials= 20
Max Error Tol= 0.3
Flow Tol Ratio= 0.001
Split Flow NTrial= 30
Split Flow Tol= 0.02
Split Flow Ratio= 0.02
Log Output Level= 0
Friction Slope Method= 1
Unsteady Friction Slope Method= 2
Unsteady Bridges Friction Slope Method= 1
Parabolic Critical Depth
Global Vel Dist=  1 , 1 , 1
Global Log Level= 0
CheckData=True
Encroach Param= -1, 0, 0, 0
BEGIN DESCRIPTION:
Multiple Run
END DESCRIPTION:

--- Crystal Creek 033.f01 (steady flow) ---

Flow Title=Multiple
Program Version=4.10
Number of Profiles= 7
Profile Names=10-year,25-year,50-year,1pct_min,100-year,1pct_plu,500-year
River Rch & RM=Crystal Creek 03,Reach-1         ,3343
     530     700     929     406    1227    3705    2208
Boundary for River Rch & Prof#=Crystal Creek 03,Reach-1         , 1
Up Type= 0
Dn Type= 3
Dn Slope=0.009
Boundary for River Rch & Prof#=Crystal Creek 03,Reach-1         , 2
Up Type= 0
Dn Type= 3
Dn Slope=0.009
Boundary for River Rch & Prof#=Crystal Creek 03,Reach-1         , 3
Up Type= 0
Dn Type= 3
Dn Slope=0.009
Boundary for River Rch & Prof#=Crystal Creek 03,Reach-1         , 4
Up Type= 0
Dn Type= 3
Dn Slope=0.009
Boundary for River Rch & Prof#=Crystal Creek 03,Reach-1         , 5
Up Type= 0
Dn Type= 3
Dn Slope=0.009
Boundary for River Rch & Prof#=Crystal Creek 03,Reach-1         , 6
Up Type= 0
Dn Type= 3
Dn Slope=0.009
Boundary for River Rch & Prof#=Crystal Creek 03,Reach-1         , 7
Up Type= 0
Dn Type= 3
Dn Slope=0.009
DSS Import GetInterval= 0
DSS Import GetPeak= 0
DSS Import FillOption= 0

--- Crystal Creek 033.f02 (steady flow) ---

Flow Title=Orig_BLE_Flow
Program Version=4.10
Number of Profiles= 7
Profile Names=10-year,25-year,50-year,1pct_min,100-year,1pct_plu,500-year
River Rch & RM=Crystal Creek 03,Reach-1         ,3343
     530     686     808     313     944    2851    1284
Boundary for River Rch & Prof#=Crystal Creek 03,Reach-1         , 1
Up Type= 0
Dn Type= 3
Dn Slope=0.009
Boundary for River Rch & Prof#=Crystal Creek 03,Reach-1         , 2
Up Type= 0
Dn Type= 3
Dn Slope=0.009
Boundary for River Rch & Prof#=Crystal Creek 03,Reach-1         , 3
Up Type= 0
Dn Type= 3
Dn Slope=0.009
Boundary for River Rch & Prof#=Crystal Creek 03,Reach-1         , 4
Up Type= 0
Dn Type= 3
Dn Slope=0.009
Boundary for River Rch & Prof#=Crystal Creek 03,Reach-1         , 5
Up Type= 0
Dn Type= 3
Dn Slope=0.009
Boundary for River Rch & Prof#=Crystal Creek 03,Reach-1         , 6
Up Type= 0
Dn Type= 3
Dn Slope=0.009
Boundary for River Rch & Prof#=Crystal Creek 03,Reach-1         , 7
Up Type= 0
Dn Type= 3
Dn Slope=0.009
DSS Import GetInterval= 0
DSS Import GetPeak= 0
DSS Import FillOption= 0

--- Crystal Creek 033.g01 (geometry) ---

Geom Title=Existing Conditions
Program Version=4.10

River Reach=Crystal Creek 03,Reach-1
Reach XY= 30
      3856063.24     10083941.86      3856298.24     10083746.86
      3856328.24     10083766.86      3856408.24     10083646.86
      3856508.24     10083636.86      3856648.24     10083536.86
      3856698.24     10083456.86      3856658.24     10083446.86
      3856628.24     10083396.86      3856748.24     10083346.86
      3856798.24     10083246.86      3857018.24     10083256.86
      3857058.24     10083216.86      3857068.24     10083136.86
      3857128.24     10083086.86      3857288.24     10083036.86
      3857328.24     10082936.86      3857448.24     10082896.86
      3857538.24     10082966.86      3857478.24     10083026.86
      3857448.24     10083126.86      3857448.24     10083206.86
      3857478.24     10083236.86      3857538.24     10083206.86
      3857598.24     10083206.86      3857638.24     10083246.86
      3857838.24     10083236.86      3857928.24     10083156.86
      3858018.24     10083146.86      3858108.24     10083036.86

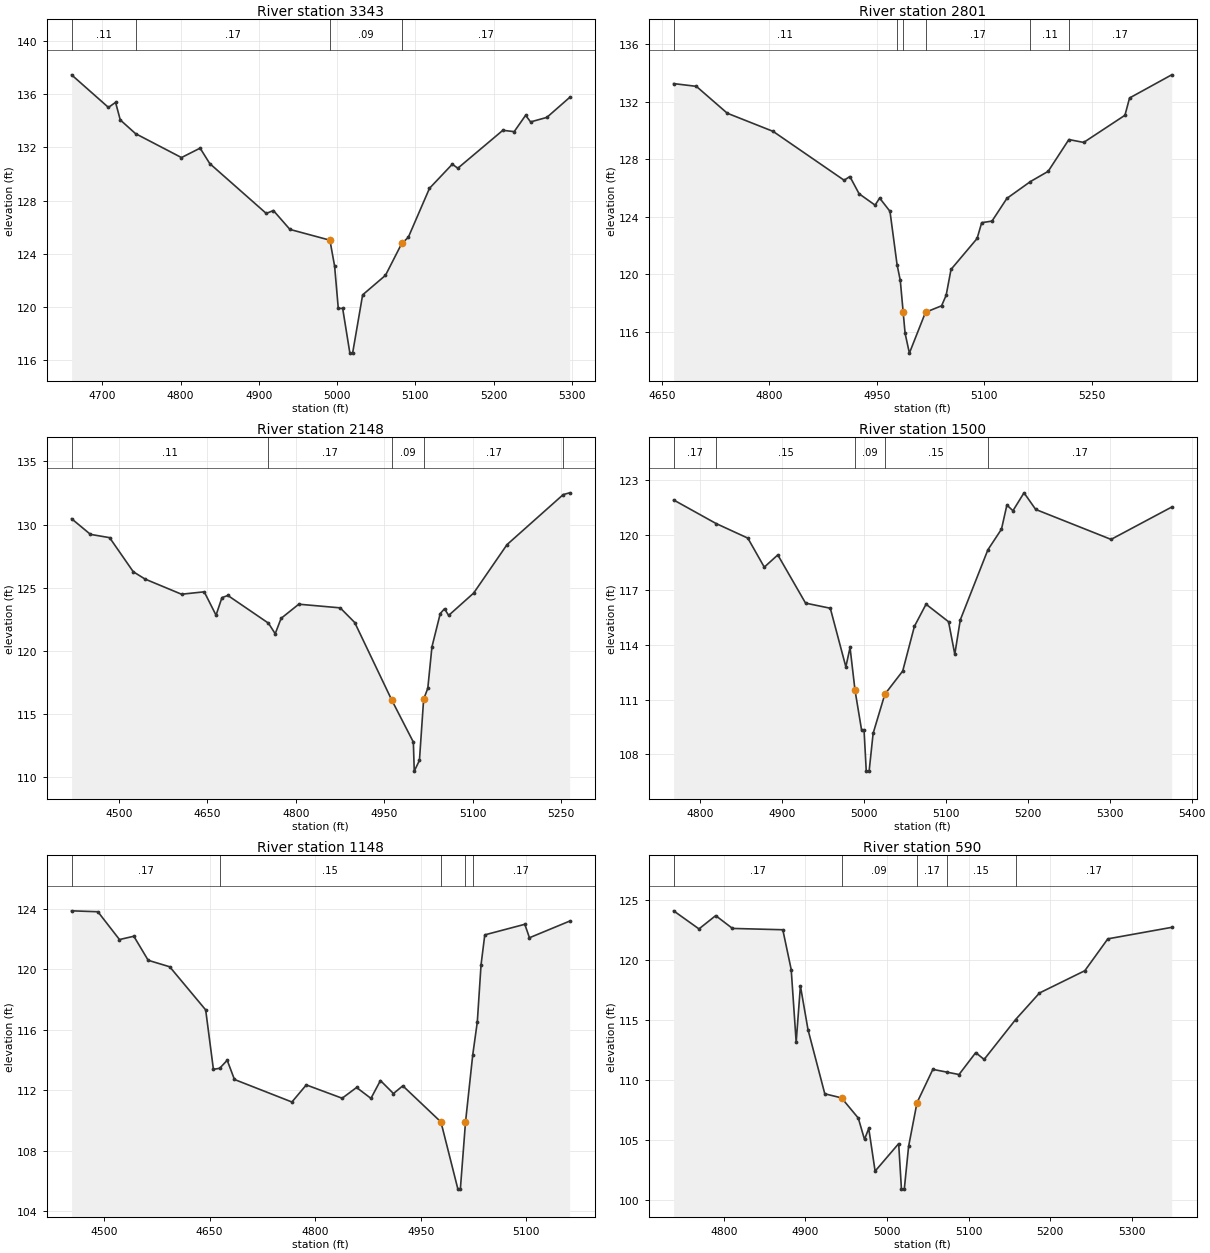
Type RM Length L Ch R = 1 ,3343    ,542,542,542
BEGIN DESCRIPTION:
Crystal Creek 033 5.0
END DESCRIPTION:
XS GIS Cut Line= 3
      3856317.09     10084158.04      3856127.74      10083871.7
      3855893.85     10083695.37
#Sta/Elev= 30
  4660.8  137.45  4707.9     135    4717  135.38    4723  134.06  4742.5  133.03
  4801.2  131.23    4825  131.94  4837.3  130.78  4909.5  127.03  4918.6  127.25
  4939.7  125.83  4990.8  125.02  4996.8  123.07  5001.5  119.89  5007.1  119.89
  5016.3  116.53  5019.8  116.53  5032.6  120.91  5061.8  122.38  5082.6  124.78
  5090.9  125.23    5118  128.92  5147.1  130.73  5154.2  130.43  5211.7  133.28
  5226.2  133.18  5240.8  134.41  5247.1  133.91  5267.9  134.25    5297  135.75
#Mann= 4 ,-1 , 0
  4660.8     .11       0  4742.5     .17       0  4990.8     .09       0
  5082.6     .17       0
Bank Sta=4990.8,5082.6
XS Rating Curve= 0 ,0
Exp/Cntr=0.3,0.1

Type RM Length L Ch R = 1 ,2801    ,653,653,653
BEGIN DESCRIPTION:
Mapping XS df28f753
END DESCRIPTION:
XS GIS Cut Line= 2
      3856731.06      10083882.8      3856295.29     10083341.12
#Sta/Elev= 30
  4666.6  133.26  4698.3  133.07  4741.5   131.2  4805.4  129.94  4904.6  126.54
  4912.6   126.8  4925.5   125.6  4947.8  124.81  4954.2   125.3  4968.6  124.38
  4978.5  120.67    4983  119.57    4987 117.379  4989.7   115.9  4995.7  114.52
  5018.2  117.36  5040.6  117.81    5047  118.54  5053.8  120.34  5090.2  122.49
  5096.6  123.59    5111   123.7  5131.8  125.28  5164.7  126.45  5189.4  127.16
  5218.3  129.37    5239  129.17  5296.6  131.06    5303  132.26  5361.8  133.87
#Mann= 6 ,-1 , 0
  4666.6     .11       0  4978.5     .17       0    4987     .09       0
  5018.2     .17       0  5164.7     .11       0  5218.3     .17       0
Bank Sta=4987,5018.2
XS Rating Curve= 0 ,0
Exp/Cntr=0.3,0.1

Type RM Length L Ch R = 1 ,2148    ,648,648,648
BEGIN DESCRIPTION:
Crystal Creek 033 4.0
END DESCRIPTION:
XS GIS Cut Line= 3
      3856845.18     10083825.44      3856806.13     10083247.36
      3856617.82     10083061.04
#Sta/Elev= 30
  4419.9  130.46  4451.9  129.22  4484.4  128.96  4524.5  126.26  4544.5  125.68
  4606.3  124.48  4644.8  124.67  4664.8  122.82  4674.8  124.21  4684.9  124.38
  4753.6  122.19  4765.1  121.35  4775.1  122.57  4805.1  123.69  4875.3   123.4
  4899.9  122.24 4962.87116.0798  4999.3  112.77  5000.8  110.47  5009.6  111.32
  5016.7  116.15  5023.8  117.04  5030.8  120.31  5044.9  122.95  5052.1  123.33
  5059.1   122.8  5101.5  124.57  5158.1  128.41  5253.3  132.37  5264.2  132.51
#Mann= 5 ,-1 , 0
  4419.9     .11       0  4753.6     .17       0 4962.87     .09       0
  5016.7     .17       0  5253.3     .11       0
Bank Sta=4962.87,5016.7
XS Rating Curve= 0 ,0
Exp/Cntr=0.3,0.1

Type RM Length L Ch R = 1 ,1500    ,352,352,352
BEGIN DESCRIPTION:
Crystal Creek 033 3.0
END DESCRIPTION:
XS GIS Cut Line= 3
      3857267.86     10083261.03      3857294.98     10083030.12
      3857011.69      10082783.5
#Sta/Elev= 30
  4767.5  121.93  4819.3  120.64  4858.1  119.84  4878.2  118.25  4894.7  118.92
  4928.6  116.28  4958.8     116  4977.8  112.79  4982.9  113.85    4989   111.5
    4997  109.33    5000  109.33  5002.7  107.08  5006.2  107.08  5011.1  109.15
  5025.4  111.29  5047.2  112.56  5061.5  115.01  5075.7  116.22  5103.2  115.26
  5110.8  113.48  5117.5  115.36  5151.2   119.2  5167.8  120.33  5174.4  121.65
  5181.8  121.34  5195.3  122.32  5209.6  121.41  5301.6  119.77  5375.6  121.54
#Mann= 5 ,-1 , 0
  4767.5     .17       0  4819.3     .15       0    4989     .09       0
  5025.4     .15       0  5151.2     .17       0
#XS Ineff= 2 , 0
       0                  5075.7       0  116.22
Permanent Ineff=
       F       F
Bank Sta=4989,5025.4
XS Rating Curve= 0 ,0
Exp/Cntr=0.3,0.1

Type RM Length L Ch R = 1 ,1148    ,558,558,558
BEGIN DESCRIPTION:
Crystal Creek 033 2.0
END DESCRIPTION:
XS GIS Cut Line= 3
      3857322.84     10083407.71      3857410.29     10082985.64
      3857671.79     10082894.71
#Sta/Elev= 30
  4453.7  123.86  4491.1   123.8  4521.8  121.96  4542.2  122.18  4562.6  120.59
  4593.2  120.16  4644.3  117.31  4655.3  113.38  4664.2  113.45  4674.9  113.98
  4685.2  112.71  4766.9  111.22  4787.3  112.35  4838.3  111.47  4858.8  112.18
  4879.2  111.46  4892.7  112.64  4911.2  111.78  4924.5  112.29  4978.7   109.9
  5002.8  105.46  5006.3  105.46 5013.59109.8775  5023.9  114.34  5030.4  116.52
  5035.7  120.29    5041  122.27  5097.9  122.97  5104.5  122.08  5161.6  123.18
#Mann= 5 ,-1 , 0
  4453.7     .17       0  4664.2     .15       0  4978.7     .09       0
 5013.59     .15       0  5023.9     .17       0
#XS Ineff= 2 , 0
       0  4674.9  113.98               0
Permanent Ineff=
       F       F
Bank Sta=4978.7,5013.59
XS Rating Curve= 0 ,0
Exp/Cntr=0.3,0.1

Type RM Length L Ch R = 1 ,590     ,397,397,397
BEGIN DESCRIPTION:
Mapping XS b093b2e6
END DESCRIPTION:
XS GIS Cut Line= 2
      3857587.37     10083501.27      3857730.61      10082907.5
#Sta/Elev= 30
  4738.3  124.13  4769.4  122.62  4789.9  123.73  4810.5  122.66  4872.2  122.55
  4882.5  119.23  4888.6  113.16  4893.8  117.86  4903.1  114.21  4923.7  108.85
  4944.2  108.51  4964.8  106.82  4972.4  105.04  4977.6  105.96  4985.4  102.39
  5014.3  104.69  5017.7  100.89  5021.2  100.89  5026.5  104.47  5036.8  108.11
  5056.2  110.89  5073.5  110.66  5088.3  110.46  5108.8  112.29  5119.1  111.72
  5157.7  115.05    5187  117.27  5242.6  119.13  5270.8  121.79  5349.1  122.75
#Mann= 5 ,-1 , 0
  4738.3     .17       0  4944.2     .09       0  5036.8     .17       0
  5073.5     .15       0  5157.7     .17       0
Bank Sta=4944.2,5036.8
XS Rating Curve= 0 ,0
Exp/Cntr=0.3,0.1

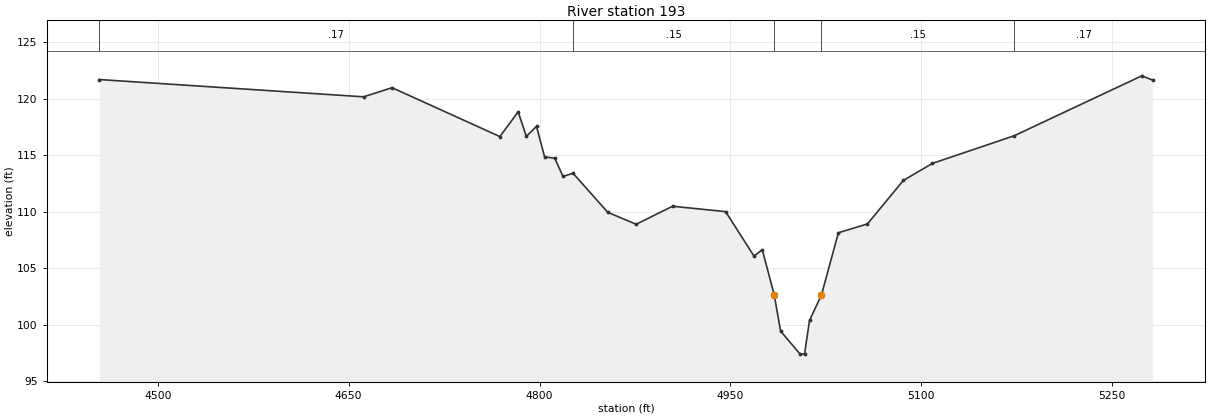
Type RM Length L Ch R = 1 ,193     ,0,0,0
BEGIN DESCRIPTION:
Crystal Creek 033 1.0
END DESCRIPTION:
XS GIS Cut Line= 3
      3857644.68     10083580.67      3857988.42     10083157.51
      3857867.31     10082902.27
#Sta/Elev= 30
  4454.1   121.7  4661.8  120.17  4684.1  120.98  4768.8  116.65  4783.2  118.84
  4789.6  116.66  4797.6  117.55    4804  114.84  4811.9  114.74  4818.4  113.12
  4826.3   113.4  4853.6  109.94  4875.9  108.88  4904.5  110.48  4946.2     110
  4968.5  106.06    4975  106.63 4984.39102.6236  4989.4   99.42  5004.7   97.38
  5008.2   97.38  5012.1  100.36 5021.49102.6225  5034.8  108.13  5057.6  108.91
  5085.8  112.76  5108.6  114.27  5172.9  116.72  5273.2  122.03  5281.8  121.65
#Mann= 5 ,-1 , 0
  4454.1     .17       0  4826.3     .15       0 4984.39     .09       0
 5021.49     .15       0  5172.9     .17       0
#XS Ineff= 2 , 0
       0    4975  106.63               0
Permanent Ineff=
       F       F
Bank Sta=4984.39,5021.49
XS Rating Curve= 0 ,0
Exp/Cntr=0.3,0.1

Chan Stop Cuts=-1
Use User Specified Reach Order=0
Composite Channel Slope=5

--- Crystal Creek 033.g10 (geometry) ---

Geom Title=Existing Conditions
Program Version=4.10

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
River Reach=Crystal Creek 03,Reach-1

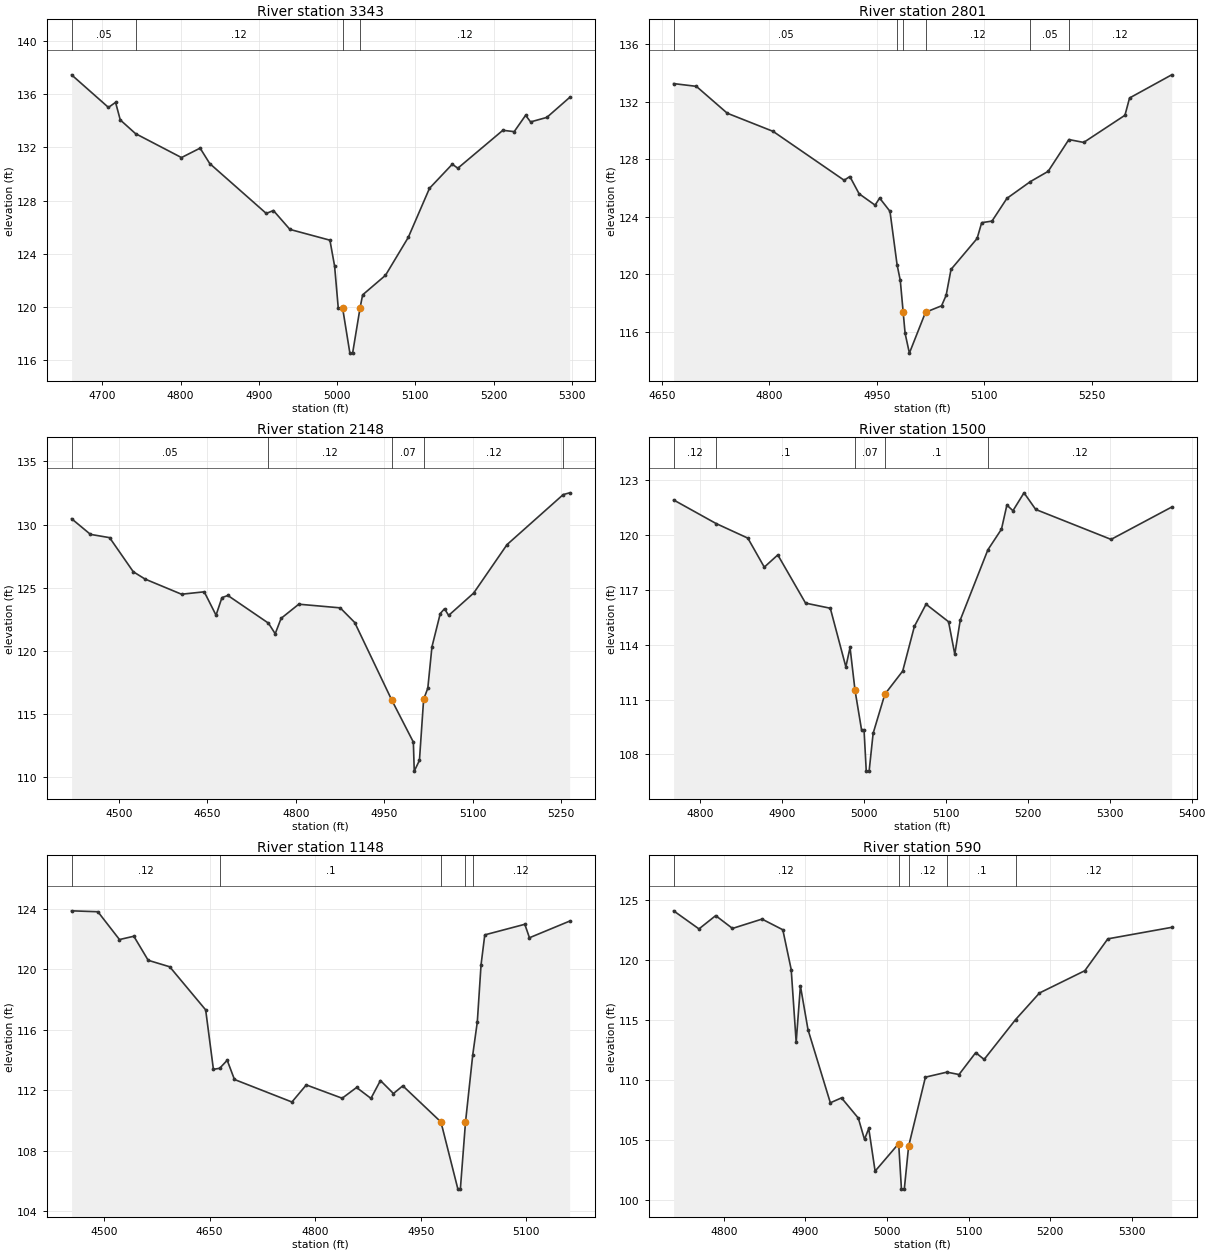
Type RM Length L Ch R = 1 ,3343    ,542,542,542
BEGIN DESCRIPTION:
Crystal Creek 033 5.0
END DESCRIPTION:
XS GIS Cut Line= 3
      3856317.09     10084158.04      3856127.74      10083871.7
      3855893.85     10083695.37
#Sta/Elev= 30
  4660.8  137.45  4707.9     135    4717  135.38    4723  134.06  4742.5  133.03
  4801.2  131.23    4825  131.94  4837.3  130.78  4909.5  127.03  4918.6  127.25
  4939.7  125.83  4990.8  125.02  4996.8  123.07  5001.5  119.89  5007.1  119.89
  5016.3  116.53  5019.8  116.53 5029.35 119.946  5032.6  120.91  5061.8  122.38
  5090.9  125.23    5118  128.92  5147.1  130.73  5154.2  130.43  5211.7  133.28
  5226.2  133.18  5240.8  134.41  5247.1  133.91  5267.9  134.25    5297  135.75
#Mann= 4 ,-1 , 0
  4660.8     .05       0  4742.5     .12       0  5007.1     .07       0
 5029.35     .12       0
Bank Sta=5007.1,5029.35
XS Rating Curve= 0 ,0
Exp/Cntr=0.3,0.1

Type RM Length L Ch R = 1 ,2801    ,653,653,653
BEGIN DESCRIPTION:
Mapping XS df28f753
END DESCRIPTION:
XS GIS Cut Line= 2
      3856731.06      10083882.8      3856295.29     10083341.12
#Sta/Elev= 30
  4666.6  133.26  4698.3  133.07  4741.5   131.2  4805.4  129.94  4904.6  126.54
  4912.6   126.8  4925.5   125.6  4947.8  124.81  4954.2   125.3  4968.6  124.38
  4978.5  120.67    4983  119.57    4987 117.379  4989.7   115.9  4995.7  114.52
  5018.2  117.36  5040.6  117.81    5047  118.54  5053.8  120.34  5090.2  122.49
  5096.6  123.59    5111   123.7  5131.8  125.28  5164.7  126.45  5189.4  127.16
  5218.3  129.37    5239  129.17  5296.6  131.06    5303  132.26  5361.8  133.87
#Mann= 6 ,-1 , 0
  4666.6     .05       0  4978.5     .12       0    4987     .07       0
  5018.2     .12       0  5164.7     .05       0  5218.3     .12       0
Bank Sta=4987,5018.2
XS Rating Curve= 0 ,0
Exp/Cntr=0.3,0.1

Type RM Length L Ch R = 1 ,2148    ,648,648,648
BEGIN DESCRIPTION:
Crystal Creek 033 4.0
END DESCRIPTION:
XS GIS Cut Line= 3
      3856845.18     10083825.44      3856806.13     10083247.36
      3856617.82     10083061.04
#Sta/Elev= 30
  4419.9  130.46  4451.9  129.22  4484.4  128.96  4524.5  126.26  4544.5  125.68
  4606.3  124.48  4644.8  124.67  4664.8  122.82  4674.8  124.21  4684.9  124.38
  4753.6  122.19  4765.1  121.35  4775.1  122.57  4805.1  123.69  4875.3   123.4
  4899.9  122.24 4962.87  116.08  4999.3  112.77  5000.8  110.47  5009.6  111.32
  5016.7  116.15  5023.8  117.04  5030.8  120.31  5044.9  122.95  5052.1  123.33
  5059.1   122.8  5101.5  124.57  5158.1  128.41  5253.3  132.37  5264.2  132.51
#Mann= 5 ,-1 , 0
  4419.9     .05       0  4753.6     .12       0 4962.87     .07       0
  5016.7     .12       0  5253.3     .05       0
Bank Sta=4962.87,5016.7
XS Rating Curve= 0 ,0
Exp/Cntr=0.3,0.1

Type RM Length L Ch R = 1 ,1500    ,352,352,352
BEGIN DESCRIPTION:
Crystal Creek 033 3.0
END DESCRIPTION:
XS GIS Cut Line= 3
      3857267.86     10083261.03      3857294.98     10083030.12
      3857011.69      10082783.5
#Sta/Elev= 30
  4767.5  121.93  4819.3  120.64  4858.1  119.84  4878.2  118.25  4894.7  118.92
  4928.6  116.28  4958.8     116  4977.8  112.79  4982.9  113.85    4989   111.5
    4997  109.33    5000  109.33  5002.7  107.08  5006.2  107.08  5011.1  109.15
  5025.4  111.29  5047.2  112.56  5061.5  115.01  5075.7  116.22  5103.2  115.26
  5110.8  113.48  5117.5  115.36  5151.2   119.2  5167.8  120.33  5174.4  121.65
  5181.8  121.34  5195.3  122.32  5209.6  121.41  5301.6  119.77  5375.6  121.54
#Mann= 5 ,-1 , 0
  4767.5     .12       0  4819.3      .1       0    4989     .07       0
  5025.4      .1       0  5151.2     .12       0
Bank Sta=4989,5025.4
XS Rating Curve= 0 ,0
Exp/Cntr=0.3,0.1

Type RM Length L Ch R = 1 ,1148    ,558,558,558
BEGIN DESCRIPTION:
Crystal Creek 033 2.0
END DESCRIPTION:
XS GIS Cut Line= 3
      3857322.84     10083407.71      3857410.29     10082985.64
      3857671.79     10082894.71
#Sta/Elev= 30
  4453.7  123.86  4491.1   123.8  4521.8  121.96  4542.2  122.18  4562.6  120.59
  4593.2  120.16  4644.3  117.31  4655.3  113.38  4664.2  113.45  4674.9  113.98
  4685.2  112.71  4766.9  111.22  4787.3  112.35  4838.3  111.47  4858.8  112.18
  4879.2  111.46  4892.7  112.64  4911.2  111.78  4924.5  112.29  4978.7   109.9
  5002.8  105.46  5006.3  105.46 5013.59 109.878  5023.9  114.34  5030.4  116.52
  5035.7  120.29    5041  122.27  5097.9  122.97  5104.5  122.08  5161.6  123.18
#Mann= 5 ,-1 , 0
  4453.7     .12       0  4664.2      .1       0  4978.7     .07       0
 5013.59      .1       0  5023.9     .12       0
Bank Sta=4978.7,5013.59
XS Rating Curve= 0 ,0
Exp/Cntr=0.3,0.1

Type RM Length L Ch R = 1 ,590     ,397,397,397
BEGIN DESCRIPTION:
Mapping XS b093b2e6
END DESCRIPTION:
XS GIS Cut Line= 2
      3857587.37     10083501.27      3857730.61      10082907.5
#Sta/Elev= 30
  4738.3  124.13  4769.4  122.62  4789.9  123.73  4810.5  122.66  4846.7  123.44
  4872.2  122.55  4882.5  119.23  4888.6  113.16  4893.8  117.86  4903.1  114.21
  4930.5   108.1  4944.2  108.51  4964.8  106.82  4972.4  105.04  4977.6  105.96
  4985.4  102.39  5014.3  104.69  5017.7  100.89  5021.2  100.89  5026.5  104.47
  5047.1  110.24  5073.5  110.66  5088.3  110.46  5108.8  112.29  5119.1  111.72
  5157.7  115.05    5187  117.27  5242.6  119.13  5270.8  121.79  5349.1  122.75
#Mann= 5 ,-1 , 0
  4738.3     .12       0  5014.3     .07       0  5026.5     .12       0
  5073.5      .1       0  5157.7     .12       0
Bank Sta=5014.3,5026.5
XS Rating Curve= 0 ,0
Exp/Cntr=0.3,0.1

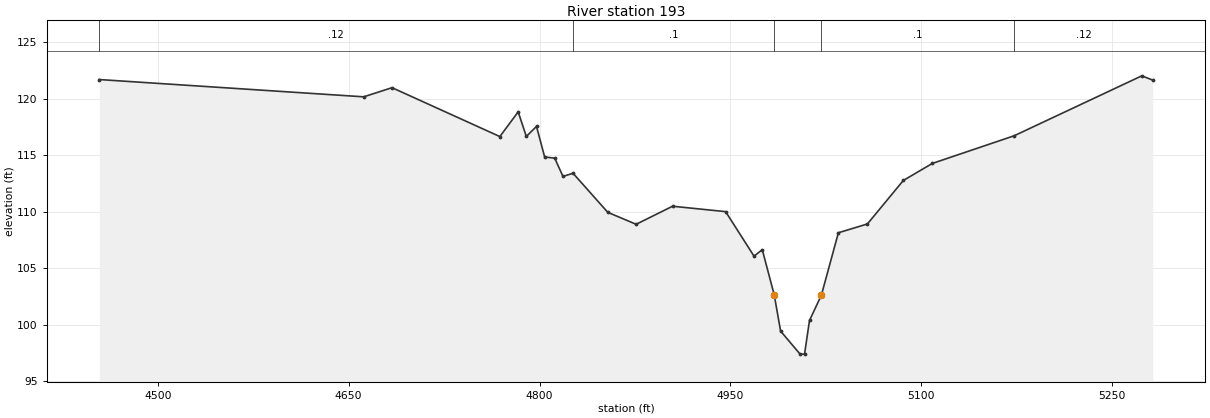
Type RM Length L Ch R = 1 ,193     ,0,0,0
BEGIN DESCRIPTION:
Crystal Creek 033 1.0
END DESCRIPTION:
XS GIS Cut Line= 3
      3857644.68     10083580.67      3857988.42     10083157.51
      3857867.31     10082902.27
#Sta/Elev= 30
  4454.1   121.7  4661.8  120.17  4684.1  120.98  4768.8  116.65  4783.2  118.84
  4789.6  116.66  4797.6  117.55    4804  114.84  4811.9  114.74  4818.4  113.12
  4826.3   113.4  4853.6  109.94  4875.9  108.88  4904.5  110.48  4946.2     110
  4968.5  106.06    4975  106.63 4984.39 102.624  4989.4   99.42  5004.7   97.38
  5008.2   97.38  5012.1  100.36 5021.49 102.623  5034.8  108.13  5057.6  108.91
  5085.8  112.76  5108.6  114.27  5172.9  116.72  5273.2  122.03  5281.8  121.65
#Mann= 5 ,-1 , 0
  4454.1     .12       0  4826.3      .1       0 4984.39     .07       0
 5021.49      .1       0  5172.9     .12       0
Bank Sta=4984.39,5021.49
XS Rating Curve= 0 ,0
Exp/Cntr=0.3,0.1