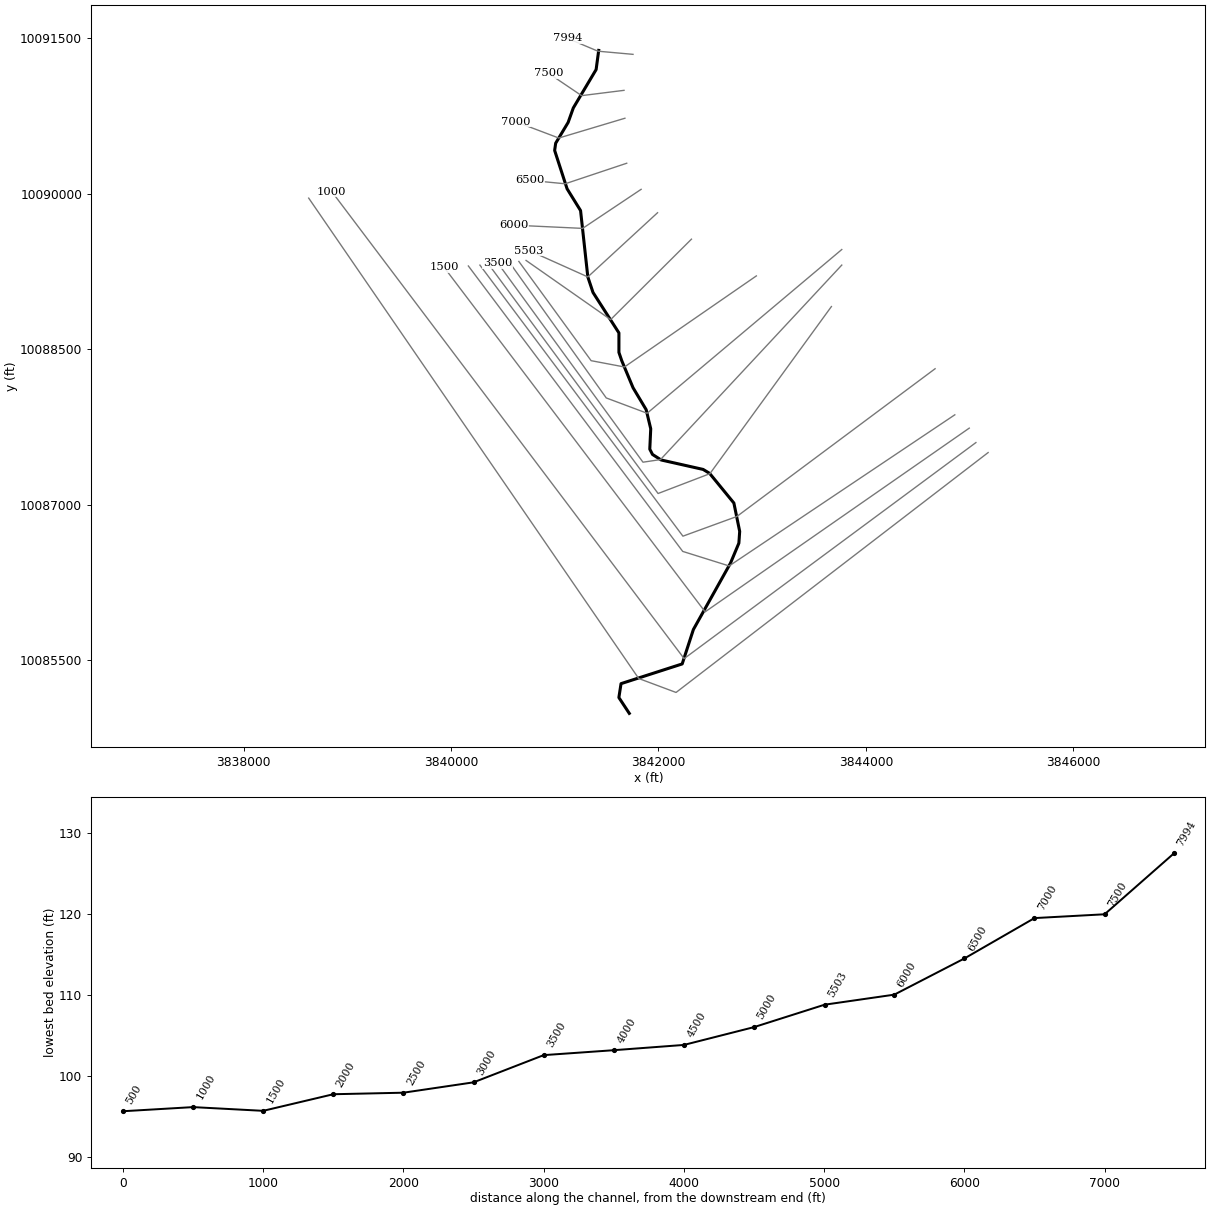
--- Crystal Creek 037.prj (project) ---

Proj Title=Crystal Creek 037 Base Level Engineering
Current Plan=p01
Default Exp/Contr=0.3,0.1
English Units
Geom File=g01
Flow File=f01
Flow File=f02
Plan File=p01
Y Axis Title=Elevation
X Axis Title(PF)=Main Channel Distance
X Axis Title(XS)=Station
BEGIN DESCRIPTION:
Crystal Creek 037
END DESCRIPTION:
DSS File=dss
DSS Export Rating Curves= 0
DSS Export Rating Curve Sorted= 0
DSS Export Volume Flow Curves= 0
DXF OffsetX= 0
DXF OffsetY= 0
DXF ScaleX= 1
DXF ScaleY= 10

--- Crystal Creek 037.p01 (plan) ---

Plan Title=Multiple Run
Program Version=4.10
Geom File=g01
Subcritical Flow
K Sum by GR= 0
Std Step Tol= 0.01
Critical Tol= 0.01
Num of Std Step Trials= 20
Max Error Tol= 0.3
Flow Tol Ratio= 0.001
Split Flow NTrial= 30
Split Flow Tol= 0.02
Split Flow Ratio= 0.02
Log Output Level= 0
Friction Slope Method= 1
Unsteady Friction Slope Method= 2
Unsteady Bridges Friction Slope Method= 1
Parabolic Critical Depth
Global Vel Dist= 1 , 1 , 1
Global Log Level= 0
CheckData=True
Encroach Param=-1 ,0,0, 0
BEGIN DESCRIPTION:
Multiple Run
END DESCRIPTION:
Computation Interval=1HOUR
Output Interval=1HOUR
Run HTab= 0
Run UNet= 0
Run PostProcess= 0
Run WQNet= 0
UNET Theta= 1
UNET Theta Warmup= 1
UNET ZTol= 0.02
UNET ZSATol= 0.05
UNET MxIter= 20
UNET MaxInSteps= 0
UNET DtIC= 0
UNET DtMin= 0
UNET MaxCRTS= 20
UNET WFStab= 2
UNET SFStab= 1
UNET WFX= 1
UNET SFX= 1
UNET DSS MLevel= 4
UNET DZMax Abort= 100
UNET Convert EG Bridges= 0
UNET Use Existing IB Tables=-1
UNET Froude Reduction=False
UNET Froude Limit= 1
UNET Froude Power= 10
UNET Time Slicing=0,0, 5
UNET Junction Losses=0
Instantaneous Interval=1HOUR
DSS File=dss
Write IC File= 0
Write IC File at Sim End=0
Echo Input=False
Echo Parameters=False
Echo Output=False
Write Detailed= 0
WQ AD Non Conservative
WQ ULTIMATE=-1
WQ Max Comp Step=1HOUR
WQ Output Interval=15MIN
WQ Output Selected Increments= 0
WQ Output face flow=0
WQ Output face velocity=0
WQ Output face area=0
WQ Output face dispersion=0
WQ Output cell volume=0
WQ Output cell surface area=0
WQ Output cell continuity=0
WQ Output cumulative cell continuity=0
WQ Output face conc=0
WQ Output face dconc_dx=0
WQ Output face courant=0
WQ Output face peclet=0
WQ Output face adv mass=0
WQ Output face disp mass=0
WQ Output cell mass=0
WQ Output cell source sink temp=0
WQ Output cell source sink nsm=0
WQ Output MaxMinRange=-1
WQ Daily Max Min Mean=-1
WQ Daily Range=0
WQ Daily Time=0
WQ Create Restart=0
WQ Fixed Restart=0
WQ System Summary=0
WQ Use Fixed Temperature=0
Sorting and Armoring Iterations= 10
XS Update Threshold= 0.02
Hydraulics Update Threshold= 0.02
Energy Slope Method= 1
Volume Change Method= 0
XS Weighting Method= 0
Number of US Weighted Cross Sections= 1
Number of DS Weighted Cross Sections= 1
Upstream XS Weight=0.25
Main XS Weight=0.5
Downstream XS Weight=0.25
Number of DS XS's Weighted with US Boundary= 1
Upstream Boundary Weight= 1
Weight of XSs Associated with US Boundary= 0
Number of US XS's Weighted with DS Boundary= 1
Downstream Boundary Weight= 0.5
Weight of XSs Associated with DS Boundary= 0.5
Sediment Output Level= 4
Mass or Volume Output= 0
Output Increment Type= 1
Profile and TS Output Increment= 10
XS Output Flag= 0
XS Output Increment= 10
Disregard all LS=0
Disregard all Conn=0
Disregard all Breaches=0
Disregard all Pumps=0

--- Crystal Creek 037.f01 (steady flow) ---

Flow Title=Multiple
Program Version=4.10
Number of Profiles= 7
Profile Names=10-year,25-year,50-year,1pct_min,100-year,1pct_plu,500-year
River Rch & RM=Crystal Creek 03,Reach-1         ,7994
     690     924    1240     546    1650    4983    3022
River Rch & RM=Crystal Creek 03,Reach-1         ,5000
    1065    1468    2007     901    2722    8220    5174
Boundary for River Rch & Prof#=Crystal Creek 03,Reach-1         , 1
Up Type= 0
Dn Type= 3
Dn Slope=0.001
Boundary for River Rch & Prof#=Crystal Creek 03,Reach-1         , 2
Up Type= 0
Dn Type= 3
Dn Slope=0.001
Boundary for River Rch & Prof#=Crystal Creek 03,Reach-1         , 3
Up Type= 0
Dn Type= 3
Dn Slope=0.001
Boundary for River Rch & Prof#=Crystal Creek 03,Reach-1         , 4
Up Type= 0
Dn Type= 3
Dn Slope=0.001
Boundary for River Rch & Prof#=Crystal Creek 03,Reach-1         , 5
Up Type= 0
Dn Type= 3
Dn Slope=0.001
Boundary for River Rch & Prof#=Crystal Creek 03,Reach-1         , 6
Up Type= 0
Dn Type= 3
Dn Slope=0.001
Boundary for River Rch & Prof#=Crystal Creek 03,Reach-1         , 7
Up Type= 0
Dn Type= 3
Dn Slope=0.001
DSS Import GetInterval= 0
DSS Import GetPeak= 0
DSS Import FillOption= 0

--- Crystal Creek 037.f02 (steady flow) ---

Flow Title=Orig_BLE_Flow
Program Version=4.10
Number of Profiles= 7
Profile Names=10-year,25-year,50-year,1pct_min,100-year,1pct_plu,500-year
River Rch & RM=Crystal Creek 03,Reach-1         ,7994
     690     906    1078     420    1269    3833    1757
River Rch & RM=Crystal Creek 03,Reach-1         ,5000
    1065    1439    1745     693    2094    6323    3008
Boundary for River Rch & Prof#=Crystal Creek 03,Reach-1         , 1
Up Type= 0
Dn Type= 3
Dn Slope=0.001
Boundary for River Rch & Prof#=Crystal Creek 03,Reach-1         , 2
Up Type= 0
Dn Type= 3
Dn Slope=0.001
Boundary for River Rch & Prof#=Crystal Creek 03,Reach-1         , 3
Up Type= 0
Dn Type= 3
Dn Slope=0.001
Boundary for River Rch & Prof#=Crystal Creek 03,Reach-1         , 4
Up Type= 0
Dn Type= 3
Dn Slope=0.001
Boundary for River Rch & Prof#=Crystal Creek 03,Reach-1         , 5
Up Type= 0
Dn Type= 3
Dn Slope=0.001
Boundary for River Rch & Prof#=Crystal Creek 03,Reach-1         , 6
Up Type= 0
Dn Type= 3
Dn Slope=0.001
Boundary for River Rch & Prof#=Crystal Creek 03,Reach-1         , 7
Up Type= 0
Dn Type= 3
Dn Slope=0.001
DSS Import GetInterval= 0
DSS Import GetPeak= 0
DSS Import FillOption= 0

--- Crystal Creek 037.g01 (geometry) ---

Geom Title=Existing Conditions
Program Version=4.10

River Reach=Crystal Creek 03,Reach-1
Reach XY= 30
      3841423.24     10091381.86      3841398.24     10091196.86
      3841178.24     10090826.86      3841128.24     10090686.86
      3841008.24     10090486.86      3840998.24     10090416.86
      3841118.24     10090046.86      3841248.24     10089836.86
      3841318.24     10089196.86      3841368.24     10089046.86
      3841618.24     10088656.86      3841618.24     10088468.47
      3841645.54     10088388.65      3841754.48      10088127.8
      3841880.79     10087916.86      3841925.06     10087731.96
      3841915.94     10087535.35      3841941.98     10087484.57
      3842025.32     10087431.18      3842430.27     10087340.04
      3842492.77     10087302.27      3842727.14     10087015.82
      3842783.13     10086742.38      3842775.32      10086629.1
      3842694.59     10086436.39      3842336.52     10085795.76
      3842228.44     10085463.73       3841638.6     10085273.63
      3841617.77     10085139.51      3841718.24     10084986.86

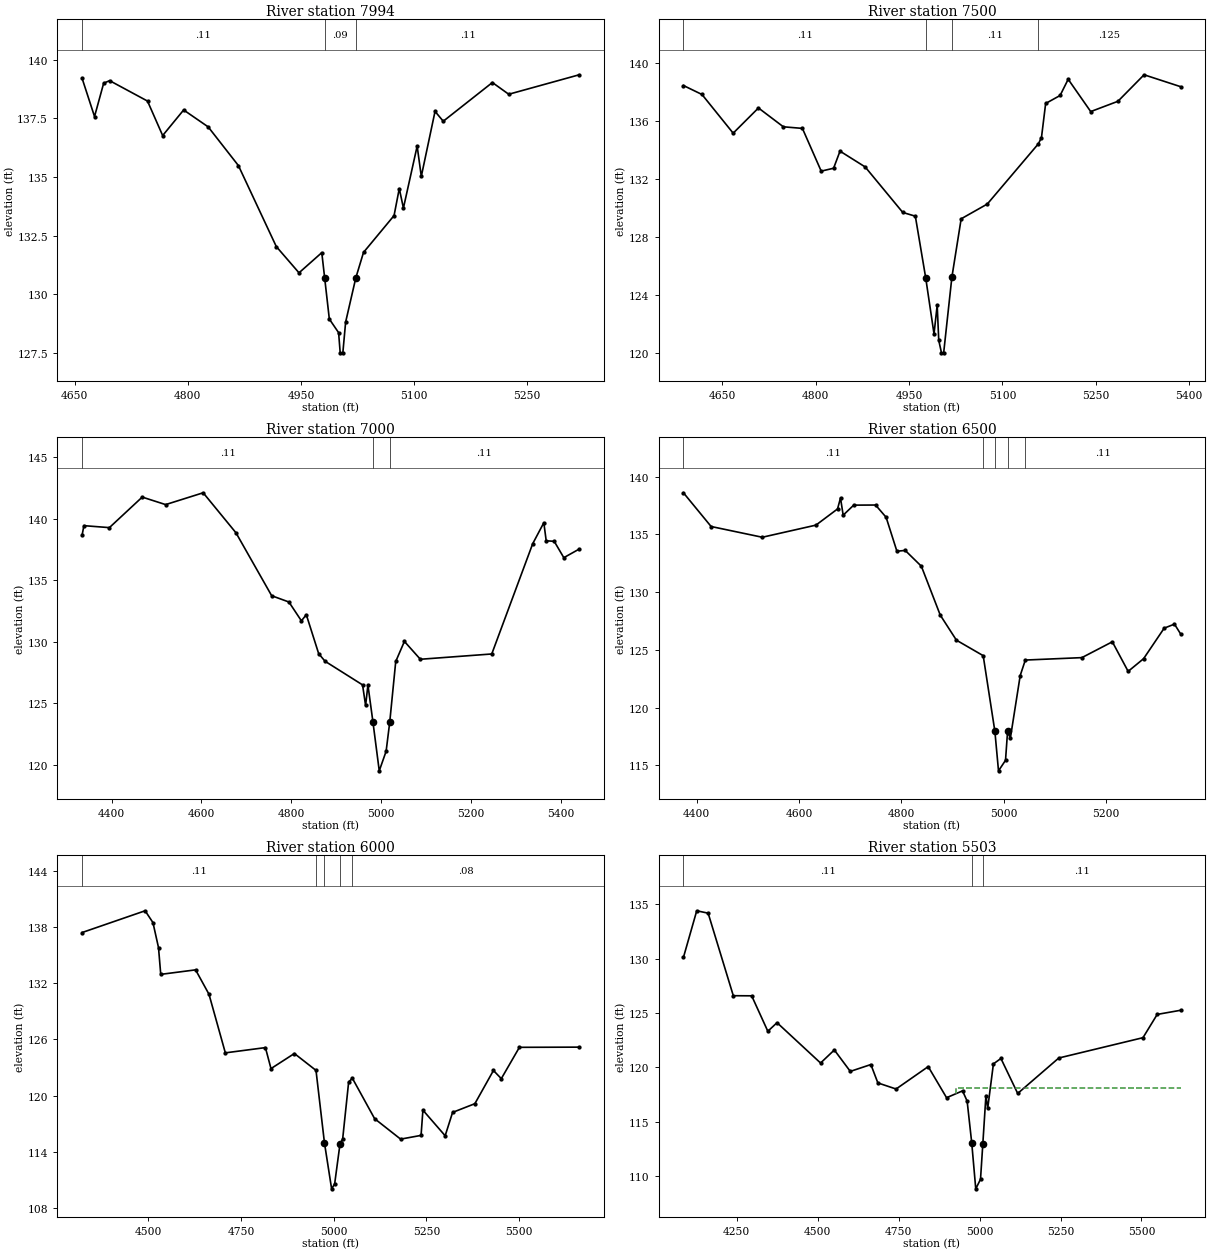
Type RM Length L Ch R = 1 ,7994    ,494,494,494
BEGIN DESCRIPTION:
Crystal Creek 037 16.0
END DESCRIPTION:
XS GIS Cut Line= 3
      3841754.24     10091343.77      3841415.61     10091374.24
       3841121.8     10091498.21
#Sta/Elev= 30
    4660  139.21  4676.5  137.58  4688.6     139  4696.5  139.11  4746.7  138.24
  4766.8  136.77  4794.6  137.86  4827.1  137.14  4867.2  135.49  4917.4  132.04
  4947.5  130.92  4977.7  131.78 4981.59130.6792  4987.7  128.95    5000  128.37
  5002.1  127.51  5005.6  127.51  5009.3  128.82 5022.76 130.701    5033  131.79
  5073.5  133.36  5080.4  134.51  5085.9  133.68  5104.1  136.32  5109.6  135.03
  5127.8   137.8  5138.7  137.38  5203.8  139.03  5225.5  138.53  5318.9  139.36
#Mann= 3 , 0 , 0
    4660     .11       0 4981.59     .09       0 5022.76     .11       0
Bank Sta=4981.59,5022.76
XS Rating Curve= 0 ,0
Exp/Cntr=0.3,0.1

Type RM Length L Ch R = 1 ,7500    ,500,500,500
BEGIN DESCRIPTION:
Crystal Creek 037 15.0
END DESCRIPTION:
XS GIS Cut Line= 3
      3841667.46     10090996.55      3841258.24     10090945.45
      3840938.25     10091161.51
#Sta/Elev= 30
  4587.6  138.44  4617.4  137.82  4667.5  135.15  4708.1  136.89  4748.1  135.59
  4778.7  135.48  4808.9  132.53  4828.8  132.73  4839.1  133.91  4879.5  132.82
  4939.9  129.68  4960.1  129.42 4976.75125.1651  4990.1   121.3  4995.2  123.28
  4997.7  120.85  5002.1  119.99  5005.6  119.99  5018.8  125.21  5033.7  129.24
  5075.7  130.26  5157.8  134.42  5162.7  134.85  5169.4   137.2  5192.6  137.75
  5205.6  138.87  5241.8  136.64  5285.5  137.35  5327.5  139.18  5386.1  138.36
#Mann= 4 ,-1 , 0
  4587.6     .11       0 4976.75     .09       0  5018.8     .11       0
  5157.8    .125       0
Bank Sta=4976.75,5018.8
XS Rating Curve= 0 ,0
Exp/Cntr=0.3,0.1

Type RM Length L Ch R = 1 ,7000    ,500,500,500
BEGIN DESCRIPTION:
Crystal Creek 037 14.0
END DESCRIPTION:
XS GIS Cut Line= 3
      3841676.09     10090727.44      3841038.24     10090536.57
      3840625.81     10090692.72
#Sta/Elev= 30
  4334.2  138.66  4338.3  139.43    4395  139.27  4468.1  141.75  4520.2  141.14
  4603.8   142.1  4676.8  138.85  4756.3  133.74  4794.7  133.23  4822.5   131.7
  4833.4   132.2  4860.9  129.04  4875.1  128.42  4958.6   126.5  4965.4  124.83
  4970.6  126.49 4981.73123.4921  4995.8  119.52  5011.1  121.11 5019.19123.4907
  5032.5   128.4  5051.8  130.03  5087.3  128.58  5246.3  129.01  5337.4  137.96
  5362.2  139.67  5367.5   138.2  5385.3  138.16  5406.7  136.83    5441  137.53
#Mann= 3 , 0 , 0
  4334.2     .11       0 4981.73     .09       0 5019.19     .11       0
#XS Ineff= 2 , 0
       0  4970.6  126.49               0
Permanent Ineff=
       F       F
Bank Sta=4981.73,5019.19
XS Rating Curve= 0 ,0
Exp/Cntr=0.3,0.1

Type RM Length L Ch R = 1 ,6500    ,500,500,500
BEGIN DESCRIPTION:
Crystal Creek 037 13.0
END DESCRIPTION:
XS GIS Cut Line= 3
      3841693.45     10090293.41      3841099.86     10090095.24
      3840755.97      10090128.5
#Sta/Elev= 30
  4374.2   138.6  4428.3  135.68  4528.3  134.75  4633.1   135.8  4675.3   137.2
  4681.1  138.15  4686.3  136.66  4706.9  137.53  4749.6  137.54  4770.2  136.48
  4791.3  133.54  4807.5  133.61  4839.1  132.24    4876  128.01  4907.6  125.84
  4959.9   124.5 4982.73117.9458  4989.8  114.53  5003.5  115.44 5007.53117.9587
  5012.9  117.34  5032.2  122.78  5042.2  124.12  5152.7  124.33  5212.2   125.7
  5243.1  123.14  5273.3  124.24  5313.5  126.88  5333.6  127.23  5345.5  126.39
#Mann= 5 ,-1 , 0
  4374.2     .11       0  4959.9     .12       0 4982.73     .09       0
 5007.53     .12       0  5042.2     .11       0
Bank Sta=4982.73,5007.53
XS Rating Curve= 0 ,0
Exp/Cntr=0.3,0.1

Type RM Length L Ch R = 1 ,6000    ,497,497,497
BEGIN DESCRIPTION:
Crystal Creek 037 12.0
END DESCRIPTION:
XS GIS Cut Line= 3
      3841832.42     10090041.71      3841268.24     10089664.98
      3840606.77     10089696.14
#Sta/Elev= 30
  4321.6  137.39  4491.6  139.71  4512.7  138.45  4527.7  135.78  4533.7  132.93
  4627.7  133.41  4663.8  130.81  4707.9  124.56    4816  125.12    4831  122.88
  4894.1  124.49  4952.4  122.69  4975.2  114.96  4994.5  110.06  5002.7  110.59
  5017.1114.8465  5024.3  115.38  5040.4  121.44  5050.4  121.86  5110.5  117.54
  5180.6  115.36  5235.7  115.76  5240.7  118.45  5300.7  115.72  5320.7  118.21
  5380.8  119.14  5430.9  122.68  5452.1  121.81  5500.9  125.15  5662.2  125.17
#Mann= 5 ,-1 , 0
  4321.6     .11       0  4952.4     .12       0  4975.2     .09       0
  5017.1     .12       0  5050.4     .08       0
Bank Sta=4975.2,5017.1
XS Rating Curve= 0 ,0
Exp/Cntr=0.3,0.1

Type RM Length L Ch R = 1 ,5503    ,503,503,503
BEGIN DESCRIPTION:
Crystal Creek 037 11.0
END DESCRIPTION:
XS GIS Cut Line= 3
      3841990.84     10089816.03      3841318.24     10089196.86
      3840752.07     10089451.03
#Sta/Elev= 30
  4085.8   130.1  4126.9  134.39  4162.1  134.17  4239.8  126.58  4296.5  126.57
  4346.4  123.31  4374.8   124.1  4509.2  120.39  4551.7  121.59    4601  119.62
  4664.5  120.25  4686.1  118.56  4742.3     118  4841.5  120.06  4898.2   117.2
  4947.5  117.83  4961.7  116.89  4975.9  113.04  4988.3  108.82    5003   109.7
 5010.14112.9641  5019.7   117.4  5025.2  116.22  5042.8  120.31    5066  120.81
  5117.8  117.59  5244.6  120.85  5504.6  122.72  5548.5  124.86  5620.6  125.24
#Mann= 3 , 0 , 0
  4085.8     .11       0  4975.9     .09       0 5010.14     .11       0
#XS Ineff= 3 ,-1
  4926.6  4841.5  118.12  5019.7  5042.8   117.4  5042.8  5244.6  120.31
Permanent Ineff=
       F       F       F
Bank Sta=4975.9,5010.14
XS Rating Curve= 0 ,0
Exp/Cntr=0.3,0.1

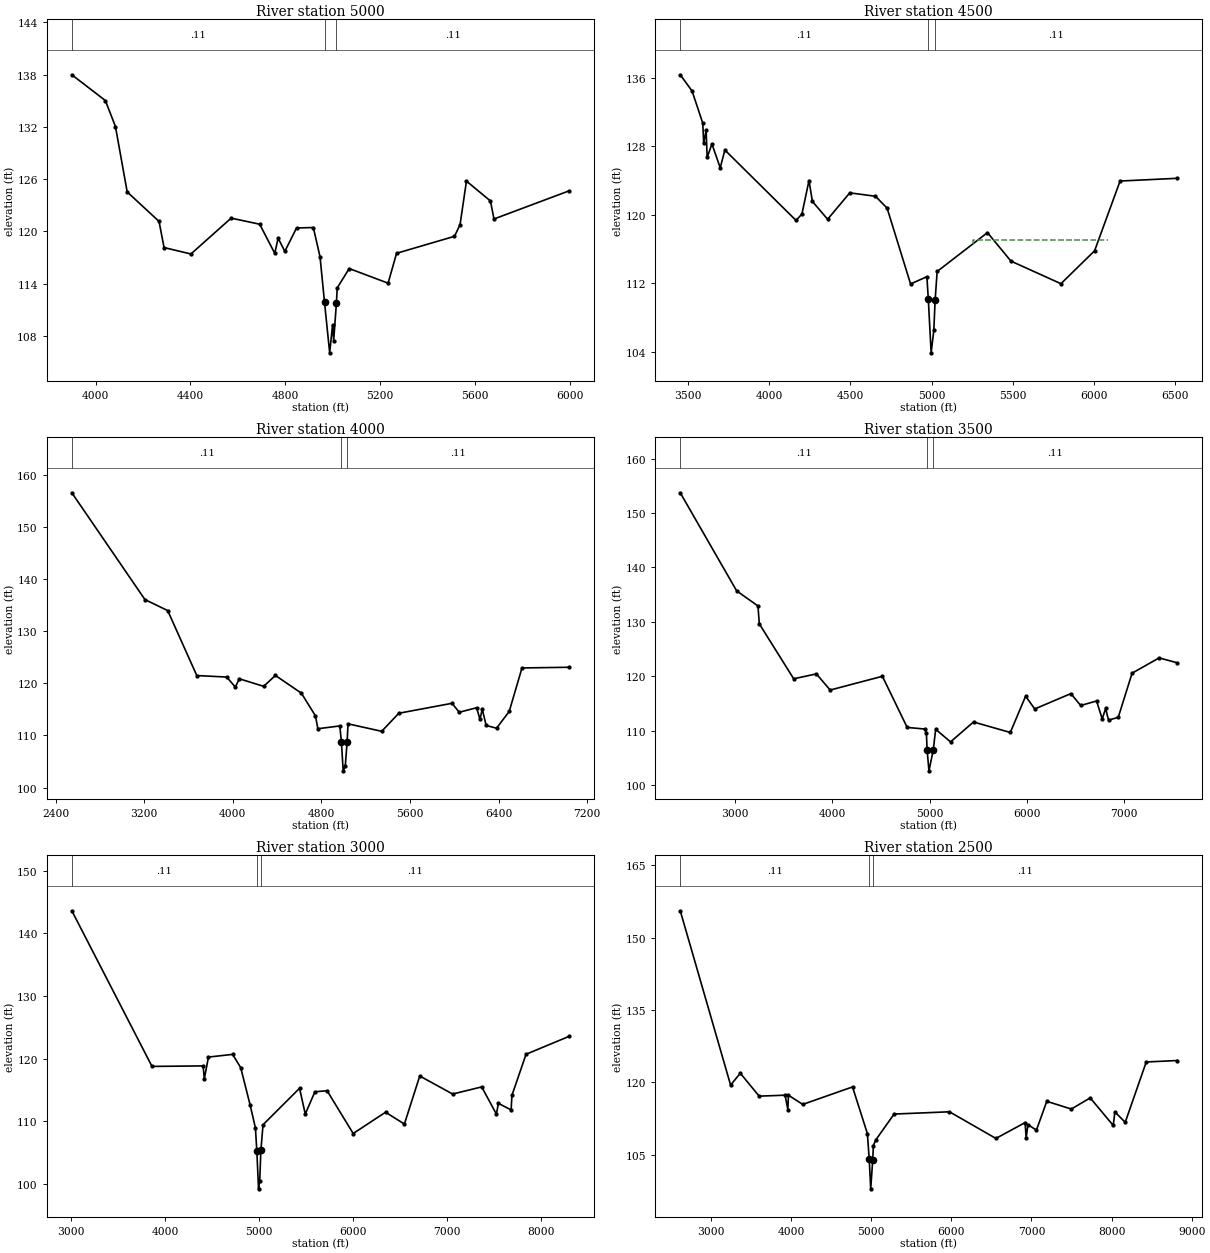
Type RM Length L Ch R = 1 ,5000    ,500,500,500
BEGIN DESCRIPTION:
Crystal Creek 037 10.0
END DESCRIPTION:
XS GIS Cut Line= 3
      3842317.87     10089561.09      3841538.24      10088785.1
      3840722.58     10089355.83
#Sta/Elev= 30
    3900  137.98  4041.4  135.02  4083.9  132.04  4133.4  124.53  4267.7  121.14
  4288.9  118.14  4402.1   117.4  4571.8  121.52    4692  120.82  4755.6  117.48
  4769.8  119.22  4798.1   117.7  4847.5  120.39  4918.3  120.44  4946.5  117.08
 4965.47111.8464  4987.2  106.05  4999.3  109.25  5004.1  107.46 5015.68111.8184
    5019  113.51  5069.5  115.73  5233.5  114.05  5269.2  117.48  5513.4  119.43
  5536.9  120.77  5563.9  125.77  5665.1  123.49  5679.9  121.42  5995.5  124.64
#Mann= 3 , 0 , 0
    3900     .11       0 4965.47     .09       0 5015.68     .11       0
#XS Ineff= 2 , 0
       0                  5069.5       0  115.73
Permanent Ineff=
       F       F
Bank Sta=4965.47,5015.68
XS Rating Curve= 0 ,0
Exp/Cntr=0.3,0.1

Type RM Length L Ch R = 1 ,4500    ,500,500,500
BEGIN DESCRIPTION:
Crystal Creek 037 9.0
END DESCRIPTION:
XS GIS Cut Line= 4
      3842943.92     10089206.61      3841671.53     10088328.12
      3841350.18     10088388.91      3840652.96     10089346.29
#Sta/Elev= 30
  3453.8  136.35  3526.6  134.45  3592.2   130.7  3598.2  128.33  3613.1  129.88
  3619.2  126.69  3648.9  128.26  3699.6  125.48  3728.5  127.55    4166  119.33
  4202.4  120.07  4245.9  123.99  4266.8  121.55  4360.4  119.46  4496.7  122.55
  4654.9  122.15  4726.5  120.76  4870.8   111.9  4971.2  112.75    4980  110.09
  4997.4  103.85  5013.9   106.5 5021.77109.9798  5034.3  113.36  5343.9   117.9
  5488.4  114.57  5795.9  111.93    6003  115.78  6159.8  123.93  6511.4  124.25
#Mann= 3 , 0 , 0
  3453.8     .11       0    4980     .09       0 5021.77     .11       0
#XS Ineff= 2 ,-1
  5064.8  5145.7  113.74  5255.5  6082.5  117.09
Permanent Ineff=
       F       F
Bank Sta=4980,5021.77
XS Rating Curve= 0 ,0
Exp/Cntr=0.3,0.1

Type RM Length L Ch R = 1 ,4000    ,500,500,500
BEGIN DESCRIPTION:
Crystal Creek 037 8.0
END DESCRIPTION:
XS GIS Cut Line= 4
      3843767.85     10089461.07      3841890.35     10087881.78
      3841496.01     10088029.54      3840558.48     10089342.08
#Sta/Elev= 30
  2546.6   156.6  3206.7  136.09  3412.2  133.98  3674.9   121.5  3944.8  121.21
  4023.2  119.29  4058.6  120.88  4278.4  119.43    4385  121.52  4619.1  118.12
  4746.6  113.75  4768.1  111.29  4966.4  111.82  4980.7  108.78  4996.6   103.2
  5015.5   104.1 5032.24108.7171  5040.4  112.23  5344.4  110.79  5499.1  114.26
  5979.6  116.17  6044.8  114.45  6202.1  115.32  6231.6  113.09  6252.4  115.02
  6288.1  111.91  6381.5  111.39  6495.8   114.6  6611.3  122.96  7034.1  123.09
#Mann= 3 , 0 , 0
  2546.6     .11       0  4980.7     .09       0 5032.24     .11       0
Bank Sta=4980.7,5032.24
XS Rating Curve= 0 ,0
Exp/Cntr=0.3,0.1

Type RM Length L Ch R = 1 ,3500    ,500,500,500
BEGIN DESCRIPTION:
Crystal Creek 037 7.0
END DESCRIPTION:
XS GIS Cut Line= 4
      3843767.87      10089311.1      3842019.16     10087434.87
      3841850.18     10087409.75      3840449.13     10089331.63
#Sta/Elev= 30
  2435.2   153.7  3015.4  135.68  3234.8  132.89  3248.9   129.6  3602.6  119.51
  3836.2  120.41  3977.8  117.44  4515.2  119.97  4770.3  110.57    4954  110.27
  4968.1  109.46  4975.5  106.43  4994.3  102.59 5038.84  106.42  5063.4  110.23
  5216.5  107.91  5452.9  111.57  5831.5  109.64  5989.2  116.32  6082.5  113.96
  6454.9  116.79  6555.3   114.6  6719.4  115.43    6777  112.13  6812.6  114.05
  6841.9  111.92  6942.1  112.41  7084.5  120.54  7362.9  123.35  7549.2  122.45
#Mann= 3 , 0 , 0
  2435.2     .11       0  4975.5     .09       0 5038.84     .11       0
Bank Sta=4975.5,5038.84
XS Rating Curve= 0 ,0
Exp/Cntr=0.3,0.1

Type RM Length L Ch R = 1 ,3000    ,500,500,500
BEGIN DESCRIPTION:
Crystal Creek 037 6.0
END DESCRIPTION:
XS GIS Cut Line= 4
      3843667.85     10088911.07      3842495.98     10087299.13
      3841996.01     10087107.66      3840355.52     10089326.24
#Sta/Elev= 30
  3007.1  143.61    3860  118.77    4404  118.85  4416.5  116.78  4460.5  120.26
  4717.8  120.69  4803.6  118.58  4904.1  112.61  4960.5  108.94  4975.2   105.3
  4993.6   99.23    5006  100.45  5018.5105.3789  5041.3  109.46  5429.8  115.28
  5490.6  111.17  5593.4  114.72  5722.8  114.89  6000.4  108.06  6344.9  111.46
  6545.3  109.57  6708.7  117.24  7058.8  114.36  7367.8   115.5  7524.3  111.15
  7545.2  112.88  7680.9  111.82  7689.3  114.15  7839.6  120.71  8294.6  123.55
#Mann= 3 , 0 , 0
  3007.1     .11       0  4975.2     .09       0  5018.5     .11       0
Bank Sta=4975.2,5018.5
XS Rating Curve= 0 ,0
Exp/Cntr=0.3,0.1

Type RM Length L Ch R = 1 ,2500    ,500,500,500
BEGIN DESCRIPTION:
Crystal Creek 037 5.0
END DESCRIPTION:
XS GIS Cut Line= 4
      3844667.85     10088311.07      3842755.65     10086886.02
      3842235.59      10086696.2      3840277.25      10089310.8
#Sta/Elev= 30
  2615.2  155.55  3243.9  119.44  3364.8   121.9  3600.5  117.15  3923.7  117.35
  3959.1  114.36  3965.4  117.35  4144.7  115.44  4766.1  119.06  4951.7  109.39
 4974.83104.0319  4993.3   97.95 5018.52103.9838  5026.6  106.92  5057.2   108.1
  5285.1  113.44  5976.7  113.91    6556  108.39  6920.7  111.67    6934   108.5
  6956.1  111.25  7062.3  110.11  7191.5  116.08  7497.8  114.48  7733.7  116.79
  8020.9  111.08  8041.7  113.88  8170.9  111.73  8433.4  124.23  8820.3  124.53
#Mann= 3 , 0 , 0
  2615.2     .11       0 4974.83     .09       0 5018.52     .11       0
Bank Sta=4974.83,5018.52
XS Rating Curve= 0 ,0
Exp/Cntr=0.3,0.1

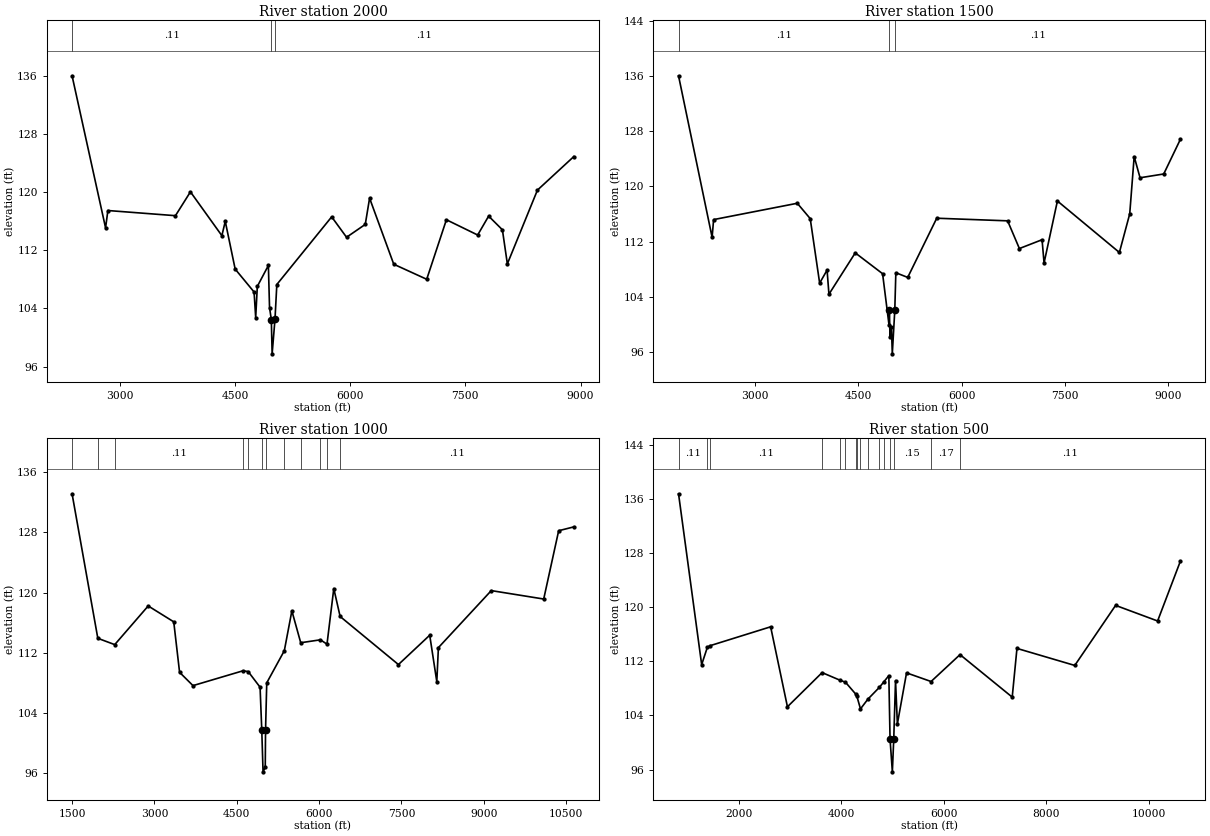
Type RM Length L Ch R = 1 ,2000    ,500,500,500
BEGIN DESCRIPTION:
Crystal Creek 037 4.0
END DESCRIPTION:
XS GIS Cut Line= 4
      3844858.18     10087866.85      3842681.42     10086408.91
      3842233.57     10086549.19        3840166.     10089302.38
#Sta/Elev= 30
  2380.1  136.02  2816.3  115.09  2846.3  117.48  3725.9  116.77    3921  120.05
  4330.3  114.02  4374.3  115.99  4503.4  109.42  4749.5  106.27  4770.5  102.76
  4791.6  107.04  4935.7  109.92  4950.7  104.13 4973.98102.4713  4984.5   97.76
  5021.7  102.51  5045.7   107.3  5759.6  116.61  5953.3   113.8    6197  115.57
  6253.2  119.18  6567.8  110.09  6996.8  108.02  7253.1  116.21  7660.2  114.11
    7803  116.71  7982.1  114.83  8046.7  110.14  8438.3  120.29  8912.4  124.91
#Mann= 3 , 0 , 0
  2380.1     .11       0 4973.98     .09       0  5021.7     .11       0
Bank Sta=4973.98,5021.7
XS Rating Curve= 0 ,0
Exp/Cntr=0.3,0.1

Type RM Length L Ch R = 1 ,1500    ,500,500,500
BEGIN DESCRIPTION:
Crystal Creek 037 3.0
END DESCRIPTION:
XS GIS Cut Line= 3
      3844997.52     10087738.34      3842449.76     10085966.16
      3839930.33     10089291.65
#Sta/Elev= 30
  1896.5  136.06  2383.4  112.62    2405  115.19  3618.2  117.56  3805.9  115.33
  3942.6  105.97  4050.3  107.86  4077.3  104.36  4458.8  110.36  4855.1  107.34
  4947.6   99.96  4953.7  102.06  4962.4   98.15  4983.3   99.65  4995.9   95.71
 5031.89102.0119  5047.3  107.48  5219.4   106.8  5640.2  115.39  6667.9  115.01
  6838.6  110.99  7167.3  112.27  7196.4   108.9  7389.8  117.89  8288.6  110.42
  8438.4  116.02  8502.9  124.34  8588.2  121.26  8931.4  121.81  9172.1  126.82
#Mann= 3 , 0 , 0
  1896.5     .11       0  4953.7     .09       0 5031.89     .11       0
Bank Sta=4953.7,5031.89
XS Rating Curve= 0 ,0
Exp/Cntr=0.3,0.1

Type RM Length L Ch R = 1 ,1000    ,500,500,500
BEGIN DESCRIPTION:
Crystal Creek 037 2.0
END DESCRIPTION:
XS GIS Cut Line= 3
      3845061.76     10087599.04      3842247.17     10085514.93
      3838848.32     10090020.14
#Sta/Elev= 30
  1497.8  133.13  1967.1  113.92  2275.4  113.08  2885.4  118.22  3350.9  116.11
  3457.3   109.4  3701.5  107.63  4612.2   109.6  4707.8   109.5  4924.5  107.42
 4955.51101.6716  4978.7   96.17  5018.9   96.79 5024.04101.6813    5046     108
  5366.3  112.27  5503.9  117.57  5665.2  113.33  6024.4  113.72  6144.2  113.14
  6267.9  120.53  6383.6  116.82  7446.1  110.43  8016.4  114.33  8145.5  108.16
  8174.6  112.68  9138.4  120.26 10093.9  119.14 10366.6  128.22 10643.5  128.73
#Mann= 12 ,-1 , 0
  1497.8     .11       0  1967.1     .15       0  2275.4     .11       0
  4612.2     .15       0  4707.8     .11       0 4955.51     .09       0
 5024.04     .11       0  5366.3     .15       0  5665.2    .125       0
  6024.4     .11       0  6144.2    .125       0  6383.6     .11       0
Bank Sta=4955.51,5024.04
XS Rating Curve= 0 ,0
Exp/Cntr=0.3,0.1

Type RM Length L Ch R = 1 ,500     ,0,0,0
BEGIN DESCRIPTION:
Crystal Creek 037 1.0
END DESCRIPTION:
XS GIS Cut Line= 4
      3845179.59     10087502.62       3842169.3     10085188.66
      3841808.92     10085323.34      3838625.89     10089956.99
#Sta/Elev= 30
   818.4  136.82  1270.3  111.53  1382.2  114.11  1437.3  114.34  2617.8  117.13
  2945.9  105.29  3623.3  110.35  3979.8   109.2  4079.5  108.93  4277.3  107.19
  4302.4  106.85  4373.2  104.98  4519.1  106.43  4743.9  108.18  4830.1  108.99
  4926.9   109.9 4950.46 100.514  4995.7   95.66 5022.84100.5303  5057.8  109.17
  5093.6  102.75  5272.9  110.31  5752.1  109.03  6317.6  113.01  7337.3  106.72
    7430  113.93  8559.3  111.41  9357.1   120.3 10177.7  117.99 10621.6  126.82
#Mann= 16 ,-1 , 0
   818.4     .11       0  1382.2     .15       0  1437.3     .11       0
  3623.3     .17       0  3979.8     .15       0  4079.5     .17       0
  4277.3     .11       0  4302.4     .17       0  4373.2     .15       0
  4519.1     .17       0  4743.9     .15       0  4830.1     .11       0
 4950.46     .09       0 5022.84     .15       0  5752.1     .17       0
  6317.6     .11       0
Bank Sta=4950.46,5022.84
XS Rating Curve= 0 ,0
Exp/Cntr=0.3,0.1

Chan Stop Cuts=-1
Use User Specified Reach Order=0
Composite Channel Slope=5

--- Crystal Creek 037.g10 (geometry) ---

Geom Title=Existing Conditions
Program Version=4.10

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
River Reach=Crystal Creek 03,Reach-1

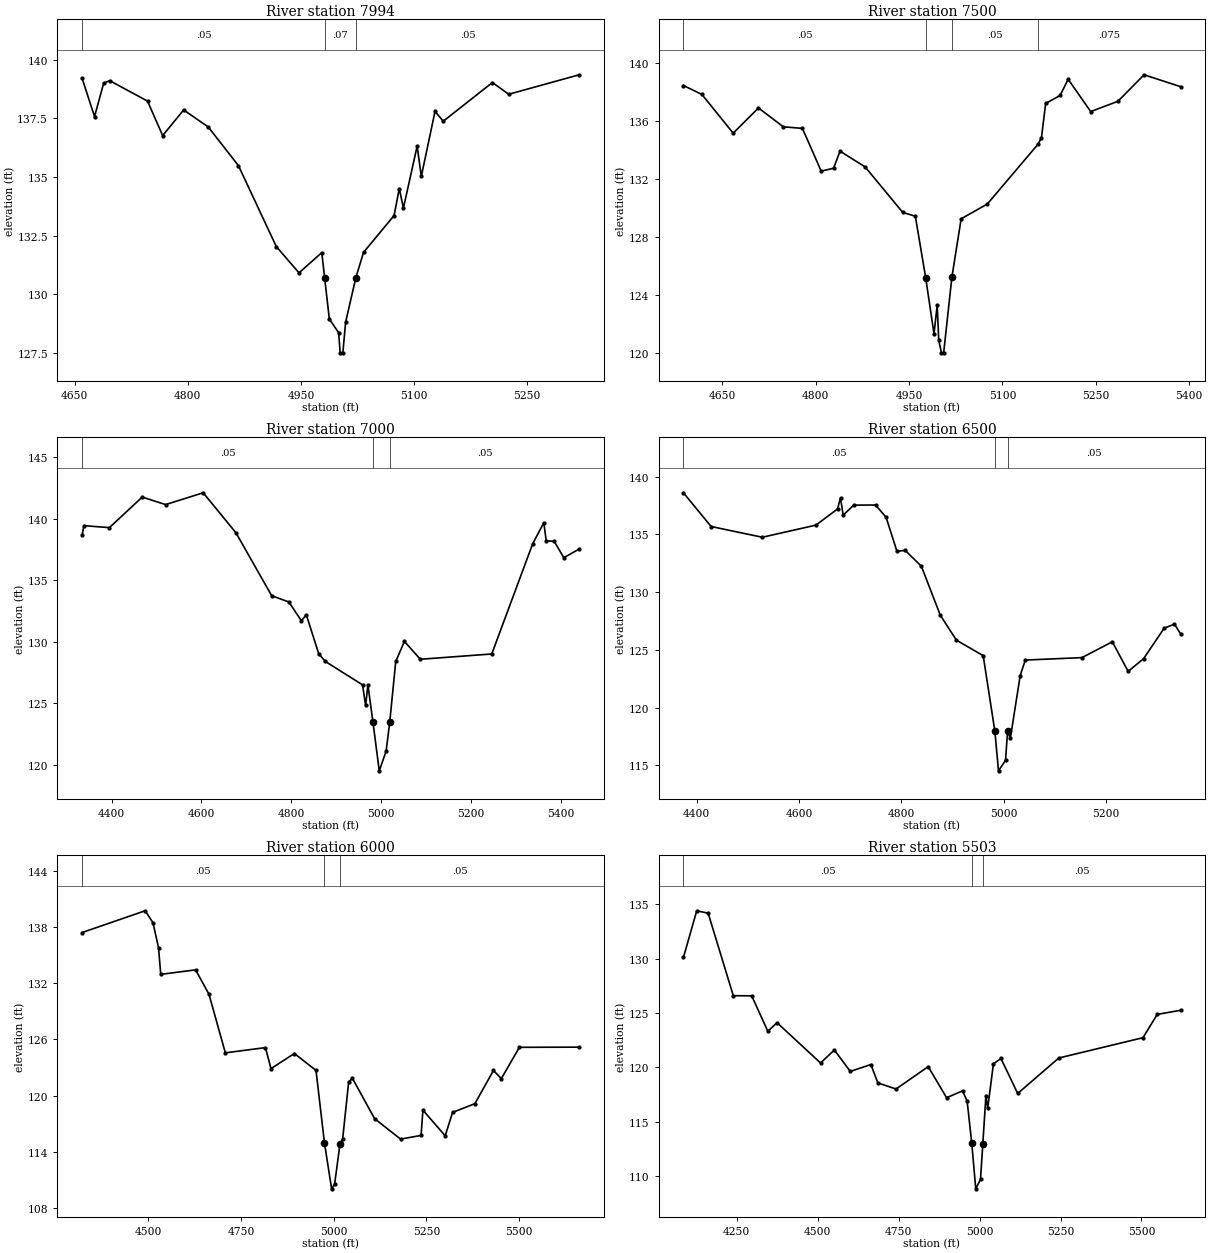
Type RM Length L Ch R = 1 ,7994    ,494,494,494
BEGIN DESCRIPTION:
Crystal Creek 037 16.0
END DESCRIPTION:
XS GIS Cut Line= 3
      3841754.24     10091343.77      3841415.61     10091374.24
       3841121.8     10091498.21
#Sta/Elev= 30
    4660  139.21  4676.5  137.58  4688.6     139  4696.5  139.11  4746.7  138.24
  4766.8  136.77  4794.6  137.86  4827.1  137.14  4867.2  135.49  4917.4  132.04
  4947.5  130.92  4977.7  131.78 4981.59 130.679  4987.7  128.95    5000  128.37
  5002.1  127.51  5005.6  127.51  5009.3  128.82 5022.76 130.701    5033  131.79
  5073.5  133.36  5080.4  134.51  5085.9  133.68  5104.1  136.32  5109.6  135.03
  5127.8   137.8  5138.7  137.38  5203.8  139.03  5225.5  138.53  5318.9  139.36
#Mann= 3 , 0 , 0
    4660     .05       0 4981.59     .07       0 5022.76     .05       0
Bank Sta=4981.59,5022.76
XS Rating Curve= 0 ,0
Exp/Cntr=0.3,0.1

Type RM Length L Ch R = 1 ,7500    ,500,500,500
BEGIN DESCRIPTION:
Crystal Creek 037 15.0
END DESCRIPTION:
XS GIS Cut Line= 3
      3841667.46     10090996.55      3841258.24     10090945.45
      3840938.25     10091161.51
#Sta/Elev= 30
  4587.6  138.44  4617.4  137.82  4667.5  135.15  4708.1  136.89  4748.1  135.59
  4778.7  135.48  4808.9  132.53  4828.8  132.73  4839.1  133.91  4879.5  132.82
  4939.9  129.68  4960.1  129.42 4976.75 125.165  4990.1   121.3  4995.2  123.28
  4997.7  120.85  5002.1  119.99  5005.6  119.99  5018.8  125.21  5033.7  129.24
  5075.7  130.26  5157.8  134.42  5162.7  134.85  5169.4   137.2  5192.6  137.75
  5205.6  138.87  5241.8  136.64  5285.5  137.35  5327.5  139.18  5386.1  138.36
#Mann= 4 ,-1 , 0
  4587.6     .05       0 4976.75     .07       0  5018.8     .05       0
  5157.8    .075       0
Bank Sta=4976.75,5018.8
XS Rating Curve= 0 ,0
Exp/Cntr=0.3,0.1

Type RM Length L Ch R = 1 ,7000    ,500,500,500
BEGIN DESCRIPTION:
Crystal Creek 037 14.0
END DESCRIPTION:
XS GIS Cut Line= 3
      3841676.09     10090727.44      3841038.24     10090536.57
      3840625.81     10090692.72
#Sta/Elev= 30
  4334.2  138.66  4338.3  139.43    4395  139.27  4468.1  141.75  4520.2  141.14
  4603.8   142.1  4676.8  138.85  4756.3  133.74  4794.7  133.23  4822.5   131.7
  4833.4   132.2  4860.9  129.04  4875.1  128.42  4958.6   126.5  4965.4  124.83
  4970.6  126.49 4981.73 123.492  4995.8  119.52  5011.1  121.11 5019.19 123.491
  5032.5   128.4  5051.8  130.03  5087.3  128.58  5246.3  129.01  5337.4  137.96
  5362.2  139.67  5367.5   138.2  5385.3  138.16  5406.7  136.83    5441  137.53
#Mann= 3 , 0 , 0
  4334.2     .05       0 4981.73     .07       0 5019.19     .05       0
Bank Sta=4981.73,5019.19
XS Rating Curve= 0 ,0
Exp/Cntr=0.3,0.1

Type RM Length L Ch R = 1 ,6500    ,500,500,500
BEGIN DESCRIPTION:
Crystal Creek 037 13.0
END DESCRIPTION:
XS GIS Cut Line= 3
      3841693.45     10090293.41      3841099.86     10090095.24
      3840755.97      10090128.5
#Sta/Elev= 30
  4374.2   138.6  4428.3  135.68  4528.3  134.75  4633.1   135.8  4675.3   137.2
  4681.1  138.15  4686.3  136.66  4706.9  137.53  4749.6  137.54  4770.2  136.48
  4791.3  133.54  4807.5  133.61  4839.1  132.24    4876  128.01  4907.6  125.84
  4959.9   124.5 4982.73 117.946  4989.8  114.53  5003.5  115.44 5007.53 117.959
  5012.9  117.34  5032.2  122.78  5042.2  124.12  5152.7  124.33  5212.2   125.7
  5243.1  123.14  5273.3  124.24  5313.5  126.88  5333.6  127.23  5345.5  126.39
#Mann= 3 , 0 , 0
  4374.2     .05       0 4982.73     .07       0 5007.53     .05       0
Bank Sta=4982.73,5007.53
XS Rating Curve= 0 ,0
Exp/Cntr=0.3,0.1

Type RM Length L Ch R = 1 ,6000    ,497,497,497
BEGIN DESCRIPTION:
Crystal Creek 037 12.0
END DESCRIPTION:
XS GIS Cut Line= 3
      3841832.42     10090041.71      3841268.24     10089664.98
      3840606.77     10089696.14
#Sta/Elev= 30
  4321.6  137.39  4491.6  139.71  4512.7  138.45  4527.7  135.78  4533.7  132.93
  4627.7  133.41  4663.8  130.81  4707.9  124.56    4816  125.12    4831  122.88
  4894.1  124.49  4952.4  122.69  4975.2  114.96  4994.5  110.06  5002.7  110.59
  5017.1 114.847  5024.3  115.38  5040.4  121.44  5050.4  121.86  5110.5  117.54
  5180.6  115.36  5235.7  115.76  5240.7  118.45  5300.7  115.72  5320.7  118.21
  5380.8  119.14  5430.9  122.68  5452.1  121.81  5500.9  125.15  5662.2  125.17
#Mann= 3 , 0 , 0
  4321.6     .05       0  4975.2     .07       0  5017.1     .05       0
Bank Sta=4975.2,5017.1
XS Rating Curve= 0 ,0
Exp/Cntr=0.3,0.1

Type RM Length L Ch R = 1 ,5503    ,503,503,503
BEGIN DESCRIPTION:
Crystal Creek 037 11.0
END DESCRIPTION:
XS GIS Cut Line= 3
      3841990.84     10089816.03      3841318.24     10089196.86
      3840752.07     10089451.03
#Sta/Elev= 30
  4085.8   130.1  4126.9  134.39  4162.1  134.17  4239.8  126.58  4296.5  126.57
  4346.4  123.31  4374.8   124.1  4509.2  120.39  4551.7  121.59    4601  119.62
  4664.5  120.25  4686.1  118.56  4742.3     118  4841.5  120.06  4898.2   117.2
  4947.5  117.83  4961.7  116.89  4975.9  113.04  4988.3  108.82    5003   109.7
 5010.14 112.964  5019.7   117.4  5025.2  116.22  5042.8  120.31    5066  120.81
  5117.8  117.59  5244.6  120.85  5504.6  122.72  5548.5  124.86  5620.6  125.24
#Mann= 3 , 0 , 0
  4085.8     .05       0  4975.9     .07       0 5010.14     .05       0
Bank Sta=4975.9,5010.14
XS Rating Curve= 0 ,0
Exp/Cntr=0.3,0.1

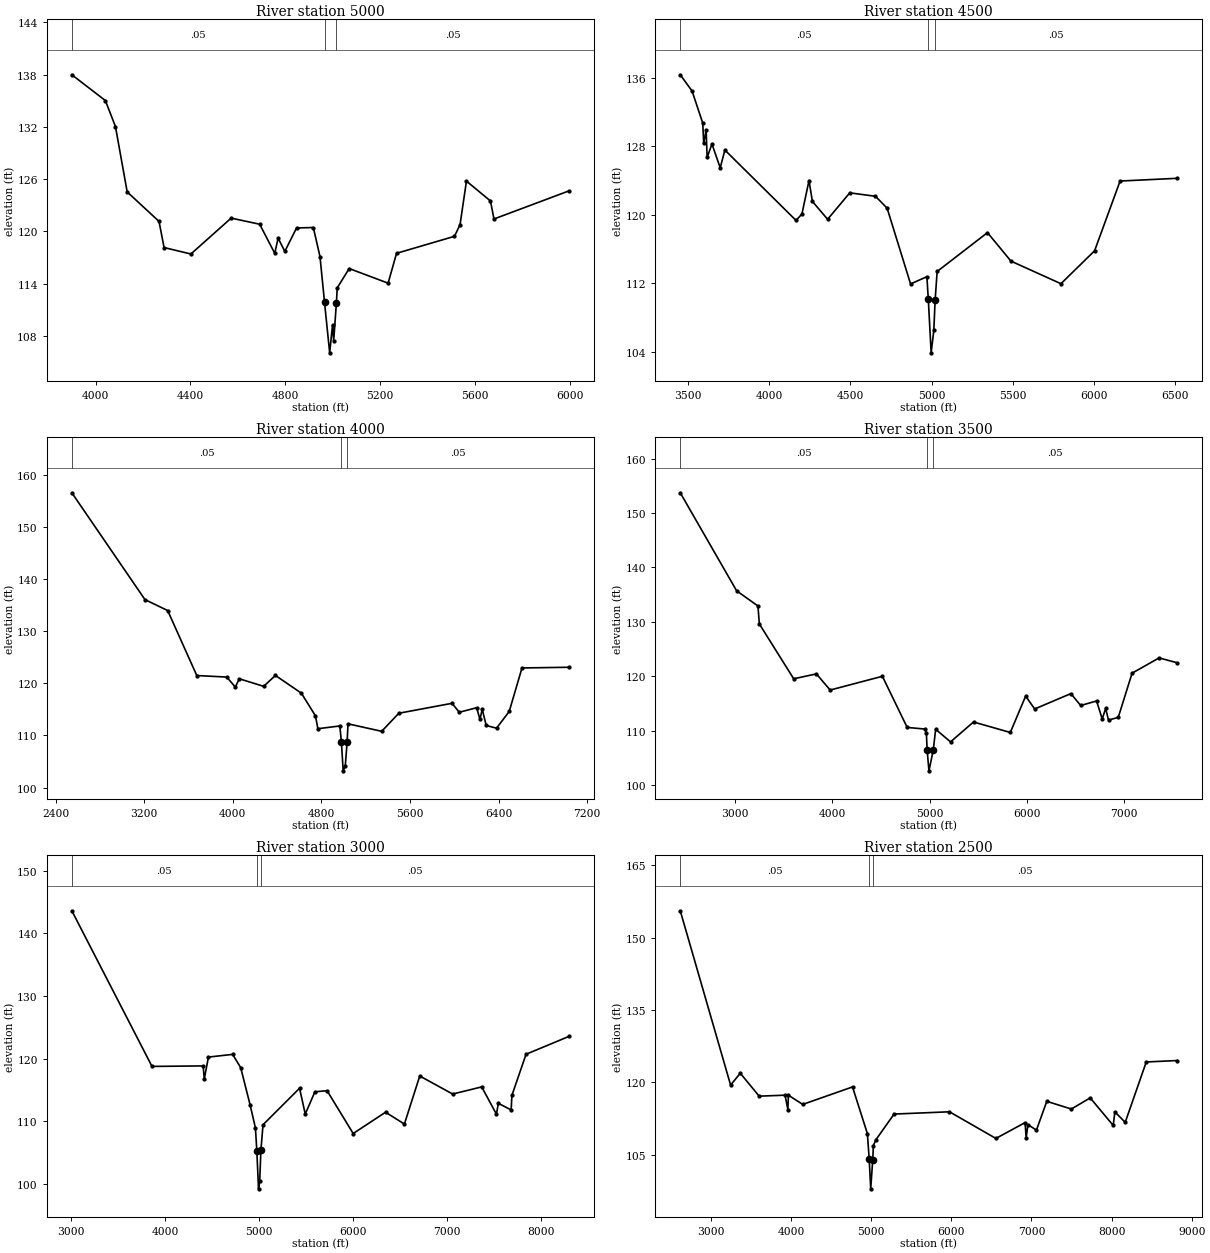
Type RM Length L Ch R = 1 ,5000    ,500,500,500
BEGIN DESCRIPTION:
Crystal Creek 037 10.0
END DESCRIPTION:
XS GIS Cut Line= 3
      3842317.87     10089561.09      3841538.24      10088785.1
      3840722.58     10089355.83
#Sta/Elev= 30
    3900  137.98  4041.4  135.02  4083.9  132.04  4133.4  124.53  4267.7  121.14
  4288.9  118.14  4402.1   117.4  4571.8  121.52    4692  120.82  4755.6  117.48
  4769.8  119.22  4798.1   117.7  4847.5  120.39  4918.3  120.44  4946.5  117.08
 4965.47 111.846  4987.2  106.05  4999.3  109.25  5004.1  107.46 5015.68 111.818
    5019  113.51  5069.5  115.73  5233.5  114.05  5269.2  117.48  5513.4  119.43
  5536.9  120.77  5563.9  125.77  5665.1  123.49  5679.9  121.42  5995.5  124.64
#Mann= 3 , 0 , 0
    3900     .05       0 4965.47     .07       0 5015.68     .05       0
Bank Sta=4965.47,5015.68
XS Rating Curve= 0 ,0
Exp/Cntr=0.3,0.1

Type RM Length L Ch R = 1 ,4500    ,500,500,500
BEGIN DESCRIPTION:
Crystal Creek 037 9.0
END DESCRIPTION:
XS GIS Cut Line= 4
      3842943.92     10089206.61      3841671.53     10088328.12
      3841350.18     10088388.91      3840652.96     10089346.29
#Sta/Elev= 30
  3453.8  136.35  3526.6  134.45  3592.2   130.7  3598.2  128.33  3613.1  129.88
  3619.2  126.69  3648.9  128.26  3699.6  125.48  3728.5  127.55    4166  119.33
  4202.4  120.07  4245.9  123.99  4266.8  121.55  4360.4  119.46  4496.7  122.55
  4654.9  122.15  4726.5  120.76  4870.8   111.9  4971.2  112.75    4980  110.09
  4997.4  103.85  5013.9   106.5 5021.77  109.98  5034.3  113.36  5343.9   117.9
  5488.4  114.57  5795.9  111.93    6003  115.78  6159.8  123.93  6511.4  124.25
#Mann= 3 , 0 , 0
  3453.8     .05       0    4980     .07       0 5021.77     .05       0
Bank Sta=4980,5021.77
XS Rating Curve= 0 ,0
Exp/Cntr=0.3,0.1

Type RM Length L Ch R = 1 ,4000    ,500,500,500
BEGIN DESCRIPTION:
Crystal Creek 037 8.0
END DESCRIPTION:
XS GIS Cut Line= 4
      3843767.85     10089461.07      3841890.35     10087881.78
      3841496.01     10088029.54      3840558.48     10089342.08
#Sta/Elev= 30
  2546.6   156.6  3206.7  136.09  3412.2  133.98  3674.9   121.5  3944.8  121.21
  4023.2  119.29  4058.6  120.88  4278.4  119.43    4385  121.52  4619.1  118.12
  4746.6  113.75  4768.1  111.29  4966.4  111.82  4980.7  108.78  4996.6   103.2
  5015.5   104.1 5032.24 108.717  5040.4  112.23  5344.4  110.79  5499.1  114.26
  5979.6  116.17  6044.8  114.45  6202.1  115.32  6231.6  113.09  6252.4  115.02
  6288.1  111.91  6381.5  111.39  6495.8   114.6  6611.3  122.96  7034.1  123.09
#Mann= 3 , 0 , 0
  2546.6     .05       0  4980.7     .07       0 5032.24     .05       0
Bank Sta=4980.7,5032.24
XS Rating Curve= 0 ,0
Exp/Cntr=0.3,0.1

Type RM Length L Ch R = 1 ,3500    ,500,500,500
BEGIN DESCRIPTION:
Crystal Creek 037 7.0
END DESCRIPTION:
XS GIS Cut Line= 4
      3843767.87      10089311.1      3842019.16     10087434.87
      3841850.18     10087409.75      3840449.13     10089331.63
#Sta/Elev= 30
  2435.2   153.7  3015.4  135.68  3234.8  132.89  3248.9   129.6  3602.6  119.51
  3836.2  120.41  3977.8  117.44  4515.2  119.97  4770.3  110.57    4954  110.27
  4968.1  109.46  4975.5  106.43  4994.3  102.59 5038.84  106.42  5063.4  110.23
  5216.5  107.91  5452.9  111.57  5831.5  109.64  5989.2  116.32  6082.5  113.96
  6454.9  116.79  6555.3   114.6  6719.4  115.43    6777  112.13  6812.6  114.05
  6841.9  111.92  6942.1  112.41  7084.5  120.54  7362.9  123.35  7549.2  122.45
#Mann= 3 , 0 , 0
  2435.2     .05       0  4975.5     .07       0 5038.84     .05       0
Bank Sta=4975.5,5038.84
XS Rating Curve= 0 ,0
Exp/Cntr=0.3,0.1

Type RM Length L Ch R = 1 ,3000    ,500,500,500
BEGIN DESCRIPTION:
Crystal Creek 037 6.0
END DESCRIPTION:
XS GIS Cut Line= 4
      3843667.85     10088911.07      3842495.98     10087299.13
      3841996.01     10087107.66      3840355.52     10089326.24
#Sta/Elev= 30
  3007.1  143.61    3860  118.77    4404  118.85  4416.5  116.78  4460.5  120.26
  4717.8  120.69  4803.6  118.58  4904.1  112.61  4960.5  108.94  4975.2   105.3
  4993.6   99.23    5006  100.45  5018.5 105.379  5041.3  109.46  5429.8  115.28
  5490.6  111.17  5593.4  114.72  5722.8  114.89  6000.4  108.06  6344.9  111.46
  6545.3  109.57  6708.7  117.24  7058.8  114.36  7367.8   115.5  7524.3  111.15
  7545.2  112.88  7680.9  111.82  7689.3  114.15  7839.6  120.71  8294.6  123.55
#Mann= 3 , 0 , 0
  3007.1     .05       0  4975.2     .07       0  5018.5     .05       0
Bank Sta=4975.2,5018.5
XS Rating Curve= 0 ,0
Exp/Cntr=0.3,0.1

Type RM Length L Ch R = 1 ,2500    ,500,500,500
BEGIN DESCRIPTION:
Crystal Creek 037 5.0
END DESCRIPTION:
XS GIS Cut Line= 4
      3844667.85     10088311.07      3842755.65     10086886.02
      3842235.59      10086696.2      3840277.25      10089310.8
#Sta/Elev= 30
  2615.2  155.55  3243.9  119.44  3364.8   121.9  3600.5  117.15  3923.7  117.35
  3959.1  114.36  3965.4  117.35  4144.7  115.44  4766.1  119.06  4951.7  109.39
 4974.83 104.032  4993.3   97.95 5018.52 103.984  5026.6  106.92  5057.2   108.1
  5285.1  113.44  5976.7  113.91    6556  108.39  6920.7  111.67    6934   108.5
  6956.1  111.25  7062.3  110.11  7191.5  116.08  7497.8  114.48  7733.7  116.79
  8020.9  111.08  8041.7  113.88  8170.9  111.73  8433.4  124.23  8820.3  124.53
#Mann= 3 , 0 , 0
  2615.2     .05       0 4974.83     .07       0 5018.52     .05       0
Bank Sta=4974.83,5018.52
XS Rating Curve= 0 ,0
Exp/Cntr=0.3,0.1