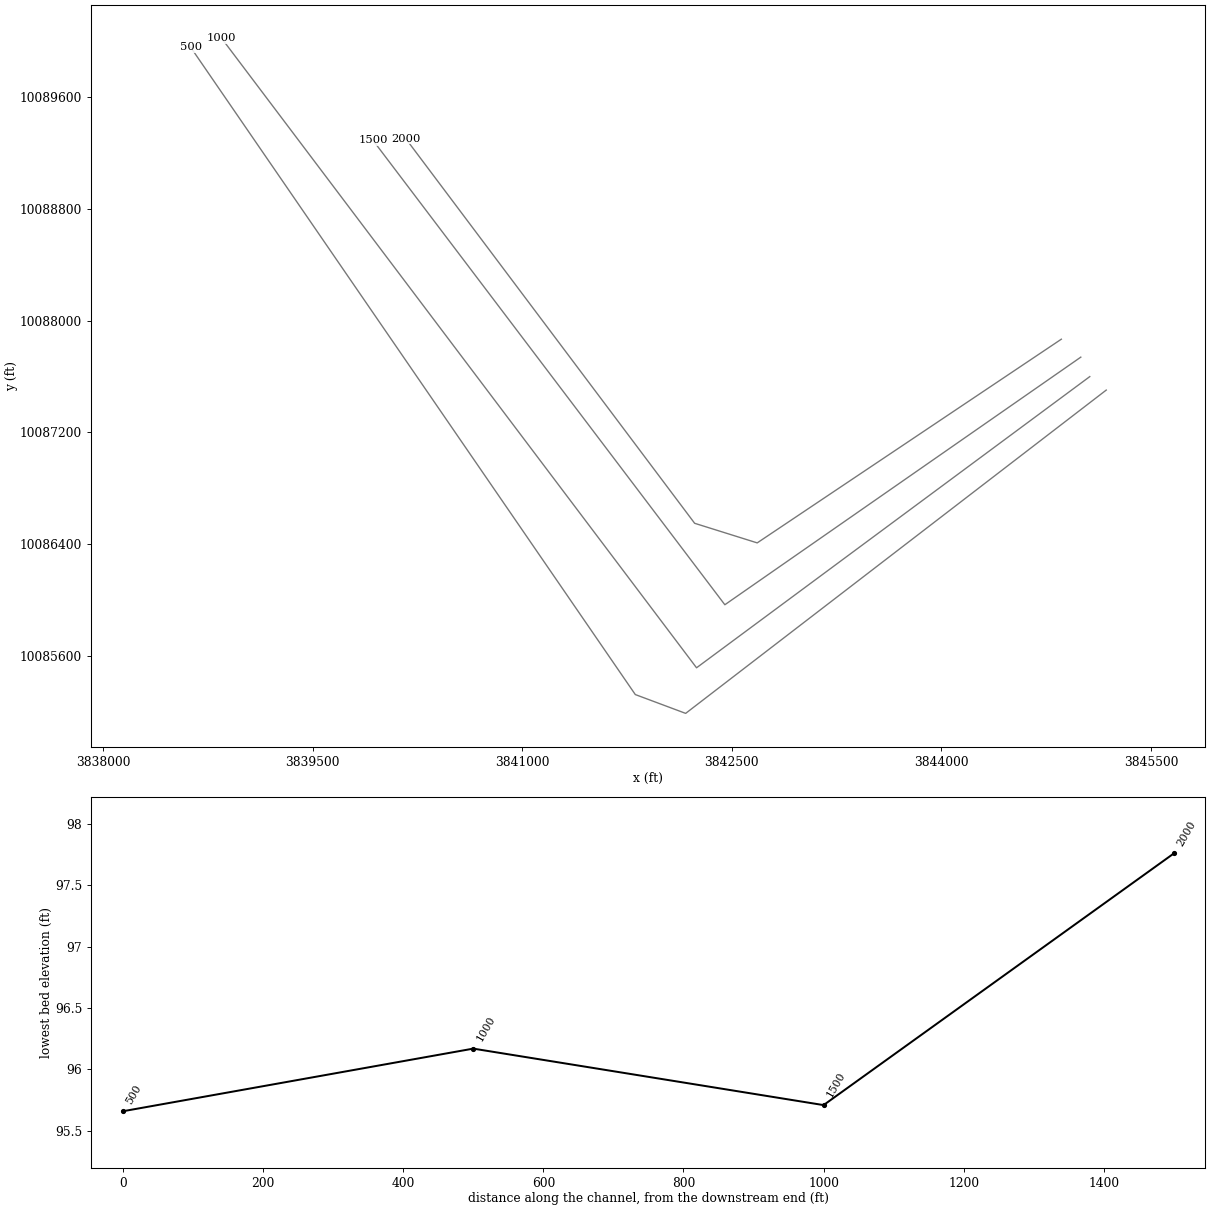
HEC-RAS study Crystal Creek 037.prj: Crystal Creek 037 Base Level Engineering

--- Crystal Creek 037.g10 (geometry) --- (continued)

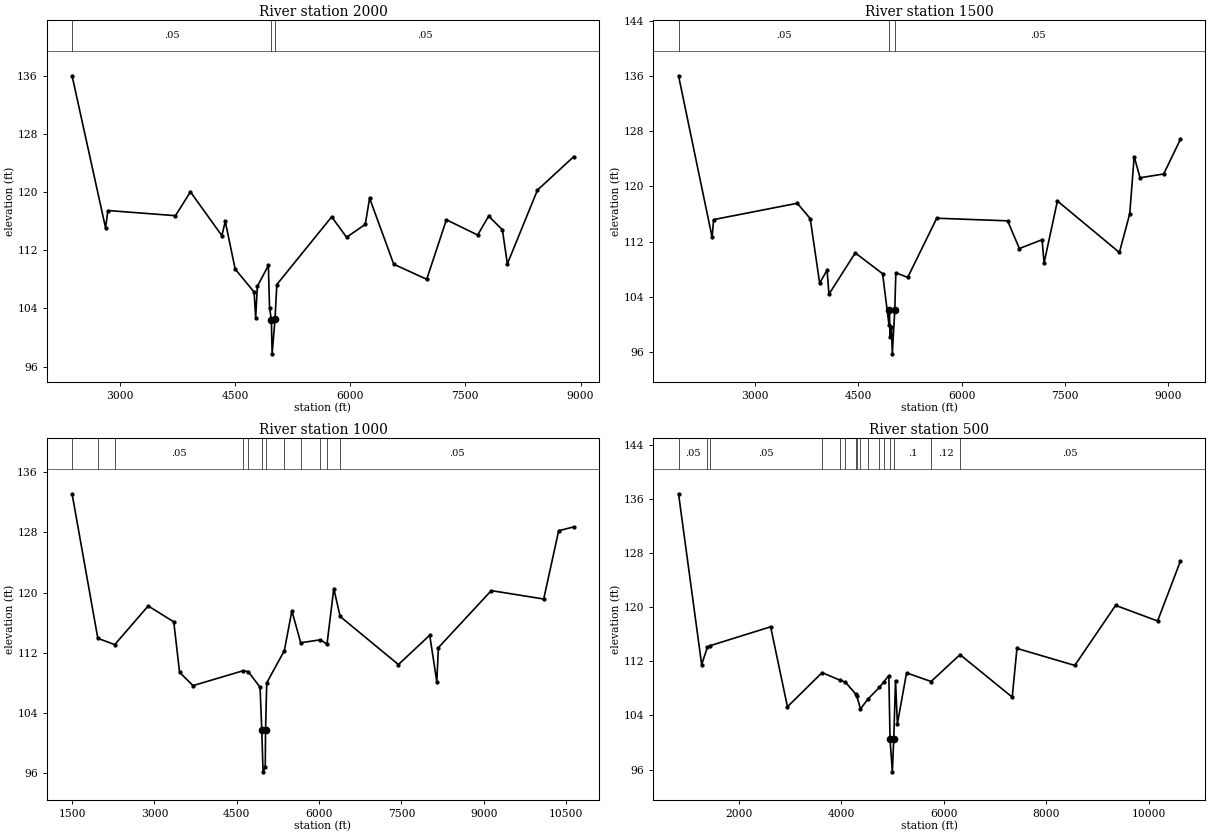
Type RM Length L Ch R = 1 ,2000    ,500,500,500
BEGIN DESCRIPTION:
Crystal Creek 037 4.0
END DESCRIPTION:
XS GIS Cut Line= 4
      3844858.18     10087866.85      3842681.42     10086408.91
      3842233.57     10086549.19        3840166.     10089302.38
#Sta/Elev= 30
  2380.1  136.02  2816.3  115.09  2846.3  117.48  3725.9  116.77    3921  120.05
  4330.3  114.02  4374.3  115.99  4503.4  109.42  4749.5  106.27  4770.5  102.76
  4791.6  107.04  4935.7  109.92  4950.7  104.13 4973.98 102.471  4984.5   97.76
  5021.7  102.51  5045.7   107.3  5759.6  116.61  5953.3   113.8    6197  115.57
  6253.2  119.18  6567.8  110.09  6996.8  108.02  7253.1  116.21  7660.2  114.11
    7803  116.71  7982.1  114.83  8046.7  110.14  8438.3  120.29  8912.4  124.91
#Mann= 3 , 0 , 0
  2380.1     .05       0 4973.98     .07       0  5021.7     .05       0
Bank Sta=4973.98,5021.7
XS Rating Curve= 0 ,0
Exp/Cntr=0.3,0.1

Type RM Length L Ch R = 1 ,1500    ,500,500,500
BEGIN DESCRIPTION:
Crystal Creek 037 3.0
END DESCRIPTION:
XS GIS Cut Line= 3
      3844997.52     10087738.34      3842449.76     10085966.16
      3839930.33     10089291.65
#Sta/Elev= 30
  1896.5  136.06  2383.4  112.62    2405  115.19  3618.2  117.56  3805.9  115.33
  3942.6  105.97  4050.3  107.86  4077.3  104.36  4458.8  110.36  4855.1  107.34
  4947.6   99.96  4953.7  102.06  4962.4   98.15  4983.3   99.65  4995.9   95.71
 5031.89 102.012  5047.3  107.48  5219.4   106.8  5640.2  115.39  6667.9  115.01
  6838.6  110.99  7167.3  112.27  7196.4   108.9  7389.8  117.89  8288.6  110.42
  8438.4  116.02  8502.9  124.34  8588.2  121.26  8931.4  121.81  9172.1  126.82
#Mann= 3 , 0 , 0
  1896.5     .05       0  4953.7     .07       0 5031.89     .05       0
Bank Sta=4953.7,5031.89
XS Rating Curve= 0 ,0
Exp/Cntr=0.3,0.1

Type RM Length L Ch R = 1 ,1000    ,500,500,500
BEGIN DESCRIPTION:
Crystal Creek 037 2.0
END DESCRIPTION:
XS GIS Cut Line= 3
      3845061.76     10087599.04      3842247.17     10085514.93
      3838848.32     10090020.14
#Sta/Elev= 30
  1497.8  133.13  1967.1  113.92  2275.4  113.08  2885.4  118.22  3350.9  116.11
  3457.3   109.4  3701.5  107.63  4612.2   109.6  4707.8   109.5  4924.5  107.42
 4955.51 101.672  4978.7   96.17  5018.9   96.79 5024.04 101.681    5046     108
  5366.3  112.27  5503.9  117.57  5665.2  113.33  6024.4  113.72  6144.2  113.14
  6267.9  120.53  6383.6  116.82  7446.1  110.43  8016.4  114.33  8145.5  108.16
  8174.6  112.68  9138.4  120.26 10093.9  119.14 10366.6  128.22 10643.5  128.73
#Mann= 12 ,-1 , 0
  1497.8     .05       0  1967.1      .1       0  2275.4     .05       0
  4612.2      .1       0  4707.8     .05       0 4955.51     .07       0
 5024.04     .05       0  5366.3      .1       0  5665.2    .075       0
  6024.4     .05       0  6144.2    .075       0  6383.6     .05       0
Bank Sta=4955.51,5024.04
XS Rating Curve= 0 ,0
Exp/Cntr=0.3,0.1

Type RM Length L Ch R = 1 ,500     ,0,0,0
BEGIN DESCRIPTION:
Crystal Creek 037 1.0
END DESCRIPTION:
XS GIS Cut Line= 4
      3845179.59     10087502.62       3842169.3     10085188.66
      3841808.92     10085323.34      3838625.89     10089956.99
#Sta/Elev= 30
   818.4  136.82  1270.3  111.53  1382.2  114.11  1437.3  114.34  2617.8  117.13
  2945.9  105.29  3623.3  110.35  3979.8   109.2  4079.5  108.93  4277.3  107.19
  4302.4  106.85  4373.2  104.98  4519.1  106.43  4743.9  108.18  4830.1  108.99
  4926.9   109.9 4950.46 100.514  4995.7   95.66 5022.84  100.53  5057.8  109.17
  5093.6  102.75  5272.9  110.31  5752.1  109.03  6317.6  113.01  7337.3  106.72
    7430  113.93  8559.3  111.41  9357.1   120.3 10177.7  117.99 10621.6  126.82
#Mann= 16 ,-1 , 0
   818.4     .05       0  1382.2      .1       0  1437.3     .05       0
  3623.3     .12       0  3979.8      .1       0  4079.5     .12       0
  4277.3     .05       0  4302.4     .12       0  4373.2      .1       0
  4519.1     .12       0  4743.9      .1       0  4830.1     .05       0
 4950.46     .07       0 5022.84      .1       0  5752.1     .12       0
  6317.6     .05       0
Bank Sta=4950.46,5022.84
XS Rating Curve= 0 ,0
Exp/Cntr=0.3,0.1