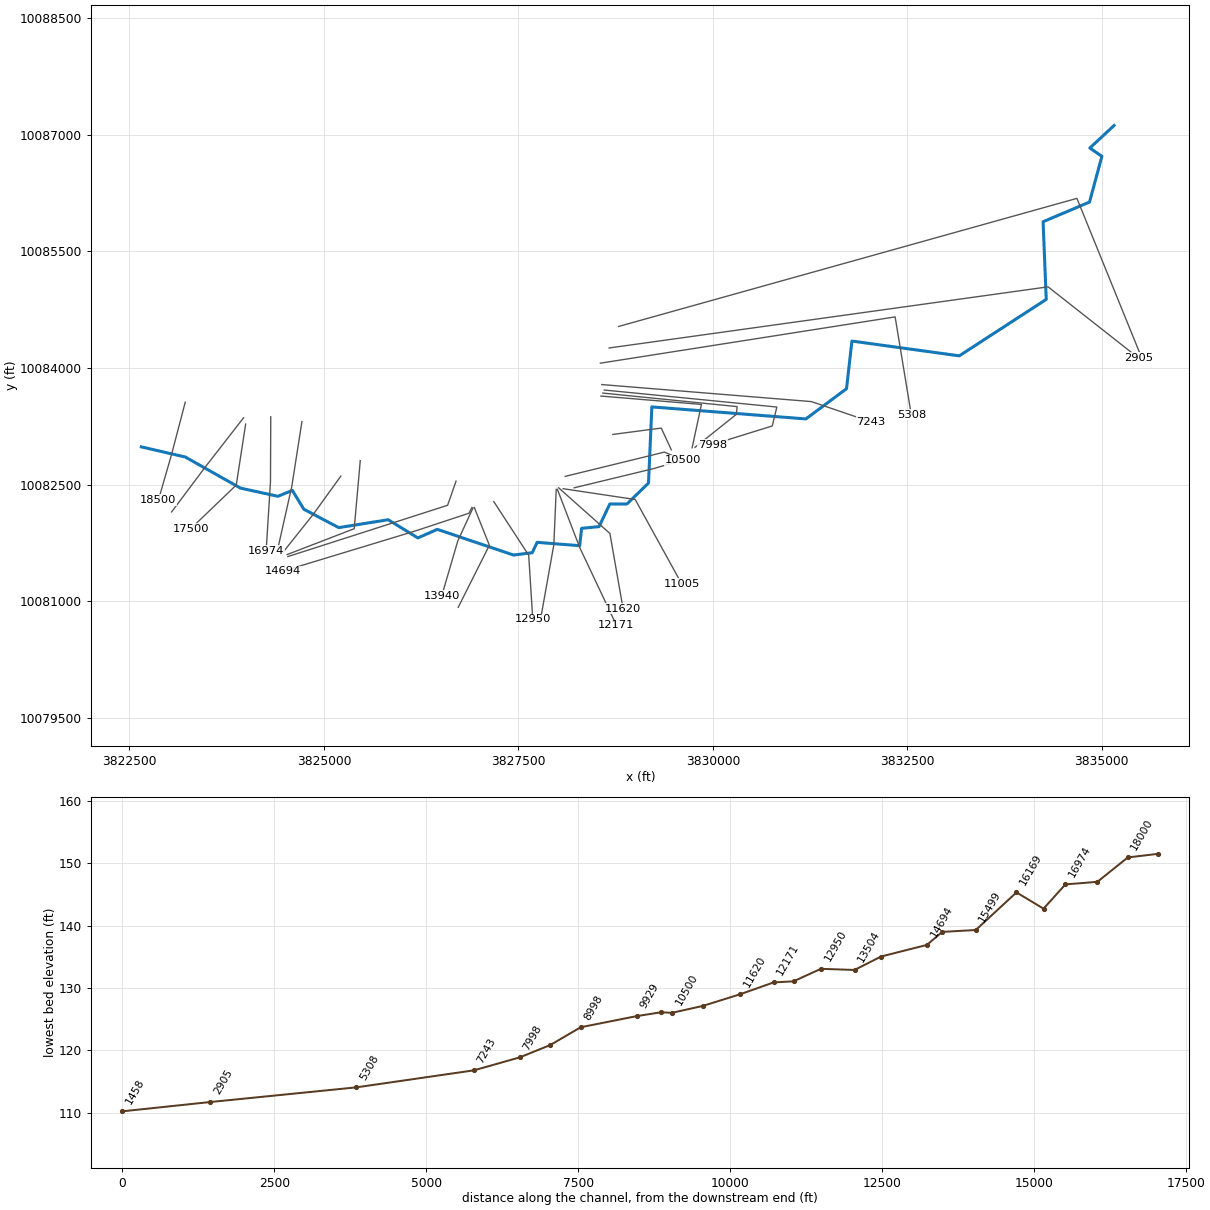
--- Crystal Creek 038.prj (project) ---

Proj Title=Crystal Creek 038 Base Level Engineering
Current Plan=p01
Default Exp/Contr=0.3,0.1
English Units
Geom File=g01
Flow File=f01
Flow File=f02
Plan File=p01
Y Axis Title=Elevation
X Axis Title(PF)=Main Channel Distance
X Axis Title(XS)=Station
BEGIN DESCRIPTION:
Crystal Creek 038
END DESCRIPTION:
DSS Export Rating Curves= 0
DSS Export Rating Curve Sorted= 0
DSS Export Volume Flow Curves= 0
DXF OffsetX= 0
DXF OffsetY= 0
DXF ScaleX= 1
DXF ScaleY= 10

--- Crystal Creek 038.p01 (plan) ---

Plan Title=Multiple Run
Short Identifier=Multiple
Geom File=g01
Flow File=f01
Subcritical Flow
K Sum by GR= 0
Std Step Tol= 0.01
Critical Tol= 0.01
Num of Std Step Trials= 20
Max Error Tol= 0.3
Flow Tol Ratio= 0.001
Split Flow NTrial= 30
Split Flow Tol= 0.02
Split Flow Ratio= 0.02
Log Output Level= 0
Friction Slope Method= 1
Unsteady Friction Slope Method= 2
Unsteady Bridges Friction Slope Method= 1
Parabolic Critical Depth
Global Vel Dist=  1 , 1 , 1
Global Log Level= 0
CheckData=True
Encroach Param= -1, 0, 0, 0
BEGIN DESCRIPTION:
Multiple Run
END DESCRIPTION:

--- Crystal Creek 038.f01 (steady flow) ---

Flow Title=Multiple
Program Version=4.10
Number of Profiles= 7
Profile Names=10-year,25-year,50-year,1pct_min,100-year,1pct_plu,500-year
River Rch & RM=Crystal Creek 03,Reach-1         ,18500
     701     945    1272     564    1702    5140    3146
River Rch & RM=Crystal Creek 03,Reach-1         ,16974
    1036    1420    1934     864    2610    7882    4916
River Rch & RM=Crystal Creek 03,Reach-1         ,5308
    1238    1709    2338    1049    3167    9564    6013
Boundary for River Rch & Prof#=Crystal Creek 03,Reach-1         , 1
Up Type= 0
Dn Type= 3
Dn Slope=0.001
Boundary for River Rch & Prof#=Crystal Creek 03,Reach-1         , 2
Up Type= 0
Dn Type= 3
Dn Slope=0.001
Boundary for River Rch & Prof#=Crystal Creek 03,Reach-1         , 3
Up Type= 0
Dn Type= 3
Dn Slope=0.001
Boundary for River Rch & Prof#=Crystal Creek 03,Reach-1         , 4
Up Type= 0
Dn Type= 3
Dn Slope=0.001
Boundary for River Rch & Prof#=Crystal Creek 03,Reach-1         , 5
Up Type= 0
Dn Type= 3
Dn Slope=0.001
Boundary for River Rch & Prof#=Crystal Creek 03,Reach-1         , 6
Up Type= 0
Dn Type= 3
Dn Slope=0.001
Boundary for River Rch & Prof#=Crystal Creek 03,Reach-1         , 7
Up Type= 0
Dn Type= 3
Dn Slope=0.001
DSS Import GetInterval= 0
DSS Import GetPeak= 0
DSS Import FillOption= 0

--- Crystal Creek 038.f02 (steady flow) ---

Flow Title=Orig_BLE_Flow
Program Version=4.10
Number of Profiles= 7
Profile Names=10-year,25-year,50-year,1pct_min,100-year,1pct_plu,500-year
River Rch & RM=Crystal Creek 03,Reach-1         ,18500
     701     926    1106     433    1309    3953    1829
River Rch & RM=Crystal Creek 03,Reach-1         ,16974
    1036    1392    1682     665    2008    6063    2858
River Rch & RM=Crystal Creek 03,Reach-1         ,5308
    1238    1675    2033     807    2436    7357    3496
Boundary for River Rch & Prof#=Crystal Creek 03,Reach-1         , 1
Up Type= 0
Dn Type= 3
Dn Slope=0.001
Boundary for River Rch & Prof#=Crystal Creek 03,Reach-1         , 2
Up Type= 0
Dn Type= 3
Dn Slope=0.001
Boundary for River Rch & Prof#=Crystal Creek 03,Reach-1         , 3
Up Type= 0
Dn Type= 3
Dn Slope=0.001
Boundary for River Rch & Prof#=Crystal Creek 03,Reach-1         , 4
Up Type= 0
Dn Type= 3
Dn Slope=0.001
Boundary for River Rch & Prof#=Crystal Creek 03,Reach-1         , 5
Up Type= 0
Dn Type= 3
Dn Slope=0.001
Boundary for River Rch & Prof#=Crystal Creek 03,Reach-1         , 6
Up Type= 0
Dn Type= 3
Dn Slope=0.001
Boundary for River Rch & Prof#=Crystal Creek 03,Reach-1         , 7
Up Type= 0
Dn Type= 3
Dn Slope=0.001
DSS Import GetInterval= 0
DSS Import GetPeak= 0
DSS Import FillOption= 0

--- Crystal Creek 038.g01 (geometry) ---

Geom Title=Existing Conditions
Program Version=4.10

River Reach=Crystal Creek 03,Reach-1
Reach XY= 30
      3822653.24     10082986.86      3823218.24     10082856.86
      3823928.24     10082456.86      3824409.34     10082351.93
      3824594.76     10082427.55      3824742.07     10082185.63
      3825191.44     10081948.99      3825826.68     10082050.74
      3826208.24     10081816.86      3826458.24     10081926.86
      3827438.24     10081596.86      3827678.24     10081626.86
      3827741.85     10081760.05      3828288.24     10081716.86
      3828313.42     10081940.16      3828537.58     10081962.19
      3828675.44     10082251.88      3828896.73     10082253.73
       3829173.3     10082522.01      3829216.25     10083500.55
      3831196.18     10083346.11      3831718.63     10083734.27
      3831788.24     10084346.86      3833168.24     10084156.86
      3834286.14     10084882.14      3834245.79     10085880.23
      3834842.52     10086132.94      3835001.79     10086721.17
      3834846.77     10086827.35      3835158.24     10087116.86

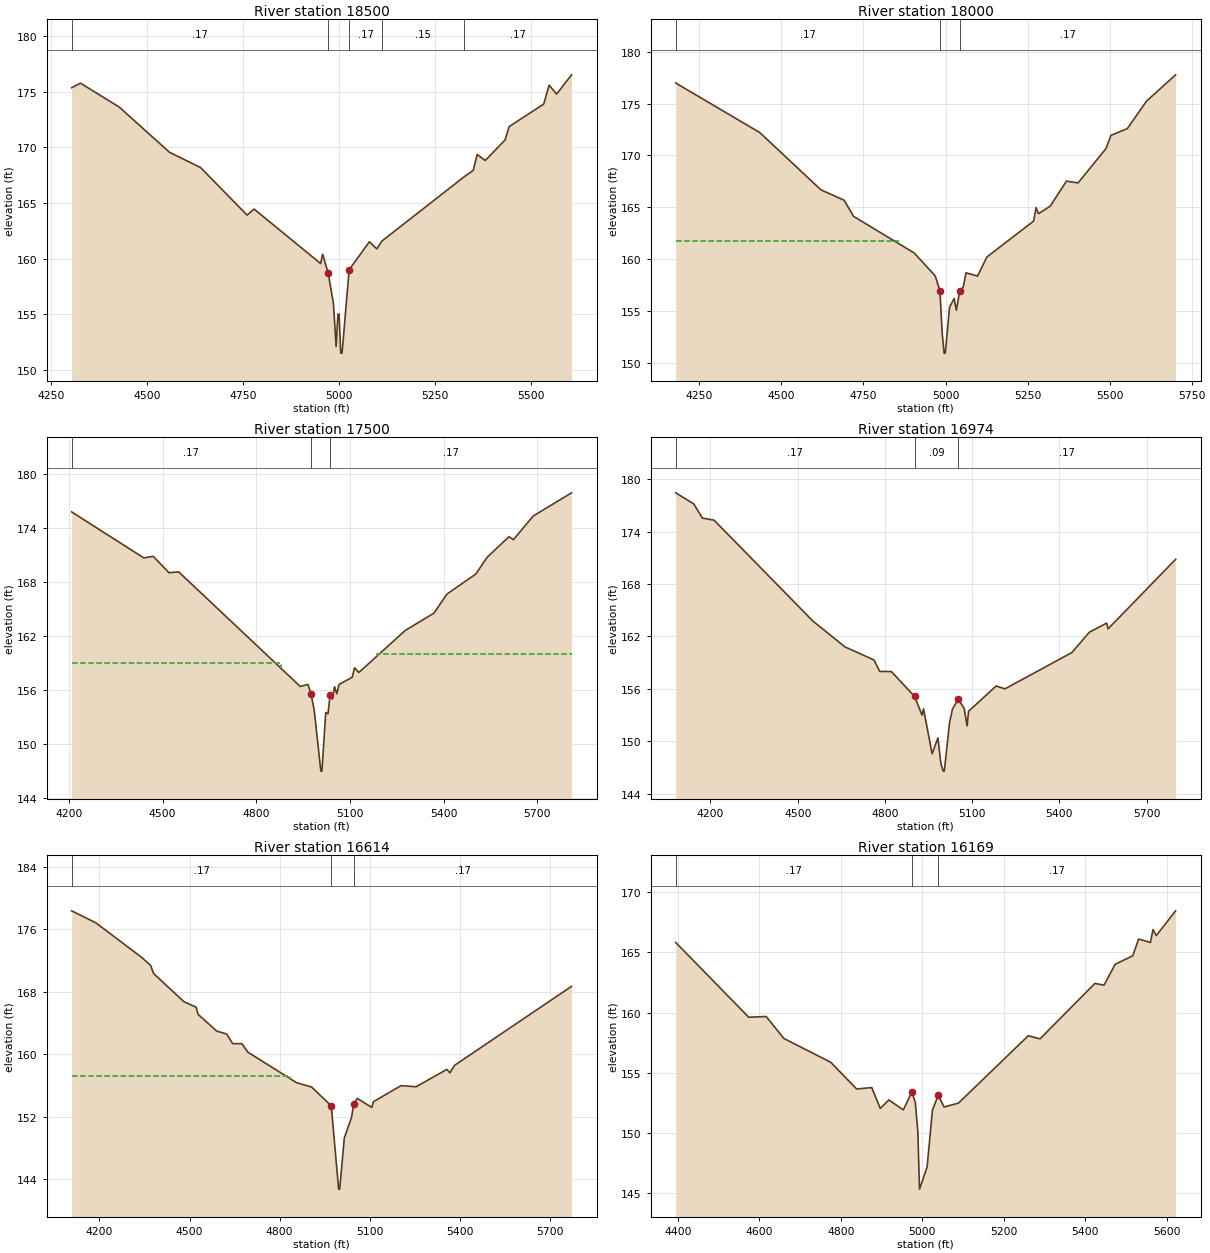
Type RM Length L Ch R = 1 ,18500   ,500,500,500
BEGIN DESCRIPTION:
Crystal Creek 038 37.0
END DESCRIPTION:
XS GIS Cut Line= 3
      3823217.85     10083561.05      3823041.39     10082886.86
      3822873.19     10082304.88
#Sta/Elev= 30
  4303.1  175.37  4325.9  175.78  4427.1  173.63  4558.1  169.56  4638.9  168.19
  4760.2  163.91  4778.6  164.45  4951.9  159.55  4957.1  160.39 4971.64158.6857
  4985.3  155.95  4992.3  152.09  4997.1     155    5000     155  5004.3  151.49
  5007.8  151.49  5026.2  158.99  5078.9  161.51  5098.6  160.87  5111.5  161.57
  5326.1  167.36  5349.5  167.93    5360  169.37  5380.8  168.82  5432.8  170.68
  5443.2  171.87  5533.3   173.9  5547.3   175.6    5567   174.8  5605.8  176.53
#Mann= 5 ,-1 , 0
  4303.1     .17       0 4971.64     .09       0  5026.2     .17       0
  5111.5     .15       0  5326.1     .17       0
Bank Sta=4971.64,5026.2
XS Rating Curve= 0 ,0
Exp/Cntr=0.3,0.1

Type RM Length L Ch R = 1 ,18000   ,500,500,500
BEGIN DESCRIPTION:
Crystal Creek 038 36.0
END DESCRIPTION:
XS GIS Cut Line= 3
      3823967.83     10083361.04       3823463.1       10082712.
      3823042.93     10082150.75
#Sta/Elev= 30
  4177.8  176.98  4433.9   172.2  4620.3  166.67  4690.9  165.67  4719.8  164.11
  4904.4  160.58  4968.7  158.36  4983.1  156.89  4989.5  152.97  4995.7  150.91
  4999.2  150.91  5012.3  155.33  5026.1  156.18  5033.1  155.05 5043.23156.9082
  5053.9  157.26  5062.3  158.66  5097.7  158.35  5126.1  160.19  5268.6  163.66
    5276  164.95  5283.2  164.37  5318.6  165.08  5368.6  167.51    5404  167.34
  5489.4  170.67    5504  171.93  5554.1  172.58  5612.4  175.23  5701.1  177.77
#Mann= 3 , 0 , 0
  4177.8     .17       0  4983.1     .09       0 5043.23     .17       0
#XS Ineff= 2 , 0
       0  4854.6  161.74               0
Permanent Ineff=
       F       F
Bank Sta=4983.1,5043.23
XS Rating Curve= 0 ,0
Exp/Cntr=0.3,0.1

Type RM Length L Ch R = 1 ,17500   ,526,526,526
BEGIN DESCRIPTION:
Crystal Creek 038 35.0
END DESCRIPTION:
XS GIS Cut Line= 3
      3823994.33     10083279.26      3823873.99     10082496.86
      3823289.78     10081935.79
#Sta/Elev= 30
  4208.4  175.82  4439.3  170.71  4469.6  170.88  4520.2  169.06  4551.3  169.15
  4940.9  156.41  4965.4  156.64  4975.5  155.57  4985.6  153.76  5006.8     147
  5010.3     147  5022.4  153.52  5029.7  153.38  5036.6  155.49  5043.8     155
  5050.7  156.38    5058  155.59  5064.9  156.63  5107.3  157.44  5114.6  158.48
  5128.7  157.97  5277.2  162.64    5369  164.56  5411.4   166.7  5503.6  168.92
  5538.8  170.74  5609.6  173.07  5623.7  172.73  5687.5  175.37    5810  177.94
#Mann= 3 , 0 , 0
  4208.4     .17       0  4975.5     .09       0  5036.6     .17       0
#XS Ineff= 2 , 0
       0  4877.6  158.99  5185.3       0  159.97
Permanent Ineff=
       F       F
Bank Sta=4975.5,5036.6
XS Rating Curve= 0 ,0
Exp/Cntr=0.3,0.1

Type RM Length L Ch R = 1 ,16974   ,360,360,360
BEGIN DESCRIPTION:
Crystal Creek 038 34.0
END DESCRIPTION:
XS GIS Cut Line= 3
      3824317.25     10083372.98      3824313.77     10082539.65
      3824258.27     10081655.12
#Sta/Elev= 30
  4080.4  178.43  4142.3  177.17  4172.3  175.54  4212.3   175.3  4552.3  163.76
  4662.3  160.81  4762.3  159.31  4782.3     158  4822.3  157.98  4902.3  155.13
  4927.9  152.99  4932.9  153.71  4962.4  148.58  4982.4  150.39  4992.5  147.47
  5000.7  146.59  5004.3  146.59  5022.5  152.17  5032.5  153.69  5052.6  154.84
  5072.6  153.77  5082.6  151.77  5087.9  153.44  5182.8  156.33  5212.9     156
  5443.4  160.16  5503.5  162.49  5562.9  163.53  5567.9  162.87    5800  170.82
#Mann= 3 , 0 , 0
  4080.4     .17       0  4902.3     .09       0  5052.6     .17       0
#XS Ineff= 2 , 0
       0  4822.3  157.98               0
Permanent Ineff=
       F       F
Bank Sta=4902.3,5052.6
XS Rating Curve= 0 ,0
Exp/Cntr=0.3,0.1

Type RM Length L Ch R = 1 ,16614   ,445,445,445
BEGIN DESCRIPTION:
Crystal Creek 038 33.0
END DESCRIPTION:
XS GIS Cut Line= 3
      3824717.85     10083311.04      3824588.08     10082480.62
      3824407.64     10081675.59
#Sta/Elev= 30
  4107.3  178.34  4188.2   176.8  4340.1  172.39  4370.4  171.35  4380.5   170.3
  4481.8  166.69  4522.2     166  4527.8  165.11  4590.5  162.94  4623.5  162.57
  4643.7  161.33  4674.1  161.33  4694.3  160.24  4856.7  156.33  4906.9  155.77
  4972.3  153.36  4996.8   142.7  5000.4   142.7  5015.7  149.24  5039.6  151.86
 5046.93153.5417    5059  154.32  5107.5  153.16  5112.6  153.89  5204.5  155.95
  5254.8  155.81  5357.3  158.03  5367.5   157.6    5383  158.55  5772.8  168.67
#Mann= 3 , 0 , 0
  4107.3     .17       0  4972.3     .09       0 5046.93     .17       0
#XS Ineff= 2 , 0
       0    4836  157.24  5357.3       0  158.03
Permanent Ineff=
       F       F
Bank Sta=4972.3,5046.93
XS Rating Curve= 0 ,0
Exp/Cntr=0.3,0.1

Type RM Length L Ch R = 1 ,16169   ,670,670,670
BEGIN DESCRIPTION:
Crystal Creek 038 32.0
END DESCRIPTION:
XS GIS Cut Line= 3
      3825217.83     10082611.03      3824865.86     10082122.98
      3824476.71     10081634.71
#Sta/Elev= 30
  4395.1  165.83  4574.2  159.61    4617  159.67  4660.1  157.85  4775.4  155.86
  4838.9  153.64  4875.9  153.76  4896.9  152.02  4917.8  152.73  4953.4   151.9
  4974.5   153.4  4982.8  152.51  4988.9  150.13  4993.1  145.31  5011.7  147.15
  5024.8  151.88  5038.9  153.12  5053.3  152.14  5088.8  152.47  5259.9  158.07
  5288.7  157.81  5423.2  162.42  5445.7  162.28  5472.9  164.01  5516.1  164.72
  5530.5  166.11  5559.4  165.83  5565.8   166.9  5573.8   166.4  5621.2  168.46
#Mann= 3 , 0 , 0
  4395.1     .17       0  4974.5     .09       0  5038.9     .17       0
#XS Ineff= 2 , 0
       0  4760.7  156.02  5203.9       0  156.08
Permanent Ineff=
       F       F
Bank Sta=4974.5,5038.9
XS Rating Curve= 0 ,0
Exp/Cntr=0.3,0.1

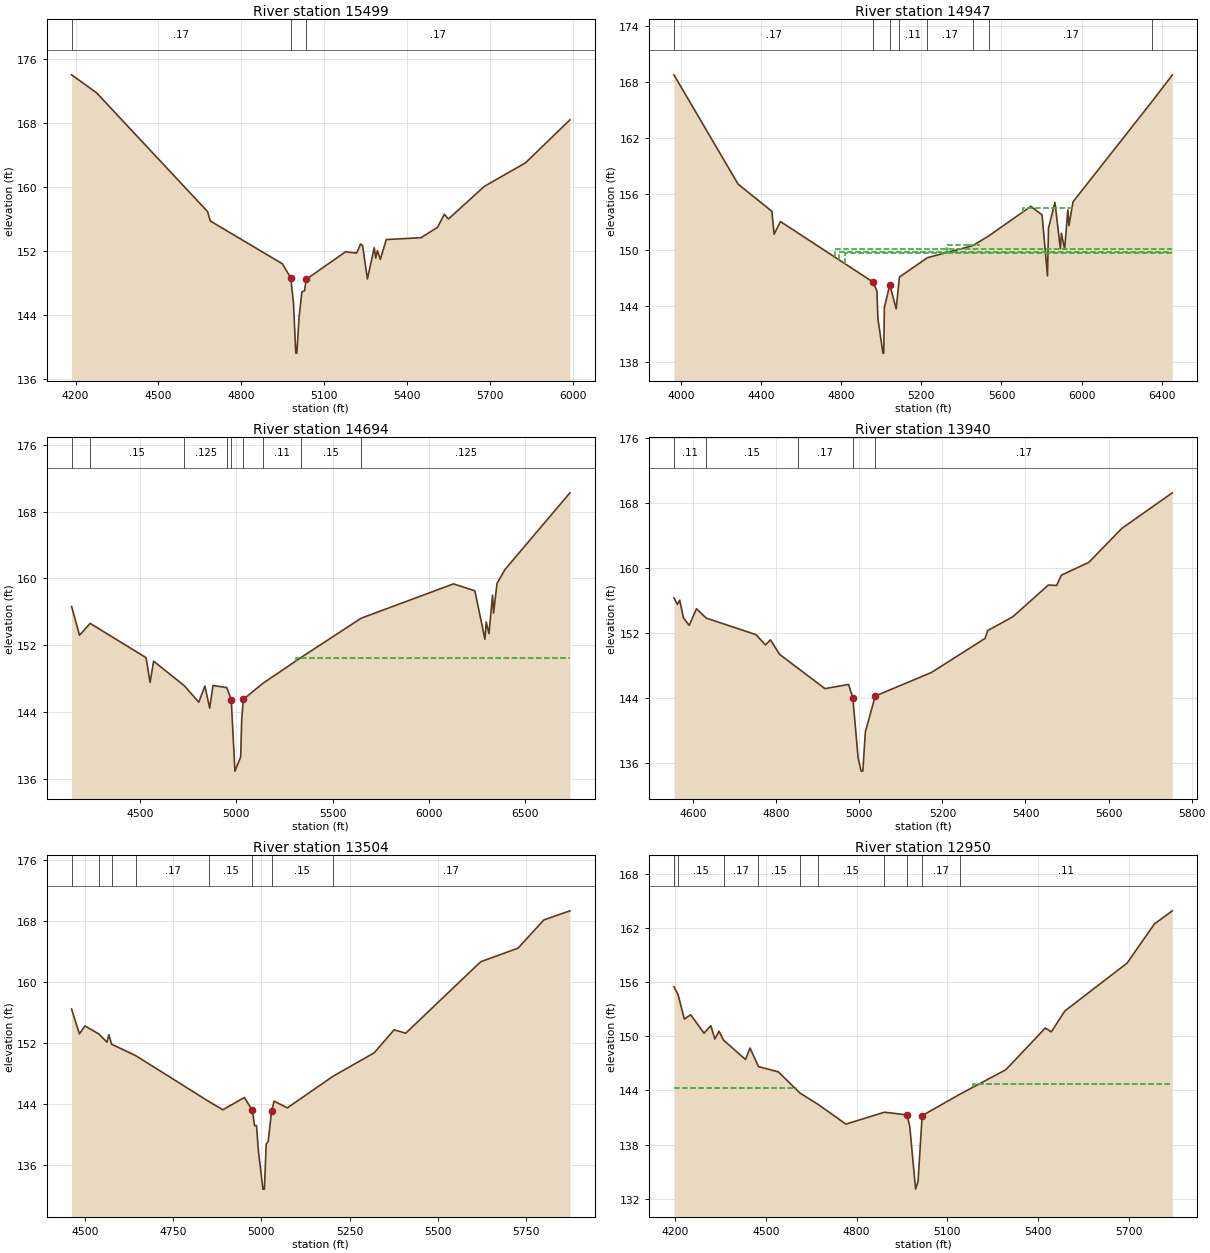
Type RM Length L Ch R = 1 ,15499   ,552,552,552
BEGIN DESCRIPTION:
Crystal Creek 038 31.0
END DESCRIPTION:
XS GIS Cut Line= 3
      3825467.85     10082811.06      3825390.16     10081935.48
      3824527.75     10081603.02
#Sta/Elev= 30
  4185.7  174.05    4276  171.81  4677.6  156.97  4687.7  155.79  4948.7  150.44
  4978.8  148.67  4988.8  145.52  4996.9  139.28  5000.8  139.28  5008.9  143.77
    5019  146.93    5029  147.08  5034.2  148.49    5177  151.94  5217.2  151.78
  5231.6  152.91  5238.7  152.73  5256.2  148.55  5280.8  152.45  5286.2  151.16
  5292.3  152.09    5303  150.99  5324.4  153.47    5450   153.7  5509.9     155
  5534.5  156.63  5549.5  156.04  5679.1  160.11  5828.1  163.05    5989  168.43
#Mann= 3 , 0 , 0
  4185.7     .17       0  4978.8     .09       0  5034.2     .17       0
#XS Ineff= 2 , 0
       0                  5231.6       0  152.91
Permanent Ineff=
       F       F
Bank Sta=4978.8,5034.2
XS Rating Curve= 0 ,0
Exp/Cntr=0.3,0.1

Type RM Length L Ch R = 1 ,14947   ,253,253,253
BEGIN DESCRIPTION:
Crystal Creek 038 30.0
END DESCRIPTION:
XS GIS Cut Line= 4
       3826699.2     10082546.63      3826590.76     10082236.55
      3826022.11     10082053.54      3824536.44     10081576.98
#Sta/Elev= 30
  3966.2  168.75  4286.5  157.05  4454.8  154.15  4465.8   151.7  4497.4  153.06
  4959.6  146.58  4978.7  145.63  4983.9  142.64  5008.8  138.98  5012.7  138.98
    5016  143.86  5042.9  146.28    5075  143.71  5090.8  147.11  5230.5  149.19
  5456.3  150.47  5537.5  151.53  5747.2  154.69  5802.7  153.76  5829.6  147.25
  5834.8  152.37    5867   155.1  5893.8  150.17  5899.1   151.8  5915.2  150.09
  5931.2  154.31  5936.5  152.63  5957.2  155.17    6353  165.95  6452.3  168.73
#Mann= 8 ,-1 , 0
  3966.2     .17       0  4959.6     .09       0  5042.9     .17       0
  5090.8     .11       0  5230.5     .17       0  5456.3     .11       0
  5537.5     .17       0    6353    .125       0
#XS Ineff= 8 ,-1
  4818.1  4791.5  149.68  4791.5  4770.5  149.75  4770.5  4684.6  150.09
  4684.6  4633.9  150.37  4633.9  4612.9  150.47  5327.1  5444.1   150.5
  5444.1  5495.1  150.59  5706.4  5957.2   154.5
Permanent Ineff=
       F       F       F       F       F       F       F       F
Bank Sta=4959.6,5042.9
XS Rating Curve= 0 ,0
Exp/Cntr=0.3,0.1

Type RM Length L Ch R = 1 ,14694   ,754,754,754
BEGIN DESCRIPTION:
Crystal Creek 038 29.0
END DESCRIPTION:
XS GIS Cut Line= 4
      3826904.03     10082208.45      3826865.18     10082134.13
      3826170.55     10081904.67      3824475.69     10081390.35
#Sta/Elev= 30
  4144.4  156.64  4185.5  153.19  4240.9  154.61  4530.9   150.5  4551.9  147.53
  4570.2  150.08  4729.4  147.14  4804.7  145.16  4836.3   147.1  4861.2  144.45
  4878.4  147.16  4949.9  146.91  4973.1  145.47  4992.3  136.89    5022  138.59
  5027.2  142.99  5035.8   145.5  5138.6  147.44  5336.5  150.54  5648.1  155.24
  6126.9  159.35  6237.6  158.52  6289.8  152.71  6296.5  154.77  6310.7  153.38
  6329.4     158  6334.7  155.85  6352.5   159.4  6394.3  161.08    6731  170.27
#Mann= 9 ,-1 , 0
  4144.4     .11       0  4240.9     .15       0  4729.4    .125       0
  4949.9     .15       0  4973.1     .09       0  5035.8     .15       0
  5138.6     .11       0  5336.5     .15       0  5648.1    .125       0
#XS Ineff= 2 , 0
       0  4570.2  150.05  5307.5       0  150.45
Permanent Ineff=
       F       F
Bank Sta=4973.1,5035.8
XS Rating Curve= 0 ,0
Exp/Cntr=0.3,0.1

Type RM Length L Ch R = 1 ,13940   ,436,436,436
BEGIN DESCRIPTION:
Crystal Creek 038 28.0
END DESCRIPTION:
XS GIS Cut Line= 3
      3826917.08     10082201.99      3826721.76      10081778.8
      3826515.96     10081074.76
#Sta/Elev= 30
  4553.8  156.37  4562.1  155.56  4567.6  156.09  4576.8  153.89  4590.6  152.98
    4608  155.03  4631.6  153.87  4751.2  151.84  4774.1  150.57  4786.1   151.2
  4808.1  149.41  4852.1  147.71  4917.3  145.19  4974.2  145.71  4984.4  144.07
  4997.1  136.68  5004.3  135.03  5008.4  135.03  5014.6  139.88  5038.4  144.28
  5173.8  147.18  5302.6  151.37  5309.2  152.34  5369.5  154.04  5455.1  157.95
    5475  157.89  5486.4  159.16  5552.4  160.74  5632.2  164.93  5753.4   169.3
#Mann= 5 ,-1 , 0
  4553.8     .11       0  4631.6     .15       0  4852.1     .17       0
  4984.4     .09       0  5038.4     .17       0
Bank Sta=4984.4,5038.4
XS Rating Curve= 0 ,0
Exp/Cntr=0.3,0.1

Type RM Length L Ch R = 1 ,13504   ,554,554,554
BEGIN DESCRIPTION:
Crystal Creek 038 27.0
END DESCRIPTION:
XS GIS Cut Line= 3
      3826934.44      10082206.3      3827127.58     10081722.38
      3826726.68     10080924.91
#Sta/Elev= 30
  4461.6  156.44  4483.8  153.19  4499.5  154.23    4539  153.18    4562  152.11
  4567.4  153.07  4575.1  151.84  4643.3  150.35  4851.9  144.32  4890.7  143.26
  4951.7  144.87  4974.3   143.2  4980.6  141.19  4986.2  141.19  4991.4  137.97
  5004.4  132.88  5008.5  132.88  5013.7  138.77  5019.3   139.1  5028.9  143.06
  5036.1  144.39  5073.6  143.51  5202.6  147.63  5319.9  150.71  5376.5  153.72
  5409.4  153.28  5622.1  162.63  5728.1  164.41  5801.2   168.1  5875.2  169.29
#Mann= 8 ,-1 , 0
  4461.6     .11       0    4539     .15       0  4575.1     .11       0
  4643.3     .17       0  4851.9     .15       0  4974.3     .09       0
  5028.9     .15       0  5202.6     .17       0
Bank Sta=4974.3,5028.9
XS Rating Curve= 0 ,0
Exp/Cntr=0.3,0.1

Type RM Length L Ch R = 1 ,12950   ,450,450,450
BEGIN DESCRIPTION:
Crystal Creek 038 26.0
END DESCRIPTION:
XS GIS Cut Line= 3
      3827183.97     10082284.48      3827633.22     10081594.34
       3827685.3     10080771.87
#Sta/Elev= 30
  4196.4   155.5  4210.2  154.61  4230.7  151.92  4251.7   152.4  4295.9  150.35
  4318.2  151.18  4331.7  149.71  4345.3  150.57  4360.5  149.58  4432.9  147.44
    4448  148.71  4475.8  146.65  4541.6  146.06  4612.8  143.72  4673.4  142.45
  4764.9  140.27  4892.2  141.59  4967.2  141.29    4976  140.02  4995.3  133.06
  5003.4  133.92 5017.01141.2116  5142.6   143.6  5293.7   146.3    5424  150.92
    5444   150.5  5488.9  152.82  5694.5  158.12  5784.7  162.46    5844  163.92
#Mann= 10 ,-1 , 0
  4196.4     .11       0  4210.2     .15       0  4360.5     .17       0
  4475.8     .15       0  4612.8     .17       0  4673.4     .15       0
  4892.2     .17       0  4967.2     .09       0 5017.01     .17       0
  5142.6     .11       0
#XS Ineff= 2 , 0
       0  4598.9   144.3  5183.5       0  144.71
Permanent Ineff=
       F       F
Bank Sta=4967.2,5017.01
XS Rating Curve= 0 ,0
Exp/Cntr=0.3,0.1

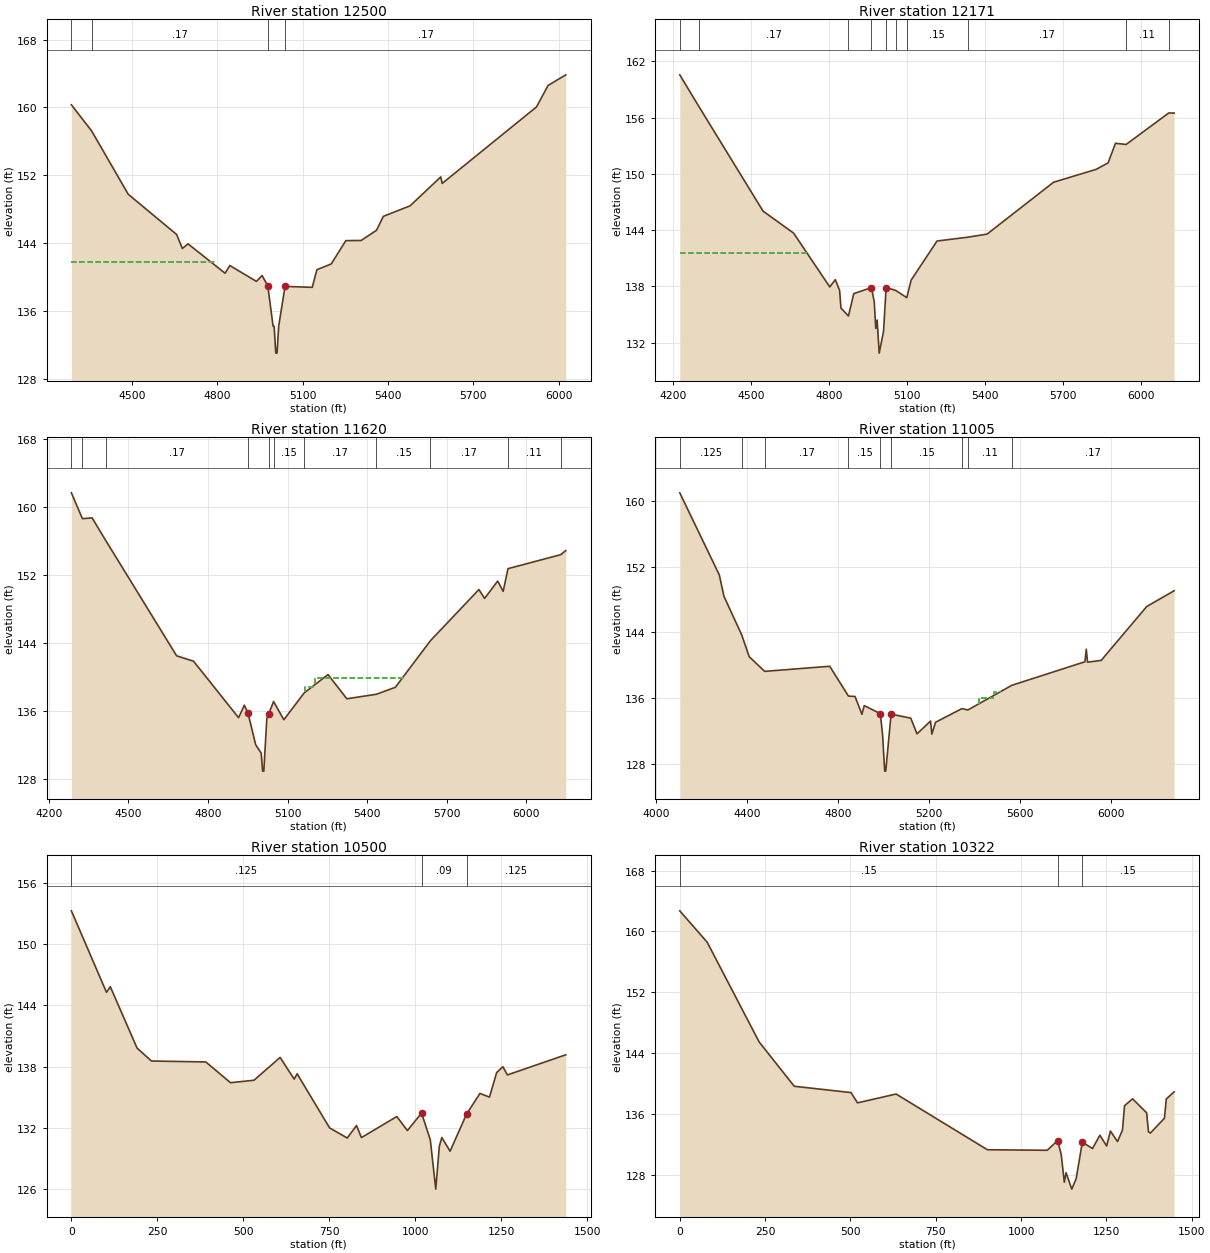
Type RM Length L Ch R = 1 ,12500   ,329,329,329
BEGIN DESCRIPTION:
Crystal Creek 038 25.0
END DESCRIPTION:
XS GIS Cut Line= 3
      3827986.95     10082440.74       3827956.2      10081728.9
      3827776.45     10080719.78
#Sta/Elev= 30
  4287.5  160.31  4358.3  157.25  4487.4  149.77  4657.5  145.03  4677.5  143.38
  4697.5  143.93  4827.7  140.47  4844.3  141.38  4937.8  139.51  4957.8   140.2
  4977.8  138.97  4996.4  134.22    5000  134.22  5005.8  131.06  5010.2  131.06
  5016.1  134.26  5038.4  138.92    5134  138.81  5150.2  140.88  5200.9  141.57
    5252  144.31  5305.9  144.33  5359.8  145.53  5383.8  147.17  5477.8  148.41
  5585.6  151.82  5590.7  151.05  5922.1  160.06  5962.7  162.59    6025  163.84
#Mann= 4 ,-1 , 0
  4287.5     .15       0  4358.3     .17       0  4977.8     .09       0
  5038.4     .17       0
#XS Ineff= 2 , 0
       0  4787.6  141.85               0
Permanent Ineff=
       F       F
Bank Sta=4977.8,5038.4
XS Rating Curve= 0 ,0
Exp/Cntr=0.3,0.1

Type RM Length L Ch R = 1 ,12171   ,551,551,551
BEGIN DESCRIPTION:
Crystal Creek 038 24.0
END DESCRIPTION:
XS GIS Cut Line= 3
      3828002.14      10082440.7       3828288.6     10081694.16
      3828761.15     10080694.87
#Sta/Elev= 30
  4224.7  160.57  4298.6  157.18  4545.6  146.03  4663.5  143.68  4802.7  137.94
  4824.1  138.72  4840.5  137.58  4845.8  135.69  4874.6  134.84  4895.2  137.23
  4963.4  137.87  4974.1  136.35  4979.9  133.51  4985.2  134.41  4993.2  130.88
  5009.9  133.21 5019.82137.8768    5056  137.58  5099.4   136.8  5116.2  138.67
  5215.8  142.84  5334.8  143.25  5408.9  143.58  5664.8  149.11  5829.6  150.49
  5875.2  151.18  5903.5  153.27  5944.4  153.14  6108.9   156.5  6129.7  156.49
#Mann= 10 ,-1 , 0
  4224.7     .15       0  4298.6     .17       0  4874.6     .15       0
  4963.4     .09       0 5019.82     .15       0    5056     .17       0
  5099.4     .15       0  5334.8     .17       0  5944.4     .11       0
  6108.9     .17       0
#XS Ineff= 2 , 0
       0    4717  141.53               0
Permanent Ineff=
       F       F
Bank Sta=4963.4,5019.82
XS Rating Curve= 0 ,0
Exp/Cntr=0.3,0.1

Type RM Length L Ch R = 1 ,11620   ,615,615,615
BEGIN DESCRIPTION:
Crystal Creek 038 23.0
END DESCRIPTION:
XS GIS Cut Line= 3
      3828017.89     10082461.04      3828677.06     10081874.29
      3828846.32     10080908.59
#Sta/Elev= 30
  4285.3  161.64  4326.9  158.61  4363.4   158.7  4414.7  156.05    4682  142.51
  4745.6  141.88  4915.3  135.25    4937  136.72  4951.2  135.75  4979.7  132.08
  5000.6  131.09  5005.8  128.98  5010.4  128.98  5021.6  135.13    5029   135.7
  5047.1  137.15  5085.9  135.01  5162.5  138.16  5252.3  140.31  5323.3  137.47
  5434.5     138  5506.1  138.82    5638  144.28  5820.8  150.29  5842.3  149.25
  5891.6  151.29  5912.2  150.08  5930.4  152.74  6128.8  154.38  6148.2  154.86
#Mann= 11 ,-1 , 0
  4285.3     .15       0  4326.9    .125       0  4414.7     .17       0
  4951.2     .09       0    5029     .17       0  5047.1     .15       0
  5162.5     .17       0  5434.5     .15       0    5638     .17       0
  5930.4     .11       0  6128.8     .17       0
#XS Ineff= 2 ,-1
  5166.4    5204  138.87    5204  5545.3  139.88
Permanent Ineff=
       F       F
Bank Sta=4951.2,5029
XS Rating Curve= 0 ,0
Exp/Cntr=0.3,0.1

Type RM Length L Ch R = 1 ,11005   ,505,505,505
BEGIN DESCRIPTION:
Crystal Creek 038 22.0
END DESCRIPTION:
XS GIS Cut Line= 3
      3828075.89     10082449.38      3829002.58     10082310.48
      3829599.37     10081227.58
#Sta/Elev= 30
  4105.4     161  4279.3     151  4299.5  148.41  4378.3  143.66  4410.7  141.04
  4478.7  139.26  4764.6  139.88  4846.9  136.25  4875.9   136.2  4906.2  134.03
  4916.3  135.09  4987.1  134.11  4997.2  131.47  5006.3  127.11  5010.9  127.11
  5034.4 134.054  5120.9  133.56  5148.4  131.65    5208  133.21  5213.7  131.62
  5229.8  133.06  5345.5  134.72  5372.2  134.56  5565.1  137.56  5886.7  140.43
  5892.4  141.96  5898.1  140.38  5957.8  140.59  6158.4  147.16  6278.9  149.08
#Mann= 9 ,-1 , 0
  4105.4    .125       0  4378.3     .11       0  4478.7     .17       0
  4846.9     .15       0  4987.1     .09       0  5034.4     .15       0
  5345.5     .17       0  5372.2     .11       0  5565.1     .17       0
#XS Ineff= 3 ,-1
  4875.9  4835.4   136.2  5420.1  5487.1  136.05  5487.1  5517.6  136.73
Permanent Ineff=
       F       F       F
Bank Sta=4987.1,5034.4
XS Rating Curve= 0 ,0
Exp/Cntr=0.3,0.1

Type RM Length L Ch R = 1 ,10500   ,178,178,178
XS GIS Cut Line= 3
      3828217.85     10082461.07      3829234.52     10082706.62
       3829612.5     10082817.03
#Sta/Elev= 30
       0  153.23   102.1  145.26   113.2  145.81     191  139.81   232.9  138.54
   390.9  138.45   462.9  136.42   531.1  136.66     607  138.89   648.1  136.77
   656.7  137.29     751     132   802.4  131.01   829.4  132.23   843.6  131.05
   946.5  133.11   977.3  131.74  1018.5  133.45  1043.9  130.84  1059.8  126.01
  1070.2  130.21  1077.5  131.06  1101.5  129.72  1149.6  133.36  1188.3  135.37
  1216.1  135.01  1236.9  137.41  1255.2  137.98  1268.1  137.18    1438  139.15
#Mann= 3 , 0 , 0
       0    .125       0  1018.5     .09       0  1149.6    .125       0
Bank Sta=1018.5,1149.6
XS Rating Curve= 0 ,0
Exp/Cntr=0.3,0.1

Type RM Length L Ch R = 1 ,10322   ,393,393,393
XS GIS Cut Line= 4
      3828101.97     10082607.79      3829230.44      10082883.4
      3829377.76     10082920.21      3829502.47     10082865.31
#Sta/Elev= 30
       0  162.71    80.2  158.59   232.5  145.47   335.5  139.63   501.9   138.8
   520.8  137.45     634  138.61   901.6  131.28  1076.6  131.21  1107.5  132.48
  1117.8  130.65  1126.8     127    1132  128.26  1148.7   126.1  1161.6  127.48
  1179.6  132.26  1209.6  131.45  1231.1  133.19  1250.9  131.77    1262  133.74
  1282.7  132.36  1297.3  133.87  1303.3  137.07  1326.9  137.98  1368.1  136.14
  1373.5  133.64  1379.1  133.48  1420.2  135.42  1425.7  137.96  1448.8   138.9
#Mann= 3 , 0 , 0
       0     .15       0  1107.5     .09       0  1179.6     .15       0
Bank Sta=1107.5,1179.6
XS Rating Curve= 0 ,0
Exp/Cntr=0.3,0.1

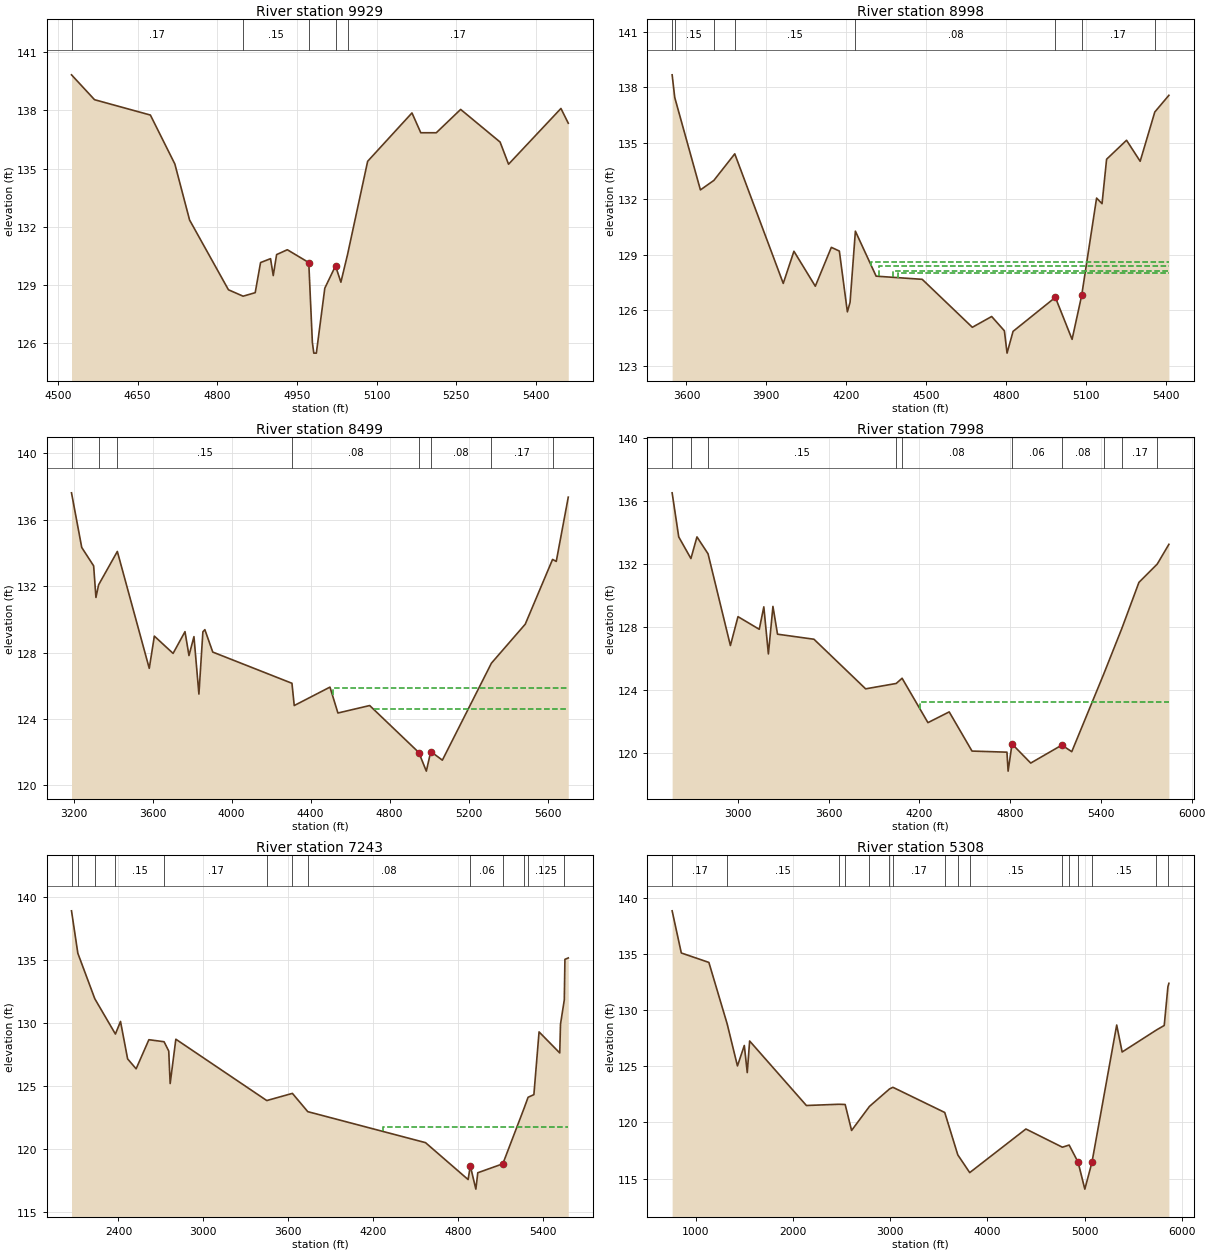
Type RM Length L Ch R = 1 ,9929    ,931,931,931
BEGIN DESCRIPTION:
Crystal Creek 038 19.0
END DESCRIPTION:
XS GIS Cut Line= 3
      3828714.79     10083146.85      3829337.21     10083228.45
      3829466.54     10082948.97
#Sta/Elev= 30
  4525.4  139.82  4568.8  138.54    4674  137.75  4720.1  135.23  4747.8  132.35
    4821  128.76  4848.6  128.43  4871.4  128.61  4881.5  130.16  4900.3  130.36
  4905.4  129.49  4911.7  130.57  4931.9  130.82  4972.3  130.16  4979.1  126.05
  4981.8   125.5  4986.6   125.5  5002.5  128.84  5022.7  129.99  5032.8  129.15
  5045.4  130.58  5083.2  135.37  5166.7  137.86  5183.3  136.84  5212.5  136.84
  5258.4  138.04  5332.7  136.36  5348.6  135.22  5447.3  138.09  5461.1  137.33
#Mann= 5 ,-1 , 0
  4525.4     .17       0  4848.6     .15       0  4972.3     .09       0
  5022.7     .15       0  5045.4     .17       0
Bank Sta=4972.3,5022.7
XS Rating Curve= 0 ,0
Exp/Cntr=0.3,0.1

Type RM Length L Ch R = 1 ,8998    ,499,499,499
BEGIN DESCRIPTION:
Crystal Creek 038 18.0
END DESCRIPTION:
XS GIS Cut Line= 3
        3828562.     10083639.91       3829853.7     10083532.27
      3829734.04     10082975.57
#Sta/Elev= 30
  3546.2  138.67    3556  137.45  3652.4  132.48  3702.9  132.99  3781.4  134.42
  3963.5  127.45  4003.6  129.18  4083.9   127.3  4144.1  129.39  4174.2  129.19
  4204.3  125.92  4214.4  126.43  4234.4  130.26  4312.3  127.84  4485.3  127.67
  4673.6  125.09  4746.2  125.67    4794   124.9    4804   123.7  4826.5  124.87
  4985.4   126.7  5048.2  124.44  5084.2   126.8  5140.2  132.04  5160.7  131.74
  5177.8  134.13  5252.7  135.15  5303.9  134.02  5358.8  136.67  5411.8  137.57
#Mann= 8 ,-1 , 0
  3546.2     .17       0    3556     .15       0  3702.9     .17       0
  3781.4     .15       0  4234.4     .08       0  4985.4     .06       0
  5084.2     .17       0  5358.8     .11       0
#XS Ineff= 5 ,-1
    4395  4374.9  128.02  4374.9  4324.7  128.12  4324.7  4294.6  128.39
  4294.6  4234.4  128.58  4234.4  3863.1  130.26
Permanent Ineff=
       F       F       F       F       F
Bank Sta=4985.4,5084.2
XS Rating Curve= 0 ,0
Exp/Cntr=0.3,0.1

Type RM Length L Ch R = 1 ,8499    ,501,501,501
BEGIN DESCRIPTION:
Crystal Creek 038 17.0
END DESCRIPTION:
XS GIS Cut Line= 4
      3828586.31     10083678.11      3830312.04     10083504.49
      3830303.36     10083405.54      3829771.61     10082981.17
#Sta/Elev= 30
  3189.8  137.62  3241.6  134.33  3301.9  133.22  3313.5  131.32    3327  132.08
  3421.8  134.09  3583.3  127.05  3609.1  128.99  3703.9  127.95  3764.2  129.26
  3784.3  127.82  3809.5  128.96  3834.6   125.5  3854.7  129.25  3864.7  129.38
  3904.7  128.03  4305.5  126.15    4317  124.81  4497.9  125.92  4538.1  124.36
  4698.9  124.81  4947.7  121.98  4985.5  120.86    5008  122.04  5066.7  121.52
  5314.9  127.36  5486.2  129.71  5624.4  133.61  5643.1  133.49  5703.9  137.36
#Mann= 8 ,-1 , 0
  3189.8     .15       0    3327     .17       0  3421.8     .15       0
  4305.5     .08       0  4947.7     .06       0    5008     .08       0
  5314.9     .17       0  5624.4     .11       0
#XS Ineff= 5 ,-1
    4719  4698.9  124.63  4698.9  4510.9  124.81  4510.9  4266.7  125.86
  3864.7  3513.9  129.38  5215.6  5244.4  124.93
Permanent Ineff=
       F       F       F       F       F
Bank Sta=4947.7,5008
XS Rating Curve= 0 ,0
Exp/Cntr=0.3,0.1

Type RM Length L Ch R = 1 ,7998    ,755,755,755
BEGIN DESCRIPTION:
Crystal Creek 038 16.0
END DESCRIPTION:
XS GIS Cut Line= 4
      3828604.45     10083717.53      3830823.21     10083498.78
      3830764.19     10083255.72      3829995.08     10083016.83
#Sta/Elev= 30
  2564.5   136.5  2608.1  133.71  2688.7  132.34  2728.7  133.71    2802  132.64
  2949.8  126.83    3000  128.66  3140.7  127.86  3170.8  129.28    3201   126.3
  3231.1  129.31  3261.3  127.55  3502.4  127.23  3844.1  124.09  4046.3  124.43
  4085.2  124.76  4256.1  121.95  4396.7  122.63  4547.5  120.15  4778.6  120.08
  4786.2  118.88  4812.2   120.6  4935.7  119.39  5141.9  120.53  5207.1  120.11
  5418.2  125.02  5538.5  127.92  5651.3  130.83  5772.4  131.99  5849.5  133.24
#Mann= 10 ,-1 , 0
  2564.5     .15       0  2688.7     .17       0    2802     .15       0
  4046.3     .17       0  4085.2     .08       0  4812.2     .06       0
  5141.9     .08       0  5418.2     .11       0  5538.5     .17       0
  5772.4     .11       0
#XS Ineff= 3 ,-1
  4396.7  4205.4  122.63  4205.4  4155.6  123.26  5354.4  5380.4  123.28
Permanent Ineff=
       F       F       F
Bank Sta=4812.2,5141.9
XS Rating Curve= 0 ,0
Exp/Cntr=0.3,0.1

Type RM Length L Ch R = 1 ,7243    ,1935,1935,1935
BEGIN DESCRIPTION:
Crystal Creek 038 14.0
END DESCRIPTION:
XS GIS Cut Line= 3
      3828572.37     10083787.67      3831266.79     10083568.92
      3832033.71     10083307.93
#Sta/Elev= 30
  2067.8  138.89  2112.7  135.52  2232.7  131.91  2378.4  129.11  2414.4  130.11
  2464.6  127.14  2524.8  126.35  2615.1  128.66  2722.5   128.5  2755.5  127.76
  2765.6  125.18  2805.7   128.7  3448.9  123.83  3630.1   124.4  3738.8  122.95
  4571.5  120.49  4872.8  117.56  4888.4  118.64  4927.6   116.8  4941.2   118.1
  5118.4  118.81  5268.7  123.22    5297  124.09    5338   124.3  5374.6  129.28
  5520.9  127.61  5526.2  129.89  5553.1  131.82  5557.5  135.04  5581.2  135.15
#Mann= 13 ,-1 , 0
  2067.8     .17       0  2112.7     .15       0  2232.7     .17       0
  2378.4     .15       0  2722.5     .17       0  3448.9     .15       0
  3630.1     .17       0  3738.8     .08       0  4888.4     .06       0
  5118.4     .08       0  5268.7     .17       0    5297    .125       0
  5553.1     .11       0
#XS Ineff= 4 ,-1
  5249.2  5268.7   122.6  4270.5  4069.8  121.71  4069.8  3929.4  121.79
  3929.4  3899.3  122.26
Permanent Ineff=
       F       F       F       F
Bank Sta=4888.4,5118.4
XS Rating Curve= 0 ,0
Exp/Cntr=0.3,0.1

Type RM Length L Ch R = 1 ,5308    ,2403,2403,2403
BEGIN DESCRIPTION:
Crystal Creek 038 10.0
END DESCRIPTION:
XS GIS Cut Line= 3
      3828554.56     10084062.66      3832343.65     10084657.28
      3832551.08     10083400.95
#Sta/Elev= 30
   758.7  138.83   853.1  135.08  1136.6  134.24  1324.7  128.77  1430.5  125.03
    1501  126.85  1531.3  124.44  1555.7  127.25  2139.5  121.51  2473.2  121.62
  2538.1   121.6  2604.3  119.29    2788  121.43    2994  122.98    3029  123.13
  3562.2  120.89  3696.4  117.12  3819.1  115.54    4397  119.42  4771.7   117.8
  4841.8  117.99 4933.61116.4662  5002.9  114.07  5076.1  116.45  5330.6  128.67
  5386.6  126.27  5739.7  128.23  5819.4  128.63  5857.3  132.07  5867.5  132.38
#Mann= 16 ,-1 , 0
   758.7     .17       0  1324.7     .15       0  2473.2     .17       0
  2538.1     .15       0    2788     .17       0    2994     .15       0
    3029     .17       0  3562.2     .15       0  3696.4     .17       0
  3819.1     .15       0  4771.7     .17       0  4841.8     .15       0
 4933.61     .09       0  5076.1     .15       0  5739.7     .11       0
  5857.3    .125       0
Bank Sta=4933.61,5076.1
XS Rating Curve= 0 ,0
Exp/Cntr=0.3,0.1

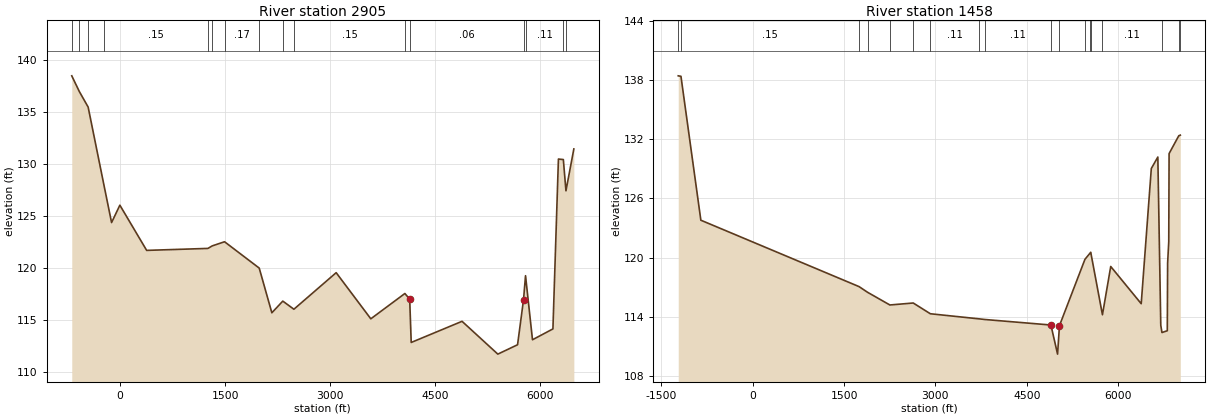
Type RM Length L Ch R = 1 ,2905    ,1447,1447,1447
BEGIN DESCRIPTION:
Crystal Creek 038 6.0
END DESCRIPTION:
XS GIS Cut Line= 3
       3828667.4     10084257.97       3834309.8     10085043.56
      3835468.67     10084132.09
#Sta/Elev= 30
  -689.7  138.44  -580.7  136.92  -455.8  135.44  -224.1  127.75  -121.1  124.35
    -2.7  126.02   380.1  121.68    1255  121.87    1316  122.11  1492.4  122.51
  1987.7  119.98  2168.1  115.69  2324.5  116.81  2483.1  116.03  3086.8  119.54
  3581.6  115.11  4068.3  117.54  4136.9     117  4158.6  112.84  4884.7  114.87
  5395.8  111.72  5677.5  112.62  5762.5  116.92  5791.4  119.25  5890.8   113.1
  6182.7  114.14  6261.3  130.45  6331.6   130.4  6368.7   127.4  6481.5  131.42
#Mann= 16 ,-1 , 0
  -689.7     .17       0  -580.7     .15       0  -455.8     .17       0
  -224.1     .15       0    1255     .17       0    1316     .15       0
  1492.4     .17       0  1987.7     .15       0  2324.5     .17       0
  2483.1     .15       0  4068.3     .11       0  4136.9     .06       0
  5762.5     .08       0  5791.4     .11       0  6331.6    .125       0
  6368.7     .11       0
Bank Sta=4136.9,5762.5
XS Rating Curve= 0 ,0
Exp/Cntr=0.3,0.1

Type RM Length L Ch R = 1 ,1458    ,0,0,0
BEGIN DESCRIPTION:
Crystal Creek 038 2.0
END DESCRIPTION:
XS GIS Cut Line= 3
      3828790.04     10084534.59      3834680.64     10086180.42
      3835482.72     10084206.45
#Sta/Elev= 30
 -1223.7  138.43   -1179  138.38  -852.2   123.8    1747  117.07  1885.1   116.5
  2252.8  115.21  2636.3  115.41  2917.9  114.32  3709.3  113.81  3810.6  113.74
  4897.8  113.18  5007.2  110.23 5038.18 113.116  5457.1  119.84  5537.8  120.44
  5551.9  120.55  5744.1  114.22  5880.4  119.11    6381  115.34    6547  129.04
  6654.1   130.2  6702.3  113.16  6721.7  112.42  6809.4   112.6  6814.8  119.47
  6833.5  121.62  6838.9  130.55  6998.4  132.36  7010.9  132.39  7023.2  132.42
#Mann= 18 ,-1 , 0
 -1223.7     .17       0   -1179     .15       0    1747     .11       0
  1885.1     .15       0  2252.8     .11       0  2636.3     .15       0
  2917.9     .11       0  3709.3     .15       0  3810.6     .11       0
  4897.8     .09       0 5038.18     .11       0  5457.1    .125       0
  5537.8     .11       0  5551.9    .125       0  5744.1     .11       0
  6721.7    .125       0  6998.4     .11       0  7010.9     .15       0
Bank Sta=4897.8,5038.18
XS Rating Curve= 0 ,0
Exp/Cntr=0.3,0.1

Chan Stop Cuts=-1
Use User Specified Reach Order=0
Composite Channel Slope=5

--- Crystal Creek 038.g10 (geometry) ---

Geom Title=Existing Conditions
Program Version=4.10

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
River Reach=Crystal Creek 03,Reach-1