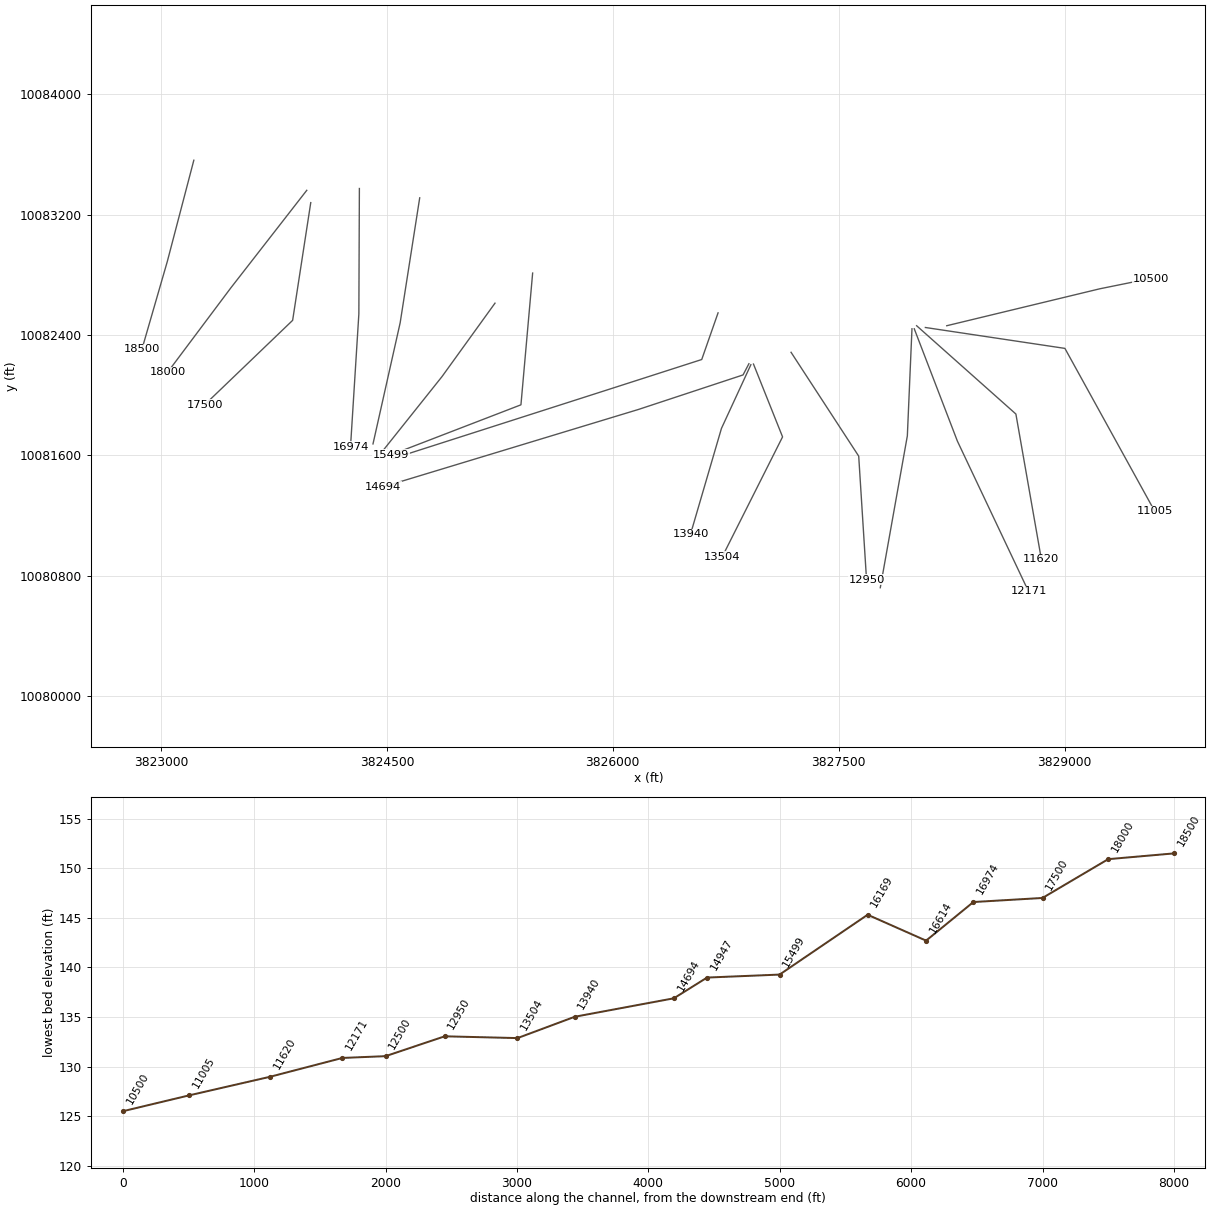
HEC-RAS study Crystal Creek 038.prj: Crystal Creek 038 Base Level Engineering

--- Crystal Creek 038.g10 (geometry) --- (continued)

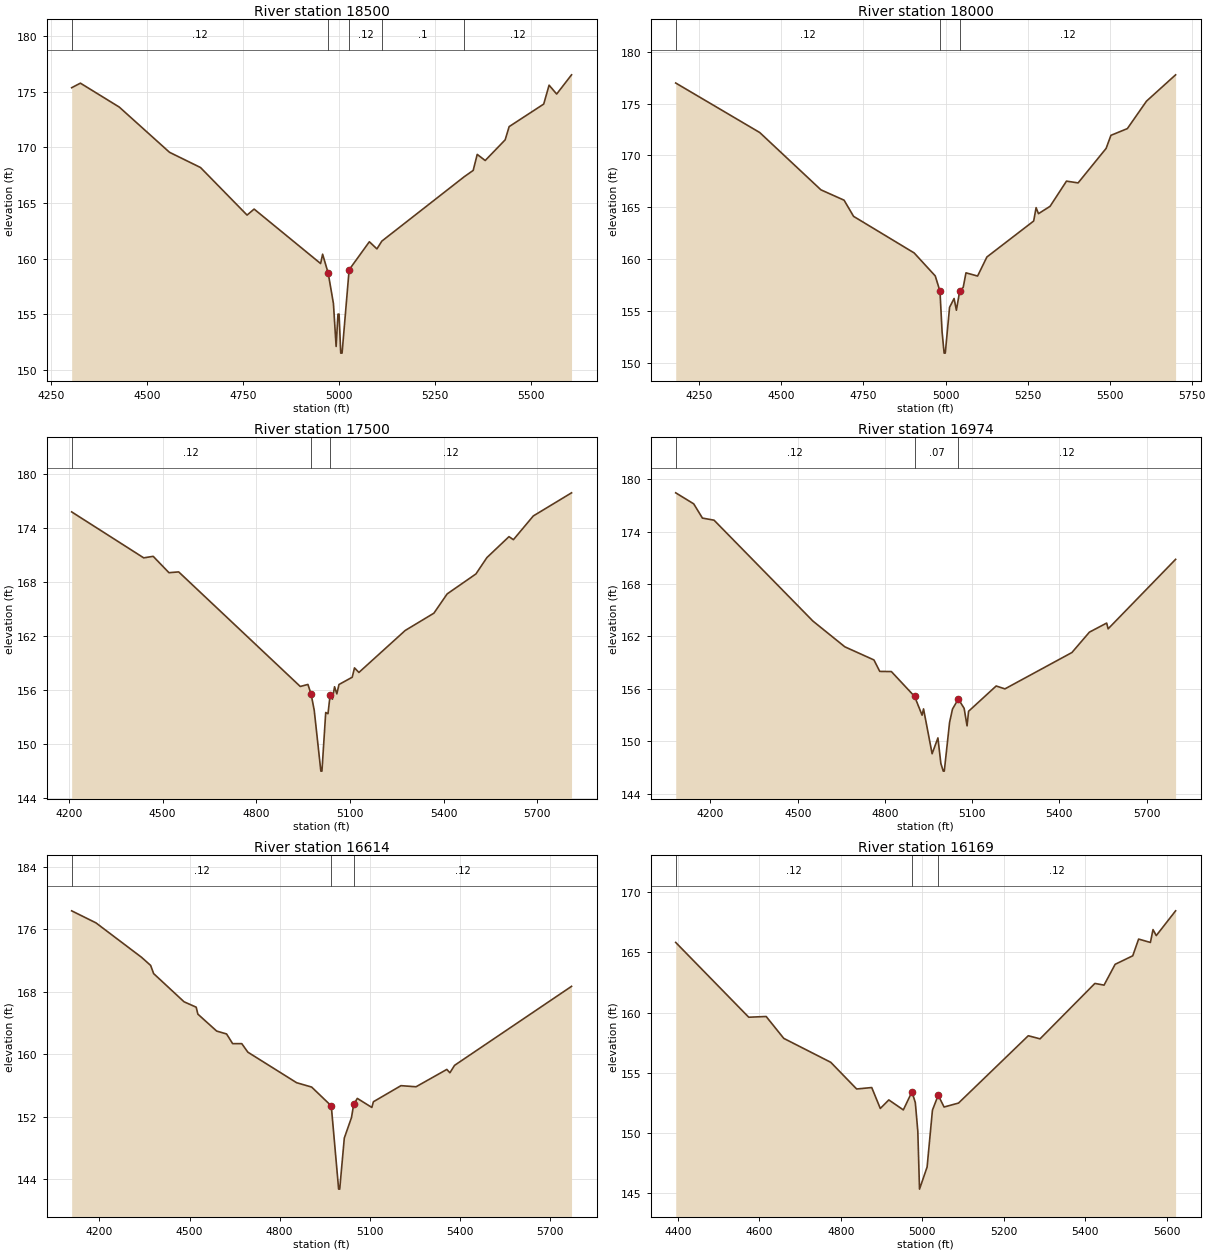
Type RM Length L Ch R = 1 ,18500   ,500,500,500
BEGIN DESCRIPTION:
Crystal Creek 038 37.0
END DESCRIPTION:
XS GIS Cut Line= 3
      3823217.85     10083561.05      3823041.39     10082886.86
      3822873.19     10082304.88
#Sta/Elev= 30
  4303.1  175.37  4325.9  175.78  4427.1  173.63  4558.1  169.56  4638.9  168.19
  4760.2  163.91  4778.6  164.45  4951.9  159.55  4957.1  160.39 4971.64 158.686
  4985.3  155.95  4992.3  152.09  4997.1     155    5000     155  5004.3  151.49
  5007.8  151.49  5026.2  158.99  5078.9  161.51  5098.6  160.87  5111.5  161.57
  5326.1  167.36  5349.5  167.93    5360  169.37  5380.8  168.82  5432.8  170.68
  5443.2  171.87  5533.3   173.9  5547.3   175.6    5567   174.8  5605.8  176.53
#Mann= 5 ,-1 , 0
  4303.1     .12       0 4971.64     .07       0  5026.2     .12       0
  5111.5      .1       0  5326.1     .12       0
Bank Sta=4971.64,5026.2
XS Rating Curve= 0 ,0
Exp/Cntr=0.3,0.1

Type RM Length L Ch R = 1 ,18000   ,500,500,500
BEGIN DESCRIPTION:
Crystal Creek 038 36.0
END DESCRIPTION:
XS GIS Cut Line= 3
      3823967.83     10083361.04       3823463.1       10082712.
      3823042.93     10082150.75
#Sta/Elev= 30
  4177.8  176.98  4433.9   172.2  4620.3  166.67  4690.9  165.67  4719.8  164.11
  4904.4  160.58  4968.7  158.36  4983.1  156.89  4989.5  152.97  4995.7  150.91
  4999.2  150.91  5012.3  155.33  5026.1  156.18  5033.1  155.05 5043.23 156.908
  5053.9  157.26  5062.3  158.66  5097.7  158.35  5126.1  160.19  5268.6  163.66
    5276  164.95  5283.2  164.37  5318.6  165.08  5368.6  167.51    5404  167.34
  5489.4  170.67    5504  171.93  5554.1  172.58  5612.4  175.23  5701.1  177.77
#Mann= 3 , 0 , 0
  4177.8     .12       0  4983.1     .07       0 5043.23     .12       0
Bank Sta=4983.1,5043.23
XS Rating Curve= 0 ,0
Exp/Cntr=0.3,0.1

Type RM Length L Ch R = 1 ,17500   ,526,526,526
BEGIN DESCRIPTION:
Crystal Creek 038 35.0
END DESCRIPTION:
XS GIS Cut Line= 3
      3823994.33     10083279.26      3823873.99     10082496.86
      3823289.78     10081935.79
#Sta/Elev= 30
  4208.4  175.82  4439.3  170.71  4469.6  170.88  4520.2  169.06  4551.3  169.15
  4940.9  156.41  4965.4  156.64  4975.5  155.57  4985.6  153.76  5006.8     147
  5010.3     147  5022.4  153.52  5029.7  153.38  5036.6  155.49  5043.8     155
  5050.7  156.38    5058  155.59  5064.9  156.63  5107.3  157.44  5114.6  158.48
  5128.7  157.97  5277.2  162.64    5369  164.56  5411.4   166.7  5503.6  168.92
  5538.8  170.74  5609.6  173.07  5623.7  172.73  5687.5  175.37    5810  177.94
#Mann= 3 , 0 , 0
  4208.4     .12       0  4975.5     .07       0  5036.6     .12       0
Bank Sta=4975.5,5036.6
XS Rating Curve= 0 ,0
Exp/Cntr=0.3,0.1

Type RM Length L Ch R = 1 ,16974   ,360,360,360
BEGIN DESCRIPTION:
Crystal Creek 038 34.0
END DESCRIPTION:
XS GIS Cut Line= 3
      3824317.25     10083372.98      3824313.77     10082539.65
      3824258.27     10081655.12
#Sta/Elev= 30
  4080.4  178.43  4142.3  177.17  4172.3  175.54  4212.3   175.3  4552.3  163.76
  4662.3  160.81  4762.3  159.31  4782.3     158  4822.3  157.98  4902.3  155.13
  4927.9  152.99  4932.9  153.71  4962.4  148.58  4982.4  150.39  4992.5  147.47
  5000.7  146.59  5004.3  146.59  5022.5  152.17  5032.5  153.69  5052.6  154.84
  5072.6  153.77  5082.6  151.77  5087.9  153.44  5182.8  156.33  5212.9     156
  5443.4  160.16  5503.5  162.49  5562.9  163.53  5567.9  162.87    5800  170.82
#Mann= 3 , 0 , 0
  4080.4     .12       0  4902.3     .07       0  5052.6     .12       0
Bank Sta=4902.3,5052.6
XS Rating Curve= 0 ,0
Exp/Cntr=0.3,0.1

Type RM Length L Ch R = 1 ,16614   ,445,445,445
BEGIN DESCRIPTION:
Crystal Creek 038 33.0
END DESCRIPTION:
XS GIS Cut Line= 3
      3824717.85     10083311.04      3824588.08     10082480.62
      3824407.64     10081675.59
#Sta/Elev= 30
  4107.3  178.34  4188.2   176.8  4340.1  172.39  4370.4  171.35  4380.5   170.3
  4481.8  166.69  4522.2     166  4527.8  165.11  4590.5  162.94  4623.5  162.57
  4643.7  161.33  4674.1  161.33  4694.3  160.24  4856.7  156.33  4906.9  155.77
  4972.3  153.36  4996.8   142.7  5000.4   142.7  5015.7  149.24  5039.6  151.86
 5046.93 153.542    5059  154.32  5107.5  153.16  5112.6  153.89  5204.5  155.95
  5254.8  155.81  5357.3  158.03  5367.5   157.6    5383  158.55  5772.8  168.67
#Mann= 3 , 0 , 0
  4107.3     .12       0  4972.3     .07       0 5046.93     .12       0
Bank Sta=4972.3,5046.93
XS Rating Curve= 0 ,0
Exp/Cntr=0.3,0.1

Type RM Length L Ch R = 1 ,16169   ,670,670,670
BEGIN DESCRIPTION:
Crystal Creek 038 32.0
END DESCRIPTION:
XS GIS Cut Line= 3
      3825217.83     10082611.03      3824865.86     10082122.98
      3824476.71     10081634.71
#Sta/Elev= 30
  4395.1  165.83  4574.2  159.61    4617  159.67  4660.1  157.85  4775.4  155.86
  4838.9  153.64  4875.9  153.76  4896.9  152.02  4917.8  152.73  4953.4   151.9
  4974.5   153.4  4982.8  152.51  4988.9  150.13  4993.1  145.31  5011.7  147.15
  5024.8  151.88  5038.9  153.12  5053.3  152.14  5088.8  152.47  5259.9  158.07
  5288.7  157.81  5423.2  162.42  5445.7  162.28  5472.9  164.01  5516.1  164.72
  5530.5  166.11  5559.4  165.83  5565.8   166.9  5573.8   166.4  5621.2  168.46
#Mann= 3 , 0 , 0
  4395.1     .12       0  4974.5     .07       0  5038.9     .12       0
Bank Sta=4974.5,5038.9
XS Rating Curve= 0 ,0
Exp/Cntr=0.3,0.1

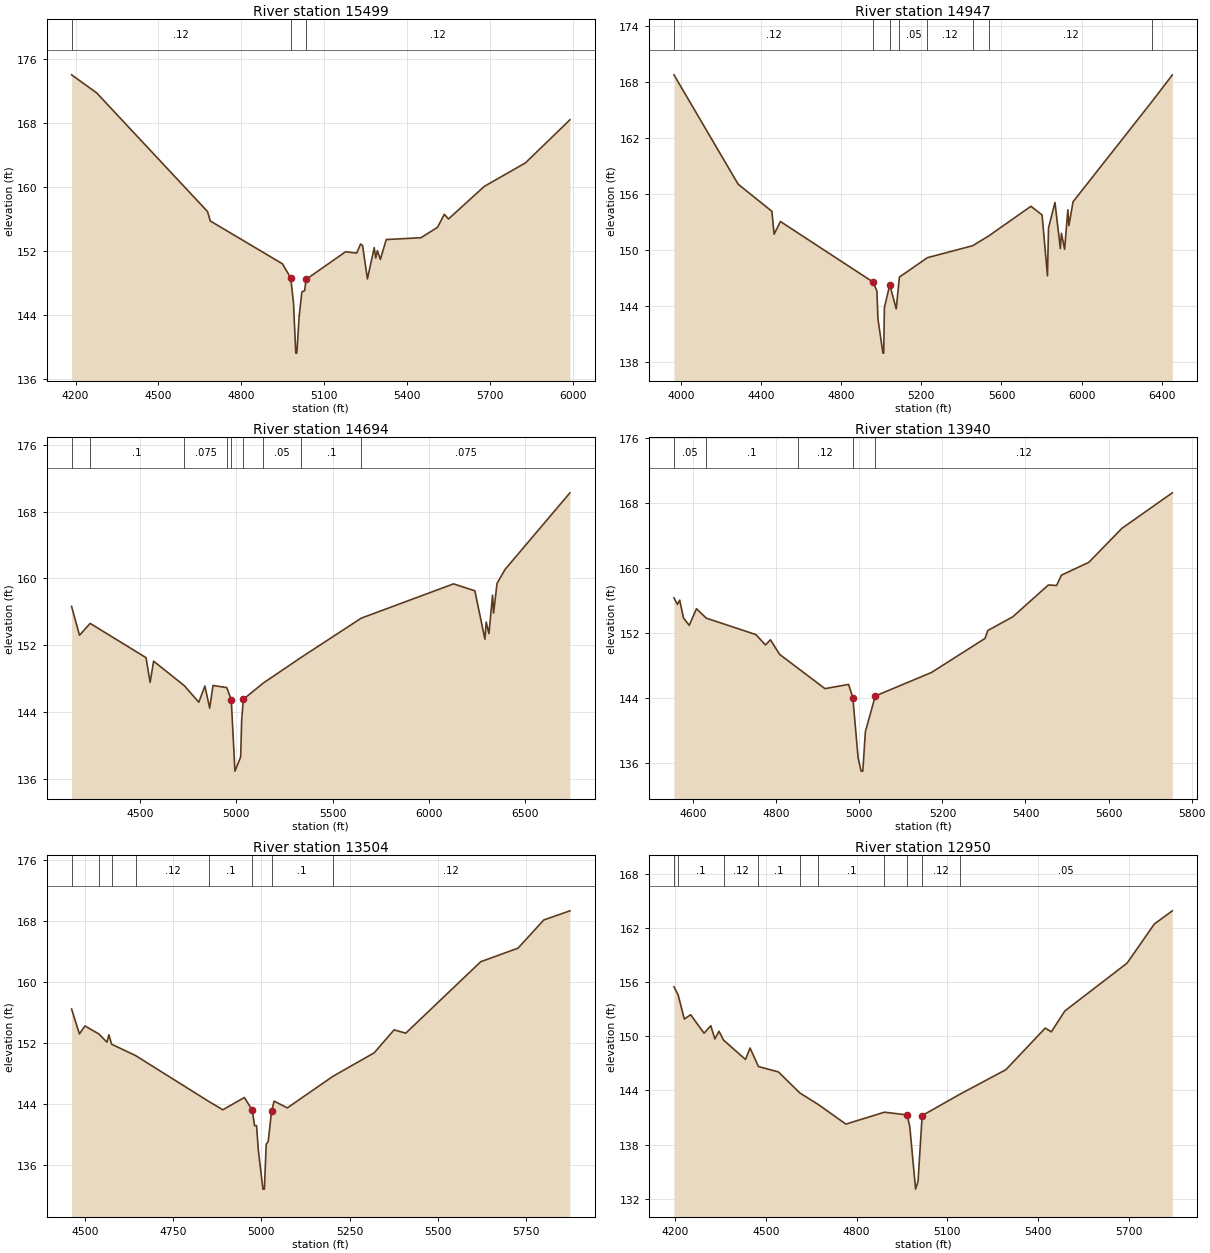
Type RM Length L Ch R = 1 ,15499   ,552,552,552
BEGIN DESCRIPTION:
Crystal Creek 038 31.0
END DESCRIPTION:
XS GIS Cut Line= 3
      3825467.85     10082811.06      3825390.16     10081935.48
      3824527.75     10081603.02
#Sta/Elev= 30
  4185.7  174.05    4276  171.81  4677.6  156.97  4687.7  155.79  4948.7  150.44
  4978.8  148.67  4988.8  145.52  4996.9  139.28  5000.8  139.28  5008.9  143.77
    5019  146.93    5029  147.08  5034.2  148.49    5177  151.94  5217.2  151.78
  5231.6  152.91  5238.7  152.73  5256.2  148.55  5280.8  152.45  5286.2  151.16
  5292.3  152.09    5303  150.99  5324.4  153.47    5450   153.7  5509.9     155
  5534.5  156.63  5549.5  156.04  5679.1  160.11  5828.1  163.05    5989  168.43
#Mann= 3 , 0 , 0
  4185.7     .12       0  4978.8     .07       0  5034.2     .12       0
Bank Sta=4978.8,5034.2
XS Rating Curve= 0 ,0
Exp/Cntr=0.3,0.1

Type RM Length L Ch R = 1 ,14947   ,253,253,253
BEGIN DESCRIPTION:
Crystal Creek 038 30.0
END DESCRIPTION:
XS GIS Cut Line= 4
       3826699.2     10082546.63      3826590.76     10082236.55
      3826022.11     10082053.54      3824536.44     10081576.98
#Sta/Elev= 30
  3966.2  168.75  4286.5  157.05  4454.8  154.15  4465.8   151.7  4497.4  153.06
  4959.6  146.58  4978.7  145.63  4983.9  142.64  5008.8  138.98  5012.7  138.98
    5016  143.86  5042.9  146.28    5075  143.71  5090.8  147.11  5230.5  149.19
  5456.3  150.47  5537.5  151.53  5747.2  154.69  5802.7  153.76  5829.6  147.25
  5834.8  152.37    5867   155.1  5893.8  150.17  5899.1   151.8  5915.2  150.09
  5931.2  154.31  5936.5  152.63  5957.2  155.17    6353  165.95  6452.3  168.73
#Mann= 8 ,-1 , 0
  3966.2     .12       0  4959.6     .07       0  5042.9     .12       0
  5090.8     .05       0  5230.5     .12       0  5456.3     .05       0
  5537.5     .12       0    6353    .075       0
Bank Sta=4959.6,5042.9
XS Rating Curve= 0 ,0
Exp/Cntr=0.3,0.1

Type RM Length L Ch R = 1 ,14694   ,754,754,754
BEGIN DESCRIPTION:
Crystal Creek 038 29.0
END DESCRIPTION:
XS GIS Cut Line= 4
      3826904.03     10082208.45      3826865.18     10082134.13
      3826170.55     10081904.67      3824475.69     10081390.35
#Sta/Elev= 30
  4144.4  156.64  4185.5  153.19  4240.9  154.61  4530.9   150.5  4551.9  147.53
  4570.2  150.08  4729.4  147.14  4804.7  145.16  4836.3   147.1  4861.2  144.45
  4878.4  147.16  4949.9  146.91  4973.1  145.47  4992.3  136.89    5022  138.59
  5027.2  142.99  5035.8   145.5  5138.6  147.44  5336.5  150.54  5648.1  155.24
  6126.9  159.35  6237.6  158.52  6289.8  152.71  6296.5  154.77  6310.7  153.38
  6329.4     158  6334.7  155.85  6352.5   159.4  6394.3  161.08    6731  170.27
#Mann= 9 ,-1 , 0
  4144.4     .05       0  4240.9      .1       0  4729.4    .075       0
  4949.9      .1       0  4973.1     .07       0  5035.8      .1       0
  5138.6     .05       0  5336.5      .1       0  5648.1    .075       0
Bank Sta=4973.1,5035.8
XS Rating Curve= 0 ,0
Exp/Cntr=0.3,0.1

Type RM Length L Ch R = 1 ,13940   ,436,436,436
BEGIN DESCRIPTION:
Crystal Creek 038 28.0
END DESCRIPTION:
XS GIS Cut Line= 3
      3826917.08     10082201.99      3826721.76      10081778.8
      3826515.96     10081074.76
#Sta/Elev= 30
  4553.8  156.37  4562.1  155.56  4567.6  156.09  4576.8  153.89  4590.6  152.98
    4608  155.03  4631.6  153.87  4751.2  151.84  4774.1  150.57  4786.1   151.2
  4808.1  149.41  4852.1  147.71  4917.3  145.19  4974.2  145.71  4984.4  144.07
  4997.1  136.68  5004.3  135.03  5008.4  135.03  5014.6  139.88  5038.4  144.28
  5173.8  147.18  5302.6  151.37  5309.2  152.34  5369.5  154.04  5455.1  157.95
    5475  157.89  5486.4  159.16  5552.4  160.74  5632.2  164.93  5753.4   169.3
#Mann= 5 ,-1 , 0
  4553.8     .05       0  4631.6      .1       0  4852.1     .12       0
  4984.4     .07       0  5038.4     .12       0
Bank Sta=4984.4,5038.4
XS Rating Curve= 0 ,0
Exp/Cntr=0.3,0.1

Type RM Length L Ch R = 1 ,13504   ,554,554,554
BEGIN DESCRIPTION:
Crystal Creek 038 27.0
END DESCRIPTION:
XS GIS Cut Line= 3
      3826934.44      10082206.3      3827127.58     10081722.38
      3826726.68     10080924.91
#Sta/Elev= 30
  4461.6  156.44  4483.8  153.19  4499.5  154.23    4539  153.18    4562  152.11
  4567.4  153.07  4575.1  151.84  4643.3  150.35  4851.9  144.32  4890.7  143.26
  4951.7  144.87  4974.3   143.2  4980.6  141.19  4986.2  141.19  4991.4  137.97
  5004.4  132.88  5008.5  132.88  5013.7  138.77  5019.3   139.1  5028.9  143.06
  5036.1  144.39  5073.6  143.51  5202.6  147.63  5319.9  150.71  5376.5  153.72
  5409.4  153.28  5622.1  162.63  5728.1  164.41  5801.2   168.1  5875.2  169.29
#Mann= 8 ,-1 , 0
  4461.6     .05       0    4539      .1       0  4575.1     .05       0
  4643.3     .12       0  4851.9      .1       0  4974.3     .07       0
  5028.9      .1       0  5202.6     .12       0
Bank Sta=4974.3,5028.9
XS Rating Curve= 0 ,0
Exp/Cntr=0.3,0.1

Type RM Length L Ch R = 1 ,12950   ,450,450,450
BEGIN DESCRIPTION:
Crystal Creek 038 26.0
END DESCRIPTION:
XS GIS Cut Line= 3
      3827183.97     10082284.48      3827633.22     10081594.34
       3827685.3     10080771.87
#Sta/Elev= 30
  4196.4   155.5  4210.2  154.61  4230.7  151.92  4251.7   152.4  4295.9  150.35
  4318.2  151.18  4331.7  149.71  4345.3  150.57  4360.5  149.58  4432.9  147.44
    4448  148.71  4475.8  146.65  4541.6  146.06  4612.8  143.72  4673.4  142.45
  4764.9  140.27  4892.2  141.59  4967.2  141.29    4976  140.02  4995.3  133.06
  5003.4  133.92 5017.01 141.212  5142.6   143.6  5293.7   146.3    5424  150.92
    5444   150.5  5488.9  152.82  5694.5  158.12  5784.7  162.46    5844  163.92
#Mann= 10 ,-1 , 0
  4196.4     .05       0  4210.2      .1       0  4360.5     .12       0
  4475.8      .1       0  4612.8     .12       0  4673.4      .1       0
  4892.2     .12       0  4967.2     .07       0 5017.01     .12       0
  5142.6     .05       0
Bank Sta=4967.2,5017.01
XS Rating Curve= 0 ,0
Exp/Cntr=0.3,0.1

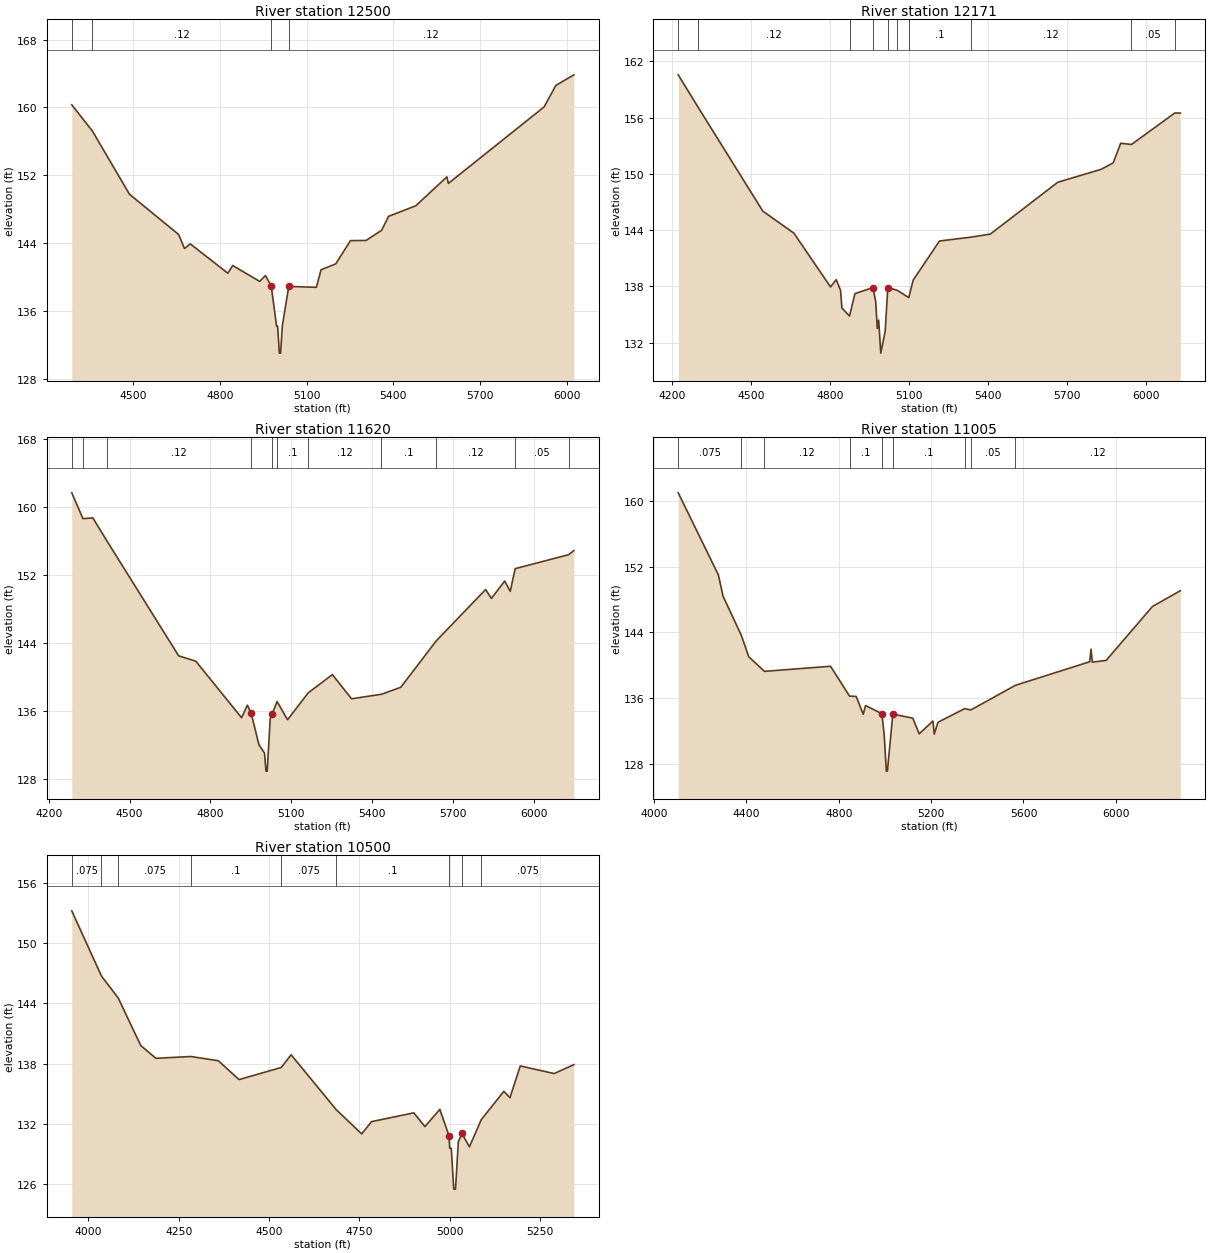
Type RM Length L Ch R = 1 ,12500   ,329,329,329
BEGIN DESCRIPTION:
Crystal Creek 038 25.0
END DESCRIPTION:
XS GIS Cut Line= 3
      3827986.95     10082440.74       3827956.2      10081728.9
      3827776.45     10080719.78
#Sta/Elev= 30
  4287.5  160.31  4358.3  157.25  4487.4  149.77  4657.5  145.03  4677.5  143.38
  4697.5  143.93  4827.7  140.47  4844.3  141.38  4937.8  139.51  4957.8   140.2
  4977.8  138.97  4996.4  134.22    5000  134.22  5005.8  131.06  5010.2  131.06
  5016.1  134.26  5038.4  138.92    5134  138.81  5150.2  140.88  5200.9  141.57
    5252  144.31  5305.9  144.33  5359.8  145.53  5383.8  147.17  5477.8  148.41
  5585.6  151.82  5590.7  151.05  5922.1  160.06  5962.7  162.59    6025  163.84
#Mann= 4 ,-1 , 0
  4287.5      .1       0  4358.3     .12       0  4977.8     .07       0
  5038.4     .12       0
Bank Sta=4977.8,5038.4
XS Rating Curve= 0 ,0
Exp/Cntr=0.3,0.1

Type RM Length L Ch R = 1 ,12171   ,551,551,551
BEGIN DESCRIPTION:
Crystal Creek 038 24.0
END DESCRIPTION:
XS GIS Cut Line= 3
      3828002.14      10082440.7       3828288.6     10081694.16
      3828761.15     10080694.87
#Sta/Elev= 30
  4224.7  160.57  4298.6  157.18  4545.6  146.03  4663.5  143.68  4802.7  137.94
  4824.1  138.72  4840.5  137.58  4845.8  135.69  4874.6  134.84  4895.2  137.23
  4963.4  137.87  4974.1  136.35  4979.9  133.51  4985.2  134.41  4993.2  130.88
  5009.9  133.21 5019.82 137.877    5056  137.58  5099.4   136.8  5116.2  138.67
  5215.8  142.84  5334.8  143.25  5408.9  143.58  5664.8  149.11  5829.6  150.49
  5875.2  151.18  5903.5  153.27  5944.4  153.14  6108.9   156.5  6129.7  156.49
#Mann= 10 ,-1 , 0
  4224.7      .1       0  4298.6     .12       0  4874.6      .1       0
  4963.4     .07       0 5019.82      .1       0    5056     .12       0
  5099.4      .1       0  5334.8     .12       0  5944.4     .05       0
  6108.9     .12       0
Bank Sta=4963.4,5019.82
XS Rating Curve= 0 ,0
Exp/Cntr=0.3,0.1

Type RM Length L Ch R = 1 ,11620   ,615,615,615
BEGIN DESCRIPTION:
Crystal Creek 038 23.0
END DESCRIPTION:
XS GIS Cut Line= 3
      3828017.89     10082461.04      3828677.06     10081874.29
      3828846.32     10080908.59
#Sta/Elev= 30
  4285.3  161.64  4326.9  158.61  4363.4   158.7  4414.7  156.05    4682  142.51
  4745.6  141.88  4915.3  135.25    4937  136.72  4951.2  135.75  4979.7  132.08
  5000.6  131.09  5005.8  128.98  5010.4  128.98  5021.6  135.13    5029   135.7
  5047.1  137.15  5085.9  135.01  5162.5  138.16  5252.3  140.31  5323.3  137.47
  5434.5     138  5506.1  138.82    5638  144.28  5820.8  150.29  5842.3  149.25
  5891.6  151.29  5912.2  150.08  5930.4  152.74  6128.8  154.38  6148.2  154.86
#Mann= 11 ,-1 , 0
  4285.3      .1       0  4326.9    .075       0  4414.7     .12       0
  4951.2     .07       0    5029     .12       0  5047.1      .1       0
  5162.5     .12       0  5434.5      .1       0    5638     .12       0
  5930.4     .05       0  6128.8     .12       0
Bank Sta=4951.2,5029
XS Rating Curve= 0 ,0
Exp/Cntr=0.3,0.1

Type RM Length L Ch R = 1 ,11005   ,505,505,505
BEGIN DESCRIPTION:
Crystal Creek 038 22.0
END DESCRIPTION:
XS GIS Cut Line= 3
      3828075.89     10082449.38      3829002.58     10082310.48
      3829599.37     10081227.58
#Sta/Elev= 30
  4105.4     161  4279.3     151  4299.5  148.41  4378.3  143.66  4410.7  141.04
  4478.7  139.26  4764.6  139.88  4846.9  136.25  4875.9   136.2  4906.2  134.03
  4916.3  135.09  4987.1  134.11  4997.2  131.47  5006.3  127.11  5010.9  127.11
  5034.4 134.054  5120.9  133.56  5148.4  131.65    5208  133.21  5213.7  131.62
  5229.8  133.06  5345.5  134.72  5372.2  134.56  5565.1  137.56  5886.7  140.43
  5892.4  141.96  5898.1  140.38  5957.8  140.59  6158.4  147.16  6278.9  149.08
#Mann= 9 ,-1 , 0
  4105.4    .075       0  4378.3     .05       0  4478.7     .12       0
  4846.9      .1       0  4987.1     .07       0  5034.4      .1       0
  5345.5     .12       0  5372.2     .05       0  5565.1     .12       0
Bank Sta=4987.1,5034.4
XS Rating Curve= 0 ,0
Exp/Cntr=0.3,0.1

Type RM Length L Ch R = 1 ,10500   ,178,178,178
BEGIN DESCRIPTION:
Crystal Creek 038 21.0
END DESCRIPTION:
XS GIS Cut Line= 3
      3828217.85     10082461.07      3829234.52     10082706.62
      3829571.16     10082774.89
#Sta/Elev= 30
  3954.1  153.23  4036.3  146.73  4082.5  144.56  4145.1  139.81    4187  138.54
  4283.6  138.72  4359.6   138.3    4417  136.42  4533.9  137.63  4561.1  138.89
  4685.8  133.43  4756.5  131.01  4783.5  132.23  4900.6  133.11  4931.4  131.74
  4972.6  133.45    4998  130.84    5000  129.58  5004.3  129.58  5011.2  125.51
    5016  125.51  5023.8  130.21    5034  131.06  5054.4  129.72  5087.5  132.44
  5149.8  135.25  5166.7  134.62  5195.3  137.78  5289.1  137.02  5343.5  137.91
#Mann= 9 ,-1 , 0
  3954.1    .075       0  4036.3     .05       0  4082.5    .075       0
  4283.6      .1       0  4533.9    .075       0  4685.8      .1       0
    4998     .07       0    5034      .1       0  5087.5    .075       0
Bank Sta=4998,5034
XS Rating Curve= 0 ,0
Exp/Cntr=0.3,0.1