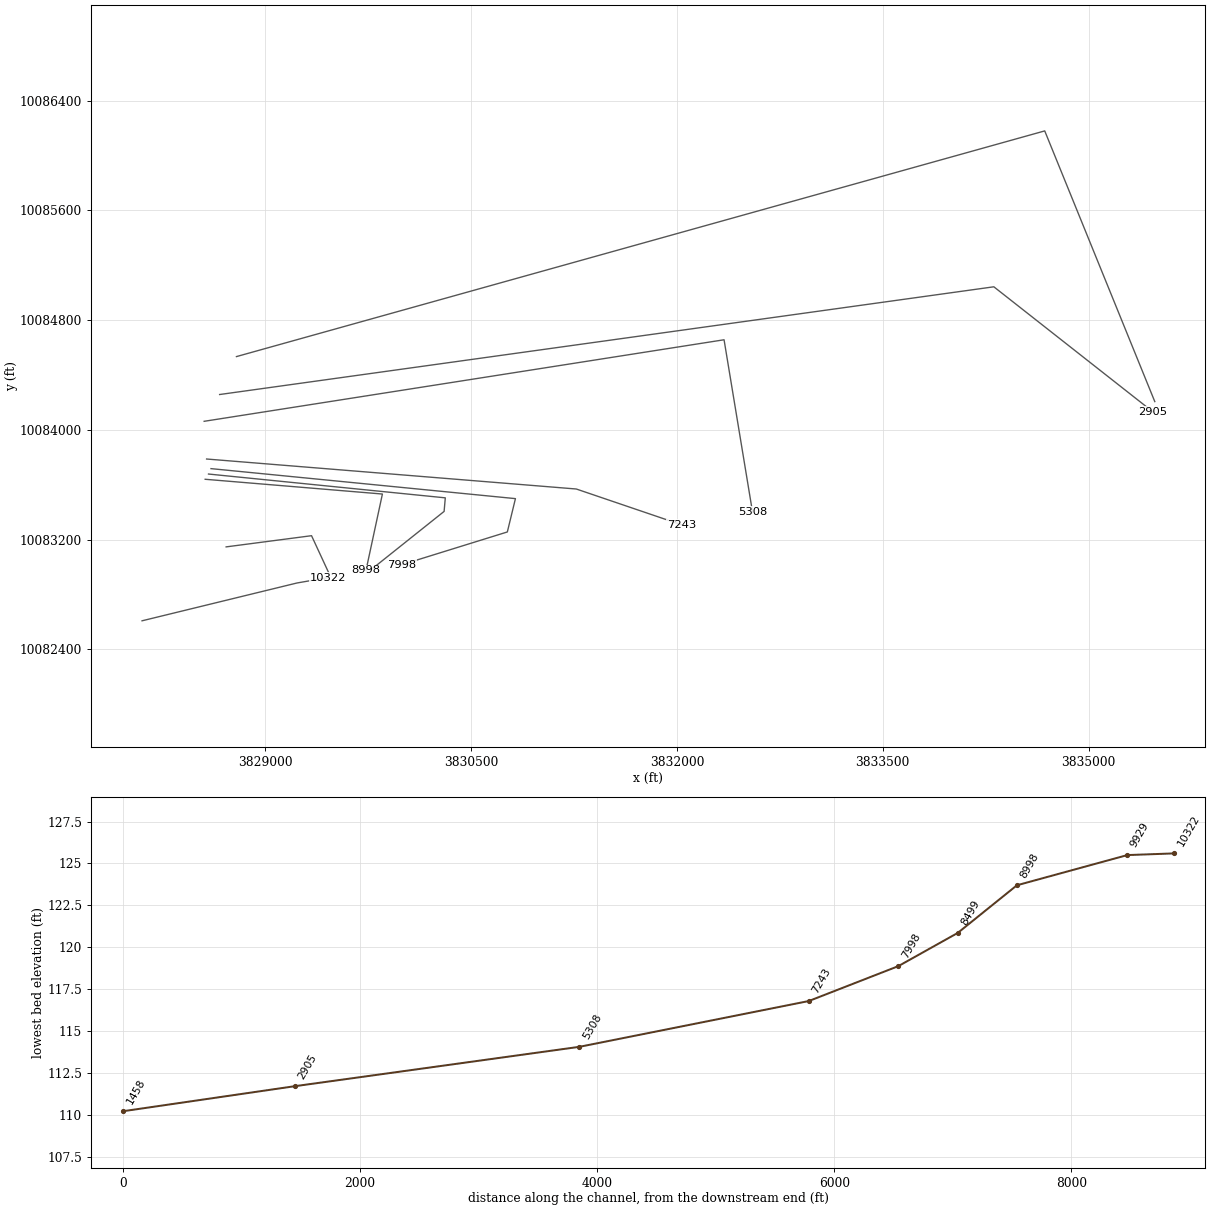
HEC-RAS study Crystal Creek 038.prj: Crystal Creek 038 Base Level Engineering

--- Crystal Creek 038.g10 (geometry) --- (continued)

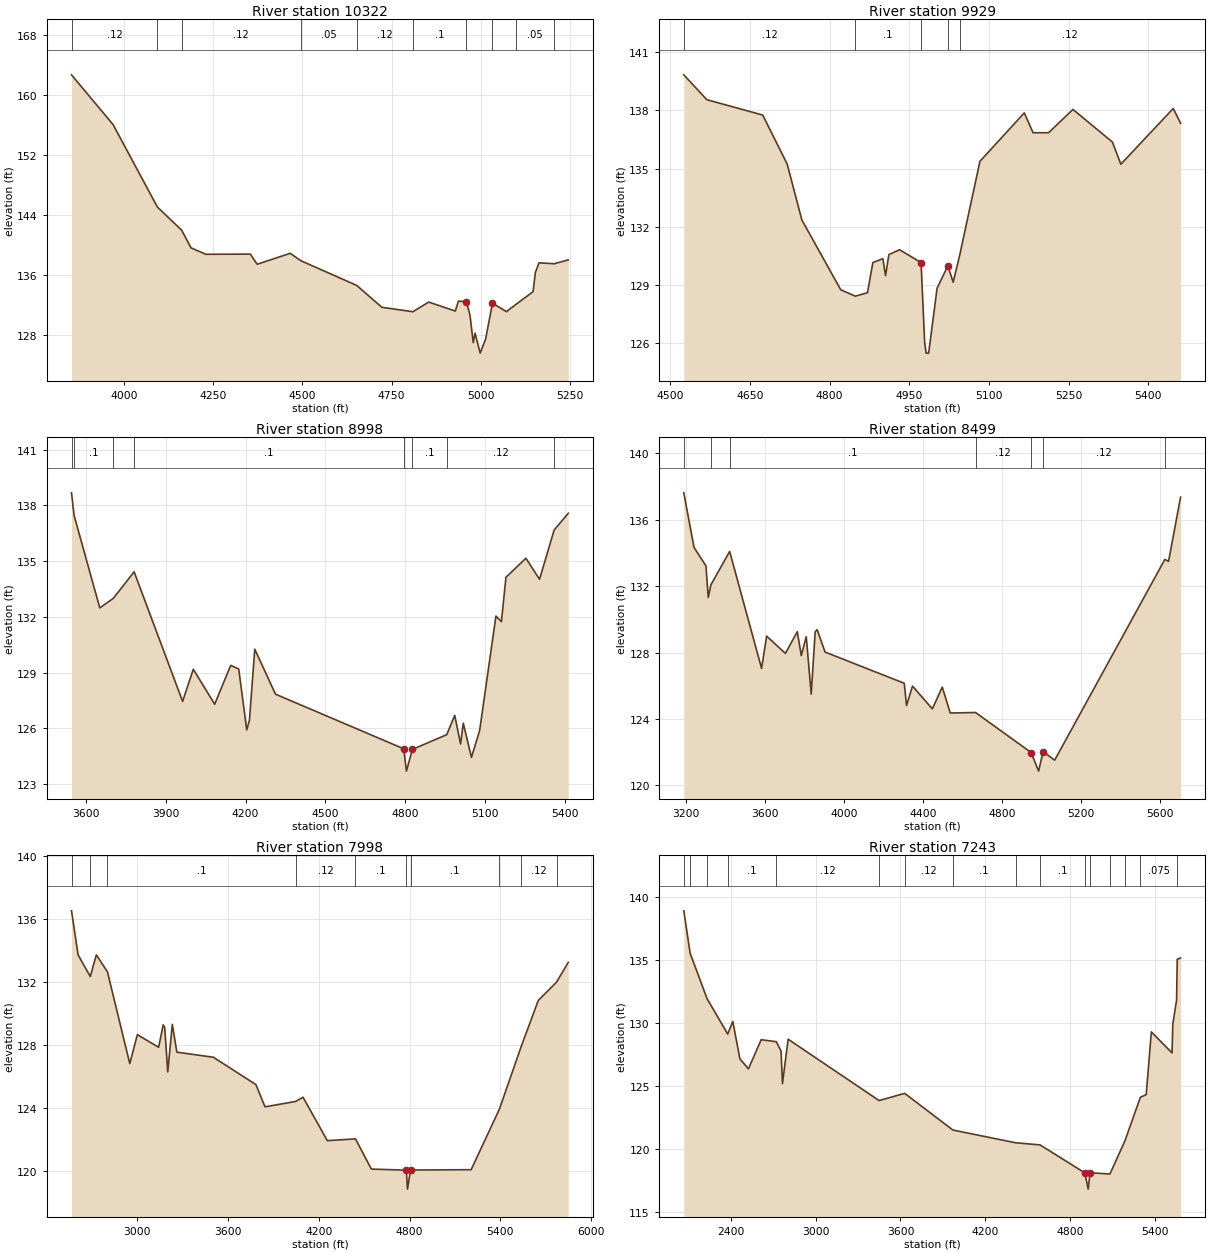
Type RM Length L Ch R = 1 ,10322   ,393,393,393
BEGIN DESCRIPTION:
Crystal Creek 038 20.0
END DESCRIPTION:
XS GIS Cut Line= 3
      3828101.98     10082607.79      3829230.44      10082883.4
      3829458.74     10082923.33
#Sta/Elev= 30
  3852.2  162.71  3968.9  156.07  4093.1  145.08  4160.9  142.01  4187.7  139.63
  4229.1  138.78  4354.1   138.8  4372.9  137.45  4465.6  138.91  4495.6  137.92
  4652.2  134.63  4722.9  131.71  4809.8  131.12  4854.1  132.41  4928.8  131.21
  4937.4  132.53  4959.7  132.48    4970  130.65    4979     127  4984.2  128.26
  4998.5   125.6  5013.8  127.48    5033  132.26  5072.1  131.13  5098.3  132.08
  5146.8  133.79  5153.3  136.35  5163.5  137.64  5206.6  137.52  5245.6  138.04
#Mann= 10 ,-1 , 0
  3852.2     .12       0  4093.1     .05       0  4160.9     .12       0
  4495.6     .05       0  4652.2     .12       0  4809.8      .1       0
  4959.7     .07       0    5033      .1       0  5098.3     .05       0
  5206.6     .12       0
Bank Sta=4959.7,5033
XS Rating Curve= 0 ,0
Exp/Cntr=0.3,0.1

Type RM Length L Ch R = 1 ,9929    ,931,931,931
BEGIN DESCRIPTION:
Crystal Creek 038 19.0
END DESCRIPTION:
XS GIS Cut Line= 3
      3828714.79     10083146.85      3829337.21     10083228.45
      3829466.54     10082948.97
#Sta/Elev= 30
  4525.4  139.82  4568.8  138.54    4674  137.75  4720.1  135.23  4747.8  132.35
    4821  128.76  4848.6  128.43  4871.4  128.61  4881.5  130.16  4900.3  130.36
  4905.4  129.49  4911.7  130.57  4931.9  130.82  4972.3  130.16  4979.1  126.05
  4981.8   125.5  4986.6   125.5  5002.5  128.84  5022.7  129.99  5032.8  129.15
  5045.4  130.58  5083.2  135.37  5166.7  137.86  5183.3  136.84  5212.5  136.84
  5258.4  138.04  5332.7  136.36  5348.6  135.22  5447.3  138.09  5461.1  137.33
#Mann= 5 ,-1 , 0
  4525.4     .12       0  4848.6      .1       0  4972.3     .07       0
  5022.7      .1       0  5045.4     .12       0
Bank Sta=4972.3,5022.7
XS Rating Curve= 0 ,0
Exp/Cntr=0.3,0.1

Type RM Length L Ch R = 1 ,8998    ,499,499,499
BEGIN DESCRIPTION:
Crystal Creek 038 18.0
END DESCRIPTION:
XS GIS Cut Line= 3
        3828562.     10083639.91       3829853.7     10083532.27
      3829734.04     10082975.57
#Sta/Elev= 30
  3546.2  138.67    3556  137.45  3652.4  132.48  3702.9  132.99  3781.4  134.42
  3963.5  127.45  4003.6  129.18  4083.9   127.3  4144.1  129.39  4174.2  129.19
  4204.3  125.92  4214.4  126.43  4234.4  130.26  4312.3  127.84    4794   124.9
    4804   123.7  4826.5  124.87  4955.3  125.66  4985.4   126.7  5007.3  125.16
  5017.5  126.28  5048.2  124.44  5078.9  125.88  5140.2  132.04  5160.7  131.74
  5177.8  134.13  5252.7  135.15  5303.9  134.02  5358.8  136.67  5411.8  137.57
#Mann= 8 ,-1 , 0
  3546.2     .12       0    3556      .1       0  3702.9     .12       0
  3781.4      .1       0    4794     .03       0  4826.5      .1       0
  4955.3     .12       0  5358.8     .05       0
Bank Sta=4794,4826.5
XS Rating Curve= 0 ,0
Exp/Cntr=0.3,0.1

Type RM Length L Ch R = 1 ,8499    ,501,501,501
BEGIN DESCRIPTION:
Crystal Creek 038 17.0
END DESCRIPTION:
XS GIS Cut Line= 4
      3828586.31     10083678.11      3830312.04     10083504.49
      3830303.36     10083405.54      3829771.61     10082981.17
#Sta/Elev= 30
  3189.8  137.62  3241.6  134.33  3301.9  133.22  3313.5  131.32    3327  132.08
  3421.8  134.09  3583.3  127.05  3609.1  128.99  3703.9  127.95  3764.2  129.26
  3784.3  127.82  3809.5  128.96  3834.6   125.5  3854.7  129.25  3864.7  129.38
  3904.7  128.03  4305.5  126.15    4317  124.81  4347.2  125.98  4447.7  124.61
  4497.9  125.92  4538.1  124.36  4666.3  124.39  4947.7  121.98  4985.5  120.86
    5008  122.04  5066.7  121.52  5624.4  133.61  5643.1  133.49  5703.9  137.36
#Mann= 7 ,-1 , 0
  3189.8      .1       0    3327     .12       0  3421.8      .1       0
  4666.3     .12       0  4947.7     .03       0    5008     .12       0
  5624.4     .05       0
Bank Sta=4947.7,5008
XS Rating Curve= 0 ,0
Exp/Cntr=0.3,0.1

Type RM Length L Ch R = 1 ,7998    ,755,755,755
BEGIN DESCRIPTION:
Crystal Creek 038 16.0
END DESCRIPTION:
XS GIS Cut Line= 4
      3828604.45     10083717.53      3830823.21     10083498.78
      3830764.19     10083255.72      3829995.08     10083016.83
#Sta/Elev= 30
  2564.5   136.5  2608.1  133.71  2688.7  132.34  2728.7  133.71    2802  132.64
  2949.8  126.83    3000  128.66  3140.7  127.86  3170.8  129.28  3180.9  129.11
    3201   126.3  3231.1  129.31  3261.3  127.55  3502.4  127.23  3783.8   125.5
  3844.1  124.09  4046.3  124.43  4095.3   124.7  4256.1  121.95  4442.3  122.06
  4547.5  120.15  4778.6  120.08  4786.2  118.88 4806.55  120.09  5207.1  120.11
  5394.4  123.95  5538.5  127.92  5651.3  130.83  5772.4  131.99  5849.5  133.24
#Mann= 10 ,-1 , 0
  2564.5      .1       0  2688.7     .12       0    2802      .1       0
  4046.3     .12       0  4442.3      .1       0  4778.6     .03       0
 4806.55      .1       0  5394.4     .05       0  5538.5     .12       0
  5772.4     .05       0
Bank Sta=4778.6,4806.55
XS Rating Curve= 0 ,0
Exp/Cntr=0.3,0.1

Type RM Length L Ch R = 1 ,7243    ,1935,1935,1935
BEGIN DESCRIPTION:
Crystal Creek 038 14.0
END DESCRIPTION:
XS GIS Cut Line= 3
      3828572.37     10083787.67      3831266.79     10083568.92
      3832033.71     10083307.93
#Sta/Elev= 30
  2067.8  138.89  2112.7  135.52  2232.7  131.91  2378.4  129.11  2414.4  130.11
  2464.6  127.14  2524.8  126.35  2615.1  128.66  2722.5   128.5  2755.5  127.76
  2765.6  125.18  2805.7   128.7  3448.9  123.83  3630.1   124.4    3971  121.49
  4414.3  120.48  4587.5  120.31  4904.2  118.09  4927.6   116.8  4941.2   118.1
  5081.6     118  5187.2  120.62    5297  124.09    5338   124.3  5374.6  129.28
  5520.9  127.61  5526.2  129.89  5553.1  131.82  5557.5  135.04  5581.2  135.15
#Mann= 16 ,-1 , 0
  2067.8     .12       0  2112.7      .1       0  2232.7     .12       0
  2378.4      .1       0  2722.5     .12       0  3448.9      .1       0
  3630.1     .12       0    3971      .1       0  4414.3     .12       0
  4587.5      .1       0  4904.2     .03       0  4941.2      .1       0
  5081.6     .05       0  5187.2     .12       0    5297    .075       0
  5553.1     .05       0
Bank Sta=4904.2,4941.2
XS Rating Curve= 0 ,0
Exp/Cntr=0.3,0.1

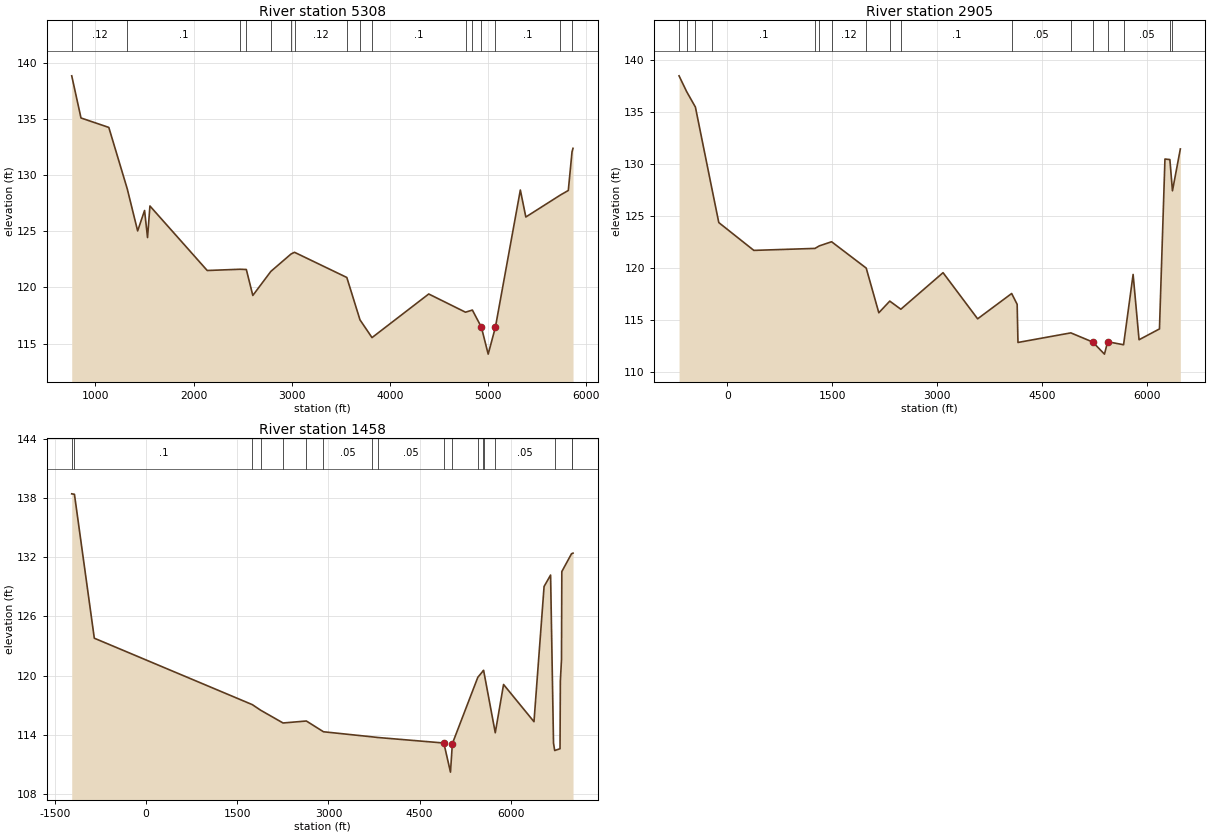
Type RM Length L Ch R = 1 ,5308    ,2403,2403,2403
BEGIN DESCRIPTION:
Crystal Creek 038 10.0
END DESCRIPTION:
XS GIS Cut Line= 3
      3828554.56     10084062.66      3832343.65     10084657.28
      3832551.08     10083400.95
#Sta/Elev= 30
   758.7  138.83   853.1  135.08  1136.6  134.24  1324.7  128.77  1430.5  125.03
    1501  126.85  1531.3  124.44  1555.7  127.25  2139.5  121.51  2473.2  121.62
  2538.1   121.6  2604.3  119.29    2788  121.43    2994  122.98    3029  123.13
  3562.2  120.89  3696.4  117.12  3819.1  115.54    4397  119.42  4771.7   117.8
  4841.8  117.99 4933.61 116.466  5002.9  114.07  5076.1  116.45  5330.6  128.67
  5386.6  126.27  5739.7  128.23  5819.4  128.63  5857.3  132.07  5867.5  132.38
#Mann= 16 ,-1 , 0
   758.7     .12       0  1324.7      .1       0  2473.2     .12       0
  2538.1      .1       0    2788     .12       0    2994      .1       0
    3029     .12       0  3562.2      .1       0  3696.4     .12       0
  3819.1      .1       0  4771.7     .12       0  4841.8      .1       0
 4933.61     .07       0  5076.1      .1       0  5739.7     .05       0
  5857.3    .075       0
Bank Sta=4933.61,5076.1
XS Rating Curve= 0 ,0
Exp/Cntr=0.3,0.1

Type RM Length L Ch R = 1 ,2905    ,1447,1447,1447
BEGIN DESCRIPTION:
Crystal Creek 038 6.0
END DESCRIPTION:
XS GIS Cut Line= 3
       3828667.4     10084257.97       3834309.8     10085043.56
      3835468.67     10084132.09
#Sta/Elev= 30
  -689.7  138.44  -580.7  136.92  -455.8  135.44  -224.1  127.75  -121.1  124.35
   380.1  121.68    1255  121.87    1316  122.11  1492.4  122.51  1987.7  119.98
  2168.1  115.69  2324.5  116.81  2483.1  116.03  3086.8  119.54  3581.6  115.11
  4068.3  117.54    4147   116.5  4158.6  112.84  4915.1  113.76  5228.4  112.88
  5395.8  111.72  5441.7  112.91  5669.3  112.62  5805.8  119.37  5890.8   113.1
  6182.7  114.14  6261.3  130.45  6331.6   130.4  6368.7   127.4  6481.5  131.42
#Mann= 17 ,-1 , 0
  -689.7     .12       0  -580.7      .1       0  -455.8     .12       0
  -224.1      .1       0    1255     .12       0    1316      .1       0
  1492.4     .12       0  1987.7      .1       0  2324.5     .12       0
  2483.1      .1       0  4068.3     .05       0  4915.1      .1       0
  5228.4     .03       0  5441.7      .1       0  5669.3     .05       0
  6331.6    .075       0  6368.7     .05       0
Bank Sta=5228.4,5441.7
XS Rating Curve= 0 ,0
Exp/Cntr=0.3,0.1

Type RM Length L Ch R = 1 ,1458    ,0,0,0
BEGIN DESCRIPTION:
Crystal Creek 038 2.0
END DESCRIPTION:
XS GIS Cut Line= 3
      3828790.04     10084534.59      3834680.64     10086180.42
      3835482.72     10084206.45
#Sta/Elev= 30
 -1223.7  138.43   -1179  138.38  -852.2   123.8    1747  117.07  1885.1   116.5
  2252.8  115.21  2636.3  115.41  2917.9  114.32  3709.3  113.81  3810.6  113.74
  4897.8  113.18  5007.2  110.23 5038.18 113.116  5457.1  119.84  5537.8  120.44
  5551.9  120.55  5744.1  114.22  5880.4  119.11    6381  115.34    6547  129.04
  6654.1   130.2  6702.3  113.16  6721.7  112.42  6809.4   112.6  6814.8  119.47
  6833.5  121.62  6838.9  130.55  6998.4  132.36  7010.9  132.39  7023.2  132.42
#Mann= 18 ,-1 , 0
 -1223.7     .12       0   -1179      .1       0    1747     .05       0
  1885.1      .1       0  2252.8     .05       0  2636.3      .1       0
  2917.9     .05       0  3709.3      .1       0  3810.6     .05       0
  4897.8     .07       0 5038.18     .05       0  5457.1    .075       0
  5537.8     .05       0  5551.9    .075       0  5744.1     .05       0
  6721.7    .075       0  6998.4     .05       0  7010.9      .1       0
Bank Sta=4897.8,5038.18
XS Rating Curve= 0 ,0
Exp/Cntr=0.3,0.1