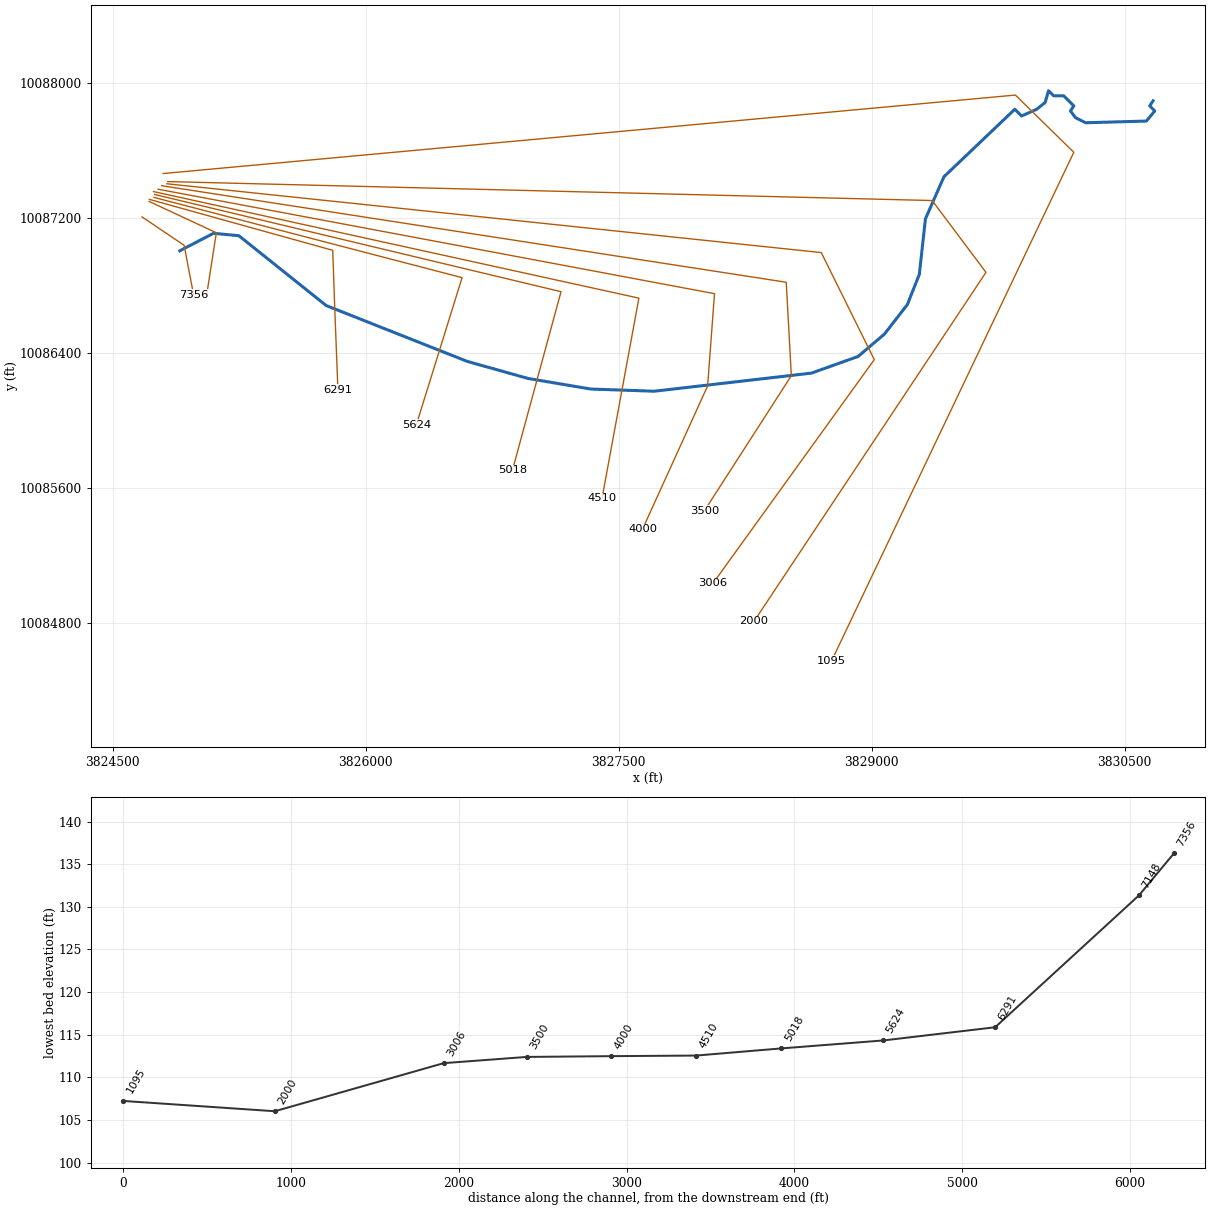
--- Crystal Creek 039.prj (project) ---

Proj Title=Crystal Creek 039 Base Level Engineering
Current Plan=p01
Default Exp/Contr=0.3,0.1
English Units
Geom File=g01
Flow File=f01
Flow File=f02
Plan File=p01
Y Axis Title=Elevation
X Axis Title(PF)=Main Channel Distance
X Axis Title(XS)=Station
BEGIN DESCRIPTION:
Crystal Creek 039
END DESCRIPTION:
DSS Export Rating Curves= 0
DSS Export Rating Curve Sorted= 0
DSS Export Volume Flow Curves= 0
DXF OffsetX= 0
DXF OffsetY= 0
DXF ScaleX= 1
DXF ScaleY= 10

--- Crystal Creek 039.p01 (plan) ---

Plan Title=Multiple Run
Short Identifier=Multiple
Geom File=g01
Flow File=f01
Subcritical Flow
K Sum by GR= 0
Std Step Tol= 0.01
Critical Tol= 0.01
Num of Std Step Trials= 20
Max Error Tol= 0.3
Flow Tol Ratio= 0.001
Split Flow NTrial= 30
Split Flow Tol= 0.02
Split Flow Ratio= 0.02
Log Output Level= 0
Friction Slope Method= 1
Unsteady Friction Slope Method= 2
Unsteady Bridges Friction Slope Method= 1
Parabolic Critical Depth
Global Vel Dist=  1 , 1 , 1
Global Log Level= 0
CheckData=True
Encroach Param= -1, 0, 0, 0
BEGIN DESCRIPTION:
Multiple Run
END DESCRIPTION:

--- Crystal Creek 039.f01 (steady flow) ---

Flow Title=Multiple
Program Version=4.10
Number of Profiles= 7
Profile Names=10-year,25-year,50-year,1pct_min,100-year,1pct_plu,500-year
River Rch & RM=Crystal Creek 03,Reach-1         ,7356
     679     919    1242     553    1669    5040    3111
Boundary for River Rch & Prof#=Crystal Creek 03,Reach-1         , 1
Up Type= 0
Dn Type= 3
Dn Slope=0.005
Boundary for River Rch & Prof#=Crystal Creek 03,Reach-1         , 2
Up Type= 0
Dn Type= 3
Dn Slope=0.005
Boundary for River Rch & Prof#=Crystal Creek 03,Reach-1         , 3
Up Type= 0
Dn Type= 3
Dn Slope=0.005
Boundary for River Rch & Prof#=Crystal Creek 03,Reach-1         , 4
Up Type= 0
Dn Type= 3
Dn Slope=0.005
Boundary for River Rch & Prof#=Crystal Creek 03,Reach-1         , 5
Up Type= 0
Dn Type= 3
Dn Slope=0.005
Boundary for River Rch & Prof#=Crystal Creek 03,Reach-1         , 6
Up Type= 0
Dn Type= 3
Dn Slope=0.005
Boundary for River Rch & Prof#=Crystal Creek 03,Reach-1         , 7
Up Type= 0
Dn Type= 3
Dn Slope=0.005
DSS Import GetInterval= 0
DSS Import GetPeak= 0
DSS Import FillOption= 0

--- Crystal Creek 039.f02 (steady flow) ---

Flow Title=Orig_BLE_Flow
Program Version=4.10
Number of Profiles= 7
Profile Names=10-year,25-year,50-year,1pct_min,100-year,1pct_plu,500-year
River Rch & RM=Crystal Creek 03,Reach-1         ,7356
     679     901    1080     425    1284    3877    1809
Boundary for River Rch & Prof#=Crystal Creek 03,Reach-1         , 1
Up Type= 0
Dn Type= 3
Dn Slope=0.005
Boundary for River Rch & Prof#=Crystal Creek 03,Reach-1         , 2
Up Type= 0
Dn Type= 3
Dn Slope=0.005
Boundary for River Rch & Prof#=Crystal Creek 03,Reach-1         , 3
Up Type= 0
Dn Type= 3
Dn Slope=0.005
Boundary for River Rch & Prof#=Crystal Creek 03,Reach-1         , 4
Up Type= 0
Dn Type= 3
Dn Slope=0.005
Boundary for River Rch & Prof#=Crystal Creek 03,Reach-1         , 5
Up Type= 0
Dn Type= 3
Dn Slope=0.005
Boundary for River Rch & Prof#=Crystal Creek 03,Reach-1         , 6
Up Type= 0
Dn Type= 3
Dn Slope=0.005
Boundary for River Rch & Prof#=Crystal Creek 03,Reach-1         , 7
Up Type= 0
Dn Type= 3
Dn Slope=0.005
DSS Import GetInterval= 0
DSS Import GetPeak= 0
DSS Import FillOption= 0

--- Crystal Creek 039.g01 (geometry) ---

Geom Title=Existing Conditions
Program Version=4.10

River Reach=Crystal Creek 03,Reach-1
Reach XY= 30
      3824896.87     10087007.47      3825096.77     10087111.35
       3825246.8     10087097.02      3825765.08     10086682.79
      3826600.86     10086351.83      3826962.38     10086250.37
      3827334.35     10086187.79      3827710.42     10086174.82
      3828642.32     10086282.23       3828918.8     10086380.83
      3829074.77     10086513.25      3829211.22     10086688.88
      3829281.99     10086867.48      3829318.24     10087196.86
      3829428.24     10087446.86      3829848.24     10087846.86
      3829888.24     10087806.86      3829978.24     10087846.86
      3830028.24     10087886.86      3830048.24     10087956.86
      3830078.24     10087926.86      3830138.24     10087926.86
      3830198.24     10087866.86      3830178.24     10087836.86
      3830208.24     10087796.86      3830268.24     10087766.86
      3830628.24     10087776.86      3830678.24     10087836.86
      3830648.24     10087866.86      3830668.24     10087896.86

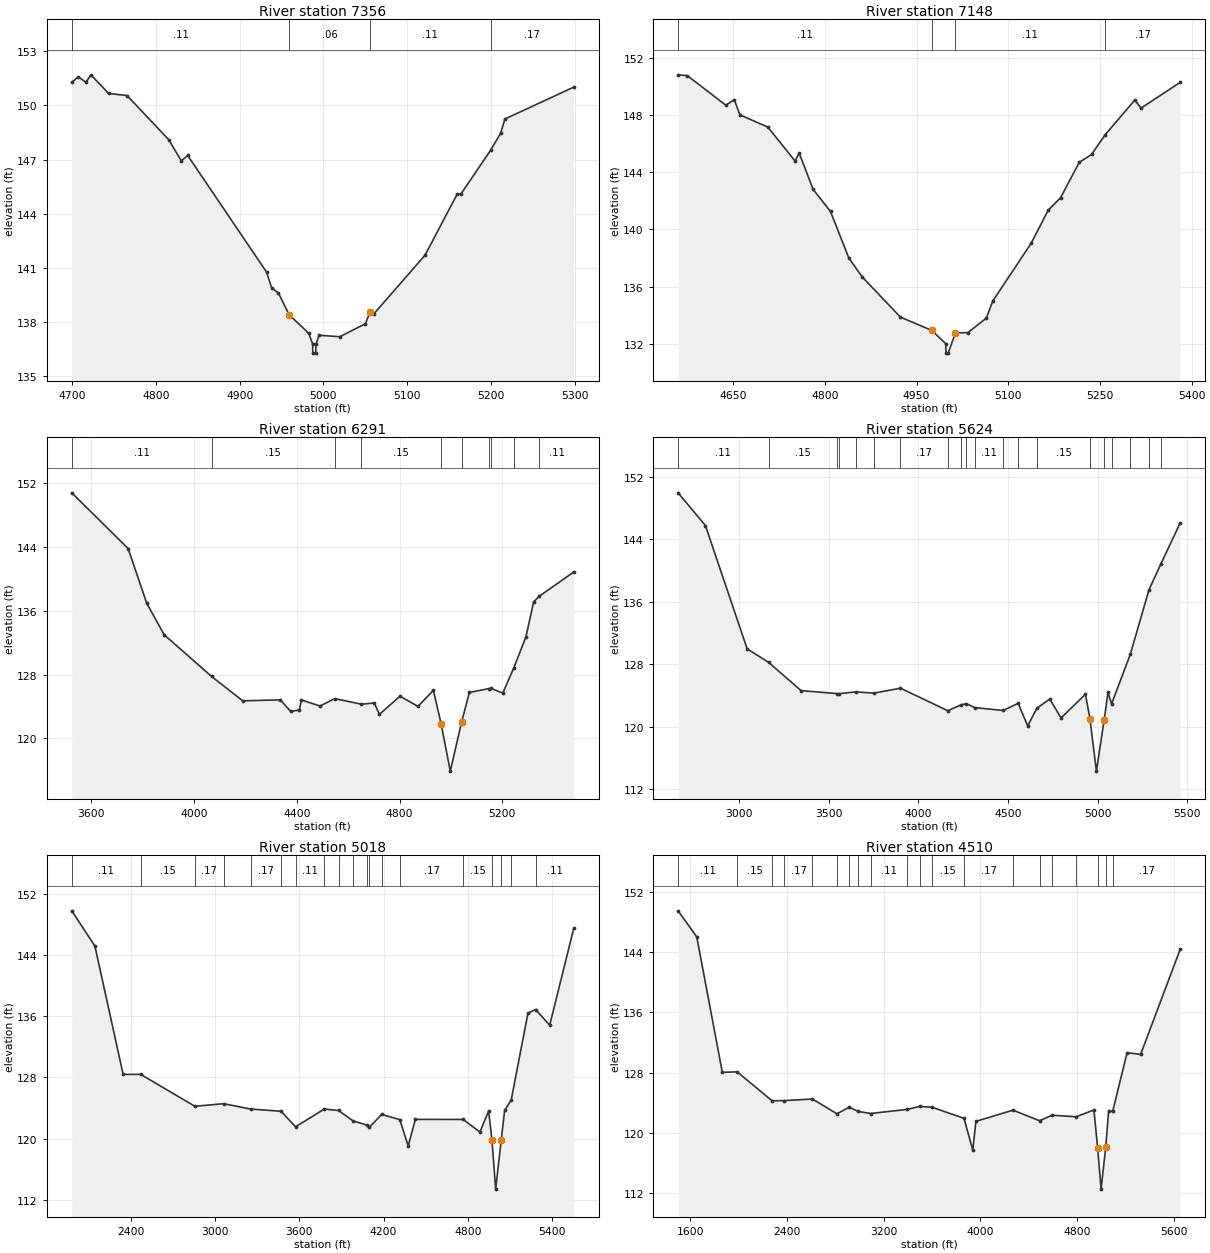
Type RM Length L Ch R = 1 ,7356    ,208,208,208
BEGIN DESCRIPTION:
Crystal Creek 039 14.0
END DESCRIPTION:
XS GIS Cut Line= 3
        3824673.     10087208.28      3824922.39     10087040.28
      3824978.55      10086746.5
#Sta/Elev= 30
  4699.3  151.28  4707.2  151.59  4716.2  151.29  4722.2   151.7  4743.2  150.67
  4765.4  150.55  4815.2   148.1  4830.2  146.93  4837.8  147.23  4932.1  140.76
  4938.1  139.89  4946.3   139.6  4959.1  138.39  4982.5  137.37  4987.1  136.77
  4987.3  136.27  4990.8  136.27  4991.1  136.77  4994.8  137.26  5019.6  137.18
  5050.1   137.9  5055.5  138.53  5060.5  138.46  5121.4   141.7  5159.6  145.07
  5164.7  145.12  5199.9  147.53  5211.7  148.46  5216.8  149.25  5299.1  151.02
#Mann= 4 ,-1 , 0
  4699.3     .11       0  4959.1     .06       0  5055.5     .11       0
  5199.9     .17       0
Bank Sta=4959.1,5055.5
XS Rating Curve= 0 ,0
Exp/Cntr=0.3,0.1

Type RM Length L Ch R = 1 ,7148    ,857,857,857
BEGIN DESCRIPTION:
Crystal Creek 039 13.0
END DESCRIPTION:
XS GIS Cut Line= 3
      3824714.63     10087300.31      3825113.57     10087114.48
      3825054.94     10086737.81
#Sta/Elev= 30
  4559.9  150.82    4575  150.76  4638.1  148.69  4651.7  149.09  4660.9  148.02
  4706.7  147.16    4751   144.8    4758  145.34  4780.8   142.8  4809.2  141.26
  4839.2     138  4861.3  136.67  4923.6  133.87  4974.8  132.94  4997.7  132.01
  4998.2  131.35  5001.7  131.35  5013.6  132.77  5033.8  132.78  5064.2   133.8
  5074.5  134.99  5137.4  139.03  5165.4  141.35  5185.6  142.22    5216  144.69
  5236.2  145.25  5258.8  146.64  5307.1  149.06  5317.2  148.49  5381.2  150.29
#Mann= 4 ,-1 , 0
  4559.9     .11       0  4974.8     .06       0  5013.6     .11       0
  5258.8     .17       0
Bank Sta=4974.8,5013.6
XS Rating Curve= 0 ,0
Exp/Cntr=0.3,0.1

Type RM Length L Ch R = 1 ,6291    ,667,667,667
BEGIN DESCRIPTION:
Crystal Creek 039 12.0
END DESCRIPTION:
XS GIS Cut Line= 4
      3824716.44     10087312.44      3825803.69     10087010.38
      3825815.81     10086661.35      3825834.42     10086184.98
#Sta/Elev= 30
  3523.7   150.8  3743.1  143.81  3815.8  136.93  3883.5  132.99  4068.1  127.76
  4189.4   124.7  4335.9  124.82  4376.2  123.37  4409.6  123.55  4417.7  124.81
  4490.4  124.05  4547.5  124.98    4651  124.28  4701.5  124.43  4721.5     123
  4801.5  125.28  4871.6  124.01  4931.6  126.01  4961.6  121.84  4997.3  115.88
  5041.7  122.08  5071.7  125.75  5146.8  126.23  5156.5  126.25  5201.8  125.68
  5245.1  128.87  5291.9  132.73  5321.9  137.12  5343.3  137.81  5478.1  140.87
#Mann= 10 ,-1 , 0
  3523.7     .11       0  4068.1     .15       0  4547.5     .17       0
    4651     .15       0  4961.6     .09       0  5041.7     .15       0
  5146.8     .17       0  5156.5     .15       0  5245.1     .17       0
  5343.3     .11       0
#XS Ineff= 2 , 0
       0  4931.6  126.01               0
Permanent Ineff=
       F       F
Bank Sta=4961.6,5041.7
XS Rating Curve= 0 ,0
Exp/Cntr=0.3,0.1

Type RM Length L Ch R = 1 ,5624    ,606,606,606
BEGIN DESCRIPTION:
Crystal Creek 039 11.0
END DESCRIPTION:
XS GIS Cut Line= 3
      3824744.17     10087324.03      3826570.57     10086848.33
      3826299.72     10085976.77
#Sta/Elev= 30
  2660.9  149.93    2813  145.75  3045.7  129.98  3166.1  128.23  3346.7  124.63
  3547.2  124.25  3557.5  124.23  3650.2  124.47  3753.2  124.31  3900.6  124.94
    4165  122.06    4238   122.8  4269.2  122.97    4314  122.46  4473.9  122.09
  4557.4     123  4610.7  120.11  4661.6  122.37  4733.9  123.55  4796.7  121.13
  4932.8  124.17 4957.92 121.022  4993.9  114.33  5037.5  120.93  5058.5  124.41
  5078.5  122.93  5182.7  129.26  5286.9  137.51  5354.1  140.87  5460.9  146.07
#Mann= 20 ,-1 , 0
  2660.9     .11       0  3166.1     .15       0  3547.2     .17       0
  3557.5     .15       0  3650.2     .17       0  3753.2     .15       0
  3900.6     .17       0    4165     .15       0    4238     .11       0
  4269.2     .15       0    4314     .11       0  4473.9     .17       0
  4557.4     .11       0  4661.6     .15       0 4957.92     .09       0
  5037.5     .15       0  5078.5     .11       0  5182.7     .17       0
  5286.9     .11       0  5354.1     .17       0
Bank Sta=4957.92,5037.5
XS Rating Curve= 0 ,0
Exp/Cntr=0.3,0.1

Type RM Length L Ch R = 1 ,5018    ,508,508,508
BEGIN DESCRIPTION:
Crystal Creek 039 10.0
END DESCRIPTION:
XS GIS Cut Line= 3
      3824747.65     10087341.39      3827157.37       10086765.
      3826869.19     10085706.01
#Sta/Elev= 30
  1979.8  149.75  2144.5  145.16  2345.8  128.38  2470.7  128.39  2856.7  124.22
  3061.4  124.56  3252.9  123.86  3470.9  123.57  3573.3  121.54    3778  123.86
  3880.4  123.67  3982.7  122.31  4085.1  121.75  4097.6  121.46  4187.5  123.16
  4316.1  122.48  4375.7  119.05  4427.1  122.51  4767.8   122.5  4886.5  120.86
  4948.7  123.61  4972.2  119.87  4998.7   113.4 5038.44119.8089  5062.7  123.69
  5109.2  125.01  5228.5  136.37  5282.7  136.86  5383.7  134.81    5555  147.48
#Mann= 19 ,-1 , 0
  1979.8     .11       0  2470.7     .15       0  2856.7     .17       0
  3061.4     .15       0  3252.9     .17       0  3470.9     .15       0
  3573.3     .11       0    3778     .17       0  3880.4     .11       0
  3982.7     .17       0  4085.1     .15       0  4097.6     .17       0
  4187.5     .15       0  4316.1     .17       0  4767.8     .15       0
  4972.2     .09       0 5038.44     .15       0  5109.2     .17       0
  5282.7     .11       0
Bank Sta=4972.2,5038.44
XS Rating Curve= 0 ,0
Exp/Cntr=0.3,0.1

Type RM Length L Ch R = 1 ,4510    ,510,510,510
BEGIN DESCRIPTION:
Crystal Creek 039 9.0
END DESCRIPTION:
XS GIS Cut Line= 3
      3824740.68     10087358.75      3827619.18      10086726.8
      3827400.43     10085539.34
#Sta/Elev= 30
  1498.4  149.47  1652.5  146.01  1864.1  128.05  1987.1  128.11  2275.6  124.28
  2377.4   124.3    2610  124.51  2813.4  122.55  2913.2  123.43  2988.5  122.87
  3090.4  122.59  3395.9  123.14  3497.8  123.53  3599.6  123.42  3864.2  121.95
  3936.6  117.75  3962.9  121.55  4269.2  123.03  4490.3  121.63    4591  122.36
  4792.4  122.16  4939.4  123.06  4969.9  118.06  4998.6  112.56 5037.42118.1854
  5061.4  122.98  5094.5  122.86  5213.9  130.67  5325.8  130.42  5652.9  144.35
#Mann= 20 ,-1 , 0
  1498.4     .11       0  1987.1     .15       0  2275.6     .15       0
  2377.4     .17       0    2610     .15       0  2813.4     .17       0
  2913.2     .15       0  2988.5     .17       0  3090.4     .11       0
  3395.9     .17       0  3497.8     .17       0  3599.6     .15       0
  3864.2     .17       0  4269.2     .15       0  4490.3     .17       0
    4591     .11       0  4792.4     .15       0  4969.9     .09       0
 5037.42     .15       0  5094.5     .17       0
Bank Sta=4969.9,5037.42
XS Rating Curve= 0 ,0
Exp/Cntr=0.3,0.1

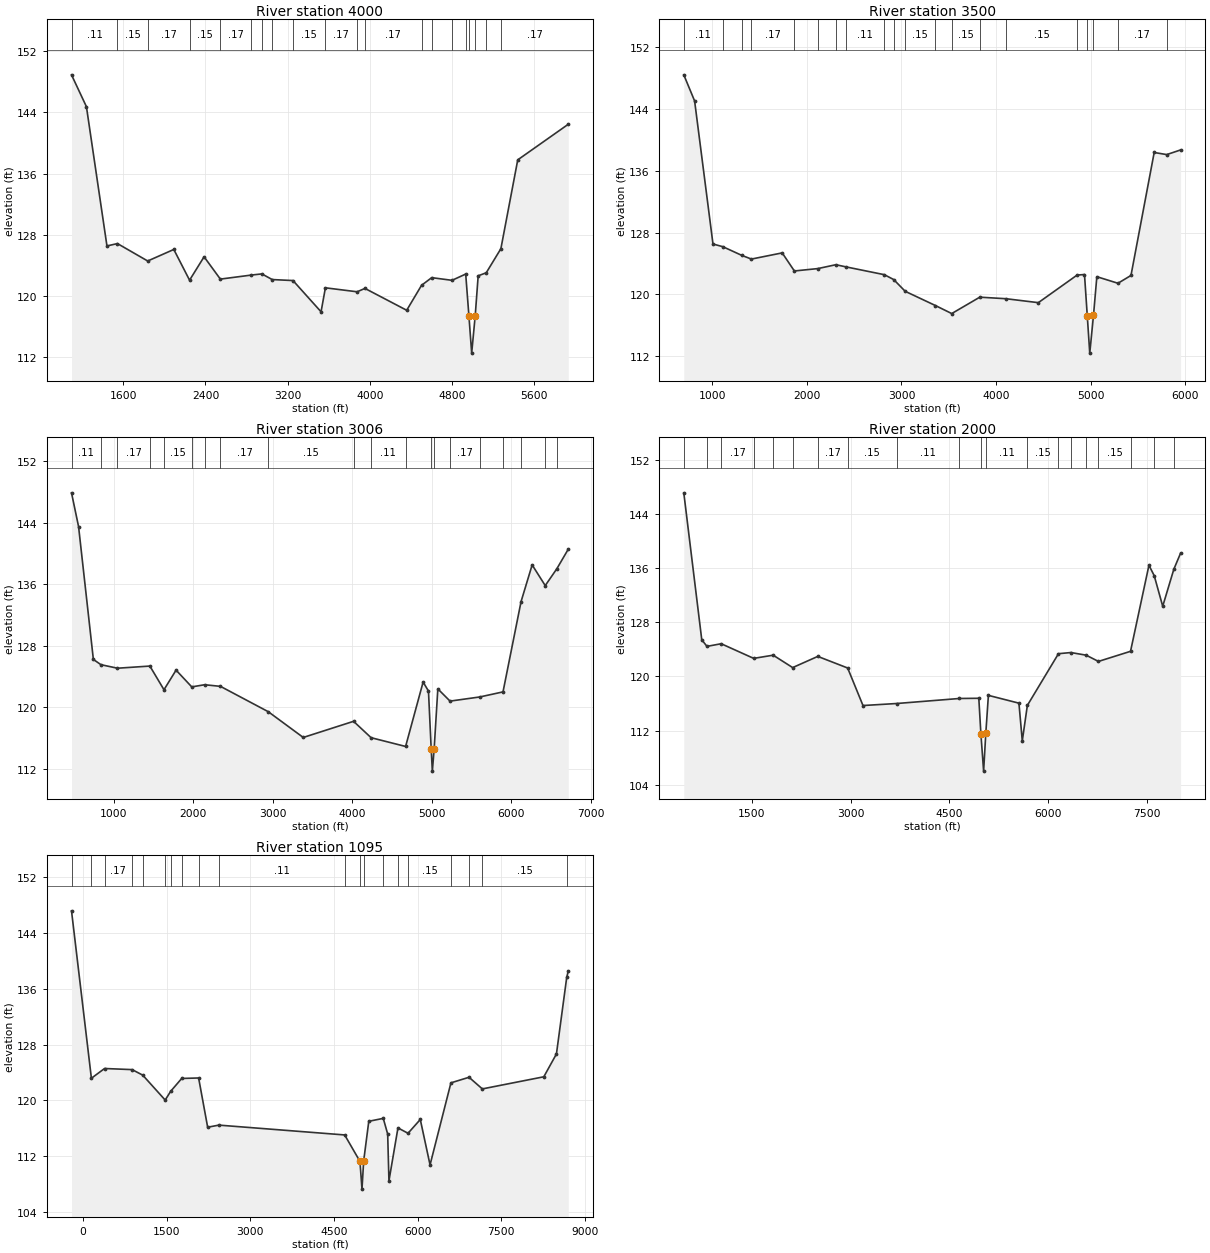
Type RM Length L Ch R = 1 ,4000    ,500,500,500
BEGIN DESCRIPTION:
Crystal Creek 039 8.0
END DESCRIPTION:
XS GIS Cut Line= 4
      3824768.49     10087372.64       3828067.5     10086753.29
      3828026.79     10086206.55      3827640.19     10085355.66
#Sta/Elev= 30
  1095.1  148.92  1240.5  144.75  1440.4  126.52  1542.8  126.83  1837.4  124.55
  2091.6  126.06  2245.2  122.04  2386.6   125.1  2545.1  122.18  2848.4  122.71
  2949.5  122.86  3050.6  122.12  3252.8  121.99  3526.2   117.9  3568.5  121.04
  3877.2  120.52  3953.9  120.96  4360.5   118.1  4505.2  121.37  4604.1  122.37
  4801.8  122.02  4935.3  122.84  4966.5117.3784  4993.5  112.49    5028   117.4
  5056.7  122.61  5135.4  123.01    5278  126.16  5442.3  137.79  5934.6  142.45
#Mann= 20 ,-1 , 0
  1095.1     .11       0  1542.8     .15       0  1837.4     .17       0
  2245.2     .15       0  2545.1     .17       0  2848.4     .11       0
  2949.5     .17       0  3050.6     .11       0  3252.8     .15       0
  3568.5     .17       0  3877.2     .15       0  3953.9     .17       0
  4505.2     .15       0  4604.1     .11       0  4801.8     .17       0
  4935.3     .11       0  4966.5     .09       0    5028     .11       0
  5135.4     .17       0    5278     .17       0
Bank Sta=4966.5,5028
XS Rating Curve= 0 ,0
Exp/Cntr=0.3,0.1

Type RM Length L Ch R = 1 ,3500    ,494,494,494
BEGIN DESCRIPTION:
Crystal Creek 039 7.0
END DESCRIPTION:
XS GIS Cut Line= 4
       3824789.3     10087393.47      3828492.85       10086821.
       3828523.1     10086266.86      3828008.04     10085466.34
#Sta/Elev= 30
   697.5  148.41   811.9  145.03  1006.2  126.52  1110.9  126.17  1312.4  125.04
  1412.8  124.57  1738.3  125.37    1867  123.03  2115.7  123.34    2306  123.84
    2417  123.55  2818.6  122.55  2917.6  121.92  3039.2   120.4  3358.6  118.56
  3531.5  117.52  3828.1  119.64  4105.4  119.44  4447.5  118.93  4857.4   122.5
  4935.7  122.57 4965.38117.1672  4991.3   112.4  5030.7  117.27  5066.3  122.29
  5289.7  121.44  5427.3  122.45  5672.8  138.36  5805.5  138.09  5951.9  138.69
#Mann= 20 ,-1 , 0
   697.5     .11       0  1110.9     .15       0  1312.4     .17       0
  1412.8     .17       0    1867     .15       0  2115.7     .17       0
    2306     .15       0    2417     .11       0  2818.6     .15       0
  2917.6     .17       0  3039.2     .15       0  3358.6     .17       0
  3531.5     .15       0  3828.1     .17       0  4105.4     .15       0
  4857.4     .15       0 4965.38     .09       0  5030.7     .15       0
  5289.7     .17       0  5805.5     .11       0
Bank Sta=4965.38,5030.7
XS Rating Curve= 0 ,0
Exp/Cntr=0.3,0.1

Type RM Length L Ch R = 1 ,3006    ,1006,1006,1006
BEGIN DESCRIPTION:
Crystal Creek 039 6.0
END DESCRIPTION:
XS GIS Cut Line= 4
      3824820.42     10087404.92       3828700.6     10086996.94
      3829015.01     10086362.22       3828058.6     10085035.63
#Sta/Elev= 30
   468.9  147.88   557.7  143.49   743.8   126.2   838.9  125.52  1046.9  125.06
    1454  125.34  1631.5  122.26  1783.5  124.81  1980.5  122.63  2142.4  122.91
  2341.6   122.7  2942.7   119.4  3382.3  116.05  4014.8  118.15  4235.2  116.02
    4669  114.88  4889.2  123.26  4956.5  122.09  4990.8  114.55  5005.2  111.67
 5027.85114.5458  5074.2  122.37  5227.8  120.78  5601.8  121.32  5893.6  121.98
  6120.8  133.74  6259.9   138.5  6424.4  135.81  6570.8  138.01  6714.2  140.55
#Mann= 20 ,-1 , 0
   468.9     .11       0   838.9     .15       0  1046.9     .17       0
    1454     .17       0  1631.5     .15       0  1980.5     .15       0
  2142.4     .11       0  2341.6     .17       0  2942.7     .15       0
  4014.8     .15       0  4235.2     .11       0    4669     .15       0
  4990.8     .09       0 5027.85     .15       0  5227.8     .17       0
  5601.8     .15       0  5893.6     .17       0  6120.8     .11       0
  6424.4     .17       0  6570.8     .11       0
Bank Sta=4990.8,5027.85
XS Rating Curve= 0 ,0
Exp/Cntr=0.3,0.1

Type RM Length L Ch R = 1 ,2000    ,905,905,905
BEGIN DESCRIPTION:
Crystal Creek 039 4.0
END DESCRIPTION:
XS GIS Cut Line= 4
      3824824.73     10087417.95      3829358.24     10087305.51
      3829677.31     10086879.86      3828302.09     10084810.63
#Sta/Elev= 30
   465.1   147.1   738.3  125.41   817.5  124.44  1033.6  124.83  1527.4  122.67
  1823.7  123.14  2120.1  121.31  2501.9  122.96  2955.8  121.25  3189.1  115.71
  3703.4  116.01  4654.4  116.75  4949.6  116.78    4981  111.55  5022.6  106.03
 5056.56111.7192  5095.2  117.21  5559.3  116.06  5610.4   110.5  5687.5  115.73
  6160.4  123.36  6349.1  123.53  6581.5  123.14    6768  122.22  7255.7  123.71
  7535.7  136.41    7616  134.87    7745  130.36  7914.2  135.83  8016.5  138.19
#Mann= 20 ,-1 , 0
   465.1     .11       0   817.5     .15       0  1033.6     .17       0
  1527.4     .17       0  1823.7     .15       0  2120.1     .11       0
  2501.9     .17       0  2955.8     .15       0  3703.4     .11       0
  4654.4     .11       0    4981     .09       0 5056.56     .11       0
  5687.5     .15       0  6160.4     .11       0  6349.1     .17       0
  6581.5     .17       0    6768     .15       0  7255.7     .15       0
    7616     .17       0  7914.2     .11       0
Bank Sta=4981,5056.56
XS Rating Curve= 0 ,0
Exp/Cntr=0.3,0.1

Type RM Length L Ch R = 1 ,1095    ,0,0,0
BEGIN DESCRIPTION:
Crystal Creek 039 2.0
END DESCRIPTION:
XS GIS Cut Line= 4
       3824798.7     10087465.69      3829851.63     10087930.98
        3830198.     10087591.56      3828761.36     10084575.05
#Sta/Elev= 30
  -202.1   147.2   154.2  123.16   390.3  124.56   883.9   124.4  1073.6  123.61
  1476.2  120.03  1574.9  121.29  1772.3  123.13  2075.3   123.2  2237.3  116.13
  2438.9  116.43  4692.1  115.02 4965.81111.2222  5002.1  107.24  5032.2  111.27
    5124  116.98  5383.5   117.4  5462.5  115.15  5485.2  108.43  5646.6  116.03
  5827.2  115.26  6046.8  117.24  6221.6  110.72  6595.7   122.5    6920   123.3
  7158.5  121.63  8259.7  123.37  8486.1  126.65    8670  137.63  8698.3  138.57
#Mann= 20 ,-1 , 0
  -202.1     .11       0   154.2     .15       0   390.3     .17       0
   883.9     .15       0  1073.6     .15       0  1476.2     .17       0
  1574.9     .11       0  1772.3     .17       0  2075.3     .15       0
  2438.9     .11       0  4692.1     .15       0 4965.81     .09       0
  5032.2     .15       0  5383.5     .17       0  5646.6     .11       0
  5827.2     .15       0  6595.7     .17       0    6920     .11       0
  7158.5     .15       0    8670     .17       0
Bank Sta=4965.81,5032.2
XS Rating Curve= 0 ,0
Exp/Cntr=0.3,0.1

Chan Stop Cuts=-1
Use User Specified Reach Order=0
Composite Channel Slope=5

--- Crystal Creek 039.g10 (geometry) ---

Geom Title=Existing Conditions
Program Version=4.10

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
River Reach=Crystal Creek 03,Reach-1

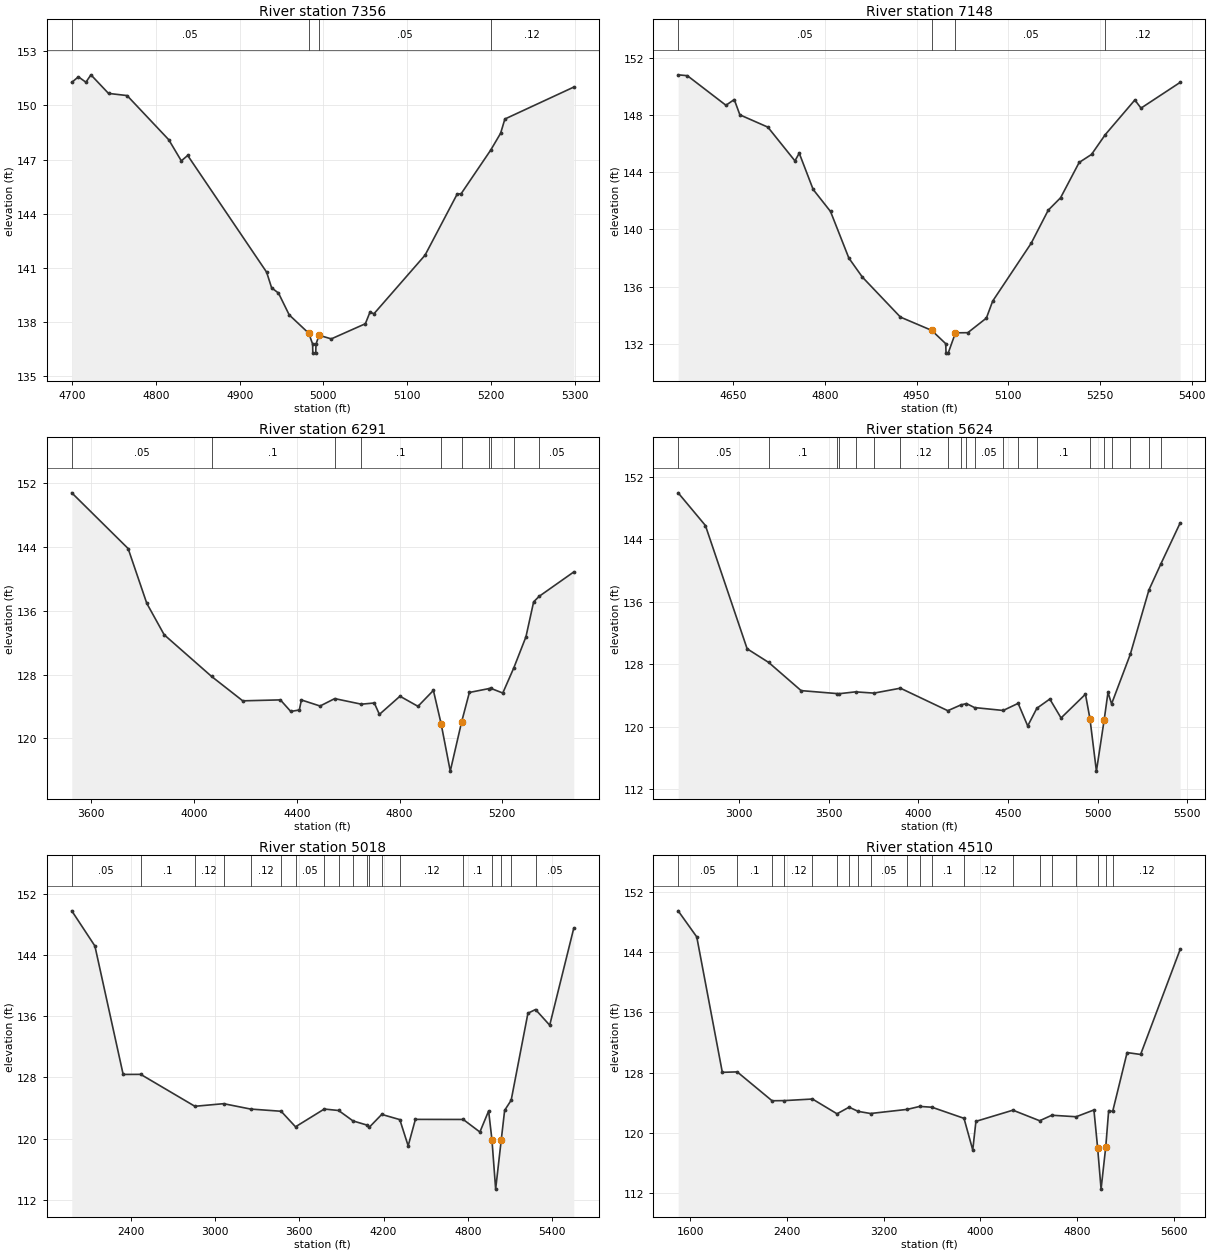
Type RM Length L Ch R = 1 ,7356    ,208,208,208
BEGIN DESCRIPTION:
Crystal Creek 039 14.0
END DESCRIPTION:
XS GIS Cut Line= 3
        3824673.     10087208.28      3824922.39     10087040.28
      3824978.55      10086746.5
#Sta/Elev= 30
  4699.3  151.28  4707.2  151.59  4716.2  151.29  4722.2   151.7  4743.2  150.67
  4765.4  150.55  4815.2   148.1  4830.2  146.93  4837.8  147.23  4932.1  140.76
  4938.1  139.89  4946.3   139.6  4959.1  138.39  4982.5  137.37  4987.1  136.77
  4987.3  136.27  4990.8  136.27  4991.1  136.77  4994.8  137.26  5009.4  137.06
  5050.1   137.9  5055.5  138.53  5060.5  138.46  5121.4   141.7  5159.6  145.07
  5164.7  145.12  5199.9  147.53  5211.7  148.46  5216.8  149.25  5299.1  151.02
#Mann= 4 ,-1 , 0
  4699.3     .05       0  4982.5     .03       0  4994.8     .05       0
  5199.9     .12       0
Bank Sta=4982.5,4994.8
XS Rating Curve= 0 ,0
Exp/Cntr=0.3,0.1

Type RM Length L Ch R = 1 ,7148    ,857,857,857
BEGIN DESCRIPTION:
Crystal Creek 039 13.0
END DESCRIPTION:
XS GIS Cut Line= 3
      3824714.63     10087300.31      3825113.57     10087114.48
      3825054.94     10086737.81
#Sta/Elev= 30
  4559.9  150.82    4575  150.76  4638.1  148.69  4651.7  149.09  4660.9  148.02
  4706.7  147.16    4751   144.8    4758  145.34  4780.8   142.8  4809.2  141.26
  4839.2     138  4861.3  136.67  4923.6  133.87  4974.8  132.94  4997.7  132.01
  4998.2  131.35  5001.7  131.35  5013.6  132.77  5033.8  132.78  5064.2   133.8
  5074.5  134.99  5137.4  139.03  5165.4  141.35  5185.6  142.22    5216  144.69
  5236.2  145.25  5258.8  146.64  5307.1  149.06  5317.2  148.49  5381.2  150.29
#Mann= 4 ,-1 , 0
  4559.9     .05       0  4974.8     .03       0  5013.6     .05       0
  5258.8     .12       0
Bank Sta=4974.8,5013.6
XS Rating Curve= 0 ,0
Exp/Cntr=0.3,0.1

Type RM Length L Ch R = 1 ,6291    ,667,667,667
BEGIN DESCRIPTION:
Crystal Creek 039 12.0
END DESCRIPTION:
XS GIS Cut Line= 4
      3824716.44     10087312.44      3825803.69     10087010.38
      3825815.81     10086661.35      3825834.42     10086184.98
#Sta/Elev= 30
  3523.7   150.8  3743.1  143.81  3815.8  136.93  3883.5  132.99  4068.1  127.76
  4189.4   124.7  4335.9  124.82  4376.2  123.37  4409.6  123.55  4417.7  124.81
  4490.4  124.05  4547.5  124.98    4651  124.28  4701.5  124.43  4721.5     123
  4801.5  125.28  4871.6  124.01  4931.6  126.01  4961.6  121.84  4997.3  115.88
  5041.7  122.08  5071.7  125.75  5146.8  126.23  5156.5  126.25  5201.8  125.68
  5245.1  128.87  5291.9  132.73  5321.9  137.12  5343.3  137.81  5478.1  140.87
#Mann= 10 ,-1 , 0
  3523.7     .05       0  4068.1      .1       0  4547.5     .12       0
    4651      .1       0  4961.6     .07       0  5041.7      .1       0
  5146.8     .12       0  5156.5      .1       0  5245.1     .12       0
  5343.3     .05       0
Bank Sta=4961.6,5041.7
XS Rating Curve= 0 ,0
Exp/Cntr=0.3,0.1

Type RM Length L Ch R = 1 ,5624    ,606,606,606
BEGIN DESCRIPTION:
Crystal Creek 039 11.0
END DESCRIPTION:
XS GIS Cut Line= 3
      3824744.17     10087324.03      3826570.57     10086848.33
      3826299.72     10085976.77
#Sta/Elev= 30
  2660.9  149.93    2813  145.75  3045.7  129.98  3166.1  128.23  3346.7  124.63
  3547.2  124.25  3557.5  124.23  3650.2  124.47  3753.2  124.31  3900.6  124.94
    4165  122.06    4238   122.8  4269.2  122.97    4314  122.46  4473.9  122.09
  4557.4     123  4610.7  120.11  4661.6  122.37  4733.9  123.55  4796.7  121.13
  4932.8  124.17 4957.92 121.022  4993.9  114.33  5037.5  120.93  5058.5  124.41
  5078.5  122.93  5182.7  129.26  5286.9  137.51  5354.1  140.87  5460.9  146.07
#Mann= 20 ,-1 , 0
  2660.9     .05       0  3166.1      .1       0  3547.2     .12       0
  3557.5      .1       0  3650.2     .12       0  3753.2      .1       0
  3900.6     .12       0    4165      .1       0    4238     .05       0
  4269.2      .1       0    4314     .05       0  4473.9     .12       0
  4557.4     .05       0  4661.6      .1       0 4957.92     .07       0
  5037.5      .1       0  5078.5     .05       0  5182.7     .12       0
  5286.9     .05       0  5354.1     .12       0
Bank Sta=4957.92,5037.5
XS Rating Curve= 0 ,0
Exp/Cntr=0.3,0.1

Type RM Length L Ch R = 1 ,5018    ,508,508,508
BEGIN DESCRIPTION:
Crystal Creek 039 10.0
END DESCRIPTION:
XS GIS Cut Line= 3
      3824747.65     10087341.39      3827157.37       10086765.
      3826869.19     10085706.01
#Sta/Elev= 30
  1979.8  149.75  2144.5  145.16  2345.8  128.38  2470.7  128.39  2856.7  124.22
  3061.4  124.56  3252.9  123.86  3470.9  123.57  3573.3  121.54    3778  123.86
  3880.4  123.67  3982.7  122.31  4085.1  121.75  4097.6  121.46  4187.5  123.16
  4316.1  122.48  4375.7  119.05  4427.1  122.51  4767.8   122.5  4886.5  120.86
  4948.7  123.61  4972.2  119.87  4998.7   113.4 5038.44 119.809  5062.7  123.69
  5109.2  125.01  5228.5  136.37  5282.7  136.86  5383.7  134.81    5555  147.48
#Mann= 19 ,-1 , 0
  1979.8     .05       0  2470.7      .1       0  2856.7     .12       0
  3061.4      .1       0  3252.9     .12       0  3470.9      .1       0
  3573.3     .05       0    3778     .12       0  3880.4     .05       0
  3982.7     .12       0  4085.1      .1       0  4097.6     .12       0
  4187.5      .1       0  4316.1     .12       0  4767.8      .1       0
  4972.2     .07       0 5038.44      .1       0  5109.2     .12       0
  5282.7     .05       0
Bank Sta=4972.2,5038.44
XS Rating Curve= 0 ,0
Exp/Cntr=0.3,0.1

Type RM Length L Ch R = 1 ,4510    ,510,510,510
BEGIN DESCRIPTION:
Crystal Creek 039 9.0
END DESCRIPTION:
XS GIS Cut Line= 3
      3824740.68     10087358.75      3827619.18      10086726.8
      3827400.43     10085539.34
#Sta/Elev= 30
  1498.4  149.47  1652.5  146.01  1864.1  128.05  1987.1  128.11  2275.6  124.28
  2377.4   124.3    2610  124.51  2813.4  122.55  2913.2  123.43  2988.5  122.87
  3090.4  122.59  3395.9  123.14  3497.8  123.53  3599.6  123.42  3864.2  121.95
  3936.6  117.75  3962.9  121.55  4269.2  123.03  4490.3  121.63    4591  122.36
  4792.4  122.16  4939.4  123.06  4969.9  118.06  4998.6  112.56 5037.42 118.185
  5061.4  122.98  5094.5  122.86  5213.9  130.67  5325.8  130.42  5652.9  144.35
#Mann= 20 ,-1 , 0
  1498.4     .05       0  1987.1      .1       0  2275.6      .1       0
  2377.4     .12       0    2610      .1       0  2813.4     .12       0
  2913.2      .1       0  2988.5     .12       0  3090.4     .05       0
  3395.9     .12       0  3497.8     .12       0  3599.6      .1       0
  3864.2     .12       0  4269.2      .1       0  4490.3     .12       0
    4591     .05       0  4792.4      .1       0  4969.9     .07       0
 5037.42      .1       0  5094.5     .12       0
Bank Sta=4969.9,5037.42
XS Rating Curve= 0 ,0
Exp/Cntr=0.3,0.1

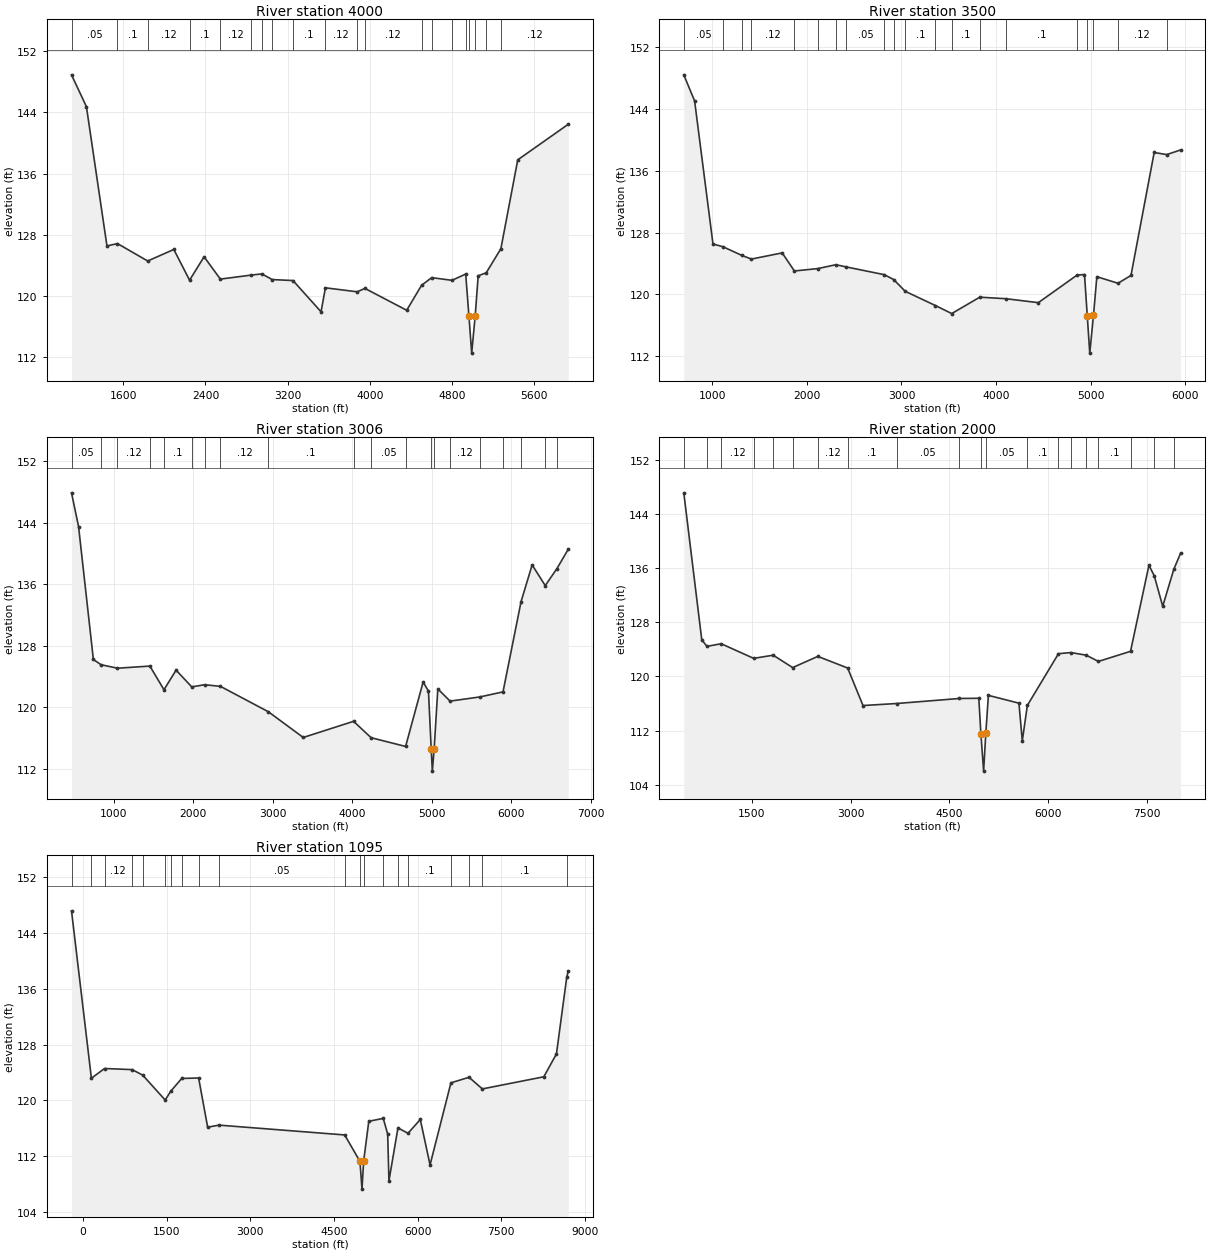
Type RM Length L Ch R = 1 ,4000    ,500,500,500
BEGIN DESCRIPTION:
Crystal Creek 039 8.0
END DESCRIPTION:
XS GIS Cut Line= 4
      3824768.49     10087372.64       3828067.5     10086753.29
      3828026.79     10086206.55      3827640.19     10085355.66
#Sta/Elev= 30
  1095.1  148.92  1240.5  144.75  1440.4  126.52  1542.8  126.83  1837.4  124.55
  2091.6  126.06  2245.2  122.04  2386.6   125.1  2545.1  122.18  2848.4  122.71
  2949.5  122.86  3050.6  122.12  3252.8  121.99  3526.2   117.9  3568.5  121.04
  3877.2  120.52  3953.9  120.96  4360.5   118.1  4505.2  121.37  4604.1  122.37
  4801.8  122.02  4935.3  122.84  4966.5 117.378  4993.5  112.49    5028   117.4
  5056.7  122.61  5135.4  123.01    5278  126.16  5442.3  137.79  5934.6  142.45
#Mann= 20 ,-1 , 0
  1095.1     .05       0  1542.8      .1       0  1837.4     .12       0
  2245.2      .1       0  2545.1     .12       0  2848.4     .05       0
  2949.5     .12       0  3050.6     .05       0  3252.8      .1       0
  3568.5     .12       0  3877.2      .1       0  3953.9     .12       0
  4505.2      .1       0  4604.1     .05       0  4801.8     .12       0
  4935.3     .05       0  4966.5     .07       0    5028     .05       0
  5135.4     .12       0    5278     .12       0
Bank Sta=4966.5,5028
XS Rating Curve= 0 ,0
Exp/Cntr=0.3,0.1

Type RM Length L Ch R = 1 ,3500    ,494,494,494
BEGIN DESCRIPTION:
Crystal Creek 039 7.0
END DESCRIPTION:
XS GIS Cut Line= 4
       3824789.3     10087393.47      3828492.85       10086821.
       3828523.1     10086266.86      3828008.04     10085466.34
#Sta/Elev= 30
   697.5  148.41   811.9  145.03  1006.2  126.52  1110.9  126.17  1312.4  125.04
  1412.8  124.57  1738.3  125.37    1867  123.03  2115.7  123.34    2306  123.84
    2417  123.55  2818.6  122.55  2917.6  121.92  3039.2   120.4  3358.6  118.56
  3531.5  117.52  3828.1  119.64  4105.4  119.44  4447.5  118.93  4857.4   122.5
  4935.7  122.57 4965.38 117.167  4991.3   112.4  5030.7  117.27  5066.3  122.29
  5289.7  121.44  5427.3  122.45  5672.8  138.36  5805.5  138.09  5951.9  138.69
#Mann= 20 ,-1 , 0
   697.5     .05       0  1110.9      .1       0  1312.4     .12       0
  1412.8     .12       0    1867      .1       0  2115.7     .12       0
    2306      .1       0    2417     .05       0  2818.6      .1       0
  2917.6     .12       0  3039.2      .1       0  3358.6     .12       0
  3531.5      .1       0  3828.1     .12       0  4105.4      .1       0
  4857.4      .1       0 4965.38     .07       0  5030.7      .1       0
  5289.7     .12       0  5805.5     .05       0
Bank Sta=4965.38,5030.7
XS Rating Curve= 0 ,0
Exp/Cntr=0.3,0.1

Type RM Length L Ch R = 1 ,3006    ,1006,1006,1006
BEGIN DESCRIPTION:
Crystal Creek 039 6.0
END DESCRIPTION:
XS GIS Cut Line= 4
      3824820.42     10087404.92       3828700.6     10086996.94
      3829015.01     10086362.22       3828058.6     10085035.63
#Sta/Elev= 30
   468.9  147.88   557.7  143.49   743.8   126.2   838.9  125.52  1046.9  125.06
    1454  125.34  1631.5  122.26  1783.5  124.81  1980.5  122.63  2142.4  122.91
  2341.6   122.7  2942.7   119.4  3382.3  116.05  4014.8  118.15  4235.2  116.02
    4669  114.88  4889.2  123.26  4956.5  122.09  4990.8  114.55  5005.2  111.67
 5027.85 114.546  5074.2  122.37  5227.8  120.78  5601.8  121.32  5893.6  121.98
  6120.8  133.74  6259.9   138.5  6424.4  135.81  6570.8  138.01  6714.2  140.55
#Mann= 20 ,-1 , 0
   468.9     .05       0   838.9      .1       0  1046.9     .12       0
    1454     .12       0  1631.5      .1       0  1980.5      .1       0
  2142.4     .05       0  2341.6     .12       0  2942.7      .1       0
  4014.8      .1       0  4235.2     .05       0    4669      .1       0
  4990.8     .07       0 5027.85      .1       0  5227.8     .12       0
  5601.8      .1       0  5893.6     .12       0  6120.8     .05       0
  6424.4     .12       0  6570.8     .05       0
Bank Sta=4990.8,5027.85
XS Rating Curve= 0 ,0
Exp/Cntr=0.3,0.1

Type RM Length L Ch R = 1 ,2000    ,905,905,905
BEGIN DESCRIPTION:
Crystal Creek 039 4.0
END DESCRIPTION:
XS GIS Cut Line= 4
      3824824.73     10087417.95      3829358.24     10087305.51
      3829677.31     10086879.86      3828302.09     10084810.63
#Sta/Elev= 30
   465.1   147.1   738.3  125.41   817.5  124.44  1033.6  124.83  1527.4  122.67
  1823.7  123.14  2120.1  121.31  2501.9  122.96  2955.8  121.25  3189.1  115.71
  3703.4  116.01  4654.4  116.75  4949.6  116.78    4981  111.55  5022.6  106.03
 5056.56 111.719  5095.2  117.21  5559.3  116.06  5610.4   110.5  5687.5  115.73
  6160.4  123.36  6349.1  123.53  6581.5  123.14    6768  122.22  7255.7  123.71
  7535.7  136.41    7616  134.87    7745  130.36  7914.2  135.83  8016.5  138.19
#Mann= 20 ,-1 , 0
   465.1     .05       0   817.5      .1       0  1033.6     .12       0
  1527.4     .12       0  1823.7      .1       0  2120.1     .05       0
  2501.9     .12       0  2955.8      .1       0  3703.4     .05       0
  4654.4     .05       0    4981     .07       0 5056.56     .05       0
  5687.5      .1       0  6160.4     .05       0  6349.1     .12       0
  6581.5     .12       0    6768      .1       0  7255.7      .1       0
    7616     .12       0  7914.2     .05       0
Bank Sta=4981,5056.56
XS Rating Curve= 0 ,0
Exp/Cntr=0.3,0.1

Type RM Length L Ch R = 1 ,1095    ,0,0,0
BEGIN DESCRIPTION:
Crystal Creek 039 2.0
END DESCRIPTION:
XS GIS Cut Line= 4
       3824798.7     10087465.69      3829851.63     10087930.98
        3830198.     10087591.56      3828761.36     10084575.05
#Sta/Elev= 30
  -202.1   147.2   154.2  123.16   390.3  124.56   883.9   124.4  1073.6  123.61
  1476.2  120.03  1574.9  121.29  1772.3  123.13  2075.3   123.2  2237.3  116.13
  2438.9  116.43  4692.1  115.02 4965.81 111.222  5002.1  107.24  5032.2  111.27
    5124  116.98  5383.5   117.4  5462.5  115.15  5485.2  108.43  5646.6  116.03
  5827.2  115.26  6046.8  117.24  6221.6  110.72  6595.7   122.5    6920   123.3
  7158.5  121.63  8259.7  123.37  8486.1  126.65    8670  137.63  8698.3  138.57
#Mann= 20 ,-1 , 0
  -202.1     .05       0   154.2      .1       0   390.3     .12       0
   883.9      .1       0  1073.6      .1       0  1476.2     .12       0
  1574.9     .05       0  1772.3     .12       0  2075.3      .1       0
  2438.9     .05       0  4692.1      .1       0 4965.81     .07       0
  5032.2      .1       0  5383.5     .12       0  5646.6     .05       0
  5827.2      .1       0  6595.7     .12       0    6920     .05       0
  7158.5      .1       0    8670     .12       0
Bank Sta=4965.81,5032.2
XS Rating Curve= 0 ,0
Exp/Cntr=0.3,0.1