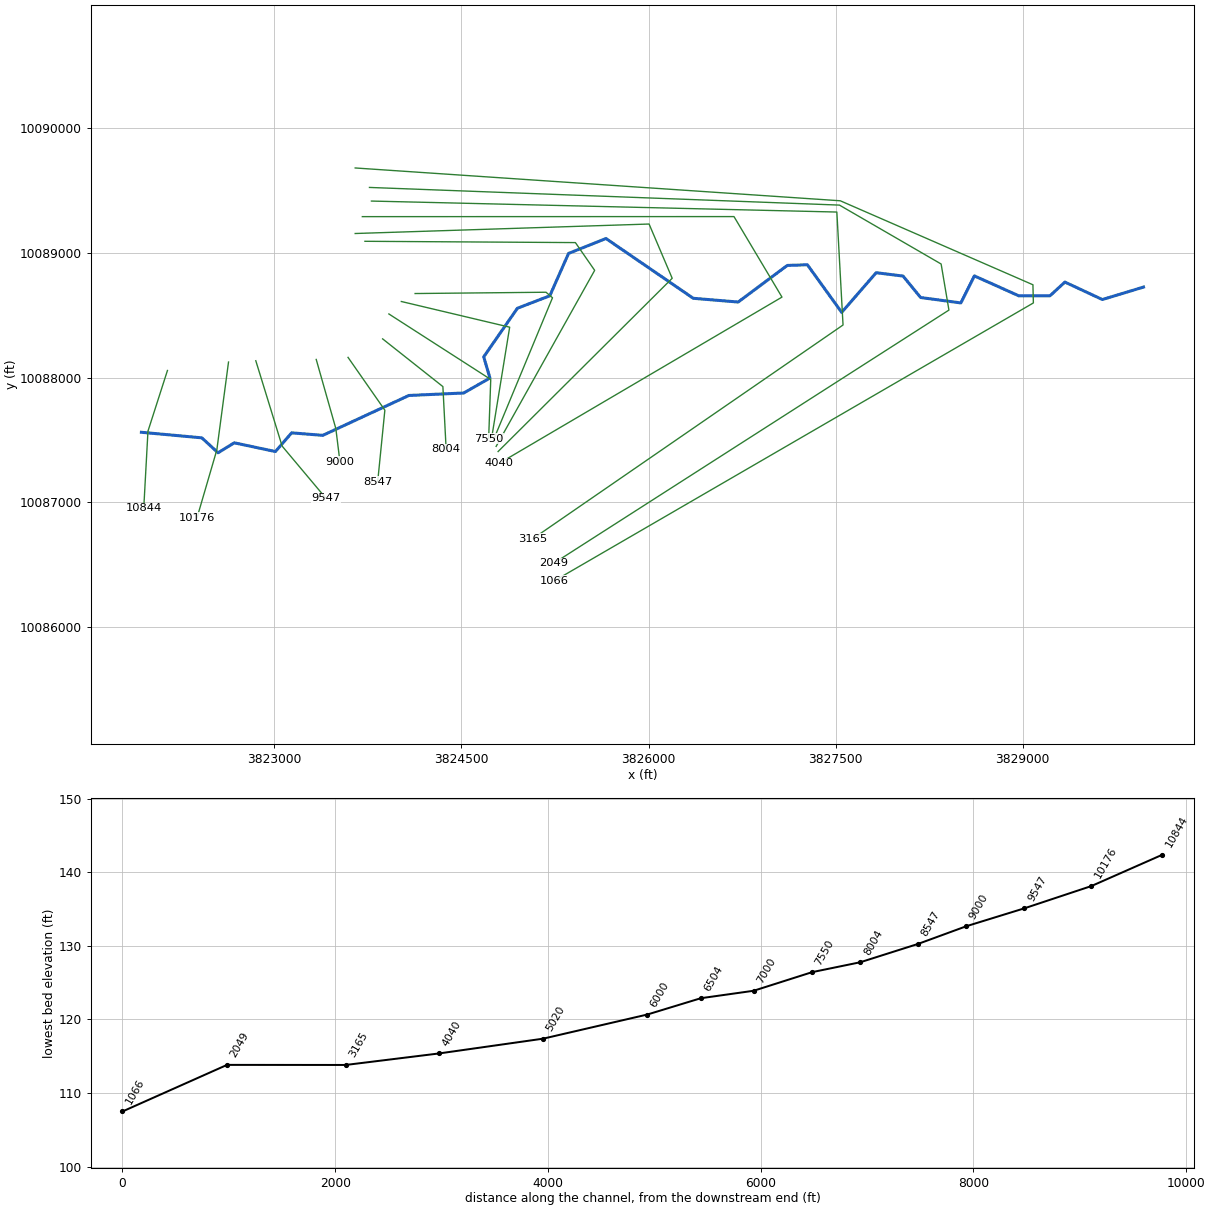
--- Crystal Creek 040.prj (project) ---

Proj Title=Crystal Creek 040 Base Level Engineering
Current Plan=p01
Default Exp/Contr=0.3,0.1
English Units
Geom File=g01
Flow File=f01
Flow File=f02
Plan File=p01
Y Axis Title=Elevation
X Axis Title(PF)=Main Channel Distance
X Axis Title(XS)=Station
BEGIN DESCRIPTION:
Crystal Creek 040
END DESCRIPTION:
DSS Export Rating Curves= 0
DSS Export Rating Curve Sorted= 0
DSS Export Volume Flow Curves= 0
DXF OffsetX= 0
DXF OffsetY= 0
DXF ScaleX= 1
DXF ScaleY= 10

--- Crystal Creek 040.p01 (plan) ---

Plan Title=Multiple Run
Short Identifier=Multiple
Geom File=g01
Flow File=f01
Subcritical Flow
K Sum by GR= 0
Std Step Tol= 0.01
Critical Tol= 0.01
Num of Std Step Trials= 20
Max Error Tol= 0.3
Flow Tol Ratio= 0.001
Split Flow NTrial= 30
Split Flow Tol= 0.02
Split Flow Ratio= 0.02
Log Output Level= 0
Friction Slope Method= 1
Unsteady Friction Slope Method= 2
Unsteady Bridges Friction Slope Method= 1
Parabolic Critical Depth
Global Vel Dist=  1 , 1 , 1
Global Log Level= 0
CheckData=True
Encroach Param= -1, 0, 0, 0
BEGIN DESCRIPTION:
Multiple Run
END DESCRIPTION:

--- Crystal Creek 040.f01 (steady flow) ---

Flow Title=Multiple
Program Version=4.10
Number of Profiles= 7
Profile Names=10-year,25-year,50-year,1pct_min,100-year,1pct_plu,500-year
River Rch & RM=Crystal Creek 04,Reach-1         ,10844
     701     946    1274     565    1706    5152    3160
River Rch & RM=Crystal Creek 04,Reach-1         ,2049
     676     907    1218     538    1624    4904    2981
Boundary for River Rch & Prof#=Crystal Creek 04,Reach-1         , 1
Up Type= 0
Dn Type= 3
Dn Slope=0.008
Boundary for River Rch & Prof#=Crystal Creek 04,Reach-1         , 2
Up Type= 0
Dn Type= 3
Dn Slope=0.008
Boundary for River Rch & Prof#=Crystal Creek 04,Reach-1         , 3
Up Type= 0
Dn Type= 3
Dn Slope=0.008
Boundary for River Rch & Prof#=Crystal Creek 04,Reach-1         , 4
Up Type= 0
Dn Type= 3
Dn Slope=0.008
Boundary for River Rch & Prof#=Crystal Creek 04,Reach-1         , 5
Up Type= 0
Dn Type= 3
Dn Slope=0.008
Boundary for River Rch & Prof#=Crystal Creek 04,Reach-1         , 6
Up Type= 0
Dn Type= 3
Dn Slope=0.008
Boundary for River Rch & Prof#=Crystal Creek 04,Reach-1         , 7
Up Type= 0
Dn Type= 3
Dn Slope=0.008
DSS Import GetInterval= 0
DSS Import GetPeak= 0
DSS Import FillOption= 0

--- Crystal Creek 040.f02 (steady flow) ---

Flow Title=Orig_BLE_Flow
Program Version=4.10
Number of Profiles= 7
Profile Names=10-year,25-year,50-year,1pct_min,100-year,1pct_plu,500-year
River Rch & RM=Crystal Creek 04,Reach-1         ,10844
     701     927    1108     435    1312    3964    1837
River Rch & RM=Crystal Creek 04,Reach-1         ,2049
     676     889    1059     414    1249    3771    1733
Boundary for River Rch & Prof#=Crystal Creek 04,Reach-1         , 1
Up Type= 0
Dn Type= 3
Dn Slope=0.008
Boundary for River Rch & Prof#=Crystal Creek 04,Reach-1         , 2
Up Type= 0
Dn Type= 3
Dn Slope=0.008
Boundary for River Rch & Prof#=Crystal Creek 04,Reach-1         , 3
Up Type= 0
Dn Type= 3
Dn Slope=0.008
Boundary for River Rch & Prof#=Crystal Creek 04,Reach-1         , 4
Up Type= 0
Dn Type= 3
Dn Slope=0.008
Boundary for River Rch & Prof#=Crystal Creek 04,Reach-1         , 5
Up Type= 0
Dn Type= 3
Dn Slope=0.008
Boundary for River Rch & Prof#=Crystal Creek 04,Reach-1         , 6
Up Type= 0
Dn Type= 3
Dn Slope=0.008
Boundary for River Rch & Prof#=Crystal Creek 04,Reach-1         , 7
Up Type= 0
Dn Type= 3
Dn Slope=0.008
DSS Import GetInterval= 0
DSS Import GetPeak= 0
DSS Import FillOption= 0

--- Crystal Creek 040.g01 (geometry) ---

Geom Title=Existing Conditions
Program Version=4.10

River Reach=Crystal Creek 04,Reach-1
Reach XY= 30
      3821933.68     10087561.41      3822418.24     10087516.86
      3822548.24     10087396.86      3822678.24     10087476.86
      3823008.24     10087406.86      3823138.24     10087556.86
      3823388.24     10087536.86      3824078.24     10087856.86
      3824518.24     10087876.86      3824728.24     10087996.86
      3824678.24     10088166.86      3824948.24     10088556.86
      3825208.24     10088656.86      3825358.24     10088996.86
      3825658.24     10089116.86      3826358.24     10088636.86
      3826718.24     10088606.86        3827112.     10088900.52
      3827273.27     10088905.94      3827548.37     10088523.78
      3827824.83     10088842.25       3828040.3     10088815.15
      3828181.24     10088643.04      3828503.77     10088599.67
      3828612.18      10088816.5      3828968.24     10088656.86
      3829218.24     10088656.86      3829338.24     10088766.86
      3829638.24     10088626.86      3829968.24     10088726.86

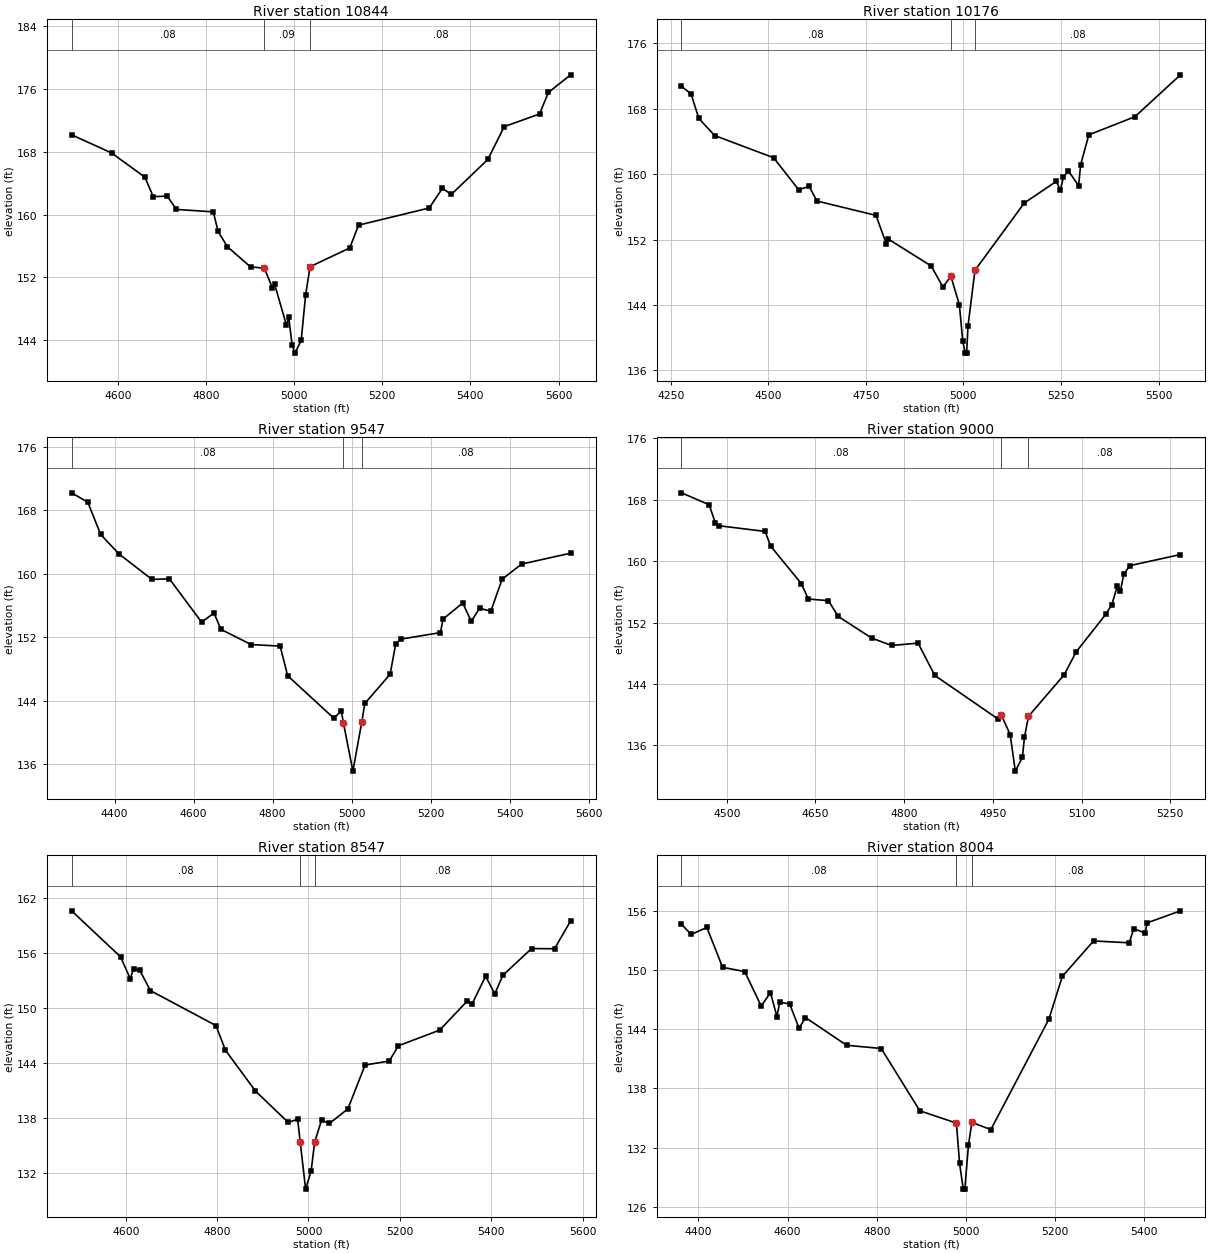
Type RM Length L Ch R = 1 ,10844   ,668,668,668
BEGIN DESCRIPTION:
Crystal Creek 040 21.0
END DESCRIPTION:
XS GIS Cut Line= 3
      3822142.59     10088057.53      3821986.34     10087570.53
      3821952.48     10086950.71
#Sta/Elev= 30
  4495.2  170.15    4586  167.84  4661.4  164.76  4680.5  162.28    4712  162.36
    4733  160.66  4816.7  160.35  4827.5  157.86  4848.6  155.92  4901.1  153.35
  4932.6  153.18  4950.5  150.72  4955.7  151.17  4982.6  145.94  4987.8  146.96
  4995.6  143.37    5002  142.38  5016.1  143.99  5026.1  149.76  5036.2  153.37
  5126.3  155.76  5146.3  158.66  5306.6  160.84  5336.6  163.35  5356.6  162.56
  5439.5  167.01  5476.8  171.19  5556.9   172.8    5577  175.54  5627.4  177.78
#Mann= 3 , 0 , 0
  4495.2     .08       0  4932.6     .09       0  5036.2     .08       0
#XS Ineff= 2 , 0
       0  4955.7  151.17               0
Permanent Ineff=
       F       F
Bank Sta=4932.6,5036.2
XS Rating Curve= 0 ,0
Exp/Cntr=0.3,0.1

Type RM Length L Ch R = 1 ,10176   ,629,629,629
BEGIN DESCRIPTION:
Crystal Creek 040 20.0
END DESCRIPTION:
XS GIS Cut Line= 3
      3822632.18     10088125.26      3822538.42     10087419.49
      3822379.69     10086875.65
#Sta/Elev= 30
  4277.7  170.75  4302.1  169.82  4322.3  166.81  4362.6  164.73  4513.9  162.01
  4577.9   158.1  4604.7   158.5  4624.9  156.72  4776.2  154.96  4802.8  151.44
  4807.8  152.06  4917.5  148.78  4947.7   146.2  4967.9  147.53  4989.7  144.04
  4998.4  139.57  5004.8  138.12  5008.3  138.12  5011.8  141.42  5029.7  148.25
  5156.1  156.48    5238  159.12  5248.5  158.05  5256.5  159.69  5269.3  160.39
  5295.2   158.6  5300.5  161.17  5321.4  164.81  5439.5  167.03  5556.2  172.15
#Mann= 3 , 0 , 0
  4277.7     .08       0  4967.9     .09       0  5029.7     .08       0
#XS Ineff= 2 , 0
       0  4967.9  147.53               0
Permanent Ineff=
       F       F
Bank Sta=4967.9,5029.7
XS Rating Curve= 0 ,0
Exp/Cntr=0.3,0.1

Type RM Length L Ch R = 1 ,9547    ,547,547,547
BEGIN DESCRIPTION:
Crystal Creek 040 19.0
END DESCRIPTION:
XS GIS Cut Line= 3
      3822850.93     10088135.59      3823061.86     10087450.74
      3823413.13     10087031.82
#Sta/Elev= 30
  4291.2  170.22  4332.1  169.04  4364.8  164.97    4411  162.51  4494.7  159.29
  4538.7  159.37  4620.3   153.9  4651.7  155.05  4669.4  152.98  4745.9  151.07
  4819.1  150.88  4838.1  147.14  4955.1  141.77    4974  142.71  4979.2  141.22
  5003.3   135.1  5025.9  141.33  5033.5  143.64  5097.5  147.32  5111.8  151.17
  5124.8  151.76    5225  152.58  5231.5  154.29  5281.4  156.32    5303  153.99
  5323.9  155.66  5352.5  155.28  5381.1  159.32  5430.5  161.23  5554.5   162.6
#Mann= 3 , 0 , 0
  4291.2     .08       0  4979.2     .09       0  5025.9     .08       0
Bank Sta=4979.2,5025.9
XS Rating Curve= 0 ,0
Exp/Cntr=0.3,0.1

Type RM Length L Ch R = 1 ,9000    ,453,453,453
BEGIN DESCRIPTION:
Crystal Creek 040 18.0
END DESCRIPTION:
XS GIS Cut Line= 3
      3823335.29     10088146.08      3823492.63     10087591.26
      3823525.38     10087325.87
#Sta/Elev= 30
  4423.3  168.92  4470.1  167.37  4480.5  165.02  4486.7  164.63  4564.9  163.89
    4574  161.99    4626   157.1  4637.9  155.08  4671.9  154.87  4688.4  152.82
  4744.9     150  4778.8  149.03  4823.5  149.34  4851.8  145.13  4958.6  139.46
    4964  140.02  4979.4  137.41    4988  132.66    5000  134.46  5003.5  137.06
  5010.3   139.8  5070.7  145.22  5090.9  148.19  5141.2  153.11  5151.3  154.34
  5160.7  156.81  5165.8  156.13  5171.5   158.3  5181.6  159.43  5267.4  160.88
#Mann= 3 , 0 , 0
  4423.3     .08       0    4964     .09       0  5010.3     .08       0
Bank Sta=4964,5010.3
XS Rating Curve= 0 ,0
Exp/Cntr=0.3,0.1

Type RM Length L Ch R = 1 ,8547    ,543,543,543
BEGIN DESCRIPTION:
Crystal Creek 040 17.0
END DESCRIPTION:
XS GIS Cut Line= 3
      3823590.48     10088162.57      3823885.64     10087738.93
      3823828.35     10087166.01
#Sta/Elev= 30
  4481.6  160.64  4588.9  155.61  4609.8  153.24  4617.5  154.33  4630.7  154.15
  4654.1  151.93  4797.4  148.12  4818.3  145.42  4883.8  140.98  4955.4  137.55
  4976.3  137.88 4981.92135.3928  4993.7  130.26  5005.8  132.24 5013.46135.3723
  5028.5  137.78    5046  137.43  5086.2  139.02  5123.9  143.81  5176.7  144.24
  5196.8  145.91  5287.2  147.62  5347.5  150.79  5357.6  150.43  5387.7   153.5
  5407.8  151.58  5425.4   153.6  5488.2  156.52  5538.5   156.5  5573.7  159.53
#Mann= 3 , 0 , 0
  4481.6     .08       0 4981.92     .09       0 5013.46     .08       0
Bank Sta=4981.92,5013.46
XS Rating Curve= 0 ,0
Exp/Cntr=0.3,0.1

Type RM Length L Ch R = 1 ,8004    ,454,454,454
BEGIN DESCRIPTION:
Crystal Creek 040 16.0
END DESCRIPTION:
XS GIS Cut Line= 3
      3823867.81      10088311.1      3824350.92     10087928.17
      3824376.96     10087426.41
#Sta/Elev= 30
  4362.2  154.69  4383.9  153.65  4419.1  154.36  4454.4  150.31    4504  149.88
  4540.9  146.38  4561.8  147.73  4576.2  145.31  4582.6  146.75  4604.7   146.6
  4625.9  144.11  4640.3  145.21  4732.3  142.39  4810.1  142.06  4896.7  135.73
  4978.7  134.48  4985.8  130.38    4994  127.77  4997.5  127.77  5005.8  132.27
  5013.4  134.55  5055.9  133.82    5186  145.03  5216.1  149.38  5286.2  152.99
  5366.3   152.8  5376.3  154.24  5401.6   153.8  5406.6  154.83  5481.1  156.05
#Mann= 3 , 0 , 0
  4362.2     .08       0  4978.7     .09       0  5013.4     .08       0
Bank Sta=4978.7,5013.4
XS Rating Curve= 0 ,0
Exp/Cntr=0.3,0.1

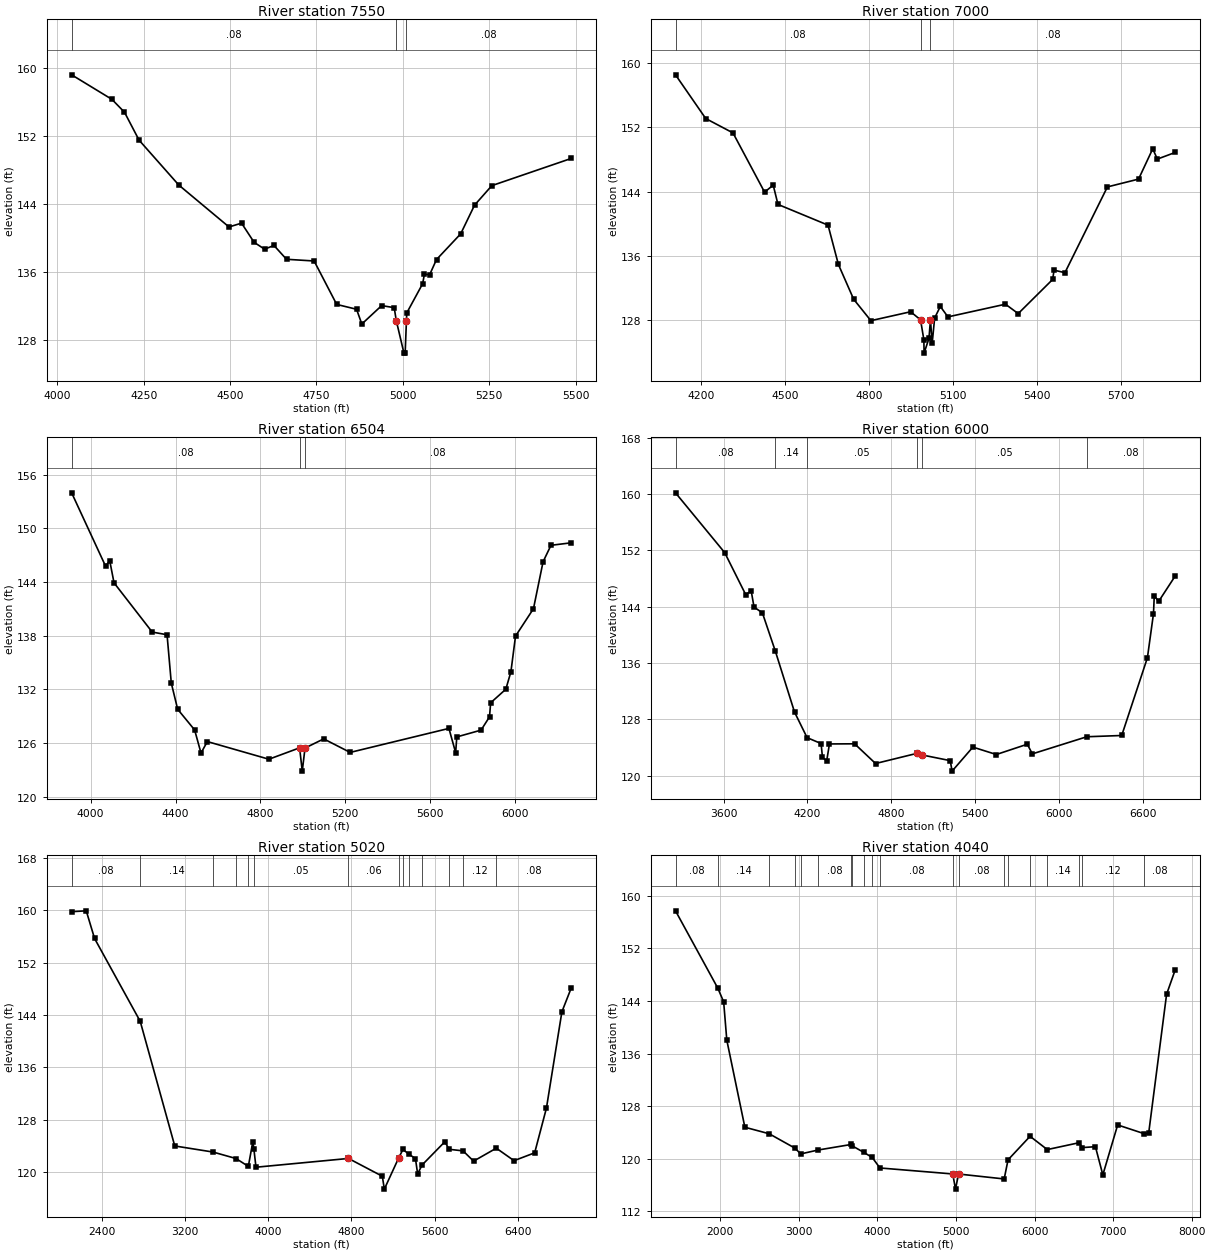
Type RM Length L Ch R = 1 ,7550    ,550,550,550
BEGIN DESCRIPTION:
Crystal Creek 040 15.0
END DESCRIPTION:
XS GIS Cut Line= 3
      3823917.86     10088511.07       3824734.6     10087985.46
      3824717.85     10087511.11
#Sta/Elev= 30
  4041.6  159.22  4158.1  156.33  4194.5  154.81  4236.7  151.52  4351.6  146.23
  4496.9  141.29  4533.2  141.74  4569.5  139.48  4599.9  138.67    4627  139.11
  4663.3  137.48  4743.2  137.28  4808.5  132.16    4866  131.59  4881.2  129.85
  4938.6  132.02  4974.9  131.78    4981  130.24  5003.1  126.42  5006.6  126.42
 5010.34130.2555  5011.3  131.16  5057.3  134.61  5062.3  135.73  5077.3  135.65
  5097.3  137.45  5167.3  140.48  5207.4  143.86  5257.4  146.16  5487.5  149.37
#Mann= 3 , 0 , 0
  4041.6     .08       0    4981     .09       0 5010.34     .08       0
Bank Sta=4981,5010.34
XS Rating Curve= 0 ,0
Exp/Cntr=0.3,0.1

Type RM Length L Ch R = 1 ,7000    ,496,496,496
BEGIN DESCRIPTION:
Crystal Creek 040 14.0
END DESCRIPTION:
XS GIS Cut Line= 3
      3824017.83     10088611.08       3824886.3     10088404.93
      3824742.81     10087521.71
#Sta/Elev= 30
  4107.4  158.53  4215.5  153.09    4313   151.3    4426  143.93  4456.9   144.8
  4473.9   142.4    4653  139.82    4690  134.93  4744.6   130.6  4806.3  127.93
  4948.4  129.04  4983.9128.0345  4995.8  125.54  4996.5  123.89    5014  125.72
  5019.4128.0429  5025.4  125.09  5034.3  128.26  5054.6   129.7  5081.9   128.4
  5287.6  129.98  5333.2  128.81  5456.4  133.06  5461.5  134.22  5500.3   133.9
  5652.3  144.58  5763.7  145.55  5814.4  149.32  5830.9  148.04  5894.8  148.87
#Mann= 3 , 0 , 0
  4107.4     .08       0  4983.9     .09       0  5019.4     .08       0
Bank Sta=4983.9,5019.4
XS Rating Curve= 0 ,0
Exp/Cntr=0.3,0.1

Type RM Length L Ch R = 1 ,6504    ,504,504,504
BEGIN DESCRIPTION:
Crystal Creek 040 13.0
END DESCRIPTION:
XS GIS Cut Line= 4
      3824128.14     10088675.04      3825177.66     10088685.46
      3825229.74     10088641.19      3824755.78     10087497.96
#Sta/Elev= 30
  3910.3  153.96    4070  145.78    4090  146.36    4110  143.91    4290  138.41
    4360  138.11    4380  132.71    4410  129.79    4490  127.48    4520   124.9
    4550  126.18  4840.1  124.21  4984.8  125.48  4997.3  122.88  5010.4125.4601
  5098.6  126.48  5223.2  124.97  5688.7  127.65  5720.4  124.94  5725.8   126.7
  5840.2  127.46    5880  128.94  5885.4  130.51    5957  132.03  5980.9  133.98
  6002.6  137.96  6087.2  141.02  6132.5  146.26  6169.7   148.1  6265.8  148.38
#Mann= 3 , 0 , 0
  3910.3     .08       0  4984.8     .09       0  5010.4     .08       0
Bank Sta=4984.8,5010.4
XS Rating Curve= 0 ,0
Exp/Cntr=0.3,0.1

Type RM Length L Ch R = 1 ,6000    ,980,980,980
BEGIN DESCRIPTION:
Crystal Creek 040 12.0
END DESCRIPTION:
XS GIS Cut Line= 4
       3823725.8     10089094.31      3825413.33      10089083.9
      3825567.85     10088861.07      3824777.91     10087448.46
#Sta/Elev= 30
  3255.2  160.18  3607.3  151.69  3757.3  145.74  3797.3  146.23  3817.3  143.96
  3877.3  143.13  3970.2  137.68  4107.3  129.04  4197.3  125.41  4297.3  124.58
  4307.3  122.62  4337.3   122.1  4357.3  124.52  4537.3  124.54  4687.3  121.74
  4982.9  123.18  5019.2  122.96  5221.9  122.15  5235.1  120.66  5384.1  124.07
  5551.9  123.02  5773.5  124.48  5809.7  123.11  6199.3  125.54  6449.5  125.72
  6633.4  136.76  6676.8  143.01  6682.5  145.52  6714.5  144.78  6832.4  148.37
#Mann= 6 ,-1 , 0
  3255.2     .08       0  3970.2     .14       0  4197.3     .05       0
  4982.9     .06       0  5019.2     .05       0  6199.3     .08       0
Bank Sta=4982.9,5019.2
XS Rating Curve= 0 ,0
Exp/Cntr=0.3,0.1

Type RM Length L Ch R = 1 ,5020    ,980,980,980
BEGIN DESCRIPTION:
Crystal Creek 040 10.0
END DESCRIPTION:
XS GIS Cut Line= 4
      3823647.72     10089156.81      3826004.08     10089232.89
      3826189.37     10088797.44      3824793.57     10087406.85
#Sta/Elev= 30
  2111.4   159.8  2251.6  159.93  2331.6   155.7  2770.3  143.03    3102  123.98
  3469.7  123.05    3690  122.06  3808.9  120.86  3852.4  124.65  3862.4  123.49
  3882.5  120.73  4771.1  122.07  5096.3  119.35  5115.7  117.38  5251.9   122.1
  5294.3  123.44    5353  122.71  5414.5  122.05  5435.7   119.7  5477.7  121.06
  5697.3  124.63  5737.5  123.47  5871.9  123.23  5973.1  121.66  6191.6  123.64
    6362  121.73    6560  122.93  6673.1  129.77  6821.6  144.49  6912.5  148.18
#Mann= 14 ,-1 , 0
  2111.4     .08       0  2770.3     .14       0  3469.7     .12       0
    3690     .08       0  3808.9     .12       0  3862.4     .05       0
  4771.1     .06       0  5251.9     .05       0  5294.3     .14       0
    5353     .08       0  5477.7     .14       0  5737.5     .08       0
  5871.9     .12       0  6191.6     .08       0
Bank Sta=4771.1,5251.9
XS Rating Curve= 0 ,0
Exp/Cntr=0.3,0.1

Type RM Length L Ch R = 1 ,4040    ,875,875,875
BEGIN DESCRIPTION:
Crystal Creek 040 8.0
END DESCRIPTION:
XS GIS Cut Line= 4
        3823705.     10089292.23      3826684.81     10089292.62
      3827069.58      10088646.4      3824803.92     10087313.04
#Sta/Elev= 30
  1429.9  157.73  1968.3  145.96  2042.8  143.88  2082.8  138.05  2312.8  124.79
    2622   123.8  2947.2  121.63    3025  120.73  3243.1  121.32  3667.9  122.17
  3671.2  122.01    3823  120.99  3933.7  120.19  4032.3  118.59  4958.8  117.68
    4994  115.37  5032.8  117.67  5613.6  116.92  5662.9  119.83  5943.1  123.41
  6162.1  121.39  6569.7  122.44  6606.1  121.69    6775  121.83  6869.5  117.54
  7058.1  125.14  7390.5  123.83  7452.5  123.84    7681  145.03  7790.7  148.74
#Mann= 20 ,-1 , 0
  1429.9     .08       0  1968.3     .14       0    2622     .12       0
  2947.2     .08       0    3025     .12       0  3243.1     .08       0
  3667.9     .14       0  3671.2     .08       0    3823     .14       0
  3933.7     .12       0  4032.3     .08       0  4958.8     .09       0
  5032.8     .08       0  5613.6     .12       0  5662.9     .14       0
  5943.1     .12       0  6162.1     .14       0  6569.7     .08       0
  6606.1     .12       0  7390.5     .08       0
Bank Sta=4958.8,5032.8
XS Rating Curve= 0 ,0
Exp/Cntr=0.3,0.1

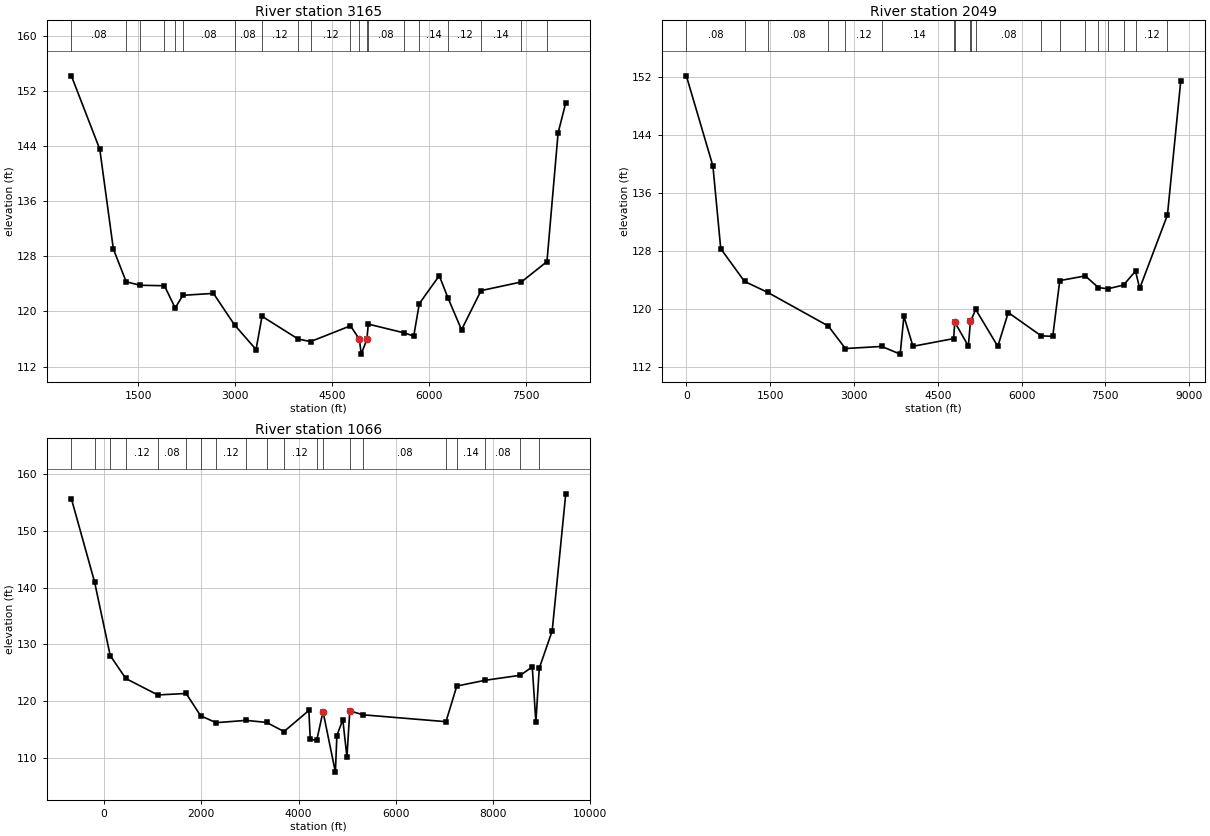
Type RM Length L Ch R = 1 ,3165    ,1116,1116,1116
BEGIN DESCRIPTION:
Crystal Creek 040 6.0
END DESCRIPTION:
XS GIS Cut Line= 4
      3823777.92     10089417.23      3827509.62     10089329.11
      3827559.17     10088422.44      3825074.77     10086708.88
#Sta/Elev= 30
   462.4  154.22   902.5  143.55  1112.5  129.08  1311.1  124.32    1527  123.81
  1903.7  123.74  2070.4  120.51  2189.4  122.35  2662.9  122.63  2990.1  118.05
  3323.1  114.48    3416   119.3  3973.6  116.01  4167.4  115.63    4786  117.92
  4924.3  115.97  4952.6  113.81 5040.29115.9664    5062  118.17  5611.3  116.91
  5766.4  116.44  5852.5  121.14  6161.6   125.2  6295.9  121.99  6506.8  117.34
  6808.5  123.03  7433.8  124.29  7829.9  127.24  8002.5  145.91  8121.2   150.3
#Mann= 20 ,-1 , 0
   462.4     .08       0  1311.1     .14       0    1527     .12       0
  1903.7     .08       0  2070.4     .12       0  2189.4     .08       0
  2990.1     .08       0    3416     .12       0  3973.6     .14       0
  4167.4     .12       0    4786     .12       0  4924.3     .09       0
 5040.29     .12       0    5062     .08       0  5611.3     .12       0
  5852.5     .14       0  6295.9     .12       0  6808.5     .14       0
  7433.8     .12       0  7829.9     .14       0
Bank Sta=4924.3,5040.29
XS Rating Curve= 0 ,0
Exp/Cntr=0.3,0.1

Type RM Length L Ch R = 1 ,2049    ,983,983,983
BEGIN DESCRIPTION:
Crystal Creek 040 4.0
END DESCRIPTION:
XS GIS Cut Line= 5
      3823762.26     10089526.61      3827530.27     10089384.83
      3828345.62     10088912.02      3828408.12     10088542.23
      3825242.12     10086511.41
#Sta/Elev= 30
    -1.1  152.17   474.8  139.74   614.9  128.35  1040.3  123.84  1453.1  122.34
  2540.6  117.69  2846.4  114.59  3495.9  114.88  3826.8  113.82  3893.9  119.04
  4055.8   114.9  4784.1  115.96  4804.3  118.22  5047.7  114.93  5085.2   118.4
  5090.3   118.4  5178.8  119.98  5574.4  114.89    5762  119.55  6350.7  116.34
  6558.2  116.27  6683.6  123.95    7140   124.6  7375.6  122.99  7543.2  122.82
  7825.2  123.34  8039.8  125.26  8114.3  122.87  8611.2  132.99  8848.5  151.39
#Mann= 19 ,-1 , 0
    -1.1     .08       0  1040.3     .12       0  1453.1     .08       0
  2540.6     .08       0  2846.4     .12       0  3495.9     .14       0
  4784.1     .09       0  4804.3     .09       0  5085.2     .09       0
  5090.3     .14       0  5178.8     .08       0  6350.7     .12       0
  6683.6     .14       0    7140     .08       0  7375.6     .12       0
  7543.2     .14       0  7825.2     .14       0  8039.8     .12       0
  8611.2     .08       0
Bank Sta=4804.3,5085.2
XS Rating Curve= 0 ,0
Exp/Cntr=0.3,0.1

Type RM Length L Ch R = 1 ,1066    ,0,0,0
BEGIN DESCRIPTION:
Crystal Creek 040 2.0
END DESCRIPTION:
XS GIS Cut Line= 5
       3823647.7     10089682.86      3827537.05     10089419.49
      3829081.65      10088745.4      3829085.21     10088599.52
      3825246.69     10086370.37
#Sta/Elev= 30
  -672.1  155.67  -195.3     141   126.4  128.04   446.3  123.99  1104.9  121.09
  1688.2  121.35  1985.6  117.43  2303.3   116.2    2922  116.61  3342.3  116.25
  3701.1  114.64  4212.1  118.35  4241.7  113.28    4374  113.08  4503.6  118.16
  4758.1  107.49  4788.7  113.92  4910.6  116.73  4995.8  110.13  5054.1  118.29
  5326.2  117.59  7032.1  116.38  7255.2  122.66  7835.2  123.67  8564.7  124.56
  8807.3  126.04  8881.8  116.28  8951.2   125.8  9217.3  132.38  9496.2  156.53
#Mann= 20 ,-1 , 0
  -672.1     .08       0  -195.3     .14       0   126.4     .08       0
   446.3     .12       0  1104.9     .08       0  1688.2     .08       0
  1985.6     .08       0  2303.3     .12       0    2922     .14       0
  3342.3     .14       0  3701.1     .12       0    4374     .08       0
  4503.6     .09       0  5054.1     .08       0  5326.2     .08       0
  7032.1     .12       0  7255.2     .14       0  7835.2     .08       0
  8564.7     .12       0  8951.2     .08       0
Bank Sta=4503.6,5054.1
XS Rating Curve= 0 ,0
Exp/Cntr=0.3,0.1

Chan Stop Cuts=-1
Use User Specified Reach Order=0
Composite Channel Slope=5

--- Crystal Creek 040.g10 (geometry) ---

Geom Title=Existing Conditions
Program Version=4.10

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
River Reach=Crystal Creek 04,Reach-1

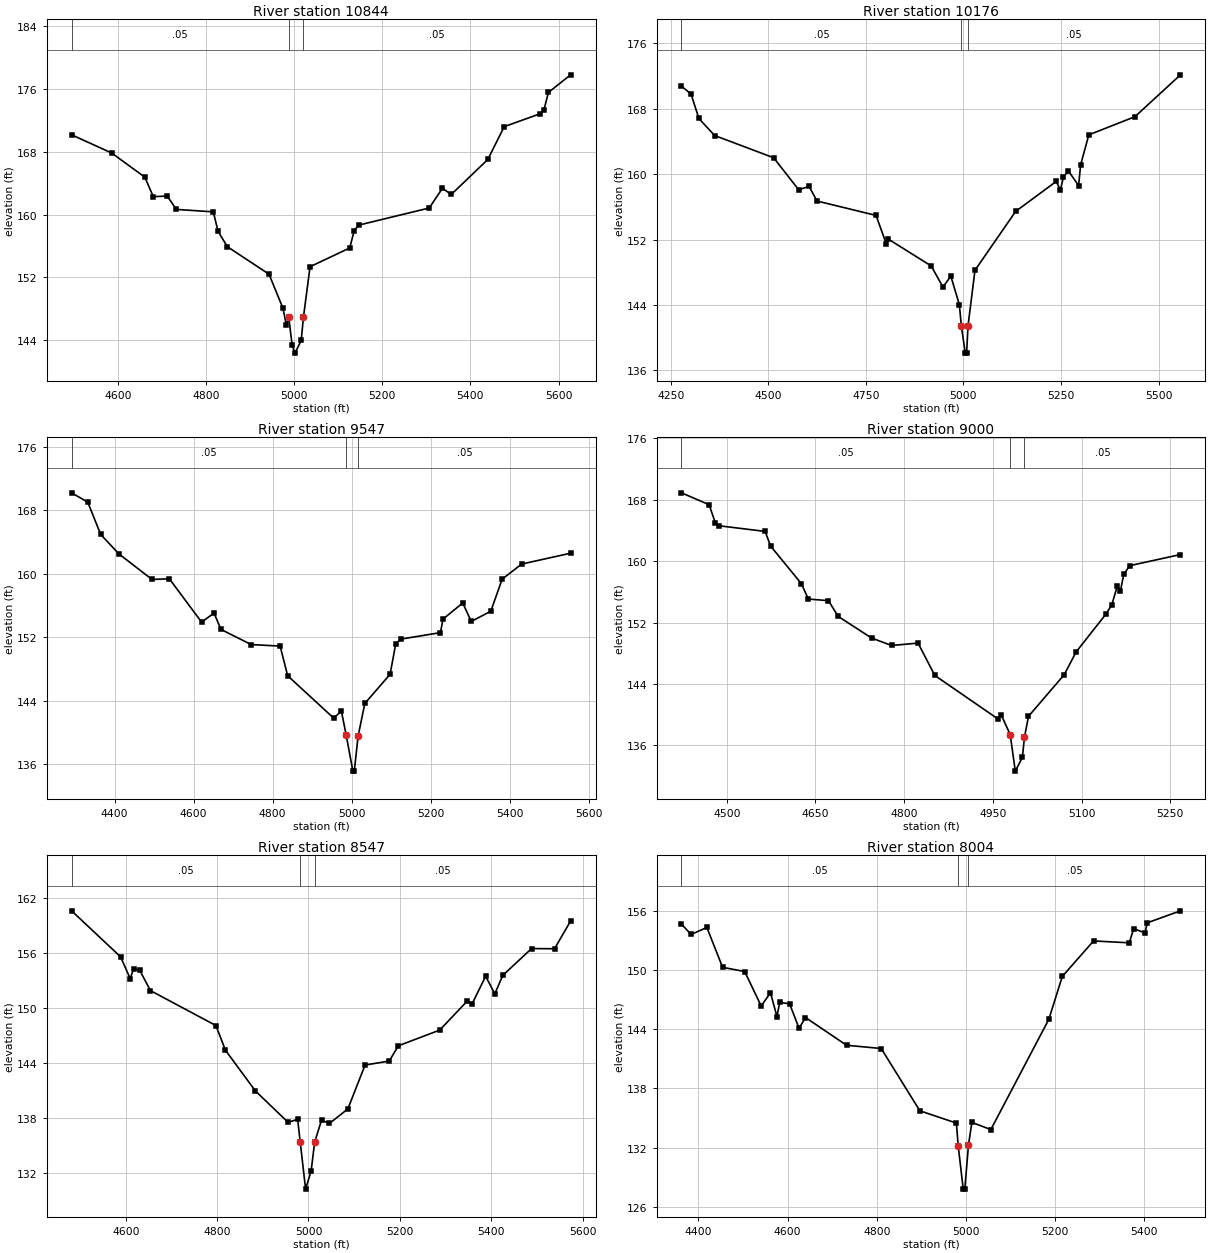
Type RM Length L Ch R = 1 ,10844   ,668,668,668
BEGIN DESCRIPTION:
Crystal Creek 040 21.0
END DESCRIPTION:
XS GIS Cut Line= 3
      3822142.59     10088057.53      3821986.34     10087570.53
      3821952.48     10086950.71
#Sta/Elev= 30
  4495.2  170.15    4586  167.84  4661.4  164.76  4680.5  162.28    4712  162.36
    4733  160.66  4816.7  160.35  4827.5  157.86  4848.6  155.92  4943.1  152.42
  4974.6   148.1  4982.6  145.94  4987.8  146.96  4995.6  143.37    5002  142.38
  5016.1  143.99 5021.27 146.973  5036.2  153.37  5126.3  155.76  5136.3  157.94
  5146.3  158.66  5306.6  160.84  5336.6  163.35  5356.6  162.56  5439.5  167.01
  5476.8  171.19  5556.9   172.8  5566.9  173.31    5577  175.54  5627.4  177.78
#Mann= 3 , 0 , 0
  4495.2     .05       0  4987.8     .07       0 5021.27     .05       0
Bank Sta=4987.8,5021.27
XS Rating Curve= 0 ,0
Exp/Cntr=0.3,0.1

Type RM Length L Ch R = 1 ,10176   ,629,629,629
BEGIN DESCRIPTION:
Crystal Creek 040 20.0
END DESCRIPTION:
XS GIS Cut Line= 3
      3822632.18     10088125.26      3822538.42     10087419.49
      3822379.69     10086875.65
#Sta/Elev= 30
  4277.7  170.75  4302.1  169.82  4322.3  166.81  4362.6  164.73  4513.9  162.01
  4577.9   158.1  4604.7   158.5  4624.9  156.72  4776.2  154.96  4802.8  151.44
  4807.8  152.06  4917.5  148.78  4947.7   146.2  4967.9  147.53  4989.7  144.04
 4994.73 141.456  5004.8  138.12  5008.3  138.12  5011.8  141.42  5029.7  148.25
  5133.9  155.45    5238  159.12  5248.5  158.05  5256.5  159.69  5269.3  160.39
  5295.2   158.6  5300.5  161.17  5321.4  164.81  5439.5  167.03  5556.2  172.15
#Mann= 3 , 0 , 0
  4277.7     .05       0 4994.73     .07       0  5011.8     .05       0
Bank Sta=4994.73,5011.8
XS Rating Curve= 0 ,0
Exp/Cntr=0.3,0.1

Type RM Length L Ch R = 1 ,9547    ,547,547,547
BEGIN DESCRIPTION:
Crystal Creek 040 19.0
END DESCRIPTION:
XS GIS Cut Line= 3
      3822850.93     10088135.59      3823061.86     10087450.74
      3823413.13     10087031.82
#Sta/Elev= 30
  4291.2  170.22  4332.1  169.04  4364.8  164.97    4411  162.51  4494.7  159.29
  4538.7  159.37  4620.3   153.9  4651.7  155.05  4669.4  152.98  4745.9  151.07
  4819.1  150.88  4838.1  147.14  4955.1  141.77    4974  142.71  4986.5  139.61
  5003.3   135.1  5006.8   135.1  5016.6 139.541  5033.5  143.64  5097.5  147.32
  5111.8  151.17  5124.8  151.76    5225  152.58  5231.5  154.29  5281.4  156.32
    5303  153.99  5352.5  155.28  5381.1  159.32  5430.5  161.23  5554.5   162.6
#Mann= 3 , 0 , 0
  4291.2     .05       0  4986.5     .07       0  5016.6     .05       0
Bank Sta=4986.5,5016.6
XS Rating Curve= 0 ,0
Exp/Cntr=0.3,0.1

Type RM Length L Ch R = 1 ,9000    ,453,453,453
BEGIN DESCRIPTION:
Crystal Creek 040 18.0
END DESCRIPTION:
XS GIS Cut Line= 3
      3823335.29     10088146.08      3823492.63     10087591.26
      3823525.38     10087325.87
#Sta/Elev= 30
  4423.3  168.92  4470.1  167.37  4480.5  165.02  4486.7  164.63  4564.9  163.89
    4574  161.99    4626   157.1  4637.9  155.08  4671.9  154.87  4688.4  152.82
  4744.9     150  4778.8  149.03  4823.5  149.34  4851.8  145.13  4958.6  139.46
    4964  140.02  4979.4  137.41    4988  132.66    5000  134.46  5003.5  137.06
  5010.3   139.8  5070.7  145.22  5090.9  148.19  5141.2  153.11  5151.3  154.34
  5160.7  156.81  5165.8  156.13  5171.5   158.3  5181.6  159.43  5267.4  160.88
#Mann= 3 , 0 , 0
  4423.3     .05       0  4979.4     .07       0  5003.5     .05       0
Bank Sta=4979.4,5003.5
XS Rating Curve= 0 ,0
Exp/Cntr=0.3,0.1

Type RM Length L Ch R = 1 ,8547    ,543,543,543
BEGIN DESCRIPTION:
Crystal Creek 040 17.0
END DESCRIPTION:
XS GIS Cut Line= 3
      3823590.48     10088162.57      3823885.64     10087738.93
      3823828.35     10087166.01
#Sta/Elev= 30
  4481.6  160.64  4588.9  155.61  4609.8  153.24  4617.5  154.33  4630.7  154.15
  4654.1  151.93  4797.4  148.12  4818.3  145.42  4883.8  140.98  4955.4  137.55
  4976.3  137.88 4981.92 135.393  4993.7  130.26  5005.8  132.24 5013.46 135.372
  5028.5  137.78    5046  137.43  5086.2  139.02  5123.9  143.81  5176.7  144.24
  5196.8  145.91  5287.2  147.62  5347.5  150.79  5357.6  150.43  5387.7   153.5
  5407.8  151.58  5425.4   153.6  5488.2  156.52  5538.5   156.5  5573.7  159.53
#Mann= 3 , 0 , 0
  4481.6     .05       0 4981.92     .07       0 5013.46     .05       0
Bank Sta=4981.92,5013.46
XS Rating Curve= 0 ,0
Exp/Cntr=0.3,0.1

Type RM Length L Ch R = 1 ,8004    ,454,454,454
BEGIN DESCRIPTION:
Crystal Creek 040 16.0
END DESCRIPTION:
XS GIS Cut Line= 3
      3823867.81      10088311.1      3824350.92     10087928.17
      3824376.96     10087426.41
#Sta/Elev= 30
  4362.2  154.69  4383.9  153.65  4419.1  154.36  4454.4  150.31    4504  149.88
  4540.9  146.38  4561.8  147.73  4576.2  145.31  4582.6  146.75  4604.7   146.6
  4625.9  144.11  4640.3  145.21  4732.3  142.39  4810.1  142.06  4896.7  135.73
  4978.7  134.48  4982.7  132.17    4994  127.77  4997.5  127.77  5005.8  132.27
  5013.4  134.55  5055.9  133.82    5186  145.03  5216.1  149.38  5286.2  152.99
  5366.3   152.8  5376.3  154.24  5401.6   153.8  5406.6  154.83  5481.1  156.05
#Mann= 3 , 0 , 0
  4362.2     .05       0  4982.7     .07       0  5005.8     .05       0
Bank Sta=4982.7,5005.8
XS Rating Curve= 0 ,0
Exp/Cntr=0.3,0.1

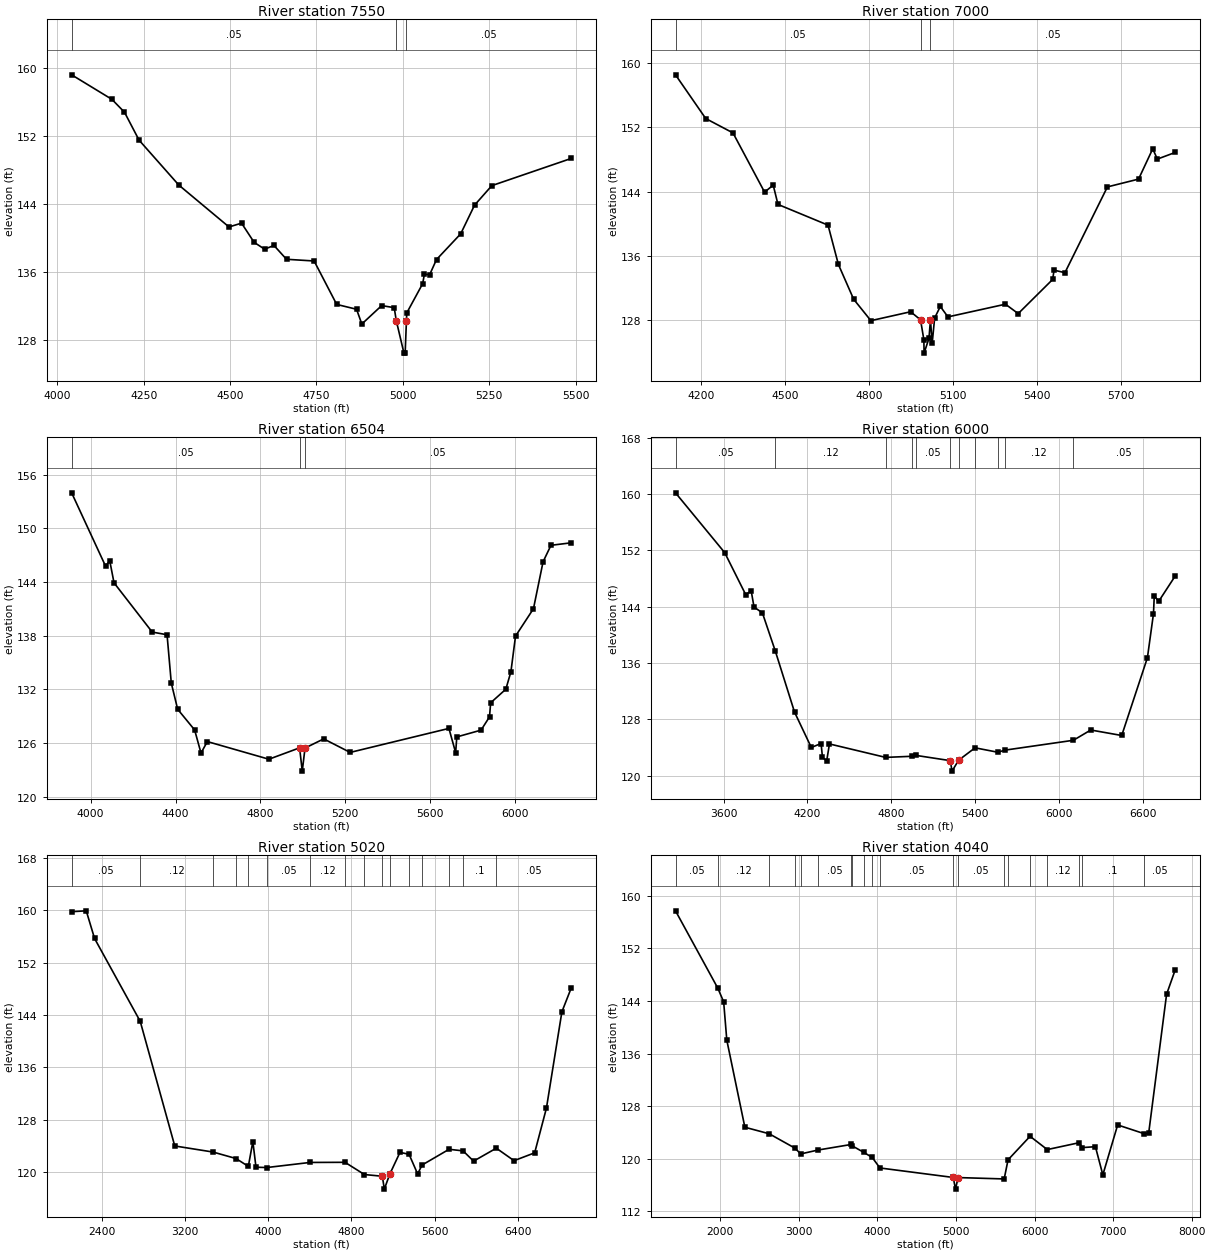
Type RM Length L Ch R = 1 ,7550    ,550,550,550
BEGIN DESCRIPTION:
Crystal Creek 040 15.0
END DESCRIPTION:
XS GIS Cut Line= 3
      3823917.86     10088511.07       3824734.6     10087985.46
      3824717.85     10087511.11
#Sta/Elev= 30
  4041.6  159.22  4158.1  156.33  4194.5  154.81  4236.7  151.52  4351.6  146.23
  4496.9  141.29  4533.2  141.74  4569.5  139.48  4599.9  138.67    4627  139.11
  4663.3  137.48  4743.2  137.28  4808.5  132.16    4866  131.59  4881.2  129.85
  4938.6  132.02  4974.9  131.78    4981  130.24  5003.1  126.42  5006.6  126.42
 5010.34 130.256  5011.3  131.16  5057.3  134.61  5062.3  135.73  5077.3  135.65
  5097.3  137.45  5167.3  140.48  5207.4  143.86  5257.4  146.16  5487.5  149.37
#Mann= 3 , 0 , 0
  4041.6     .05       0    4981     .07       0 5010.34     .05       0
Bank Sta=4981,5010.34
XS Rating Curve= 0 ,0
Exp/Cntr=0.3,0.1

Type RM Length L Ch R = 1 ,7000    ,496,496,496
BEGIN DESCRIPTION:
Crystal Creek 040 14.0
END DESCRIPTION:
XS GIS Cut Line= 3
      3824017.83     10088611.08       3824886.3     10088404.93
      3824742.81     10087521.71
#Sta/Elev= 30
  4107.4  158.53  4215.5  153.09    4313   151.3    4426  143.93  4456.9   144.8
  4473.9   142.4    4653  139.82    4690  134.93  4744.6   130.6  4806.3  127.93
  4948.4  129.04  4983.9 128.035  4995.8  125.54  4996.5  123.89    5014  125.72
  5019.4 128.043  5025.4  125.09  5034.3  128.26  5054.6   129.7  5081.9   128.4
  5287.6  129.98  5333.2  128.81  5456.4  133.06  5461.5  134.22  5500.3   133.9
  5652.3  144.58  5763.7  145.55  5814.4  149.32  5830.9  148.04  5894.8  148.87
#Mann= 3 , 0 , 0
  4107.4     .05       0  4983.9     .07       0  5019.4     .05       0
Bank Sta=4983.9,5019.4
XS Rating Curve= 0 ,0
Exp/Cntr=0.3,0.1

Type RM Length L Ch R = 1 ,6504    ,504,504,504
BEGIN DESCRIPTION:
Crystal Creek 040 13.0
END DESCRIPTION:
XS GIS Cut Line= 4
      3824128.14     10088675.04      3825177.66     10088685.46
      3825229.74     10088641.19      3824755.78     10087497.96
#Sta/Elev= 30
  3910.3  153.96    4070  145.78    4090  146.36    4110  143.91    4290  138.41
    4360  138.11    4380  132.71    4410  129.79    4490  127.48    4520   124.9
    4550  126.18  4840.1  124.21  4984.8  125.48  4997.3  122.88  5010.4  125.46
  5098.6  126.48  5223.2  124.97  5688.7  127.65  5720.4  124.94  5725.8   126.7
  5840.2  127.46    5880  128.94  5885.4  130.51    5957  132.03  5980.9  133.98
  6002.6  137.96  6087.2  141.02  6132.5  146.26  6169.7   148.1  6265.8  148.38
#Mann= 3 , 0 , 0
  3910.3     .05       0  4984.8     .07       0  5010.4     .05       0
Bank Sta=4984.8,5010.4
XS Rating Curve= 0 ,0
Exp/Cntr=0.3,0.1

Type RM Length L Ch R = 1 ,6000    ,980,980,980
BEGIN DESCRIPTION:
Crystal Creek 040 12.0
END DESCRIPTION:
XS GIS Cut Line= 4
       3823725.8     10089094.31      3825413.33      10089083.9
      3825567.85     10088861.07      3824777.91     10087448.46
#Sta/Elev= 30
  3255.2  160.18  3607.3  151.69  3757.3  145.74  3797.3  146.23  3817.3  143.96
  3877.3  143.13  3970.2  137.68  4107.3  129.04  4227.3  124.02  4297.3  124.58
  4307.3  122.62  4337.3   122.1  4357.3  124.52  4759.6  122.61  4950.2  122.77
  4974.4   122.9  5221.9  122.15  5235.1  120.66  5281.3   122.2  5399.6  123.97
    5563  123.34  5613.5  123.64  6103.4  125.04    6228   126.5  6449.5  125.72
  6633.4  136.76  6676.8  143.01  6682.5  145.52  6714.5  144.78  6832.4  148.37
#Mann= 11 ,-1 , 0
  3255.2     .05       0  3970.2     .12       0  4759.6     .05       0
  4950.2      .1       0  4974.4     .05       0  5221.9     .03       0
  5281.3     .05       0  5399.6     .12       0    5563     .05       0
  5613.5     .12       0  6103.4     .05       0
Bank Sta=5221.9,5281.3
XS Rating Curve= 0 ,0
Exp/Cntr=0.3,0.1

Type RM Length L Ch R = 1 ,5020    ,980,980,980
BEGIN DESCRIPTION:
Crystal Creek 040 10.0
END DESCRIPTION:
XS GIS Cut Line= 4
      3823647.72     10089156.81      3826004.08     10089232.89
      3826189.37     10088797.44      3824793.57     10087406.85
#Sta/Elev= 30
  2111.4   159.8  2251.6  159.93  2331.6   155.7  2770.3  143.03    3102  123.98
  3469.7  123.05    3690  122.06  3808.9  120.86  3852.4  124.65  3882.5  120.73
  3985.7  120.68  4401.6  121.46  4737.9  121.48  4924.4  119.61  5096.3  119.35
  5115.7  117.38    5167  119.64    5266     123    5353  122.71  5435.7   119.7
  5477.7  121.06  5737.5  123.47  5871.9  123.23  5973.1  121.66  6191.6  123.64
    6362  121.73    6560  122.93  6673.1  129.77  6821.6  144.49  6912.5  148.18
#Mann= 16 ,-1 , 0
  2111.4     .05       0  2770.3     .12       0  3469.7      .1       0
    3690     .05       0  3808.9      .1       0  3985.7     .05       0
  4401.6     .12       0  4737.9     .05       0  4924.4      .1       0
  5096.3     .03       0    5167     .12       0    5353     .05       0
  5477.7     .12       0  5737.5     .05       0  5871.9      .1       0
  6191.6     .05       0
Bank Sta=5096.3,5167
XS Rating Curve= 0 ,0
Exp/Cntr=0.3,0.1

Type RM Length L Ch R = 1 ,4040    ,875,875,875
BEGIN DESCRIPTION:
Crystal Creek 040 8.0
END DESCRIPTION:
XS GIS Cut Line= 4
        3823705.     10089292.23      3826684.81     10089292.62
      3827069.58      10088646.4      3824803.92     10087313.04
#Sta/Elev= 30
  1429.9  157.73  1968.3  145.96  2042.8  143.88  2082.8  138.05  2312.8  124.79
    2622   123.8  2947.2  121.63    3025  120.73  3243.1  121.32  3667.9  122.17
  3671.2  122.01    3823  120.99  3933.7  120.19  4032.3  118.59 4965.04 117.146
    4994  115.37    5027  117.13  5613.6  116.92  5662.9  119.83  5943.1  123.41
  6162.1  121.39  6569.7  122.44  6606.1  121.69    6775  121.83  6869.5  117.54
  7058.1  125.14  7390.5  123.83  7452.5  123.84    7681  145.03  7790.7  148.74
#Mann= 20 ,-1 , 0
  1429.9     .05       0  1968.3     .12       0    2622      .1       0
  2947.2     .05       0    3025      .1       0  3243.1     .05       0
  3667.9     .12       0  3671.2     .05       0    3823     .12       0
  3933.7      .1       0  4032.3     .05       0 4965.04     .07       0
    5027     .05       0  5613.6      .1       0  5662.9     .12       0
  5943.1      .1       0  6162.1     .12       0  6569.7     .05       0
  6606.1      .1       0  7390.5     .05       0
Bank Sta=4965.04,5027
XS Rating Curve= 0 ,0
Exp/Cntr=0.3,0.1