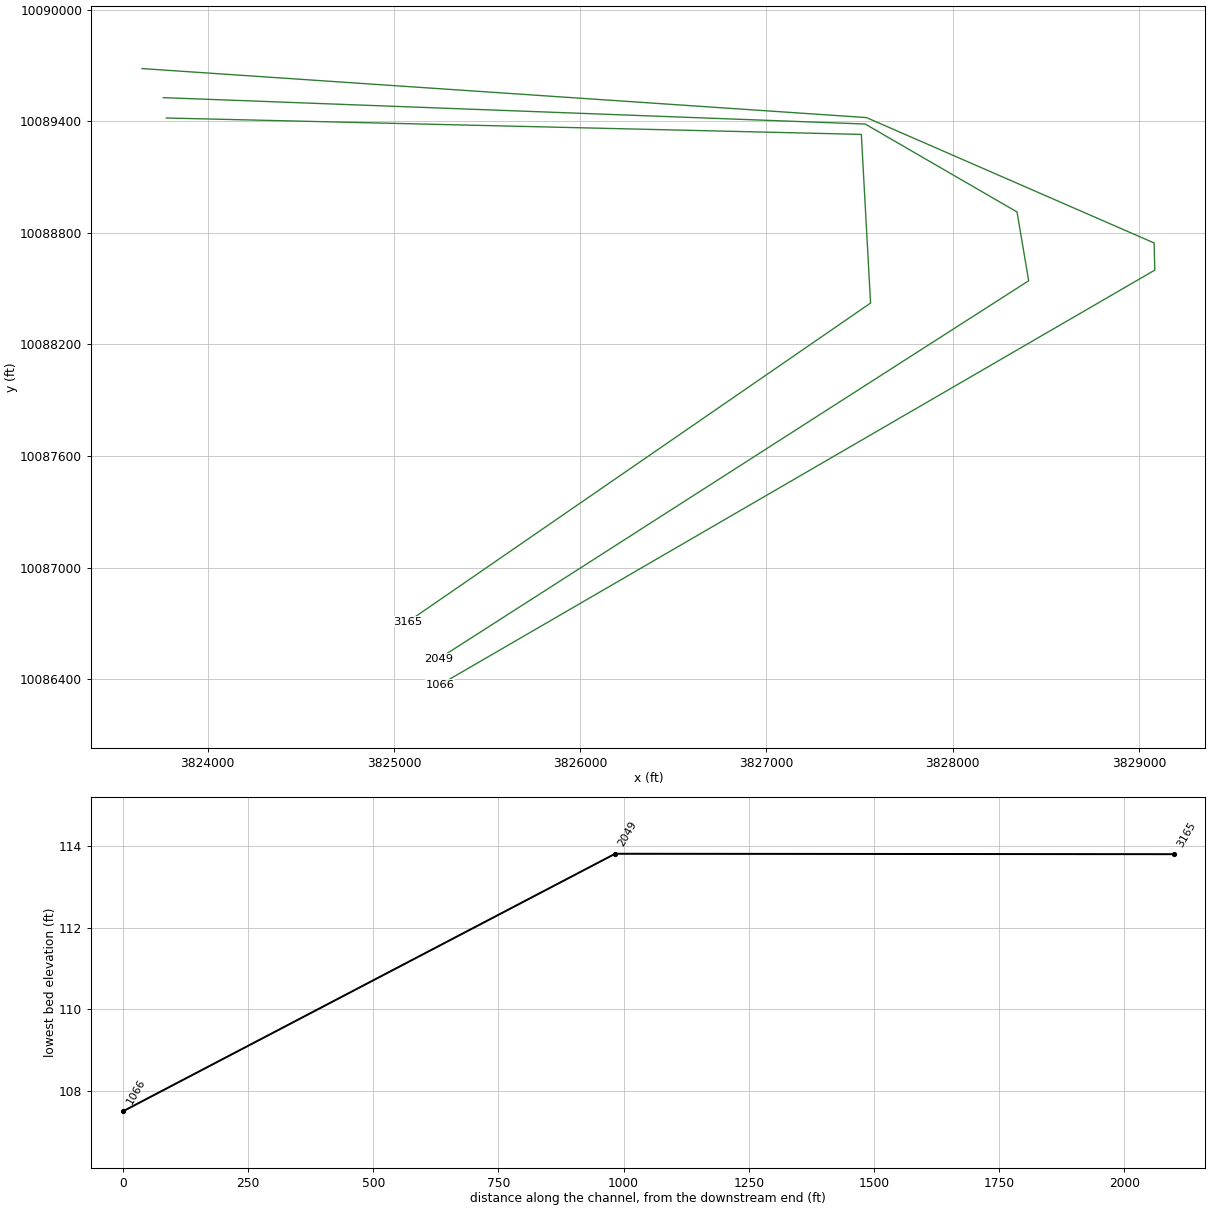
HEC-RAS study Crystal Creek 040.prj: Crystal Creek 040 Base Level Engineering

--- Crystal Creek 040.g10 (geometry) --- (continued)

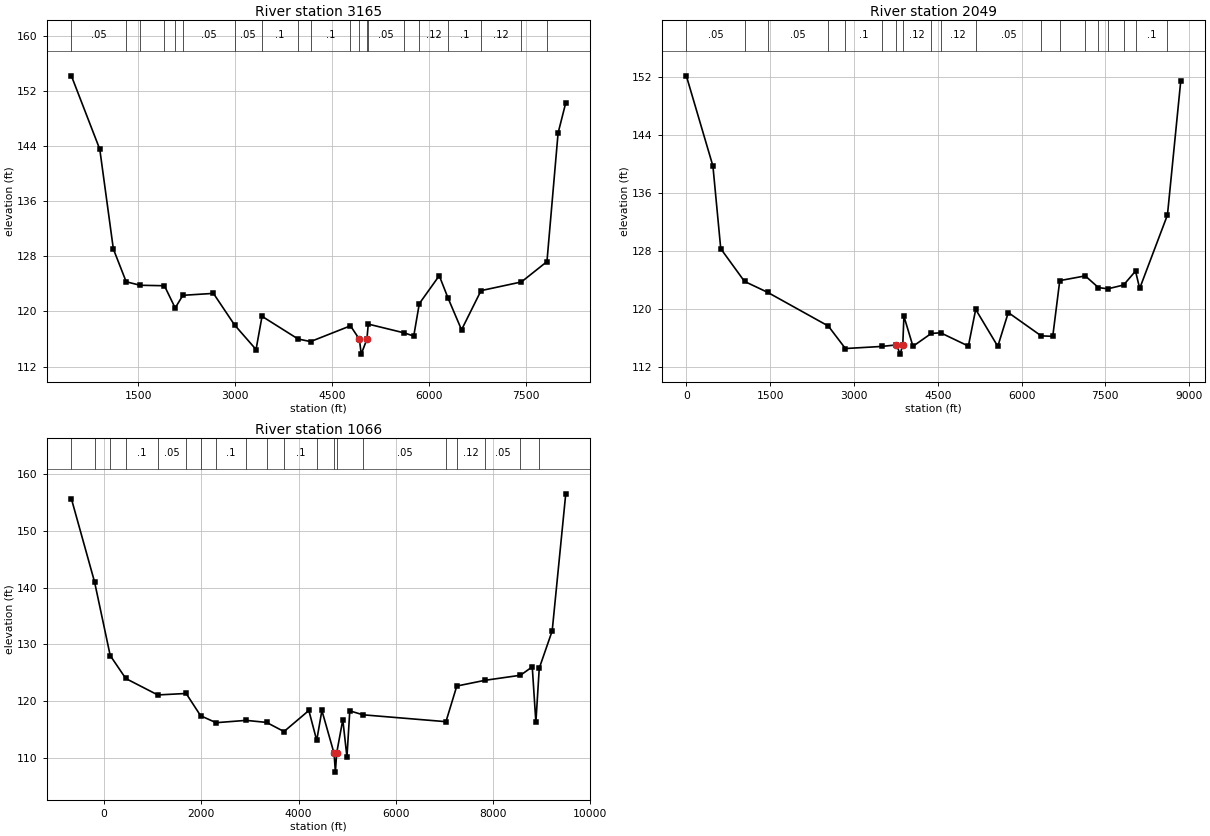
Type RM Length L Ch R = 1 ,3165    ,1116,1116,1116
BEGIN DESCRIPTION:
Crystal Creek 040 6.0
END DESCRIPTION:
XS GIS Cut Line= 4
      3823777.92     10089417.23      3827509.62     10089329.11
      3827559.17     10088422.44      3825074.77     10086708.88
#Sta/Elev= 30
   462.4  154.22   902.5  143.55  1112.5  129.08  1311.1  124.32    1527  123.81
  1903.7  123.74  2070.4  120.51  2189.4  122.35  2662.9  122.63  2990.1  118.05
  3323.1  114.48    3416   119.3  3973.6  116.01  4167.4  115.63    4786  117.92
  4924.3  115.97  4952.6  113.81 5040.29 115.966    5062  118.17  5611.3  116.91
  5766.4  116.44  5852.5  121.14  6161.6   125.2  6295.9  121.99  6506.8  117.34
  6808.5  123.03  7433.8  124.29  7829.9  127.24  8002.5  145.91  8121.2   150.3
#Mann= 20 ,-1 , 0
   462.4     .05       0  1311.1     .12       0    1527      .1       0
  1903.7     .05       0  2070.4      .1       0  2189.4     .05       0
  2990.1     .05       0    3416      .1       0  3973.6     .12       0
  4167.4      .1       0    4786      .1       0  4924.3     .07       0
 5040.29      .1       0    5062     .05       0  5611.3      .1       0
  5852.5     .12       0  6295.9      .1       0  6808.5     .12       0
  7433.8      .1       0  7829.9     .12       0
Bank Sta=4924.3,5040.29
XS Rating Curve= 0 ,0
Exp/Cntr=0.3,0.1

Type RM Length L Ch R = 1 ,2049    ,983,983,983
BEGIN DESCRIPTION:
Crystal Creek 040 4.0
END DESCRIPTION:
XS GIS Cut Line= 5
      3823762.26     10089526.61      3827530.27     10089384.83
      3828345.62     10088912.02      3828408.12     10088542.23
      3825242.12     10086511.41
#Sta/Elev= 30
    -1.1  152.17   474.8  139.74   614.9  128.35  1040.3  123.84  1453.1  122.34
  2540.6  117.69  2846.4  114.59  3495.9  114.88 3760.31 115.092  3826.8  113.82
 3873.76 115.135  3893.9  119.04  4055.8   114.9  4383.4  116.67  4550.8  116.76
  5047.7  114.93  5178.8  119.98  5574.4  114.89    5762  119.55  6350.7  116.34
  6558.2  116.27  6683.6  123.95    7140   124.6  7375.6  122.99  7543.2  122.82
  7825.2  123.34  8039.8  125.26  8114.3  122.87  8611.2  132.99  8848.5  151.39
#Mann= 19 ,-1 , 0
    -1.1     .05       0  1040.3      .1       0  1453.1     .05       0
  2540.6     .05       0  2846.4      .1       0  3495.9     .12       0
 3760.31     .07       0 3873.76     .12       0  4383.4      .1       0
  4550.8     .12       0  5178.8     .05       0  6350.7      .1       0
  6683.6     .12       0    7140     .05       0  7375.6      .1       0
  7543.2     .12       0  7825.2     .12       0  8039.8      .1       0
  8611.2     .05       0
Bank Sta=3760.31,3873.76
XS Rating Curve= 0 ,0
Exp/Cntr=0.3,0.1

Type RM Length L Ch R = 1 ,1066    ,0,0,0
BEGIN DESCRIPTION:
Crystal Creek 040 2.0
END DESCRIPTION:
XS GIS Cut Line= 5
       3823647.7     10089682.86      3827537.05     10089419.49
      3829081.65      10088745.4      3829085.21     10088599.52
      3825246.69     10086370.37
#Sta/Elev= 30
  -672.1  155.67  -195.3     141   126.4  128.04   446.3  123.99  1104.9  121.09
  1688.2  121.35  1985.6  117.43  2303.3   116.2    2922  116.61  3342.3  116.25
  3701.1  114.64  4212.1  118.35    4374  113.08  4480.5  118.35    4731  110.79
  4758.1  107.49 4784.15 110.836  4910.6  116.73  4995.8  110.13  5054.1  118.29
  5326.2  117.59  7032.1  116.38  7255.2  122.66  7835.2  123.67  8564.7  124.56
  8807.3  126.04  8881.8  116.28  8951.2   125.8  9217.3  132.38  9496.2  156.53
#Mann= 20 ,-1 , 0
  -672.1     .05       0  -195.3     .12       0   126.4     .05       0
   446.3      .1       0  1104.9     .05       0  1688.2     .05       0
  1985.6     .05       0  2303.3      .1       0    2922     .12       0
  3342.3     .12       0  3701.1      .1       0    4374     .05       0
    4731     .07       0 4784.15     .05       0  5326.2     .05       0
  7032.1      .1       0  7255.2     .12       0  7835.2     .05       0
  8564.7      .1       0  8951.2     .05       0
Bank Sta=4731,4784.15
XS Rating Curve= 0 ,0
Exp/Cntr=0.3,0.1