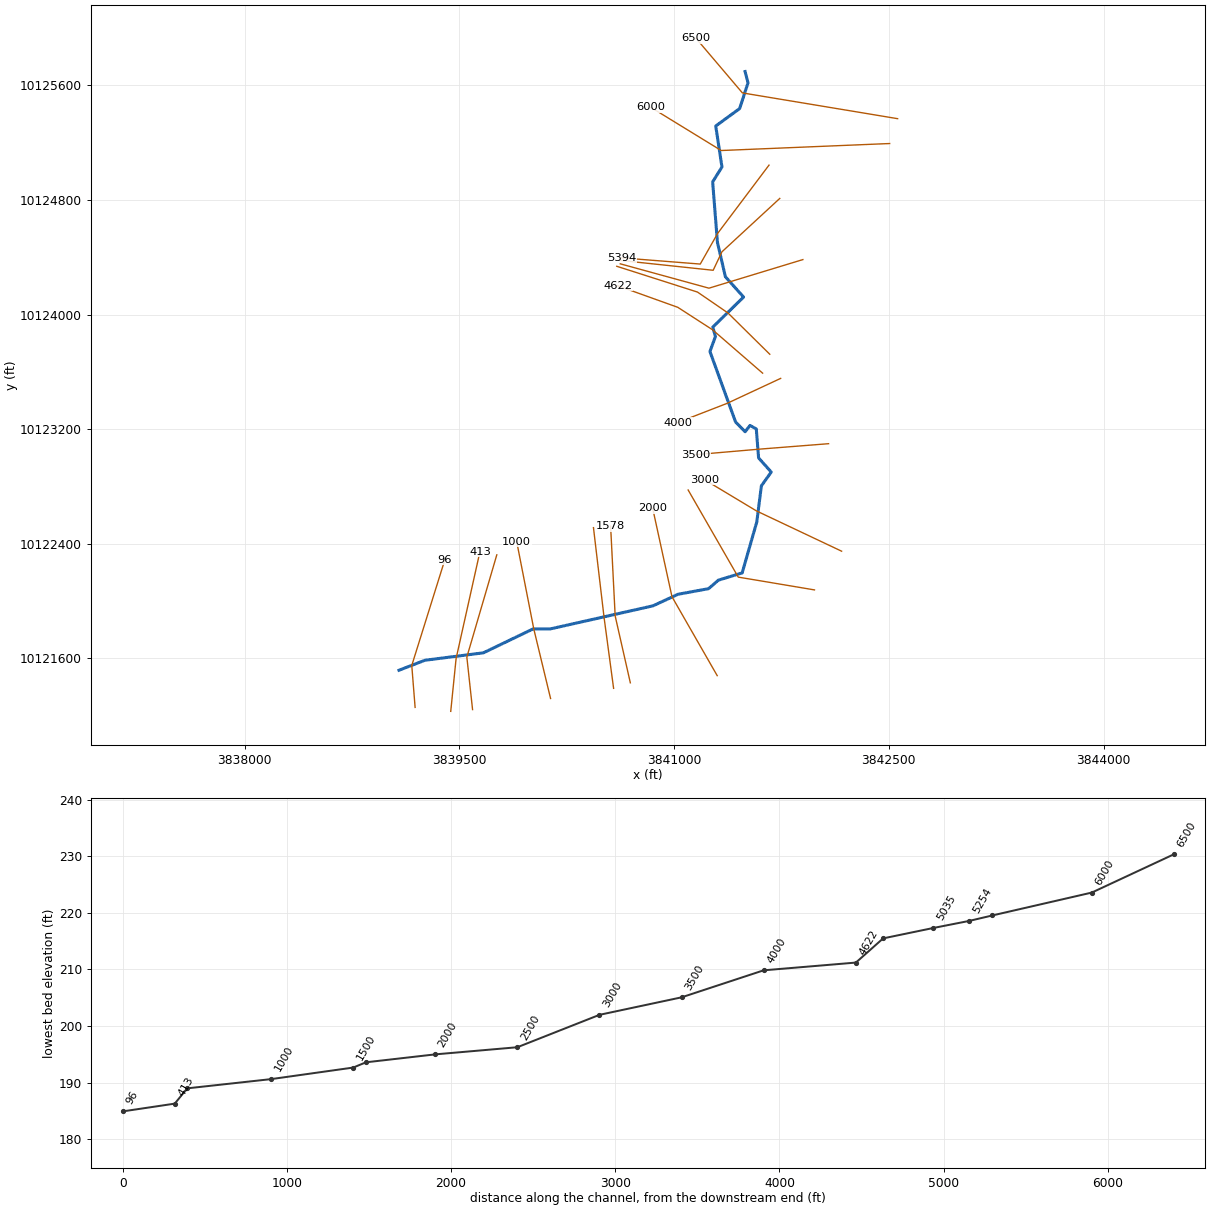
--- Crystal Creek 043.prj (project) ---

Proj Title=Crystal Creek 043 Base Level Engineering
Current Plan=p01
Default Exp/Contr=0.3,0.1
English Units
Geom File=g01
Flow File=f01
Flow File=f02
Plan File=p01
Y Axis Title=Elevation
X Axis Title(PF)=Main Channel Distance
X Axis Title(XS)=Station
BEGIN DESCRIPTION:
Crystal Creek 043
END DESCRIPTION:
DSS Export Rating Curves= 0
DSS Export Rating Curve Sorted= 0
DSS Export Volume Flow Curves= 0
DXF OffsetX= 0
DXF OffsetY= 0
DXF ScaleX= 1
DXF ScaleY= 10

--- Crystal Creek 043.p01 (plan) ---

Plan Title=Multiple Run
Short Identifier=Multiple
Geom File=g01
Flow File=f01
Subcritical Flow
K Sum by GR= 0
Std Step Tol= 0.01
Critical Tol= 0.01
Num of Std Step Trials= 20
Max Error Tol= 0.3
Flow Tol Ratio= 0.001
Split Flow NTrial= 30
Split Flow Tol= 0.02
Split Flow Ratio= 0.02
Log Output Level= 0
Friction Slope Method= 1
Unsteady Friction Slope Method= 2
Unsteady Bridges Friction Slope Method= 1
Parabolic Critical Depth
Global Vel Dist=  1 , 1 , 1
Global Log Level= 0
CheckData=True
Encroach Param= -1, 0, 0, 0
BEGIN DESCRIPTION:
Multiple Run
END DESCRIPTION:

--- Crystal Creek 043.f01 (steady flow) ---

Flow Title=Multiple
Program Version=4.10
Number of Profiles= 7
Profile Names=10-year,25-year,50-year,1pct_min,100-year,1pct_plu,500-year
River Rch & RM=Crystal Creek 04,Reach-1         ,6500
     560     748    1002     441    1333    4026    2439
Boundary for River Rch & Prof#=Crystal Creek 04,Reach-1         , 1
Up Type= 0
Dn Type= 3
Dn Slope=0.005
Boundary for River Rch & Prof#=Crystal Creek 04,Reach-1         , 2
Up Type= 0
Dn Type= 3
Dn Slope=0.005
Boundary for River Rch & Prof#=Crystal Creek 04,Reach-1         , 3
Up Type= 0
Dn Type= 3
Dn Slope=0.005
Boundary for River Rch & Prof#=Crystal Creek 04,Reach-1         , 4
Up Type= 0
Dn Type= 3
Dn Slope=0.005
Boundary for River Rch & Prof#=Crystal Creek 04,Reach-1         , 5
Up Type= 0
Dn Type= 3
Dn Slope=0.005
Boundary for River Rch & Prof#=Crystal Creek 04,Reach-1         , 6
Up Type= 0
Dn Type= 3
Dn Slope=0.005
Boundary for River Rch & Prof#=Crystal Creek 04,Reach-1         , 7
Up Type= 0
Dn Type= 3
Dn Slope=0.005
DSS Import GetInterval= 0
DSS Import GetPeak= 0
DSS Import FillOption= 0

--- Crystal Creek 043.f02 (steady flow) ---

Flow Title=Orig_BLE_Flow
Program Version=4.10
Number of Profiles= 7
Profile Names=10-year,25-year,50-year,1pct_min,100-year,1pct_plu,500-year
River Rch & RM=Crystal Creek 04,Reach-1         ,6500
     560     733     871     339    1025    3096    1418
Boundary for River Rch & Prof#=Crystal Creek 04,Reach-1         , 1
Up Type= 0
Dn Type= 3
Dn Slope=0.005
Boundary for River Rch & Prof#=Crystal Creek 04,Reach-1         , 2
Up Type= 0
Dn Type= 3
Dn Slope=0.005
Boundary for River Rch & Prof#=Crystal Creek 04,Reach-1         , 3
Up Type= 0
Dn Type= 3
Dn Slope=0.005
Boundary for River Rch & Prof#=Crystal Creek 04,Reach-1         , 4
Up Type= 0
Dn Type= 3
Dn Slope=0.005
Boundary for River Rch & Prof#=Crystal Creek 04,Reach-1         , 5
Up Type= 0
Dn Type= 3
Dn Slope=0.005
Boundary for River Rch & Prof#=Crystal Creek 04,Reach-1         , 6
Up Type= 0
Dn Type= 3
Dn Slope=0.005
Boundary for River Rch & Prof#=Crystal Creek 04,Reach-1         , 7
Up Type= 0
Dn Type= 3
Dn Slope=0.005
DSS Import GetInterval= 0
DSS Import GetPeak= 0
DSS Import FillOption= 0

--- Crystal Creek 043.g01 (geometry) ---

Geom Title=Existing Conditions
Program Version=4.10

River Reach=Crystal Creek 04,Reach-1
Reach XY= 30
      3841495.39     10125697.13        3841516.     10125618.44
      3841457.41     10125438.42      3841290.41     10125316.56
      3841333.93     10125030.46      3841268.83     10124926.29
      3841302.31      10124503.9      3841357.84      10124263.9
      3841484.88     10124121.87      3841269.99     10123912.13
      3841288.31     10123845.94      3841249.89     10123741.83
      3841429.17     10123249.22      3841495.86     10123181.36
      3841529.72     10123225.14      3841573.77      10123200.9
      3841589.84     10122998.48      3841678.18     10122899.74
      3841609.37     10122803.51      3841577.11     10122550.31
      3841475.04     10122195.28      3841309.07     10122144.77
      3841240.18     10122085.15      3841026.64     10122046.08
      3840852.16     10121965.36      3840133.41      10121803.9
      3840013.62      10121803.9      3839667.27     10121637.23
      3839258.41     10121585.15      3839076.98      10121515.4

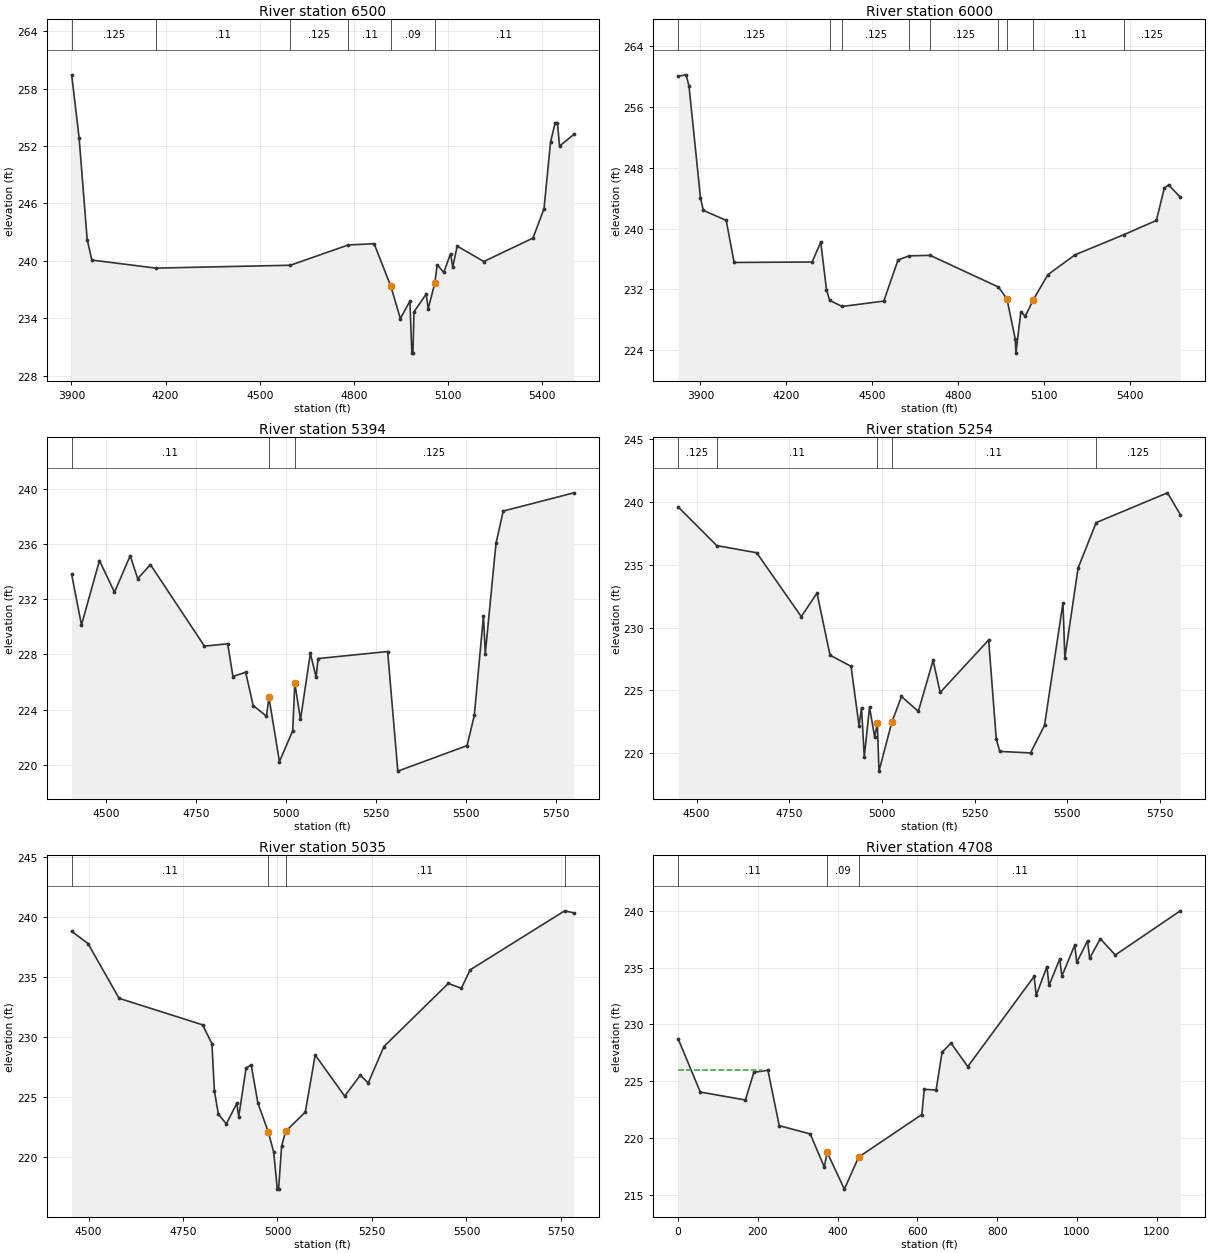
Type RM Length L Ch R = 1 ,6500    ,500,500,500
BEGIN DESCRIPTION:
Crystal Creek 043 13.0
END DESCRIPTION:
XS GIS Cut Line= 3
      3842561.36      10125367.9      3841476.78     10125547.81
      3841152.29     10125929.66
#Sta/Elev= 30
  3900.6  259.44  3924.4  252.84  3950.1  242.21    3965  240.07  4169.1  239.23
  4597.6  239.53  4782.1  241.65  4864.6  241.78  4917.8  237.34  4948.2  233.96
  4978.6  235.78  4984.8  230.34  4988.3  230.34  4991.6  234.66  5030.5  236.51
    5037     235  5057.9  237.65  5065.6  239.59  5086.4  238.78  5108.4  240.75
    5115  239.33  5129.3  241.53  5214.2  239.92  5370.9  242.37  5406.1  245.45
  5426.9  252.42  5441.2  254.38  5448.9   254.4  5455.5  251.99  5501.1  253.21
#Mann= 6 ,-1 , 0
  3900.6    .125       0  4169.1     .11       0  4597.6    .125       0
  4782.1     .11       0  4917.8     .09       0  5057.9     .11       0
Bank Sta=4917.8,5057.9
XS Rating Curve= 0 ,0
Exp/Cntr=0.3,0.1

Type RM Length L Ch R = 1 ,6000    ,606,606,606
BEGIN DESCRIPTION:
Crystal Creek 043 12.0
END DESCRIPTION:
XS GIS Cut Line= 3
      3842505.81     10125194.29      3841328.72     10125145.45
      3840837.08      10125446.9
#Sta/Elev= 30
  3821.9  260.07  3849.9  260.26  3859.9  258.78  3899.9  244.09  3909.9   242.4
    3990  241.07  4017.6  235.53  4290.3  235.59  4320.3  238.22  4340.3  231.96
  4351.3  230.53  4395.2  229.73  4540.5  230.44  4590.5  235.87  4629.2   236.4
  4702.4  236.47  4941.2  232.29  4970.8  230.74    5000  225.43  5002.3  223.58
  5019.5  229.03  5034.9  228.42  5062.1  230.57  5114.2  233.93    5209  236.54
  5380.8  239.21  5493.2  241.07  5520.4  245.29  5535.8  245.76  5576.7  244.13
#Mann= 9 ,-1 , 0
  3821.9    .125       0  4351.3     .11       0  4395.2    .125       0
  4629.2     .11       0  4702.4    .125       0  4941.2     .11       0
  4970.8     .09       0  5062.1     .11       0  5380.8    .125       0
#Block Obstruct= 2 ,-1
  4640.6  4330.3  236.34  4320.3    4000  238.22
Bank Sta=4970.8,5062.1
XS Rating Curve= 0 ,0
Exp/Cntr=0.3,0.1

Type RM Length L Ch R = 1 ,5394    ,140,140,140
BEGIN DESCRIPTION:
Crystal Creek 043 11.0
END DESCRIPTION:
XS GIS Cut Line= 4
      3841662.59     10125043.41      3841304.51     10124567.72
      3841182.25     10124352.41      3840632.36     10124395.78
#Sta/Elev= 30
  4404.6  233.79  4431.9  230.12  4481.8  234.79  4523.5  232.49  4567.2  235.14
    4588  233.48  4623.4  234.49  4773.4  228.59  4837.9  228.76  4852.5  226.39
  4887.9   226.7  4908.7  224.29  4945.7  223.52  4952.4  224.89  4981.6  220.23
  5018.5  222.47  5024.3  225.91  5040.1  223.28  5067.5  228.07  5083.4  226.35
  5089.1  227.69  5282.1   228.2  5310.4  219.54  5502.8  221.39  5522.8  223.58
  5548.2  230.78  5553.3  228.05    5583  236.03  5603.1  238.37  5799.2  239.69
#Mann= 3 , 0 , 0
  4404.6     .11       0  4952.4     .06       0  5024.3    .125       0
Bank Sta=4952.4,5024.3
XS Rating Curve= 0 ,0
Exp/Cntr=0.3,0.1

Type RM Length L Ch R = 1 ,5254    ,219,219,219
BEGIN DESCRIPTION:
Mapping XS 99e965c8
END DESCRIPTION:
XS GIS Cut Line= 4
       3841737.8     10124810.74      3841333.61     10124437.88
      3841272.53     10124309.01      3840613.46     10124379.06
#Sta/Elev= 30
  4450.1  239.61  4554.4  236.53  4662.2  235.96  4782.4  230.88  4824.9  232.75
  4860.1  227.81  4916.8  226.92  4938.3   222.2  4945.1  223.62  4952.5  219.72
  4966.7  223.67  4980.6  221.29  4987.7  222.42  4992.2  218.58 5026.87222.4745
  5052.9  224.52  5098.4  223.34  5138.3   227.4  5157.4  224.84  5288.1  229.02
  5308.7  221.13  5318.3  220.15  5401.2  220.03    5439  222.23  5488.8  231.98
  5493.8  227.58  5529.5  234.74  5578.3  238.36  5770.8  240.73  5805.4     239
#Mann= 5 ,-1 , 0
  4450.1    .125       0  4554.4     .11       0  4987.7     .09       0
 5026.87     .11       0  5578.3    .125       0
Bank Sta=4987.7,5026.87
XS Rating Curve= 0 ,0
Exp/Cntr=0.3,0.1

Type RM Length L Ch R = 1 ,5035    ,306,306,306
BEGIN DESCRIPTION:
Mapping XS 4cee7aad
END DESCRIPTION:
XS GIS Cut Line= 3
       3841899.3     10124383.67      3841243.01     10124184.01
      3840623.23     10124354.14
#Sta/Elev= 30
  4455.4  238.82  4498.7  237.79  4580.9  233.23  4801.8  231.02  4826.5  229.45
  4833.2  225.48  4843.7  223.57  4864.6  222.77  4892.2  224.47  4897.5  223.38
  4916.8   227.4  4930.3  227.69  4948.2   224.5 4975.72222.0906    4990  220.41
  4999.5  217.33    5003  217.33  5010.9  220.91  5021.4  222.14  5073.6  223.75
  5099.8  228.51  5177.8  225.08  5219.3  226.83  5240.1  226.17  5281.5  229.21
    5452  234.47  5486.5  234.07  5509.7   235.6  5759.8  240.52  5784.1  240.35
#Mann= 4 ,-1 , 0
  4455.4     .11       0 4975.72     .09       0  5021.4     .11       0
  5759.8    .125       0
Bank Sta=4975.72,5021.4
XS Rating Curve= 0 ,0
Exp/Cntr=0.3,0.1

Type RM Length L Ch R = 1 ,4708    ,166,166,166
XS GIS Cut Line= 4
      3841667.92     10123722.61      3841375.47     10124011.19
      3841162.94     10124156.79      3840598.85     10124336.97
#Sta/Elev= 30
       0  228.74    55.6  224.04   168.7  223.34   189.9  225.77   225.2  225.96
   253.5  221.08   331.3  220.35   366.6  217.43   373.7  218.74   416.8  215.49
   452.6  218.31   611.1  222.06   617.1  224.28   646.9  224.22   661.8  227.54
   684.3  228.35   726.3  226.28   892.6  234.22   897.9  232.56   924.8  235.09
     930  233.43     957  235.77   962.2  234.25   994.4  236.98   999.6  235.46
  1026.6  237.36  1031.8  235.82  1058.7  237.54  1096.2  236.11  1259.2     240
#Mann= 3 , 0 , 0
       0     .11       0   373.7     .09       0   452.6     .11       0
#XS Ineff= 2 , 0
       0   211.1  226.02               0
Permanent Ineff=
       F       F
Bank Sta=373.7,452.6
XS Rating Curve= 0 ,0
Exp/Cntr=0.3,0.1

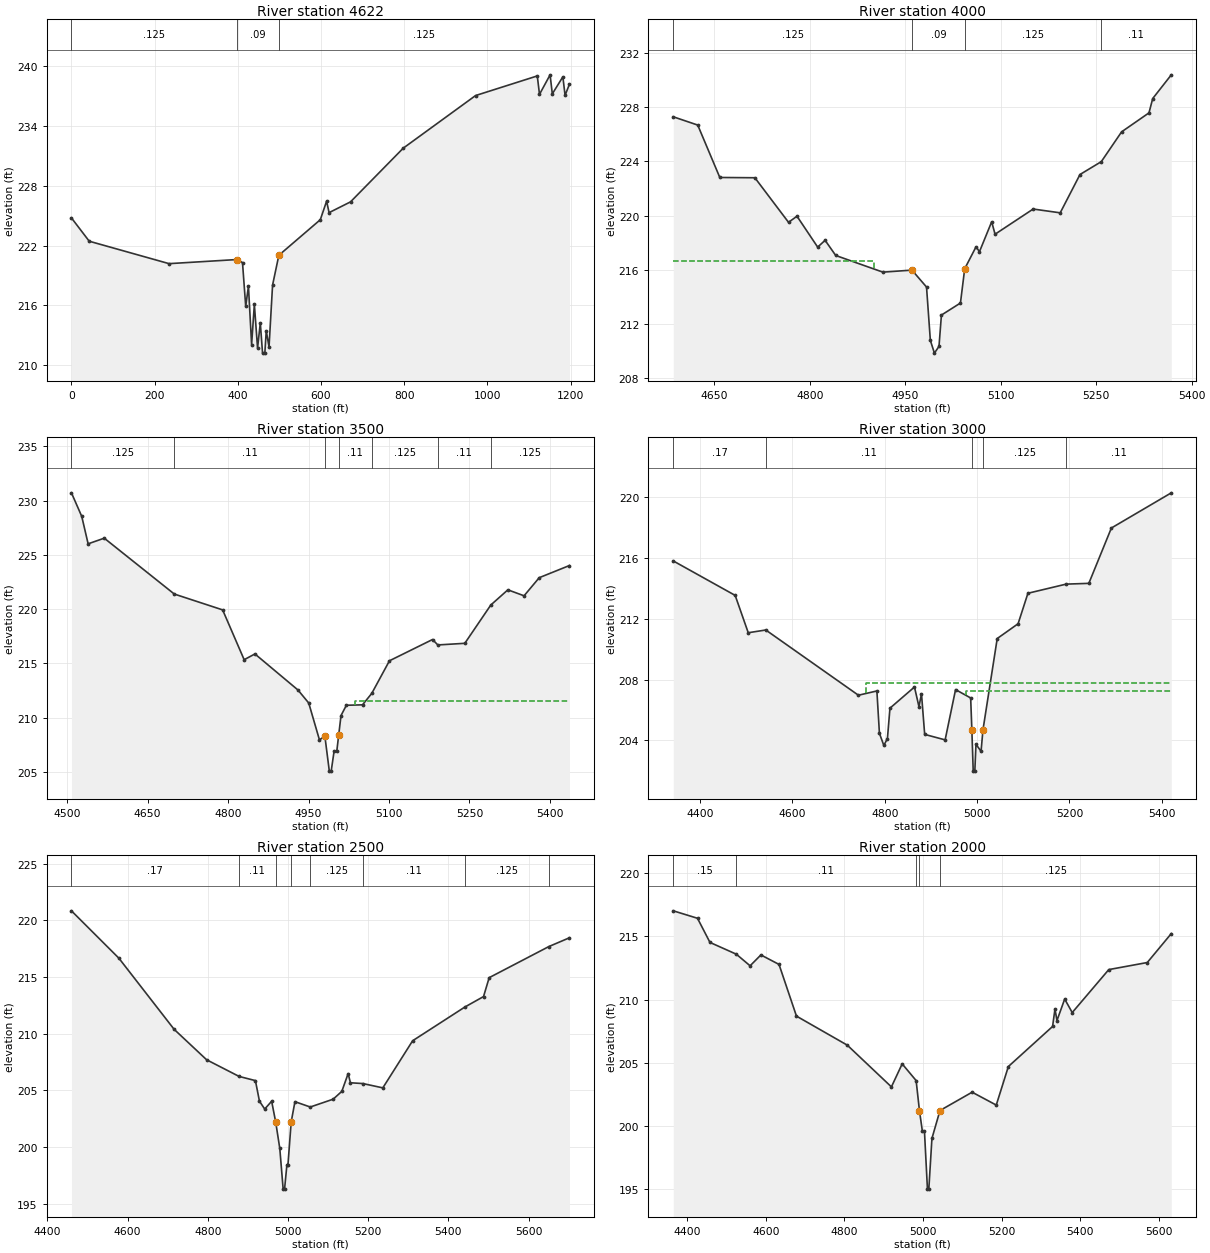
Type RM Length L Ch R = 1 ,4622    ,562,562,562
XS GIS Cut Line= 4
      3841617.98     10123590.42      3841268.51     10123893.25
      3841025.34      10124050.3      3840605.96     10124200.68
#Sta/Elev= 30
       0  224.79    42.8  222.45   234.7   220.2   397.1  220.61   411.3  220.31
     419  215.92   425.6  217.93   433.2  212.08   439.8  216.11   447.5  211.73
   454.1  214.25   459.5  211.22     465  211.22   468.4  213.46   475.1  211.85
   483.6  218.05   498.7  221.04   598.4  224.61   613.5  226.47   619.5  225.32
     671   226.4   797.8  231.79   971.7  237.07  1120.1  239.04  1125.4  237.19
  1150.9  239.15  1156.2  237.24  1181.6  238.95  1186.9  237.09  1197.4  238.21
#Mann= 3 , 0 , 0
       0    .125       0   397.1     .09       0   498.7    .125       0
Bank Sta=397.1,498.7
XS Rating Curve= 0 ,0
Exp/Cntr=0.3,0.1

Type RM Length L Ch R = 1 ,4000    ,500,500,500
BEGIN DESCRIPTION:
Crystal Creek 043 8.0
END DESCRIPTION:
XS GIS Cut Line= 3
      3841744.09     10123553.93      3841368.18     10123378.82
      3841025.08     10123245.74
#Sta/Elev= 30
  4585.3   227.3  4623.7  226.69  4658.4  222.82  4713.5   222.8  4766.4  219.51
  4779.7  219.96  4812.2  217.68  4823.9  218.18  4840.6  217.06  4914.7  215.83
  4960.4  215.98  4983.3  214.73  4989.3  210.79  4995.7  209.85  5002.9  210.35
  5006.7  212.66  5036.6  213.55  5043.3  216.08  5061.1   217.7  5066.5  217.34
  5085.7  219.55    5091  218.63  5150.9  220.49  5193.4  220.21  5224.5  223.04
    5258  223.99  5289.9  226.19  5332.9  227.59  5338.8  228.65    5368   230.4
#Mann= 4 ,-1 , 0
  4585.3    .125       0  4960.4     .09       0  5043.3    .125       0
    5258     .11       0
#XS Ineff= 2 , 0
       0  4901.1  216.62               0
Permanent Ineff=
       F       F
Bank Sta=4960.4,5043.3
XS Rating Curve= 0 ,0
Exp/Cntr=0.3,0.1

Type RM Length L Ch R = 1 ,3500    ,500,500,500
BEGIN DESCRIPTION:
Crystal Creek 043 7.0
END DESCRIPTION:
XS GIS Cut Line= 3
      3842078.87     10123097.83      3841588.29     10123059.16
      3841153.52      10123021.5
#Sta/Elev= 30
  4507.9  230.73  4527.1  228.56    4539  226.03  4569.1  226.55  4699.7   221.4
  4789.8  219.94  4829.9  215.35    4850  215.88  4930.2  212.56  4950.3  211.36
  4970.3  207.96  4980.4  208.31  4988.7  205.08  4992.2  205.08  4997.7  206.95
  5002.7  206.95 5006.13208.3791  5010.5   210.2  5020.5  211.15  5050.6  211.19
  5067.9  212.25  5100.8  215.25  5181.1  217.21    5191  216.71  5241.3  216.86
  5289.8  220.39  5321.6  221.79  5351.8  221.24  5380.1  222.91  5436.4  224.03
#Mann= 7 ,-1 , 0
  4507.9    .125       0  4699.7     .11       0  4980.4     .09       0
 5006.13     .11       0  5067.9    .125       0    5191     .11       0
  5289.8    .125       0
#XS Ineff= 2 , 0
       0                  5035.7       0   211.5
Permanent Ineff=
       F       F
Bank Sta=4980.4,5006.13
XS Rating Curve= 0 ,0
Exp/Cntr=0.3,0.1

Type RM Length L Ch R = 1 ,3000    ,500,500,500
BEGIN DESCRIPTION:
Crystal Creek 043 6.0
END DESCRIPTION:
XS GIS Cut Line= 3
      3842170.05     10122346.96      3841575.17     10122628.18
      3841214.79     10122844.85
#Sta/Elev= 30
    4342  215.78    4476  213.52  4504.3  211.07  4542.3  211.25  4742.9  206.97
  4782.9  207.25  4788.4  204.47  4797.9  203.68  4805.7  204.12  4811.2  206.12
  4864.3  207.51    4874  206.22  4879.5  207.06  4886.4   204.4  4930.7  204.04
  4953.3  207.34    4986  206.79 4988.57 204.705  4991.5  201.99    4995  201.99
  4997.5  203.75  5008.5  203.29  5012.6  204.69  5043.5  210.69  5088.7  211.66
    5110  213.66  5192.8  214.26  5241.9  214.31  5290.7  217.94  5420.5  220.25
#Mann= 5 ,-1 , 0
    4342     .17       0  4542.3     .11       0 4988.57     .09       0
  5012.6    .125       0  5192.8     .11       0
#XS Ineff= 4 ,-1
  4976.1  4953.3  207.28  4953.3  4864.3  207.34  4864.3  4760.2  207.51
  4760.2  4720.5  207.74
Permanent Ineff=
       F       F       F       F
Bank Sta=4988.57,5012.6
XS Rating Curve= 0 ,0
Exp/Cntr=0.3,0.1

Type RM Length L Ch R = 1 ,2500    ,500,500,500
BEGIN DESCRIPTION:
Crystal Creek 043 5.0
END DESCRIPTION:
XS GIS Cut Line= 3
      3841980.37     10122076.63      3841447.72     10122166.03
      3841097.57     10122774.58
#Sta/Elev= 30
  4459.9  220.84  4578.2  216.66    4716  210.38  4797.1  207.69  4878.1  206.22
  4918.8  205.85  4928.9  204.03    4942  203.34  4959.3  204.03  4969.5  202.17
  4979.6  199.86    4988  196.27  4991.5  196.27  4997.4  198.43    5000  198.43
 5008.06202.2094  5017.4  203.99  5055.6  203.52  5112.7  204.21  5134.3   204.9
  5150.1  206.47  5155.8  205.66    5187  205.59  5236.6  205.21    5311  209.37
  5441.4  212.35  5487.8  213.27  5501.9  214.94    5651  217.69  5702.1  218.46
#Mann= 8 ,-1 , 0
  4459.9     .17       0  4878.1     .11       0  4969.5     .09       0
 5008.06     .11       0  5055.6    .125       0    5187     .11       0
  5441.4    .125       0    5651     .11       0
#XS Ineff= 2 , 0
       0                  5150.1       0  206.47
Permanent Ineff=
       F       F
Bank Sta=4969.5,5008.06
XS Rating Curve= 0 ,0
Exp/Cntr=0.3,0.1

Type RM Length L Ch R = 1 ,2000    ,422,422,422
BEGIN DESCRIPTION:
Crystal Creek 043 4.0
END DESCRIPTION:
XS GIS Cut Line= 3
       3841300.7     10121477.68      3840984.66     10122028.91
      3840849.93     10122646.18
#Sta/Elev= 30
  4364.6  217.03  4426.2  216.44  4457.9  214.53  4524.9   213.6    4560  212.68
  4587.5  213.54  4633.6  212.79    4678   208.7  4807.4   206.4  4919.6   203.1
    4947  204.92  4982.5   203.6    4991  201.21  4998.4  199.59  5003.7  199.59
  5011.3  195.01  5014.8  195.01  5022.7  199.02  5043.2  201.23    5125  202.68
  5186.4  201.66  5217.2  204.71  5329.7  207.88  5335.8  209.26  5340.9  208.35
  5360.5  210.05  5379.7  208.98  5472.7  212.38  5570.7  212.94  5631.8  215.23
#Mann= 5 ,-1 , 0
  4364.6     .15       0  4524.9     .11       0  4982.5    .125       0
    4991     .09       0  5043.2    .125       0
#XS Ineff= 2 , 0
       0    4947  204.92    5125       0  202.68
Permanent Ineff=
       F       F
Bank Sta=4991,5043.2
XS Rating Curve= 0 ,0
Exp/Cntr=0.3,0.1

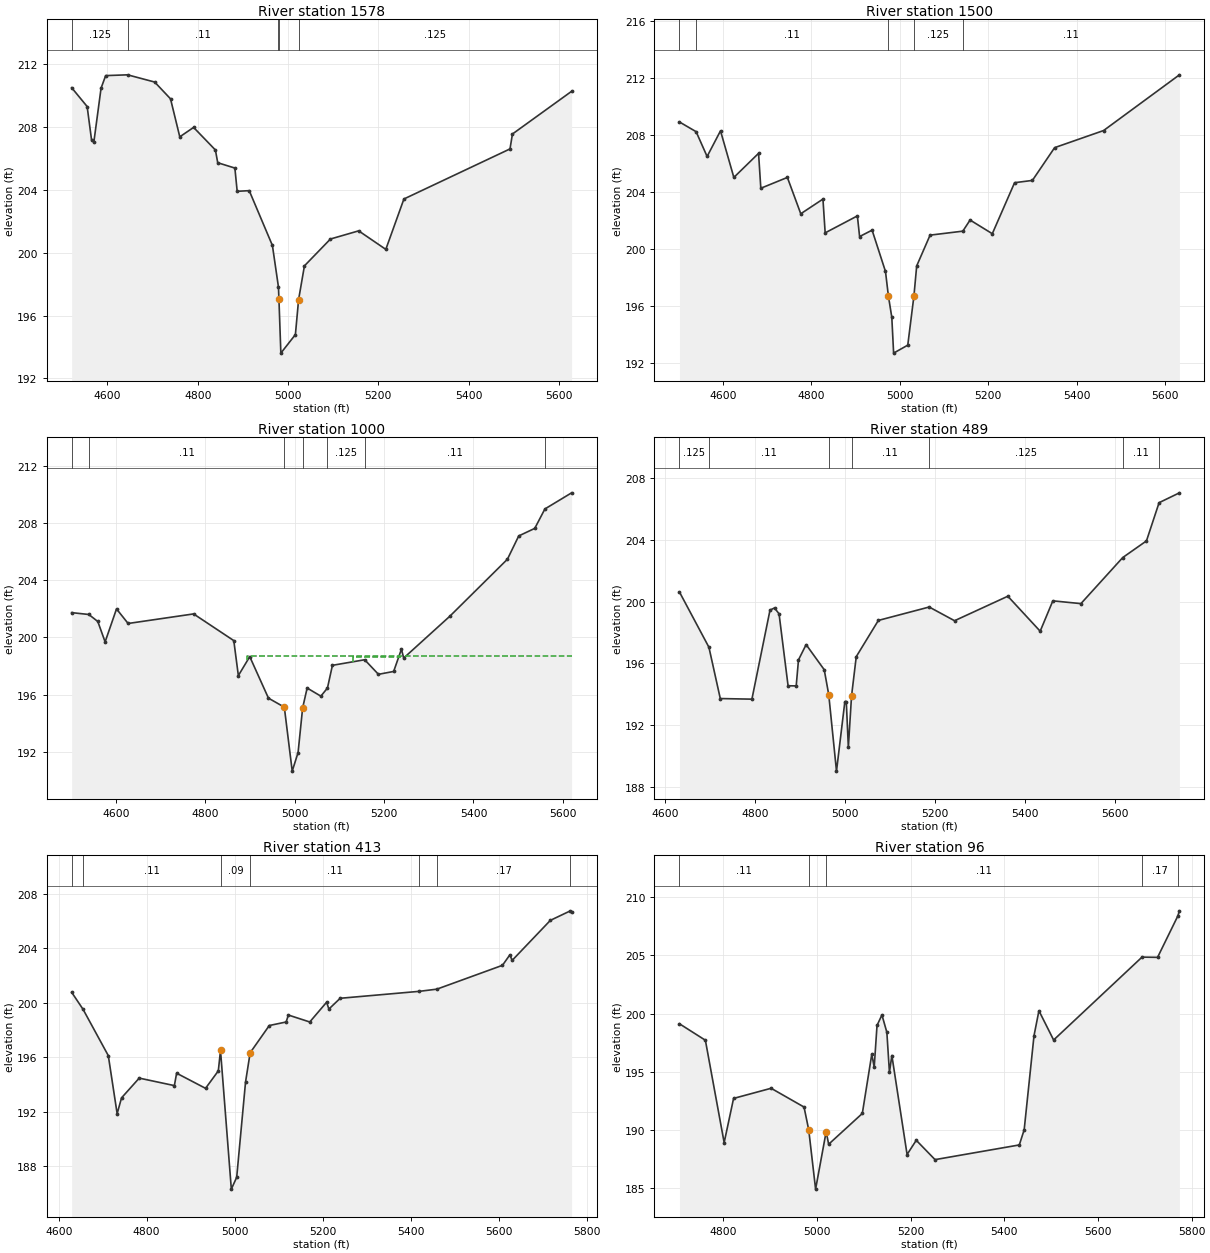
Type RM Length L Ch R = 1 ,1578    ,78,78,78
BEGIN DESCRIPTION:
Mapping XS e7350381
END DESCRIPTION:
XS GIS Cut Line= 3
      3840693.65      10121427.6      3840587.74     10121894.84
      3840555.92     10122521.94
#Sta/Elev= 30
  4520.9  210.52  4555.2  209.32    4565  207.18  4570.2  207.09    4586  210.49
  4596.2  211.29  4644.7  211.34  4704.7  210.88  4739.8  209.81  4760.3  207.39
  4790.9  207.99  4839.2  206.55  4844.3  205.74  4882.3   205.4  4887.4  203.92
  4914.1  203.96  4965.4  200.47  4978.8  197.82 4979.81197.0851  4984.1  193.61
  5016.3  194.79  5023.4  197.02  5036.3  199.17  5093.9  200.88  5156.4   201.4
  5216.5  200.22  5256.6  203.43  5491.5  206.62  5496.9  207.57  5627.9  210.29
#Mann= 5 ,-1 , 0
  4520.9    .125       0  4644.7     .11       0  4978.8     .12       0
 4979.81     .09       0  5023.4    .125       0
Bank Sta=4979.81,5023.4
XS Rating Curve= 0 ,0
Exp/Cntr=0.3,0.1

Type RM Length L Ch R = 1 ,1500    ,500,500,500
BEGIN DESCRIPTION:
Crystal Creek 043 3.0
END DESCRIPTION:
XS GIS Cut Line= 3
      3840576.75     10121389.13      3840510.32     10121883.18
      3840436.13     10122511.52
#Sta/Elev= 30
  4501.5   208.9  4539.1  208.22    4564  206.48  4594.3  208.28  4624.5  205.01
  4680.4   206.7  4685.5  204.25  4745.6  205.01  4775.9  202.46  4826.1  203.49
  4831.1  201.12    4904  202.31    4909  200.86  4937.3  201.31  4967.6  198.41
  4974.1196.7072  4981.9  195.19    4986  192.68    5018  193.24 5031.96196.6932
  5038.2   198.8  5068.5  200.96  5142.6  201.24    5159  202.02  5209.3  201.06
  5259.7  204.64    5300   204.8  5350.3   207.1  5461.1   208.3  5632.7  212.21
#Mann= 5 ,-1 , 0
  4501.5    .125       0  4539.1     .11       0  4974.1     .09       0
 5031.96    .125       0  5142.6     .11       0
Bank Sta=4974.1,5031.96
XS Rating Curve= 0 ,0
Exp/Cntr=0.3,0.1

Type RM Length L Ch R = 1 ,1000    ,511,511,511
BEGIN DESCRIPTION:
Crystal Creek 043 2.0
END DESCRIPTION:
XS GIS Cut Line= 3
      3840136.35     10121318.25       3840019.1      10121803.9
      3839900.08     10122412.06
#Sta/Elev= 30
  4500.4  201.74  4538.8  201.61  4558.9  201.12  4575.3  199.69  4600.8     202
  4626.8  200.98  4773.4  201.65  4863.4  199.78  4873.6  197.33  4899.1  198.66
    4941  195.75  4976.5  195.12  4994.2  190.64  5007.3  191.94  5017.5  195.06
  5027.6  196.46  5058.3  195.89  5073.1  196.46  5084.2  198.05  5156.4  198.44
  5187.2  197.42  5221.3  197.62  5238.7  199.18  5243.8  198.56  5346.8  201.48
    5476  205.48  5501.3  207.11  5537.2  207.64  5559.9     209  5619.7  210.13
#Mann= 7 ,-1 , 0
  4500.4    .125       0  4538.8     .11       0  4976.5     .09       0
  5017.5     .11       0  5073.1    .125       0  5156.4     .11       0
  5559.9    .125       0
#XS Ineff= 4 ,-1
  4893.9  4863.4  198.68  5084.2    5099  198.05  5129.6  5238.7  198.63
  5238.7  5272.2  199.18
Permanent Ineff=
       F       F       F       F
Bank Sta=4976.5,5017.5
XS Rating Curve= 0 ,0
Exp/Cntr=0.3,0.1

Type RM Length L Ch R = 1 ,489     ,76,76,76
BEGIN DESCRIPTION:
Mapping XS b09a260f
END DESCRIPTION:
XS GIS Cut Line= 3
      3839591.34     10121240.78      3839551.38     10121607.31
      3839760.63     10122321.49
#Sta/Elev= 30
  4631.3  200.63  4696.8  197.05  4722.1  193.72  4792.5  193.68  4832.8  199.46
  4842.8   199.6  4852.9  199.22    4873  194.55  4891.1  194.54  4896.2  196.23
  4913.2  197.22  4953.5  195.59  4963.5  193.98  4980.8  189.01  4999.4  193.52
  5002.6  193.52  5007.2  190.56  5014.3  193.89  5024.8  196.44    5074  198.79
  5187.2  199.66  5243.6  198.77  5362.2  200.36  5434.2  198.09  5462.4  200.06
  5524.9  199.88    5618  202.87  5670.8  203.95  5698.9  206.43  5744.2  207.07
#Mann= 7 ,-1 , 0
  4631.3    .125       0  4696.8     .11       0  4963.5     .09       0
  5014.3     .11       0  5187.2    .125       0    5618     .11       0
  5698.9    .125       0
#XS Ineff= 2 , 0
       0  4913.2  197.22               0
Permanent Ineff=
       F       F
Bank Sta=4963.5,5014.3
XS Rating Curve= 0 ,0
Exp/Cntr=0.3,0.1

Type RM Length L Ch R = 1 ,413     ,317,317,317
BEGIN DESCRIPTION:
Crystal Creek 043 1.0
END DESCRIPTION:
XS GIS Cut Line= 3
      3839438.83     10121228.22      3839476.21     10121596.82
      3839643.06     10122344.54
#Sta/Elev= 30
  4629.5  200.76  4655.4  199.51  4712.8  196.11  4732.9  191.85  4742.9  193.01
  4783.1  194.46    4863  193.91  4868.1  194.82  4933.9  193.71  4962.9  194.99
  4967.9  196.49  4992.5  186.31  5004.7  187.18  5024.8  194.17  5035.3  196.32
  5078.8  198.32  5117.1  198.58  5122.2  199.09  5170.8  198.58  5209.1  200.03
  5214.3  199.53    5240  200.32  5419.9  200.83  5459.8  200.99  5608.9  202.74
  5625.8  203.51  5630.9   203.1  5717.8  206.04  5763.4  206.74  5766.1  206.66
#Mann= 7 ,-1 , 0
  4629.5    .125       0  4655.4     .11       0  4967.9     .09       0
  5035.3     .11       0  5419.9    .125       0  5459.8     .17       0
  5763.4     .11       0
Bank Sta=4967.9,5035.3
XS Rating Curve= 0 ,0
Exp/Cntr=0.3,0.1

Type RM Length L Ch R = 1 ,96      ,0,0,0
BEGIN DESCRIPTION:
Crystal Creek 043 1.5
END DESCRIPTION:
XS GIS Cut Line= 3
      3839189.87     10121255.95      3839166.58     10121548.83
      3839397.76     10122287.49
#Sta/Elev= 30
  4706.2  199.12  4761.5  197.71  4801.6  188.93  4821.7  192.72  4901.9  193.59
  4972.2  191.98  4982.2  190.03  4996.9  184.94  5019.5  189.87  5024.8  188.79
  5096.7  191.43  5116.9  196.51  5122.1  195.41  5128.1  198.98  5138.6  199.88
  5149.1  198.39  5154.6  194.96  5159.8   196.4  5192.3  187.91  5211.9  189.13
    5252  187.47    5432  188.73  5442.4  190.03  5463.4   198.1  5473.9  200.24
  5505.3  197.73  5694.1  204.84  5727.3  204.82  5770.6  208.37    5774  208.81
#Mann= 5 ,-1 , 0
  4706.2     .11       0  4982.2     .09       0  5019.5     .11       0
  5694.1     .17       0  5770.6     .11       0
#Block Obstruct= 2 , 0
       0                  5138.6       0  199.88
Bank Sta=4982.2,5019.5
XS Rating Curve= 0 ,0
Exp/Cntr=0.3,0.1

Chan Stop Cuts=-1
Use User Specified Reach Order=0
Composite Channel Slope=5

--- Crystal Creek 043.g10 (geometry) ---

Geom Title=Existing Conditions
Program Version=4.10

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
River Reach=Crystal Creek 04,Reach-1

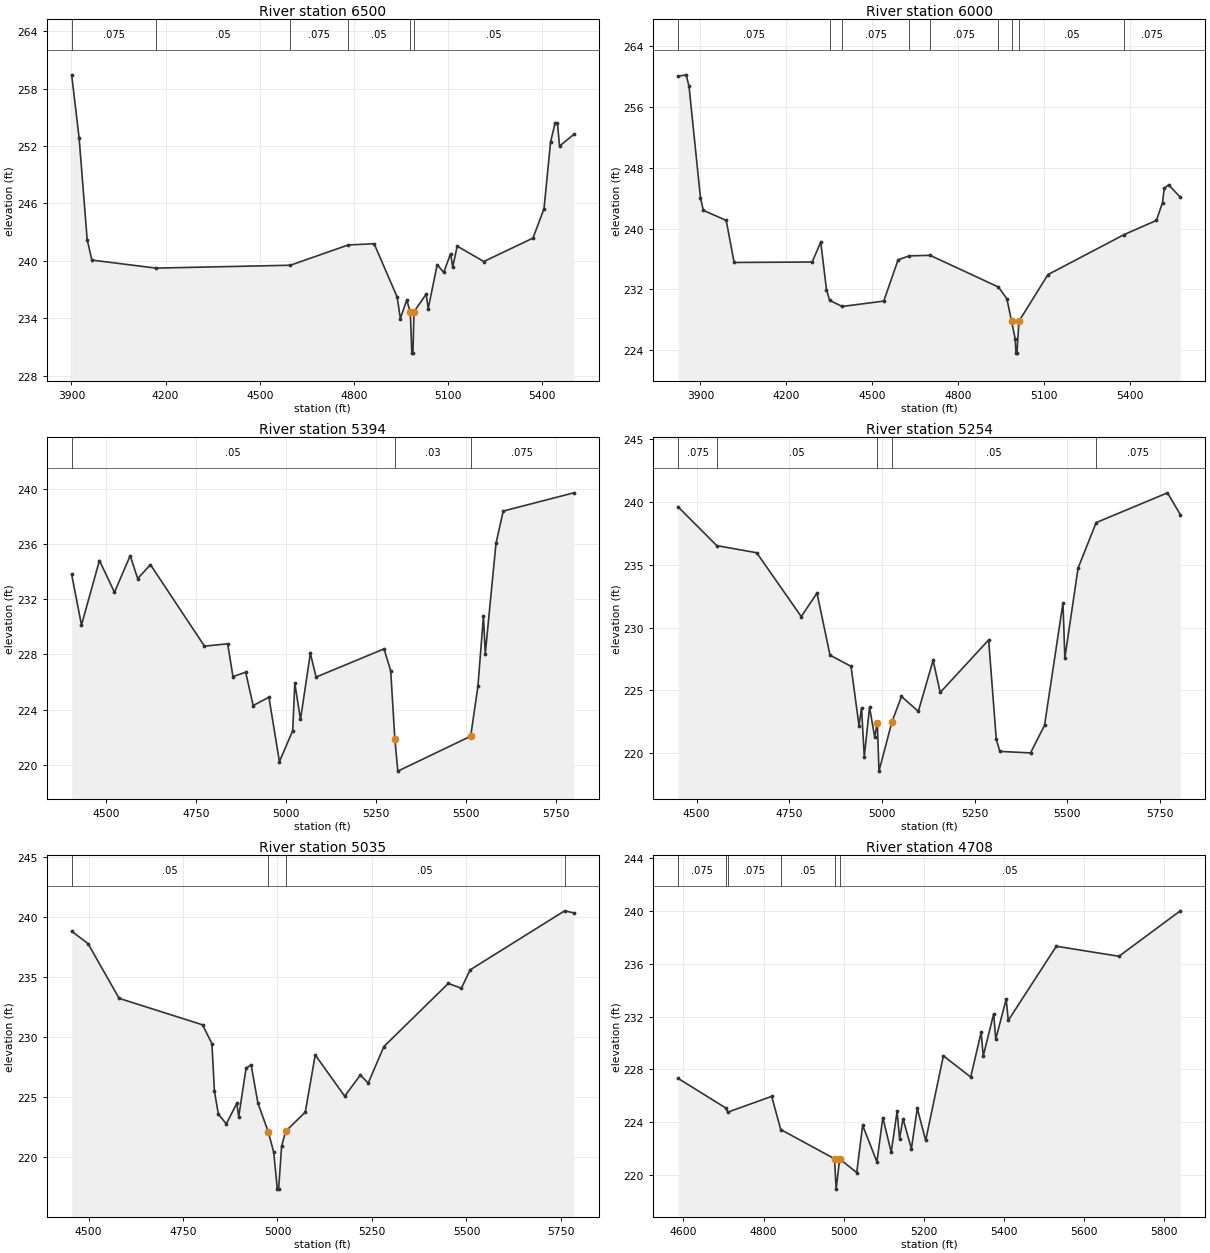
Type RM Length L Ch R = 1 ,6500    ,500,500,500
BEGIN DESCRIPTION:
Crystal Creek 043 13.0
END DESCRIPTION:
XS GIS Cut Line= 3
      3842561.36      10125367.9      3841476.78     10125547.81
      3841152.29     10125929.66
#Sta/Elev= 30
  3900.6  259.44  3924.4  252.84  3950.1  242.21    3965  240.07  4169.1  239.23
  4597.6  239.53  4782.1  241.65  4864.6  241.78  4938.1   236.2  4948.2  233.96
  4968.5  235.89 4979.97 234.633  4984.8  230.34  4988.3  230.34  4991.6  234.66
  5030.5  236.51    5037     235  5065.6  239.59  5086.4  238.78  5108.4  240.75
    5115  239.33  5129.3  241.53  5214.2  239.92  5370.9  242.37  5406.1  245.45
  5426.9  252.42  5441.2  254.38  5448.9   254.4  5455.5  251.99  5501.1  253.21
#Mann= 6 ,-1 , 0
  3900.6    .075       0  4169.1     .05       0  4597.6    .075       0
  4782.1     .05       0 4979.97     .07       0  4991.6     .05       0
Bank Sta=4979.97,4991.6
XS Rating Curve= 0 ,0
Exp/Cntr=0.3,0.1

Type RM Length L Ch R = 1 ,6000    ,606,606,606
BEGIN DESCRIPTION:
Crystal Creek 043 12.0
END DESCRIPTION:
XS GIS Cut Line= 3
      3842505.81     10125194.29      3841328.72     10125145.45
      3840837.08      10125446.9
#Sta/Elev= 30
  3821.9  260.07  3849.9  260.26  3859.9  258.78  3899.9  244.09  3909.9   242.4
    3990  241.07  4017.6  235.53  4290.3  235.59  4320.3  238.22  4340.3  231.96
  4351.3  230.53  4395.2  229.73  4540.5  230.44  4590.5  235.87  4629.2   236.4
  4702.4  236.47  4941.2  232.29  4970.8  230.74 4987.15 227.759    5000  225.43
  5002.3  223.58  5005.8  223.58  5012.8  227.77  5114.2  233.93  5380.8  239.21
  5493.2  241.07  5514.5  243.43  5520.4  245.29  5535.8  245.76  5576.7  244.13
#Mann= 9 ,-1 , 0
  3821.9    .075       0  4351.3     .05       0  4395.2    .075       0
  4629.2     .05       0  4702.4    .075       0  4941.2     .05       0
 4987.15     .07       0  5012.8     .05       0  5380.8    .075       0
Bank Sta=4987.15,5012.8
XS Rating Curve= 0 ,0
Exp/Cntr=0.3,0.1

Type RM Length L Ch R = 1 ,5394    ,140,140,140
BEGIN DESCRIPTION:
Crystal Creek 043 11.0
END DESCRIPTION:
XS GIS Cut Line= 4
      3841662.59     10125043.41      3841304.51     10124567.72
      3841182.25     10124352.41      3840632.36     10124395.78
#Sta/Elev= 30
  4404.6  233.79  4431.9  230.12  4481.8  234.79  4523.5  232.49  4567.2  235.14
    4588  233.48  4623.4  234.49  4773.4  228.59  4837.9  228.76  4852.5  226.39
  4887.9   226.7  4908.7  224.29  4952.4  224.89  4981.6  220.23  5018.5  222.47
  5024.3  225.91  5040.1  223.28  5067.5  228.07  5083.4  226.35  5272.1  228.39
  5290.6  226.81  5302.2  221.84  5310.4  219.54  5512.8  222.07  5532.9   225.7
  5548.2  230.78  5553.3  228.05    5583  236.03  5603.1  238.37  5799.2  239.69
#Mann= 3 , 0 , 0
  4404.6     .05       0  5302.2     .03       0  5512.8    .075       0
Bank Sta=5302.2,5512.8
XS Rating Curve= 0 ,0
Exp/Cntr=0.3,0.1

Type RM Length L Ch R = 1 ,5254    ,219,219,219
BEGIN DESCRIPTION:
Mapping XS 99e965c8
END DESCRIPTION:
XS GIS Cut Line= 4
       3841737.8     10124810.74      3841333.61     10124437.88
      3841272.53     10124309.01      3840613.46     10124379.06
#Sta/Elev= 30
  4450.1  239.61  4554.4  236.53  4662.2  235.96  4782.4  230.88  4824.9  232.75
  4860.1  227.81  4916.8  226.92  4938.3   222.2  4945.1  223.62  4952.5  219.72
  4966.7  223.67  4980.6  221.29  4987.7  222.42  4992.2  218.58 5026.87 222.475
  5052.9  224.52  5098.4  223.34  5138.3   227.4  5157.4  224.84  5288.1  229.02
  5308.7  221.13  5318.3  220.15  5401.2  220.03    5439  222.23  5488.8  231.98
  5493.8  227.58  5529.5  234.74  5578.3  238.36  5770.8  240.73  5805.4     239
#Mann= 5 ,-1 , 0
  4450.1    .075       0  4554.4     .05       0  4987.7     .07       0
 5026.87     .05       0  5578.3    .075       0
Bank Sta=4987.7,5026.87
XS Rating Curve= 0 ,0
Exp/Cntr=0.3,0.1

Type RM Length L Ch R = 1 ,5035    ,327,327,327
BEGIN DESCRIPTION:
Mapping XS 4cee7aad
END DESCRIPTION:
XS GIS Cut Line= 3
       3841899.3     10124383.67      3841243.01     10124184.01
      3840623.23     10124354.14
#Sta/Elev= 30
  4455.4  238.82  4498.7  237.79  4580.9  233.23  4801.8  231.02  4826.5  229.45
  4833.2  225.48  4843.7  223.57  4864.6  222.77  4892.2  224.47  4897.5  223.38
  4916.8   227.4  4930.3  227.69  4948.2   224.5 4975.72 222.091    4990  220.41
  4999.5  217.33    5003  217.33  5010.9  220.91  5021.4  222.14  5073.6  223.75
  5099.8  228.51  5177.8  225.08  5219.3  226.83  5240.1  226.17  5281.5  229.21
    5452  234.47  5486.5  234.07  5509.7   235.6  5759.8  240.52  5784.1  240.35
#Mann= 4 ,-1 , 0
  4455.4     .05       0 4975.72     .07       0  5021.4     .05       0
  5759.8    .075       0
Bank Sta=4975.72,5021.4
XS Rating Curve= 0 ,0
Exp/Cntr=0.3,0.1

Type RM Length L Ch R = 1 ,4708    ,86,86,86
BEGIN DESCRIPTION:
Crystal Creek 043 10.0
END DESCRIPTION:
XS GIS Cut Line= 4
      3841654.49     10123707.61      3841360.67     10123998.13
      3841153.19      10124146.7      3840600.15     10124336.53
#Sta/Elev= 30
  4586.8  227.32  4706.3  225.07  4710.3  224.76  4820.3  225.96  4842.8  223.45
  4977.1 221.236  4981.1  218.94  4989.9  221.23  5032.5  220.19  5047.3  223.77
  5082.9     221  5097.6  224.36  5118.5  221.73  5133.2  224.83  5139.4  222.76
    5148  224.26  5168.9     222  5183.6  225.06  5204.5  222.62  5248.7  229.03
  5316.9  227.42  5342.9   230.8  5348.2  229.02  5374.2   232.2  5379.4  230.29
  5405.4  233.31  5410.7  231.71  5530.5  237.32  5686.8  236.56  5839.9     240
#Mann= 6 ,-1 , 0
  4586.8    .075       0  4706.3     .05       0  4710.3    .075       0
  4842.8     .05       0  4977.1     .07       0  4989.9     .05       0
Bank Sta=4977.1,4989.9
XS Rating Curve= 0 ,0
Exp/Cntr=0.3,0.1

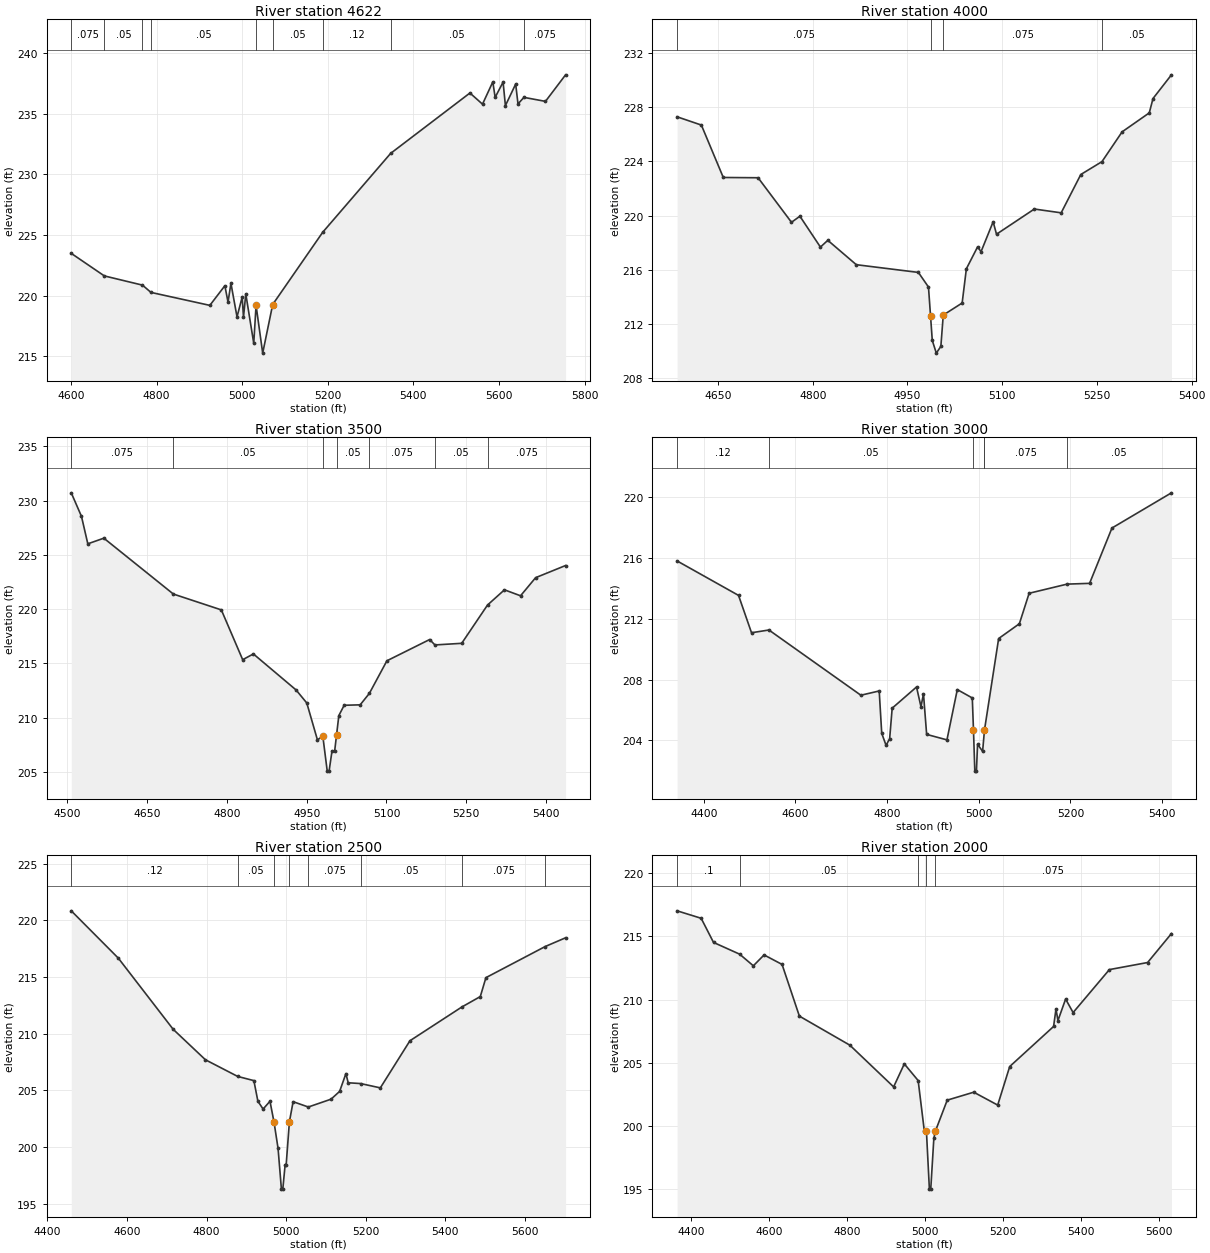
Type RM Length L Ch R = 1 ,4622    ,622,622,622
BEGIN DESCRIPTION:
Crystal Creek 043 9.0
END DESCRIPTION:
XS GIS Cut Line= 3
      3841595.96     10123661.85      3841303.79     10123934.17
       3840604.3      10124219.9
#Sta/Elev= 30
  4600.6  223.49  4677.9  221.63    4767  220.87  4786.8  220.27  4924.4   219.2
  4959.5  220.82  4966.9  219.47  4973.7  221.02  4987.9  218.25    5000  219.89
    5003  218.21  5008.4  220.15    5027  216.07  5032.4   219.2  5047.9  215.26
 5071.04 219.234  5071.2  219.27  5188.1  225.23  5346.9  231.74  5532.1  236.72
  5561.5   235.8  5585.6  237.64    5591  236.36  5609.6  237.62    5615  235.68
    5639  237.46  5644.4  235.82  5658.3  236.36  5708.6  236.03  5755.6  238.22
#Mann= 9 ,-1 , 0
  4600.6    .075       0  4677.9     .05       0    4767    .075       0
  4786.8     .05       0  5032.4     .07       0  5071.2     .05       0
  5188.1     .12       0  5346.9     .05       0  5658.3    .075       0
Bank Sta=5032.4,5071.04
XS Rating Curve= 0 ,0
Exp/Cntr=0.3,0.1

Type RM Length L Ch R = 1 ,4000    ,500,500,500
BEGIN DESCRIPTION:
Crystal Creek 043 8.0
END DESCRIPTION:
XS GIS Cut Line= 3
      3841744.09     10123553.93      3841368.18     10123378.82
      3841025.08     10123245.74
#Sta/Elev= 30
  4585.3   227.3  4623.7  226.69  4658.4  222.82  4713.5   222.8  4766.4  219.51
  4779.7  219.96  4812.2  217.68  4823.9  218.18    4869  216.38  4967.3  215.81
  4983.3  214.73 4986.58 212.576  4989.3  210.79  4995.7  209.85  5002.9  210.35
  5006.7  212.66  5036.6  213.55  5043.3  216.08  5061.1   217.7  5066.5  217.34
  5085.7  219.55    5091  218.63  5150.9  220.49  5193.4  220.21  5224.5  223.04
    5258  223.99  5289.9  226.19  5332.9  227.59  5338.8  228.65    5368   230.4
#Mann= 4 ,-1 , 0
  4585.3    .075       0 4986.58     .07       0  5006.7    .075       0
    5258     .05       0
Bank Sta=4986.58,5006.7
XS Rating Curve= 0 ,0
Exp/Cntr=0.3,0.1

Type RM Length L Ch R = 1 ,3500    ,500,500,500
BEGIN DESCRIPTION:
Crystal Creek 043 7.0
END DESCRIPTION:
XS GIS Cut Line= 3
      3842078.87     10123097.83      3841588.29     10123059.16
      3841153.52      10123021.5
#Sta/Elev= 30
  4507.9  230.73  4527.1  228.56    4539  226.03  4569.1  226.55  4699.7   221.4
  4789.8  219.94  4829.9  215.35    4850  215.88  4930.2  212.56  4950.3  211.36
  4970.3  207.96  4980.4  208.31  4988.7  205.08  4992.2  205.08  4997.7  206.95
  5002.7  206.95 5006.13 208.379  5010.5   210.2  5020.5  211.15  5050.6  211.19
  5067.9  212.25  5100.8  215.25  5181.1  217.21    5191  216.71  5241.3  216.86
  5289.8  220.39  5321.6  221.79  5351.8  221.24  5380.1  222.91  5436.4  224.03
#Mann= 7 ,-1 , 0
  4507.9    .075       0  4699.7     .05       0  4980.4     .07       0
 5006.13     .05       0  5067.9    .075       0    5191     .05       0
  5289.8    .075       0
Bank Sta=4980.4,5006.13
XS Rating Curve= 0 ,0
Exp/Cntr=0.3,0.1

Type RM Length L Ch R = 1 ,3000    ,500,500,500
BEGIN DESCRIPTION:
Crystal Creek 043 6.0
END DESCRIPTION:
XS GIS Cut Line= 3
      3842170.05     10122346.96      3841575.17     10122628.18
      3841214.79     10122844.85
#Sta/Elev= 30
    4342  215.78    4476  213.52  4504.3  211.07  4542.3  211.25  4742.9  206.97
  4782.9  207.25  4788.4  204.47  4797.9  203.68  4805.7  204.12  4811.2  206.12
  4864.3  207.51    4874  206.22  4879.5  207.06  4886.4   204.4  4930.7  204.04
  4953.3  207.34    4986  206.79 4988.57 204.705  4991.5  201.99    4995  201.99
  4997.5  203.75  5008.5  203.29  5012.6  204.69  5043.5  210.69  5088.7  211.66
    5110  213.66  5192.8  214.26  5241.9  214.31  5290.7  217.94  5420.5  220.25
#Mann= 6 ,-1 , 0
    4342     .12       0  4542.3     .05       0 4988.57     .07       0
  5012.6     .05       0  5012.6    .075       0  5192.8     .05       0
Bank Sta=4988.57,5012.6
XS Rating Curve= 0 ,0
Exp/Cntr=0.3,0.1

Type RM Length L Ch R = 1 ,2500    ,500,500,500
BEGIN DESCRIPTION:
Crystal Creek 043 5.0
END DESCRIPTION:
XS GIS Cut Line= 3
      3841980.37     10122076.63      3841447.72     10122166.03
      3841097.57     10122774.58
#Sta/Elev= 30
  4459.9  220.84  4578.2  216.66    4716  210.38  4797.1  207.69  4878.1  206.22
  4918.8  205.85  4928.9  204.03    4942  203.34  4959.3  204.03  4969.5  202.17
  4979.6  199.86    4988  196.27  4991.5  196.27  4997.4  198.43    5000  198.43
 5008.06 202.209  5017.4  203.99  5055.6  203.52  5112.7  204.21  5134.3   204.9
  5150.1  206.47  5155.8  205.66    5187  205.59  5236.6  205.21    5311  209.37
  5441.4  212.35  5487.8  213.27  5501.9  214.94    5651  217.69  5702.1  218.46
#Mann= 8 ,-1 , 0
  4459.9     .12       0  4878.1     .05       0  4969.5     .07       0
 5008.06     .05       0  5055.6    .075       0    5187     .05       0
  5441.4    .075       0    5651     .05       0
Bank Sta=4969.5,5008.06
XS Rating Curve= 0 ,0
Exp/Cntr=0.3,0.1

Type RM Length L Ch R = 1 ,2000    ,422,422,422
BEGIN DESCRIPTION:
Crystal Creek 043 4.0
END DESCRIPTION:
XS GIS Cut Line= 3
       3841300.7     10121477.68      3840984.66     10122028.91
      3840849.93     10122646.18
#Sta/Elev= 30
  4364.6  217.03  4426.2  216.44  4457.9  214.53  4524.9   213.6    4560  212.68
  4587.5  213.54  4633.6  212.79    4678   208.7  4807.4   206.4  4919.6   203.1
    4947  204.92  4982.5   203.6  4998.4  199.59  5003.7  199.59  5011.3  195.01
  5014.8  195.01  5022.7  199.02 5026.68 199.598    5057  202.05    5125  202.68
  5186.4  201.66  5217.2  204.71  5329.7  207.88  5335.8  209.26  5340.9  208.35
  5360.5  210.05  5379.7  208.98  5472.7  212.38  5570.7  212.94  5631.8  215.23
#Mann= 5 ,-1 , 0
  4364.6      .1       0  4524.9     .05       0  4982.5    .075       0
  5003.7     .07       0 5026.68    .075       0
Bank Sta=5003.7,5026.68
XS Rating Curve= 0 ,0
Exp/Cntr=0.3,0.1