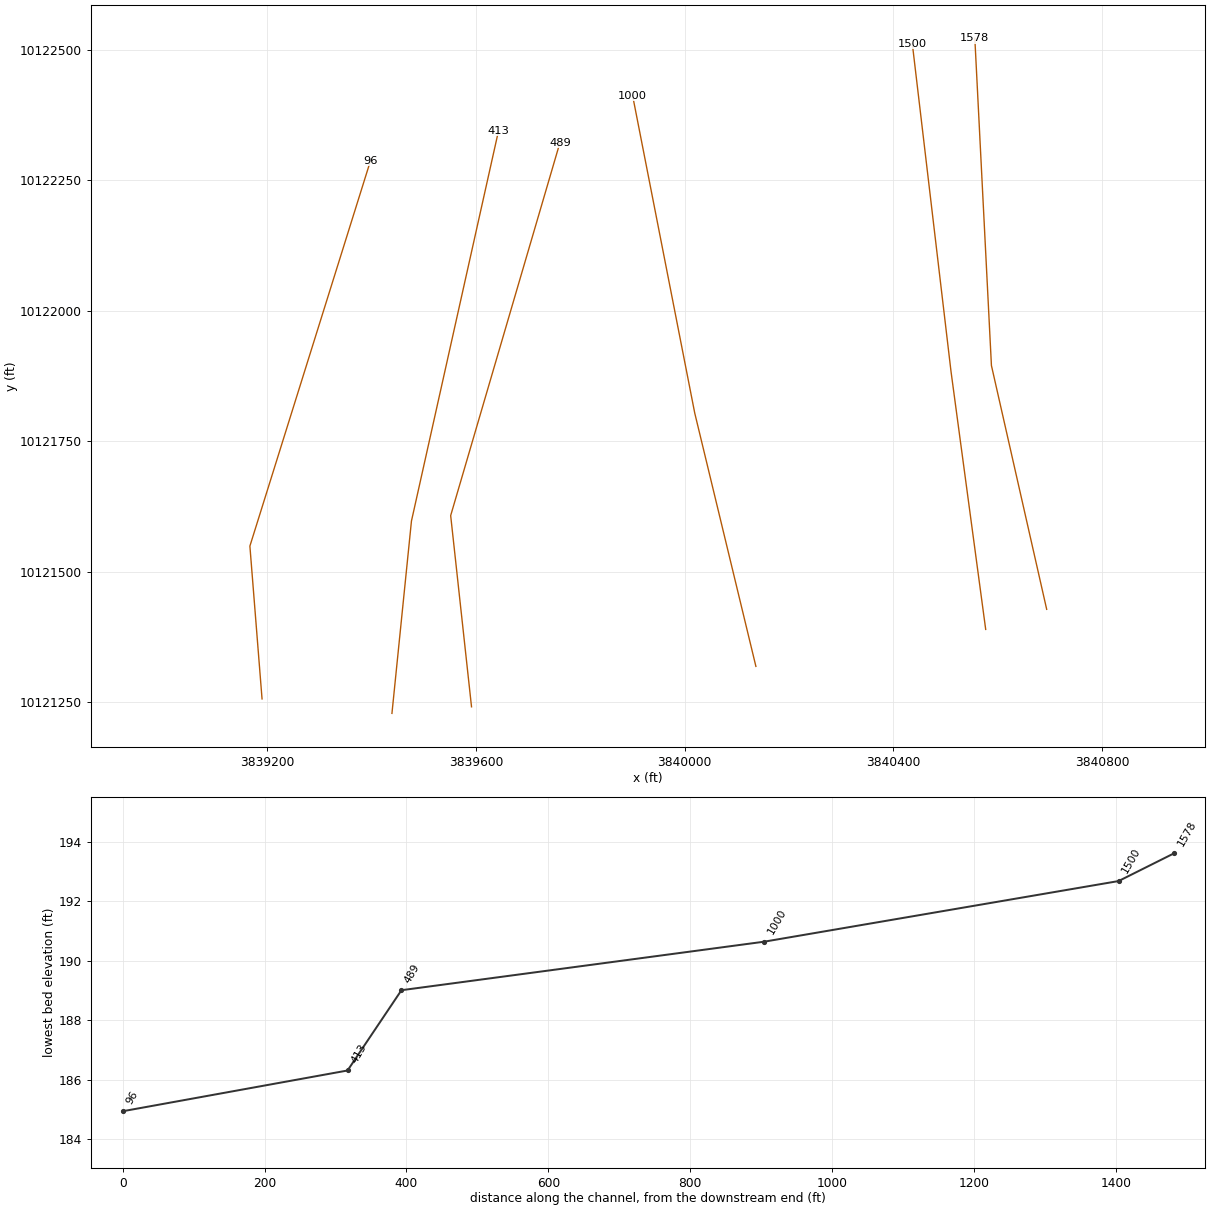
HEC-RAS study Crystal Creek 043.prj: Crystal Creek 043 Base Level Engineering

--- Crystal Creek 043.g10 (geometry) --- (continued)

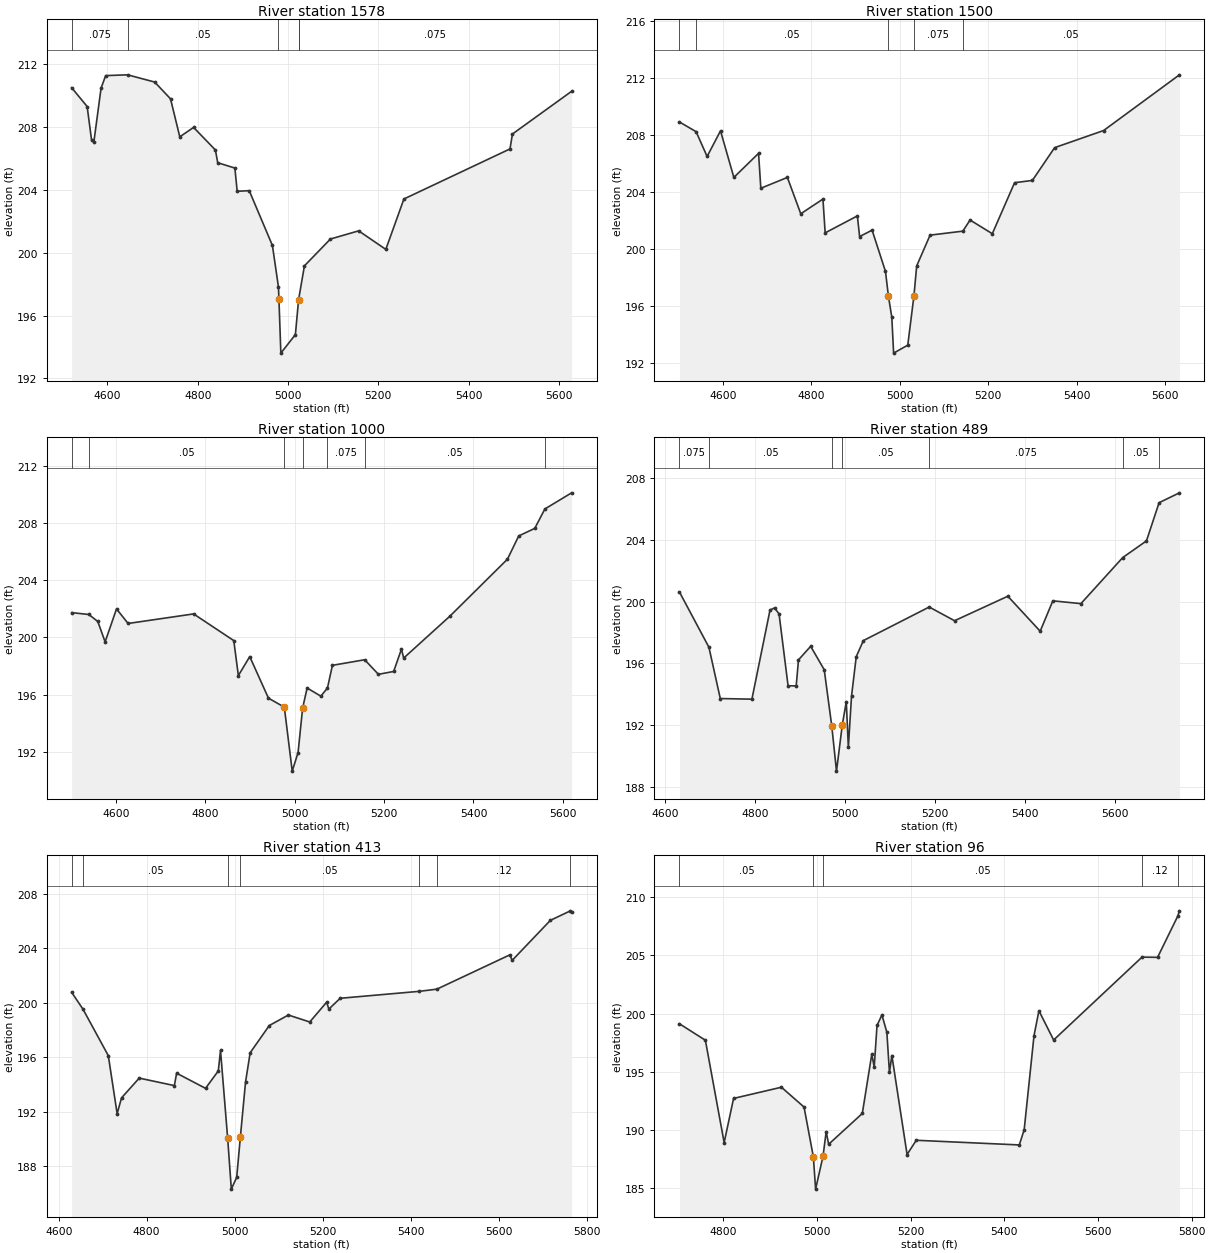
Type RM Length L Ch R = 1 ,1578    ,78,78,78
BEGIN DESCRIPTION:
Mapping XS e7350381
END DESCRIPTION:
XS GIS Cut Line= 3
      3840693.65      10121427.6      3840587.74     10121894.84
      3840555.92     10122521.94
#Sta/Elev= 30
  4520.9  210.52  4555.2  209.32    4565  207.18  4570.2  207.09    4586  210.49
  4596.2  211.29  4644.7  211.34  4704.7  210.88  4739.8  209.81  4760.3  207.39
  4790.9  207.99  4839.2  206.55  4844.3  205.74  4882.3   205.4  4887.4  203.92
  4914.1  203.96  4965.4  200.47  4978.8  197.82 4979.81 197.085  4984.1  193.61
  5016.3  194.79  5023.4  197.02  5036.3  199.17  5093.9  200.88  5156.4   201.4
  5216.5  200.22  5256.6  203.43  5491.5  206.62  5496.9  207.57  5627.9  210.29
#Mann= 5 ,-1 , 0
  4520.9    .075       0  4644.7     .05       0  4978.8     .07       0
  5023.4     .05       0  5023.4    .075       0
Bank Sta=4979.81,5023.4
XS Rating Curve= 0 ,0
Exp/Cntr=0.3,0.1

Type RM Length L Ch R = 1 ,1500    ,500,500,500
BEGIN DESCRIPTION:
Crystal Creek 043 3.0
END DESCRIPTION:
XS GIS Cut Line= 3
      3840576.75     10121389.13      3840510.32     10121883.18
      3840436.13     10122511.52
#Sta/Elev= 30
  4501.5   208.9  4539.1  208.22    4564  206.48  4594.3  208.28  4624.5  205.01
  4680.4   206.7  4685.5  204.25  4745.6  205.01  4775.9  202.46  4826.1  203.49
  4831.1  201.12    4904  202.31    4909  200.86  4937.3  201.31  4967.6  198.41
  4974.1 196.707  4981.9  195.19    4986  192.68    5018  193.24 5031.96 196.693
  5038.2   198.8  5068.5  200.96  5142.6  201.24    5159  202.02  5209.3  201.06
  5259.7  204.64    5300   204.8  5350.3   207.1  5461.1   208.3  5632.7  212.21
#Mann= 5 ,-1 , 0
  4501.5    .075       0  4539.1     .05       0  4974.1     .07       0
 5031.96    .075       0  5142.6     .05       0
Bank Sta=4974.1,5031.96
XS Rating Curve= 0 ,0
Exp/Cntr=0.3,0.1

Type RM Length L Ch R = 1 ,1000    ,511,511,511
BEGIN DESCRIPTION:
Crystal Creek 043 2.0
END DESCRIPTION:
XS GIS Cut Line= 3
      3840136.35     10121318.25       3840019.1      10121803.9
      3839900.08     10122412.06
#Sta/Elev= 30
  4500.4  201.74  4538.8  201.61  4558.9  201.12  4575.3  199.69  4600.8     202
  4626.8  200.98  4773.4  201.65  4863.4  199.78  4873.6  197.33  4899.1  198.66
    4941  195.75  4976.5  195.12  4994.2  190.64  5007.3  191.94  5017.5  195.06
  5027.6  196.46  5058.3  195.89  5073.1  196.46  5084.2  198.05  5156.4  198.44
  5187.2  197.42  5221.3  197.62  5238.7  199.18  5243.8  198.56  5346.8  201.48
    5476  205.48  5501.3  207.11  5537.2  207.64  5559.9     209  5619.7  210.13
#Mann= 7 ,-1 , 0
  4500.4    .075       0  4538.8     .05       0  4976.5     .07       0
  5017.5     .05       0  5073.1    .075       0  5156.4     .05       0
  5559.9    .075       0
Bank Sta=4976.5,5017.5
XS Rating Curve= 0 ,0
Exp/Cntr=0.3,0.1

Type RM Length L Ch R = 1 ,489     ,76,76,76
BEGIN DESCRIPTION:
Mapping XS b09a260f
END DESCRIPTION:
XS GIS Cut Line= 3
      3839591.34     10121240.78      3839551.38     10121607.31
      3839760.63     10122321.49
#Sta/Elev= 30
  4631.3  200.63  4696.8  197.05  4722.1  193.72  4792.5  193.68  4832.8  199.46
  4842.8   199.6  4852.9  199.22    4873  194.55  4891.1  194.54  4896.2  196.23
  4923.3  197.11  4953.5  195.59 4970.36 191.915  4980.8  189.01  4993.7  192.01
  5002.6  193.52  5007.2  190.56  5014.3  193.89  5024.8  196.44  5040.6  197.48
  5187.2  199.66  5243.6  198.77  5362.2  200.36  5434.2  198.09  5462.4  200.06
  5524.9  199.88    5618  202.87  5670.8  203.95  5698.9  206.43  5744.2  207.07
#Mann= 7 ,-1 , 0
  4631.3    .075       0  4696.8     .05       0 4970.36     .07       0
  4993.7     .05       0  5187.2    .075       0    5618     .05       0
  5698.9    .075       0
Bank Sta=4970.36,4993.7
XS Rating Curve= 0 ,0
Exp/Cntr=0.3,0.1

Type RM Length L Ch R = 1 ,413     ,317,317,317
BEGIN DESCRIPTION:
Crystal Creek 043 1.0
END DESCRIPTION:
XS GIS Cut Line= 3
      3839438.83     10121228.22      3839476.21     10121596.82
      3839643.06     10122344.54
#Sta/Elev= 30
  4629.5  200.76  4655.4  199.51  4712.8  196.11  4732.9  191.85  4742.9  193.01
  4783.1  194.46    4863  193.91  4868.1  194.82  4933.9  193.71  4962.9  194.99
  4967.9  196.49  4984.2  190.03  4992.5  186.31  5004.7  187.18  5013.1  190.15
  5024.8  194.17  5035.3  196.32  5078.8  198.32  5122.2  199.09  5170.8  198.58
  5209.1  200.03  5214.3  199.53    5240  200.32  5419.9  200.83  5459.8  200.99
  5625.8  203.51  5630.9   203.1  5717.8  206.04  5763.4  206.74  5766.1  206.66
#Mann= 7 ,-1 , 0
  4629.5    .075       0  4655.4     .05       0  4984.2     .07       0
  5013.1     .05       0  5419.9    .075       0  5459.8     .12       0
  5763.4     .05       0
Bank Sta=4984.2,5013.1
XS Rating Curve= 0 ,0
Exp/Cntr=0.3,0.1

Type RM Length L Ch R = 1 ,96      ,0,0,0
BEGIN DESCRIPTION:
Crystal Creek 043 1.5
END DESCRIPTION:
XS GIS Cut Line= 3
      3839189.87     10121255.95      3839166.58     10121548.83
      3839397.76     10122287.49
#Sta/Elev= 30
  4706.2  199.12  4761.5  197.71  4801.6  188.93  4821.7  192.72  4923.9  193.68
  4972.2  191.98  4992.2  187.69  4996.9  184.94  5012.8  187.77  5019.5  189.87
  5024.8  188.79  5096.7  191.43  5116.9  196.51  5122.1  195.41  5128.1  198.98
  5138.6  199.88  5149.1  198.39  5154.6  194.96  5159.8   196.4  5192.3  187.91
  5211.9  189.13    5432  188.73  5442.4  190.03  5463.4   198.1  5473.9  200.24
  5505.3  197.73  5694.1  204.84  5727.3  204.82  5770.6  208.37    5774  208.81
#Mann= 5 ,-1 , 0
  4706.2     .05       0  4992.2     .07       0  5012.8     .05       0
  5694.1     .12       0  5770.6     .05       0
Bank Sta=4992.2,5012.8
XS Rating Curve= 0 ,0
Exp/Cntr=0.3,0.1