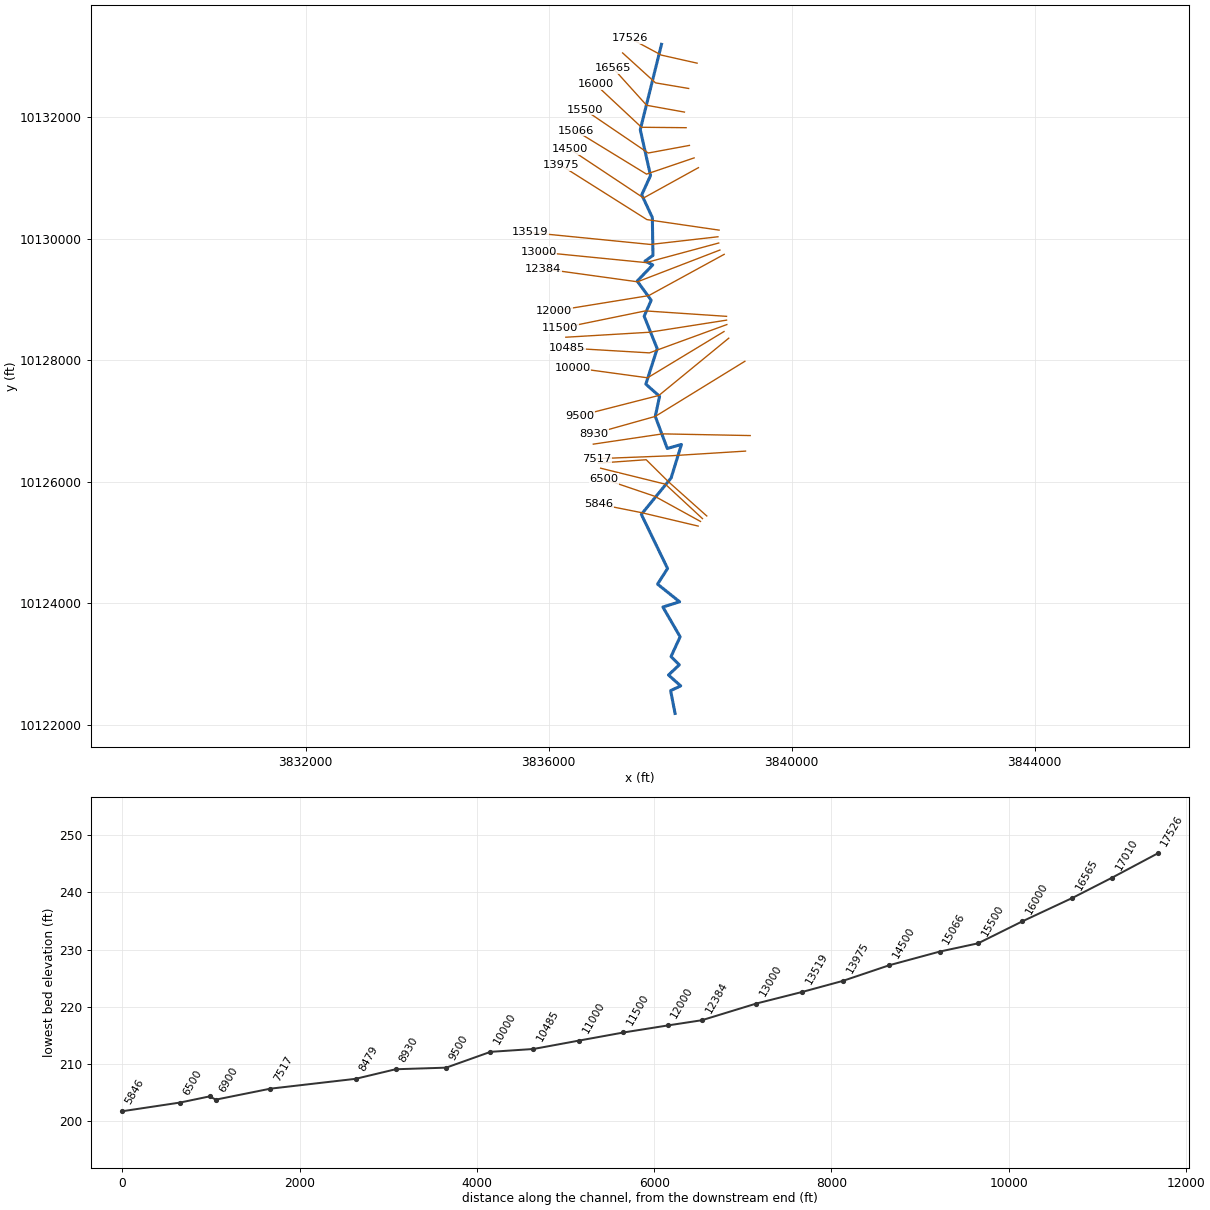
--- Crystal Creek 046.prj (project) ---

Proj Title=Crystal Creek 046 Base Level Engineering
Current Plan=p01
Default Exp/Contr=0.3,0.1
English Units
Geom File=g01
Flow File=f01
Flow File=f02
Plan File=p01
Y Axis Title=Elevation
X Axis Title(PF)=Main Channel Distance
X Axis Title(XS)=Station
BEGIN DESCRIPTION:
Crystal Creek 046
END DESCRIPTION:
DSS File=dss
DSS Export Rating Curves= 0
DSS Export Rating Curve Sorted= 0
DSS Export Volume Flow Curves= 0
DXF OffsetX= 0
DXF OffsetY= 0
DXF ScaleX= 1
DXF ScaleY= 10

--- Crystal Creek 046.p01 (plan) ---

Plan Title=Multiple Run
Program Version=4.10
Short Identifier=Multiple Run
Geom File=g01
Flow File=f01
Subcritical Flow
K Sum by GR= 0
Std Step Tol= 0.01
Critical Tol= 0.01
Num of Std Step Trials= 20
Max Error Tol= 0.3
Flow Tol Ratio= 0.001
Split Flow NTrial= 30
Split Flow Tol= 0.02
Split Flow Ratio= 0.02
Log Output Level= 0
Friction Slope Method= 1
Unsteady Friction Slope Method= 2
Unsteady Bridges Friction Slope Method= 1
Parabolic Critical Depth
Global Vel Dist= 1 , 1 , 1
Global Log Level= 0
CheckData=True
Encroach Param=-1 ,0,0, 0
BEGIN DESCRIPTION:
Multiple Run
END DESCRIPTION:
Computation Interval=1HOUR
Output Interval=1HOUR
Run HTab= 0
Run UNet= 0
Run PostProcess= 0
Run WQNet= 0
UNET Theta= 1
UNET Theta Warmup= 1
UNET ZTol= 0.02
UNET ZSATol= 0.05
UNET MxIter= 20
UNET MaxInSteps= 0
UNET DtIC= 0
UNET DtMin= 0
UNET MaxCRTS= 20
UNET WFStab= 2
UNET SFStab= 1
UNET WFX= 1
UNET SFX= 1
UNET DSS MLevel= 4
UNET DZMax Abort= 100
UNET Convert EG Bridges= 0
UNET Use Existing IB Tables=-1
UNET Froude Reduction=False
UNET Froude Limit= 1
UNET Froude Power= 10
UNET Time Slicing=0,0, 5
UNET Junction Losses=0
Instantaneous Interval=1HOUR
DSS File=dss
Write IC File= 0
Write IC File at Sim End=0
Echo Input=False
Echo Parameters=False
Echo Output=False
Write Detailed= 0
WQ AD Non Conservative
WQ ULTIMATE=-1
WQ Max Comp Step=1HOUR
WQ Output Interval=15MIN
WQ Output Selected Increments= 0
WQ Output face flow=0
WQ Output face velocity=0
WQ Output face area=0
WQ Output face dispersion=0
WQ Output cell volume=0
WQ Output cell surface area=0
WQ Output cell continuity=0
WQ Output cumulative cell continuity=0
WQ Output face conc=0
WQ Output face dconc_dx=0
WQ Output face courant=0
WQ Output face peclet=0
WQ Output face adv mass=0
WQ Output face disp mass=0
WQ Output cell mass=0
WQ Output cell source sink temp=0
WQ Output cell source sink nsm=0
WQ Output MaxMinRange=-1
WQ Daily Max Min Mean=-1
WQ Daily Range=0
WQ Daily Time=0
WQ Create Restart=0
WQ Fixed Restart=0
WQ System Summary=0
WQ Use Fixed Temperature=0
Sorting and Armoring Iterations= 10
XS Update Threshold= 0.02
Hydraulics Update Threshold= 0.02
Energy Slope Method= 1
Volume Change Method= 0
XS Weighting Method= 0
Number of US Weighted Cross Sections= 1
Number of DS Weighted Cross Sections= 1
Upstream XS Weight=0.25
Main XS Weight=0.5
Downstream XS Weight=0.25
Number of DS XS's Weighted with US Boundary= 1
Upstream Boundary Weight= 1
Weight of XSs Associated with US Boundary= 0
Number of US XS's Weighted with DS Boundary= 1
Downstream Boundary Weight= 0.5
Weight of XSs Associated with DS Boundary= 0.5
Sediment Output Level= 4
Mass or Volume Output= 0
Output Increment Type= 1
Profile and TS Output Increment= 10
XS Output Flag= 0
XS Output Increment= 10
Disregard all LS=0
Disregard all Conn=0
Disregard all Breaches=0
Disregard all Pumps=0

--- Crystal Creek 046.f01 (steady flow) ---

Flow Title=Multiple
Program Version=4.10
Number of Profiles= 7
Profile Names=10-year,25-year,50-year,1pct_min,100-year,1pct_plu,500-year
River Rch & RM=Crystal Creek 04,Reach-1         ,17526
     698     942    1270     563    1700    5134    3148
River Rch & RM=Crystal Creek 04,Reach-1         ,8930
     813    1093    1470     648    1958    5913    3593
River Rch & RM=Crystal Creek 04,Reach-1         ,140
    3368    4829    6777    3108    9386   28345   18633
Boundary for River Rch & Prof#=Crystal Creek 04,Reach-1         , 1
Up Type= 0
Dn Type= 3
Dn Slope=0.007
Boundary for River Rch & Prof#=Crystal Creek 04,Reach-1         , 2
Up Type= 0
Dn Type= 3
Dn Slope=0.007
Boundary for River Rch & Prof#=Crystal Creek 04,Reach-1         , 3
Up Type= 0
Dn Type= 3
Dn Slope=0.007
Boundary for River Rch & Prof#=Crystal Creek 04,Reach-1         , 4
Up Type= 0
Dn Type= 3
Dn Slope=0.007
Boundary for River Rch & Prof#=Crystal Creek 04,Reach-1         , 5
Up Type= 0
Dn Type= 3
Dn Slope=0.007
Boundary for River Rch & Prof#=Crystal Creek 04,Reach-1         , 6
Up Type= 0
Dn Type= 3
Dn Slope=0.007
Boundary for River Rch & Prof#=Crystal Creek 04,Reach-1         , 7
Up Type= 0
Dn Type= 3
Dn Slope=0.007
DSS Import GetInterval= 0
DSS Import GetPeak= 0
DSS Import FillOption= 0

--- Crystal Creek 046.f02 (steady flow) ---

Flow Title=Orig_BLE_Flow
Program Version=4.10
Number of Profiles= 7
Profile Names=10-year,25-year,50-year,1pct_min,100-year,1pct_plu,500-year
River Rch & RM=Crystal Creek 04,Reach-1         ,17526
     698     924    1104     433    1308    3949    1830
River Rch & RM=Crystal Creek 04,Reach-1         ,8930
     813    1072    1278     499    1506    4548    2089
River Rch & RM=Crystal Creek 04,Reach-1         ,140
    3368    4734    5893    2391    7220   21804   10833
Boundary for River Rch & Prof#=Crystal Creek 04,Reach-1         , 1
Up Type= 0
Dn Type= 3
Dn Slope=0.005
Boundary for River Rch & Prof#=Crystal Creek 04,Reach-1         , 2
Up Type= 0
Dn Type= 3
Dn Slope=0.005
Boundary for River Rch & Prof#=Crystal Creek 04,Reach-1         , 3
Up Type= 0
Dn Type= 3
Dn Slope=0.005
Boundary for River Rch & Prof#=Crystal Creek 04,Reach-1         , 4
Up Type= 0
Dn Type= 3
Dn Slope=0.005
Boundary for River Rch & Prof#=Crystal Creek 04,Reach-1         , 5
Up Type= 0
Dn Type= 3
Dn Slope=0.005
Boundary for River Rch & Prof#=Crystal Creek 04,Reach-1         , 6
Up Type= 0
Dn Type= 3
Dn Slope=0.005
Boundary for River Rch & Prof#=Crystal Creek 04,Reach-1         , 7
Up Type= 0
Dn Type= 3
Dn Slope=0.005
DSS Import GetInterval= 0
DSS Import GetPeak= 0
DSS Import FillOption= 0

--- Crystal Creek 046.g01 (geometry) ---

Geom Title=Existing Conditions
Program Version=4.10

River Reach=Crystal Creek 04,Reach-1
Reach XY= 30
      3837857.95     10133202.83      3837508.41     10131797.81
      3837677.02      10131042.1      3837532.54     10130725.05
      3837706.87     10130351.56      3837717.55     10129727.93
       3837586.6     10129633.43       3837713.5     10129571.33
       3837458.2     10129304.93      3837687.85     10128989.48
      3837572.43      10128726.3      3837787.07     10128192.43
      3837600.26     10127607.61      3837826.01     10127406.69
      3837755.35     10127076.52      3837952.45     10126548.67
        3838186.     10126614.82       3838015.9     10126062.67
      3837525.85     10125463.27       3837957.5     10124572.69
      3837792.86     10124314.69       3838156.3     10124024.17
       3837880.9     10123937.77       3838164.4     10123447.72
      3838014.55     10123122.37       3838150.9     10122986.02
       3837972.7     10122818.62      3838173.85     10122639.07
       3838007.8     10122560.77      3838080.98     10122186.83

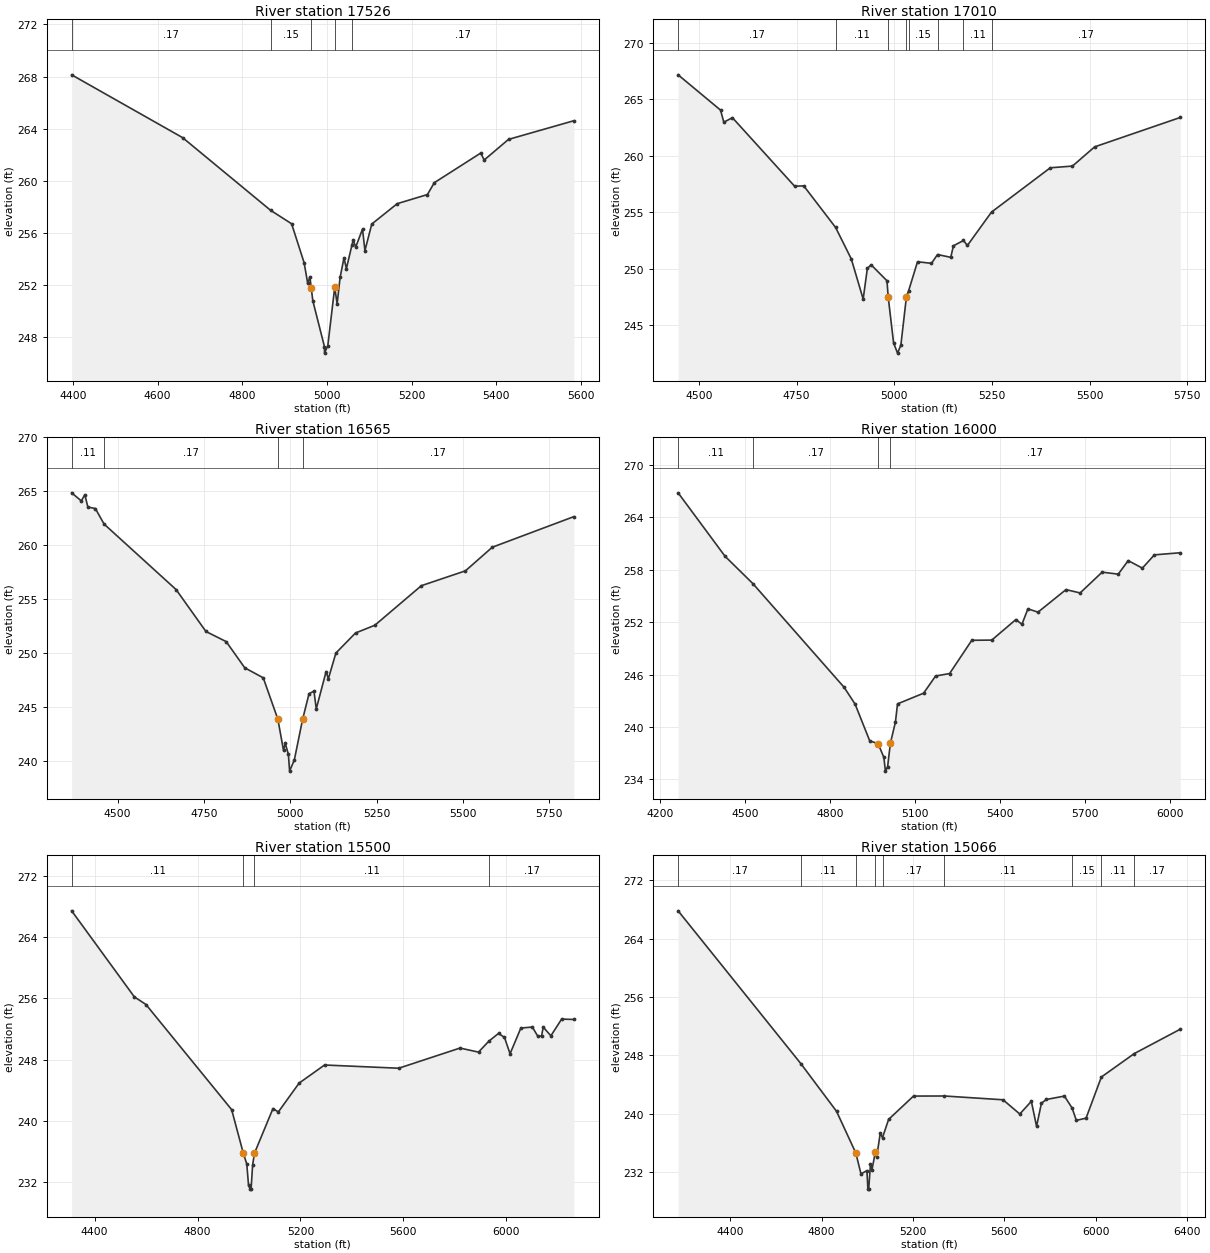
Type RM Length L Ch R = 1 ,17526   ,516,516,516
BEGIN DESCRIPTION:
Crystal Creek 046 33.0
END DESCRIPTION:
XS GIS Cut Line= 3
      3838443.79     10132892.66      3837855.35     10133025.29
      3837341.26     10133301.51
#Sta/Elev= 30
  4396.8  268.14  4659.2  263.32    4867  257.75  4916.6  256.72  4946.2  253.73
  4954.7  252.14  4959.8  252.66 4962.99251.8093  4966.7  250.82  4994.2   247.3
  4994.4   246.8  5002.2  247.38  5018.5  251.85  5024.2  250.58  5031.2   252.6
  5040.4   254.1  5046.1  253.28  5059.3   255.1  5062.3   255.5    5068  254.92
  5084.2  256.31  5089.9  254.66  5106.1   256.7  5166.2  258.26  5237.6  258.96
  5253.9  259.87  5363.5  262.14  5371.8  261.61  5429.2  263.19  5583.6  264.62
#Mann= 5 ,-1 , 0
  4396.8     .17       0    4867     .15       0 4962.99     .09       0
  5018.5     .15       0  5059.3     .17       0
#XS Ineff= 2 , 0
       0                  5040.4       0   254.1
Permanent Ineff=
       F       F
Bank Sta=4962.99,5018.5
XS Rating Curve= 0 ,0
Exp/Cntr=0.3,0.1

Type RM Length L Ch R = 1 ,17010   ,445,445,445
BEGIN DESCRIPTION:
Crystal Creek 046 32.0
END DESCRIPTION:
XS GIS Cut Line= 3
      3838304.94     10132475.99       3837759.4     10132568.33
      3837217.83     10133061.09
#Sta/Elev= 30
  4446.7  267.16  4555.3  264.04  4563.7  262.97  4585.7  263.37  4744.9  257.31
  4768.3  257.34  4849.9  253.66    4890  250.88  4920.4  247.33  4931.1  250.04
  4940.7  250.36  4981.3  248.95 4984.56247.4861  4998.3  243.44  5008.4  242.55
  5016.9  243.26  5031.1  247.52  5036.9  248.08  5059.5  250.63  5095.3  250.49
  5110.7  251.27  5144.6  251.02  5151.4  252.04  5177.1  252.51  5187.2  252.07
  5248.9  255.02  5399.4  258.94  5456.1  259.09  5512.9  260.79  5732.2  263.39
#Mann= 8 ,-1 , 0
  4446.7     .17       0  4849.9     .11       0 4984.56     .09       0
  5031.1     .17       0  5036.9     .15       0  5110.7     .17       0
  5177.1     .11       0  5248.9     .17       0
#XS Ineff= 2 , 0
       0  4940.7  250.36               0
Permanent Ineff=
       F       F
Bank Sta=4984.56,5031.1
XS Rating Curve= 0 ,0
Exp/Cntr=0.3,0.1

Type RM Length L Ch R = 1 ,16565   ,565,565,565
BEGIN DESCRIPTION:
Crystal Creek 046 31.0
END DESCRIPTION:
XS GIS Cut Line= 3
      3838235.43     10132087.11      3837612.66     10132199.33
      3837062.38     10132808.75
#Sta/Elev= 30
  4367.2  264.86  4395.2  264.11  4405.4  264.69  4414.1  263.54  4435.9   263.4
  4461.1  261.96  4669.6  255.88    4756  251.99  4814.7  251.05  4868.3  248.62
  4921.9  247.69  4964.2  243.85  4980.6  240.95  4985.6  241.61  4994.7  240.59
  4998.2  239.03  5011.9  240.07 5035.77243.8263  5054.5  246.22  5068.7  246.45
  5075.4  244.81  5103.8  248.26  5110.5  247.61  5132.2  249.99    5189  251.85
    5245  252.57  5379.6  256.24  5507.3  257.62    5585  259.81  5821.1  262.65
#Mann= 4 ,-1 , 0
  4367.2     .11       0  4461.1     .17       0  4964.2     .09       0
 5035.77     .17       0
#XS Ineff= 2 ,-1
  5054.5  5068.7  246.22  5068.7  5103.8  246.45
Permanent Ineff=
       F       F
Bank Sta=4964.2,5035.77
XS Rating Curve= 0 ,0
Exp/Cntr=0.3,0.1

Type RM Length L Ch R = 1 ,16000   ,500,500,500
BEGIN DESCRIPTION:
Crystal Creek 046 30.0
END DESCRIPTION:
XS GIS Cut Line= 3
      3838263.23     10131830.16      3837528.47     10131837.08
      3836771.56     10132544.17
#Sta/Elev= 30
  4265.2   266.8  4430.6  259.54  4529.3  256.39  4850.6  244.53  4889.2  242.61
  4940.6  238.42  4970.6  238.07  4990.6  236.51  4996.1  234.94  5003.8  235.44
 5013.57 238.121  5031.4  240.56  5038.8  242.64  5130.6  243.86  5173.1  245.83
  5222.4  246.11  5300.6  249.92    5371  249.94    5456  252.29  5477.4  251.75
  5498.5  253.52  5534.1  253.14  5632.8  255.72  5682.6  255.34  5760.3  257.72
    5817  257.49  5852.1  259.04    5902  258.18  5944.5   259.7  6035.8  259.94
#Mann= 4 ,-1 , 0
  4265.2     .11       0  4529.3     .17       0  4970.6     .09       0
 5013.57     .17       0
#XS Ineff= 2 , 0
       0                  5038.8       0  242.64
Permanent Ineff=
       F       F
Bank Sta=4970.6,5013.57
XS Rating Curve= 0 ,0
Exp/Cntr=0.3,0.1

Type RM Length L Ch R = 1 ,15500   ,434,434,434
BEGIN DESCRIPTION:
Crystal Creek 046 29.0
END DESCRIPTION:
XS GIS Cut Line= 3
      3838317.51     10131538.48      3837639.57      10131413.3
      3836594.75     10132123.42
#Sta/Elev= 30
  4310.6   267.4  4554.3  256.18  4599.6  255.18  4932.7  241.47 4978.05235.7841
  4991.6  234.37  4998.3  231.63  5004.8   231.1  5008.3   231.1  5014.2  234.22
  5021.5  235.79  5093.3   241.6  5114.3  241.17  5195.1  244.93  5293.9  247.29
  5582.4  246.87  5820.7   249.5  5892.6  248.97  5933.2  250.41  5970.5  251.41
  5993.5  250.89  6015.3  248.76  6057.3  252.11  6102.1  252.24  6123.1  251.04
    6138  251.08  6144.1  252.24    6174   251.1  6215.9  253.28  6263.3  253.23
#Mann= 4 ,-1 , 0
  4310.6     .11       0 4978.05     .09       0  5021.5     .11       0
  5933.2     .17       0
Bank Sta=4978.05,5021.5
XS Rating Curve= 0 ,0
Exp/Cntr=0.3,0.1

Type RM Length L Ch R = 1 ,15066   ,566,566,566
BEGIN DESCRIPTION:
Crystal Creek 046 28.0
END DESCRIPTION:
XS GIS Cut Line= 3
      3838394.58     10131332.77      3837610.64     10131065.96
      3836441.63     10131782.03
#Sta/Elev= 30
  4171.9  267.81  4709.5  246.85  4865.6  240.32  4950.1   234.6  4972.6  231.74
  4998.7  232.19  5002.9  229.65  5006.4  229.65  5014.2  233.05  5020.1  232.21
  5035.5  234.72  5041.4  234.05  5056.8  237.29  5066.9  236.72  5093.6  239.21
  5202.6  242.41  5338.3  242.42  5594.6   241.9  5668.1  239.95  5718.6  241.69
  5741.5  238.26  5762.8  241.43  5784.1  241.94  5863.5  242.41  5897.1  240.77
  5915.6  239.08  5958.2  239.38  6025.2  245.02  6169.5  248.24  6370.9  251.58
#Mann= 9 ,-1 , 0
  4171.9     .17       0  4709.5     .11       0  4950.1     .09       0
  5035.5     .11       0  5066.9     .17       0  5338.3     .11       0
  5897.1     .15       0  6025.2     .11       0  6169.5     .17       0
#XS Ineff= 2 , 0
       0                  5056.8       0  237.29
Permanent Ineff=
       F       F
Bank Sta=4950.1,5035.5
XS Rating Curve= 0 ,0
Exp/Cntr=0.3,0.1

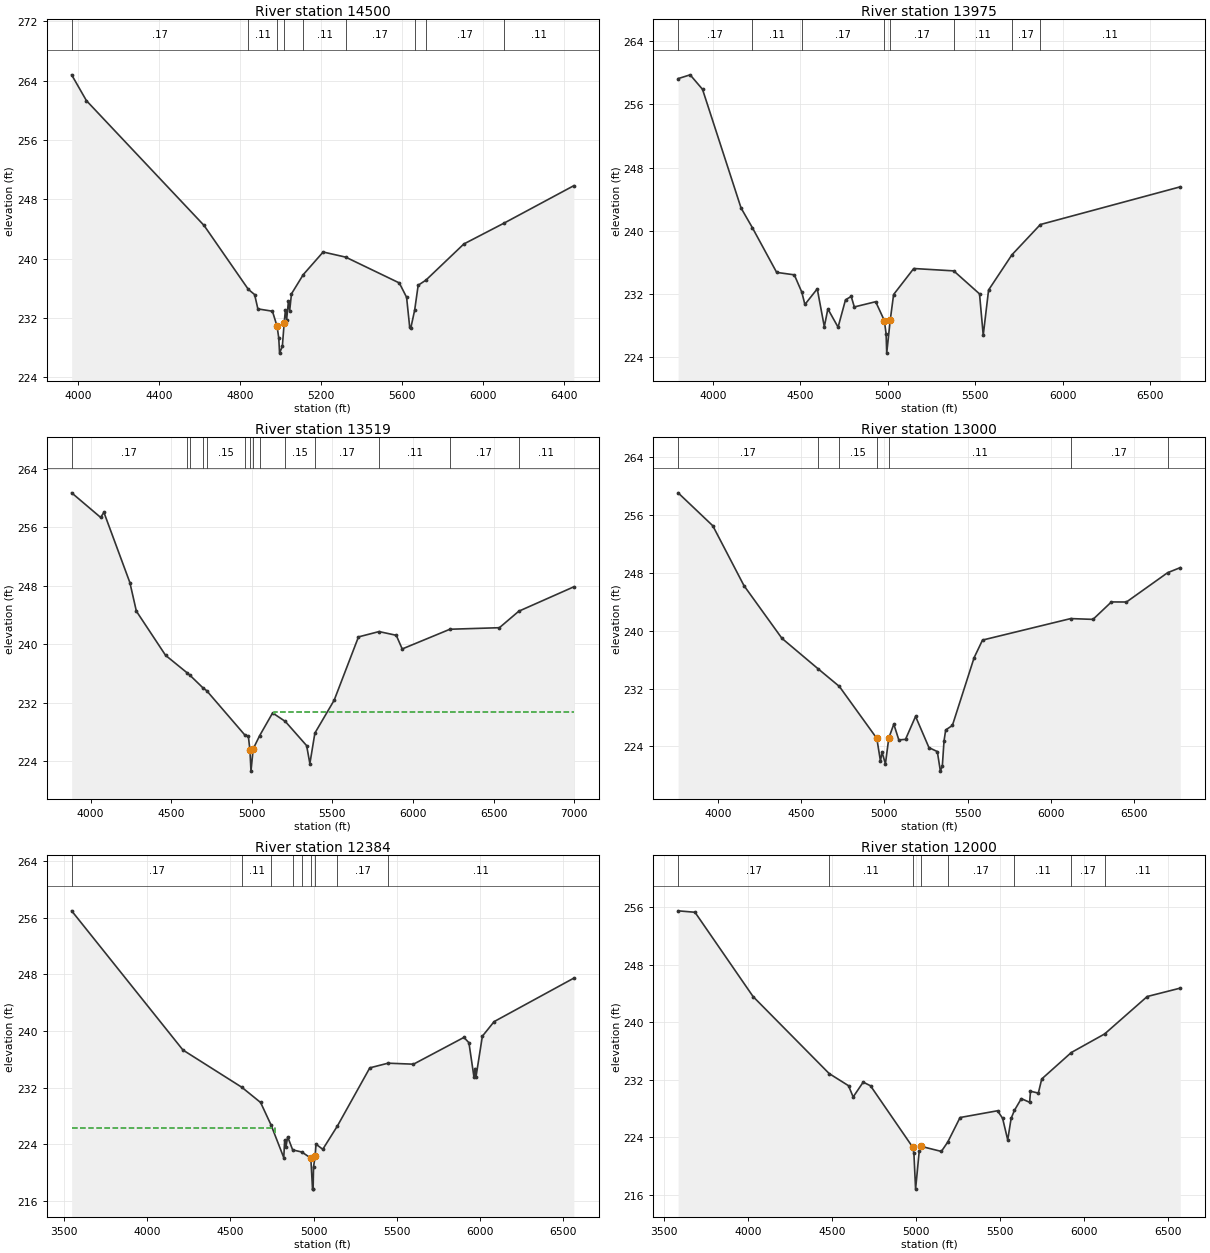
Type RM Length L Ch R = 1 ,14500   ,525,525,525
BEGIN DESCRIPTION:
Crystal Creek 046 27.0
END DESCRIPTION:
XS GIS Cut Line= 3
      3838465.33     10131172.09      3837562.52     10130672.96
      3836356.89     10131474.21
#Sta/Elev= 30
  3968.4  264.79  4041.3  261.31    4622  244.49  4840.5  235.88  4871.7  235.17
  4887.8  233.24  4959.6  232.93  4982.5   230.9  4990.9  229.31  4994.8  227.28
  5008.6  228.21  5017.6  231.34  5023.7  233.11  5029.7  231.79  5038.7  234.29
  5044.7     233  5053.6  235.27  5111.8  237.86    5210  240.91  5321.1  240.22
  5585.9  236.74  5621.9  234.81    5637  230.85    5643   230.7  5661.9  233.09
  5679.1  236.43    5717  237.11  5904.5  241.99  6102.9   244.8  6447.6  249.85
#Mann= 9 ,-1 , 0
  3968.4     .17       0  4840.5     .11       0  4982.5     .09       0
  5017.6     .17       0  5111.8     .11       0  5321.1     .17       0
  5661.9     .11       0    5717     .17       0  6102.9     .11       0
Bank Sta=4982.5,5017.6
XS Rating Curve= 0 ,0
Exp/Cntr=0.3,0.1

Type RM Length L Ch R = 1 ,13975   ,456,456,456
BEGIN DESCRIPTION:
Crystal Creek 046 26.0
END DESCRIPTION:
XS GIS Cut Line= 3
      3838805.94      10130143.6      3837618.29     10130316.69
      3836202.71      10131210.6
#Sta/Elev= 30
  3799.8  259.25  3868.6  259.73  3939.4   257.9  4160.1  242.89  4225.1  240.39
  4363.8  234.75  4464.8  234.44  4507.4  232.27  4525.5  230.69  4596.2  232.67
  4636.6  227.88  4656.9  230.13  4715.4  227.82  4757.9  231.28  4790.5  231.71
  4808.4  230.38  4930.6  231.04  4980.2  228.66  4990.3  226.96  4993.8  224.54
 5013.71228.6829  5033.2  231.95  5148.5  235.24  5377.3  234.94    5525  232.03
  5546.2   226.8  5576.8  232.52  5710.3  236.97  5873.2   240.8  6674.2  245.57
#Mann= 8 ,-1 , 0
  3799.8     .17       0  4225.1     .11       0  4507.4     .17       0
  4980.2     .09       0 5013.71     .17       0  5377.3     .11       0
  5710.3     .17       0  5873.2     .11       0
Bank Sta=4980.2,5013.71
XS Rating Curve= 0 ,0
Exp/Cntr=0.3,0.1

Type RM Length L Ch R = 1 ,13519   ,519,519,519
BEGIN DESCRIPTION:
Crystal Creek 046 25.0
END DESCRIPTION:
XS GIS Cut Line= 3
      3838786.69     10130034.31      3837676.39     10129907.74
      3835688.35     10130105.03
#Sta/Elev= 30
  3882.5  260.73  4062.5  257.36  4082.6  258.06  4243.7  248.44  4283.9  244.53
  4465.1  238.48  4597.8   236.1  4616.7  235.74  4696.7  234.03  4719.5  233.65
  4958.3  227.53  4978.4  227.44  4988.5  225.49    4995  222.62  5008.6  225.67
  5048.8  227.48  5129.2  230.59  5208.1  229.42  5340.2  226.11  5360.3  223.65
  5391.4  227.83    5511  232.33  5661.8     241  5789.5  241.73  5896.2  241.22
  5933.1  239.35  6229.2  242.05    6536  242.26  6656.4  244.52  6997.8  247.86
#Mann= 14 ,-1 , 0
  3882.5     .17       0  4597.8     .11       0  4616.7     .17       0
  4696.7     .11       0  4719.5     .15       0  4958.3     .12       0
  4988.5     .09       0  5008.6     .12       0  5048.8     .11       0
  5208.1     .15       0  5391.4     .17       0  5789.5     .11       0
  6229.2     .17       0  6656.4     .11       0
#XS Ineff= 2 , 0
       0                  5139.2       0   230.7
Permanent Ineff=
       F       T
Bank Sta=4988.5,5008.6
XS Rating Curve= 0 ,0
Exp/Cntr=0.3,0.1

Type RM Length L Ch R = 1 ,13000   ,616,616,616
BEGIN DESCRIPTION:
Crystal Creek 046 24.0
END DESCRIPTION:
XS GIS Cut Line= 3
      3838799.58     10129931.47      3837604.14     10129608.86
      3835836.26     10129783.62
#Sta/Elev= 30
  3761.8  259.03    3970  254.48  4157.2  246.21  4385.1  238.93  4603.9  234.69
  4729.7  232.29  4954.7  225.11  4976.5  221.97  4985.8  223.21  5006.3   221.6
  5026.4  225.15  5056.6  227.08  5086.7   224.9  5126.9  224.98  5187.2  228.15
  5267.6  223.84  5317.8  223.29  5336.2  220.59    5348  221.32    5358  224.74
  5368.1  226.28  5408.3   226.9  5538.9  236.27  5589.1  238.69  6118.5  241.66
  6252.4  241.55  6362.9  243.96  6453.3  243.95  6700.4     248  6776.5   248.7
#Mann= 7 ,-1 , 0
  3761.8     .17       0  4603.9     .11       0  4729.7     .15       0
  4954.7     .09       0  5026.4     .11       0  6118.5     .17       0
  6700.4     .11       0
Bank Sta=4954.7,5026.4
XS Rating Curve= 0 ,0
Exp/Cntr=0.3,0.1

Type RM Length L Ch R = 1 ,12384   ,384,384,384
BEGIN DESCRIPTION:
Crystal Creek 046 23.0
END DESCRIPTION:
XS GIS Cut Line= 3
      3838818.87     10129815.77      3837462.46     10129292.92
      3835913.41     10129507.21
#Sta/Elev= 30
  3546.3  256.96    4215  237.31  4568.8  232.05  4681.7   229.9  4744.9   226.7
  4820.9  222.11  4826.3  224.61  4833.5  223.56  4844.2  225.06  4874.3  223.21
    4929  222.91  4983.5  222.05  4993.7  217.67  4997.2  217.67  4999.8  220.83
 5009.34222.2928  5014.7  224.02  5055.1  223.29  5143.3  226.59  5337.8  234.79
  5447.3  235.45  5600.3  235.31  5903.4  239.09  5933.4  238.34  5963.7  233.49
  5970.2  234.69  5975.3  233.44  6014.2  239.26  6084.8  241.32  6563.8  247.46
#Mann= 9 ,-1 , 0
  3546.3     .17       0  4568.8     .11       0  4744.9     .15       0
  4874.3     .11       0    4929     .15       0  4983.5     .09       0
 5009.34     .15       0  5143.3     .17       0  5447.3     .11       0
#XS Ineff= 2 , 0
       0  4766.3   226.3               0
Permanent Ineff=
       F       F
Bank Sta=4983.5,5009.34
XS Rating Curve= 0 ,0
Exp/Cntr=0.3,0.1

Type RM Length L Ch R = 1 ,12000   ,500,500,500
BEGIN DESCRIPTION:
Crystal Creek 046 22.0
END DESCRIPTION:
XS GIS Cut Line= 3
      3838889.53     10129745.04       3837646.5       10129065.
      3836093.41       10128813.
#Sta/Elev= 30
  3583.1  255.51  3683.5  255.31  4029.6  243.57  4482.6  232.85  4597.8  231.16
  4625.4  229.59  4685.1  231.66  4728.7  231.15  4979.1  222.63  4987.1  221.77
  4997.1  216.76  5018.9  222.08    5029  222.72  5150.6  222.01  5188.5  223.31
    5262  226.73  5484.9  227.67  5515.3  226.62  5545.7  223.61    5566  226.61
  5585.8  227.73  5626.7  229.36  5676.2  228.85  5681.3  230.39    5728  230.13
  5748.3   232.1  5924.3  235.78    6123  238.37  6376.4  243.58  6573.4  244.75
#Mann= 8 ,-1 , 0
  3583.1     .17       0  4482.6     .11       0  4979.1     .09       0
    5029     .15       0  5188.5     .17       0  5585.8     .11       0
  5924.3     .17       0    6123     .11       0
#XS Ineff= 2 , 0
       0                  5484.9       0  227.67
Permanent Ineff=
       F       T
Bank Sta=4979.1,5029
XS Rating Curve= 0 ,0
Exp/Cntr=0.3,0.1

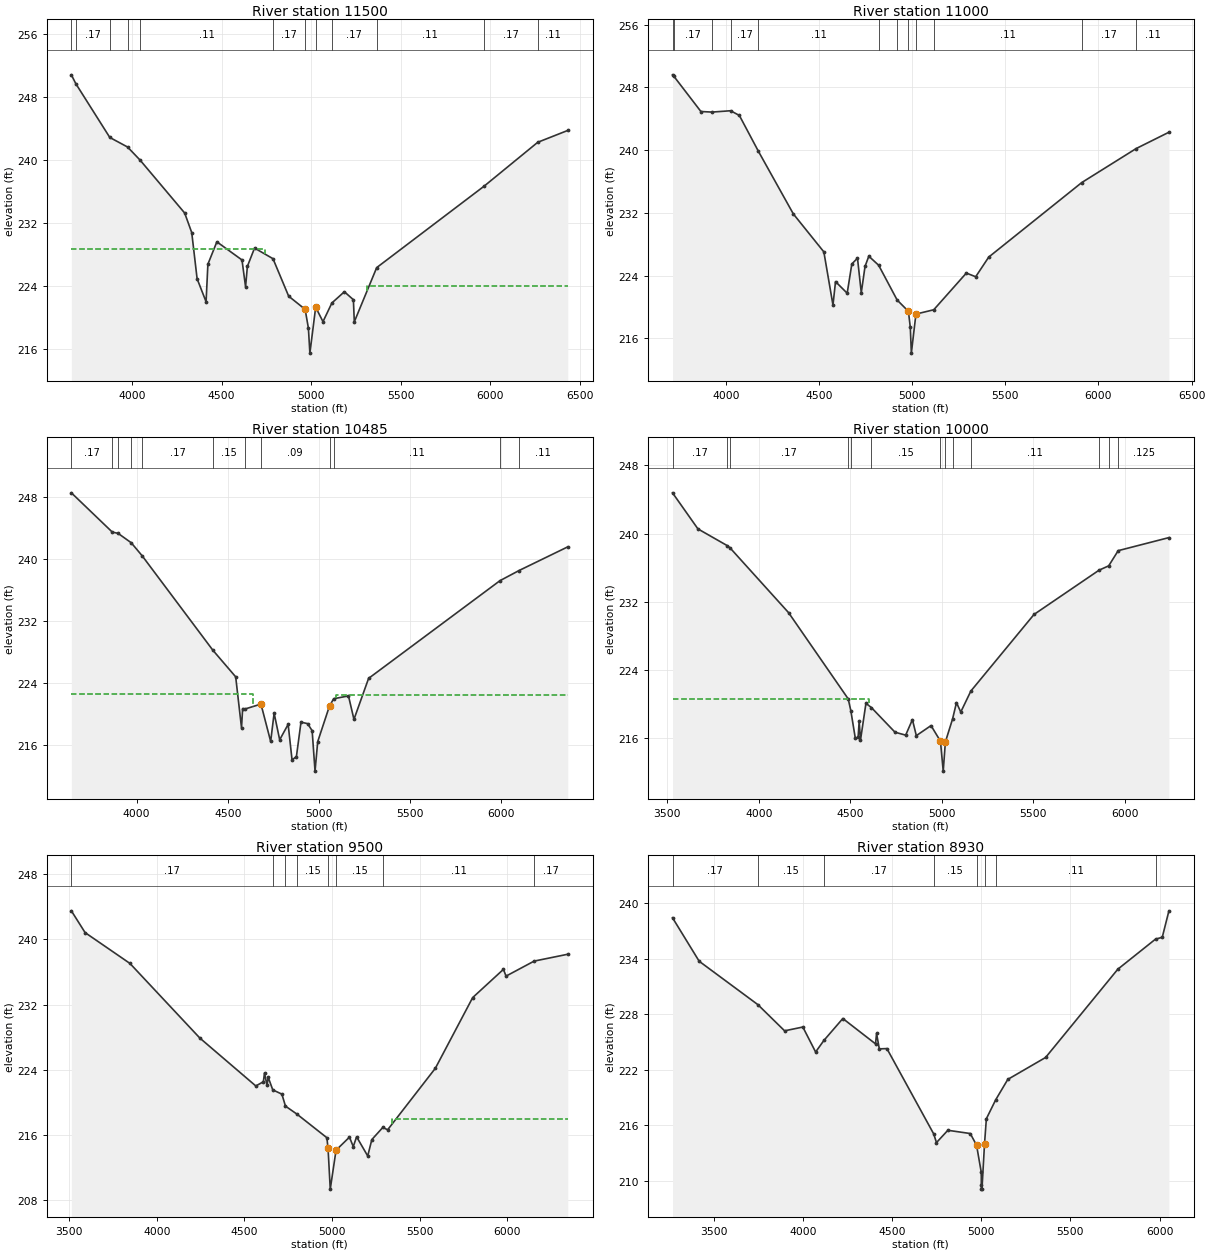
Type RM Length L Ch R = 1 ,11500   ,500,500,500
BEGIN DESCRIPTION:
Crystal Creek 046 21.0
END DESCRIPTION:
XS GIS Cut Line= 3
       3838928.4     10128723.99       3837592.3     10128813.65
      3836188.86     10128526.08
#Sta/Elev= 30
  3660.9  250.81  3685.7  249.69  3875.5  242.87  3974.6  241.66  4044.2  240.01
  4293.6  233.29    4333  230.81    4363  224.96  4413.1  222.04  4423.2   226.8
  4473.3  229.64  4613.6  227.34  4633.6  223.93  4643.7  226.53  4683.7  228.85
  4786.7   227.5  4874.2  222.75  4966.1  221.08  4984.4   218.7  4992.7  215.53
    5025  221.35  5065.8  219.52  5115.6  221.89  5185.2  223.31  5235.6   222.3
  5240.7   219.5  5365.7  226.37  5965.2  236.69    6265  242.26  6432.6  243.76
#Mann= 12 ,-1 , 0
  3660.9     .11       0  3685.7     .17       0  3875.5     .11       0
  3974.6     .17       0  4044.2     .11       0  4786.7     .17       0
  4966.1     .09       0    5025     .15       0  5115.6     .17       0
  5365.7     .11       0  5965.2     .17       0    6265     .11       0
#XS Ineff= 2 , 0
       0  4743.9  228.71  5310.8       0  224.03
Permanent Ineff=
       F       F
Bank Sta=4966.1,5025
XS Rating Curve= 0 ,0
Exp/Cntr=0.3,0.1

Type RM Length L Ch R = 1 ,11000   ,515,515,515
BEGIN DESCRIPTION:
Crystal Creek 046 20.0
END DESCRIPTION:
XS GIS Cut Line= 3
      3838928.45      10128661.5       3837658.3     10128462.09
      3836282.74     10128380.25
#Sta/Elev= 30
  3714.3  249.61  3719.8  249.48  3866.7  244.93  3926.8  244.86  4026.1  245.03
    4073  244.43  4175.4  239.85  4362.7  231.87  4526.4  227.03  4575.3  220.25
    4589  223.24  4651.6  221.76  4676.5  225.49  4706.9  226.23  4727.2  221.82
  4747.4  225.18  4767.6  226.48  4820.4  225.33  4919.7  220.89  4980.2  219.45
  4990.3  217.39  4995.9  214.12  5020.5   219.1  5116.1  219.65    5291  224.33
  5341.1  223.86  5411.2  226.37  5910.2  235.87  6202.3  240.21    6378  242.29
#Mann= 12 ,-1 , 0
  3714.3     .11       0  3719.8     .17       0  3926.8     .11       0
  4026.1     .17       0  4175.4     .11       0  4820.4     .17       0
  4919.7     .15       0  4980.2     .09       0  5020.5     .15       0
  5116.1     .11       0  5910.2     .17       0  6202.3     .11       0
#XS Ineff= 2 , 0
       0  4767.6  226.48               0
Permanent Ineff=
       F       F
Bank Sta=4980.2,5020.5
XS Rating Curve= 0 ,0
Exp/Cntr=0.3,0.1

Type RM Length L Ch R = 1 ,10485   ,485,485,485
BEGIN DESCRIPTION:
Crystal Creek 046 19.0
END DESCRIPTION:
XS GIS Cut Line= 3
      3838933.63     10128588.58      3837659.05     10128122.58
      3836298.23     10128203.16
#Sta/Elev= 30
  3642.9  248.51  3867.2  243.45  3898.8  243.29  3970.8  242.08  4030.4  240.41
    4418  228.24  4543.4   224.8  4575.4  218.22  4581.4  220.71  4592.5  220.64
  4681.9  221.29  4735.1  216.47    4754  220.12  4784.5  216.69  4830.9  218.68
  4852.2   214.1  4876.1  214.52  4901.3  218.96  4937.4  218.77  4962.4  217.86
  4978.2  212.65  4992.9  216.45  5057.7  221.06  5080.5  221.98  5161.5  222.34
  5191.5  219.32  5271.7   224.6  5991.6  237.19  6096.4   238.5  6363.2  241.55
#Mann= 12 ,-1 , 0
  3642.9     .17       0  3867.2     .11       0  3898.8     .17       0
  3970.8     .11       0  4030.4     .17       0    4418     .15       0
  4592.5     .17       0  4681.9     .09       0  5057.7     .17       0
  5080.5     .11       0  5991.6     .17       0  6096.4     .11       0
#XS Ineff= 2 , 0
       0  4637.2  222.53  5091.4       0   222.4
Permanent Ineff=
       F       F
Bank Sta=4681.9,5057.7
XS Rating Curve= 0 ,0
Exp/Cntr=0.3,0.1

Type RM Length L Ch R = 1 ,10000   ,500,500,500
BEGIN DESCRIPTION:
Crystal Creek 046 18.0
END DESCRIPTION:
XS GIS Cut Line= 3
      3838886.76     10128474.01      3837628.19     10127712.14
      3836397.12     10127880.25
#Sta/Elev= 30
  3528.8  244.78  3667.8  240.55  3827.1   238.6  3843.1  238.33  4163.3  230.73
  4489.3  220.62  4503.5  219.25    4528  216.02  4543.5  216.13  4549.3  218.04
  4556.2  215.75  4586.2   220.1  4616.2   219.6  4745.2  216.71  4803.4  216.37
  4840.3  218.19  4861.6  216.31    4942  217.49  4993.5  215.66  5008.7  212.15
  5020.5  215.57  5059.7  218.26  5081.1  220.18  5104.6  219.08  5159.8  221.54
    5505  230.52  5860.5  235.71  5913.3  236.22  5965.2     238  6242.5  239.53
#Mann= 13 ,-1 , 0
  3528.8     .17       0  3827.1     .11       0  3843.1     .17       0
  4489.3     .15       0  4503.5     .17       0  4616.2     .15       0
  4993.5     .09       0  5020.5     .15       0  5059.7     .17       0
  5159.8     .11       0  5860.5     .17       0  5913.3     .11       0
  5965.2    .125       0
#XS Ineff= 2 , 0
       0  4601.7  220.61  5081.1       0  220.18
Permanent Ineff=
       F       F
Bank Sta=4993.5,5020.5
XS Rating Curve= 0 ,0
Exp/Cntr=0.3,0.1

Type RM Length L Ch R = 1 ,9500    ,570,570,570
BEGIN DESCRIPTION:
Crystal Creek 046 17.0
END DESCRIPTION:
XS GIS Cut Line= 3
      3838964.87     10128364.62      3837814.75      10127421.6
      3836512.32     10127088.72
#Sta/Elev= 30
  3512.7  243.49  3591.1  240.82  3846.6  237.05  4245.6   227.9  4564.9  222.03
    4608  222.55  4614.5  223.63  4628.8  222.09  4635.3   223.1  4661.6  221.55
  4713.5  221.03    4734  219.56  4798.9  218.59  4970.1  215.69  4976.9  214.38
  4989.5  209.39  5022.5  214.16    5099  215.76  5120.7   214.6  5139.8   215.8
  5203.2  213.45  5226.6  215.46  5289.4  216.95  5316.8  216.66    5589   224.2
  5801.9  232.86  5977.3  236.32  5992.2  235.49  6152.5  237.33  6344.3  238.17
#Mann= 8 ,-1 , 0
  3512.7     .17       0  4661.6     .15       0    4734     .17       0
  4798.9     .15       0  4976.9     .09       0  5022.5     .15       0
  5289.4     .11       0  6152.5     .17       0
#XS Ineff= 2 , 0
       0  4791.7   218.6    5344       0  217.99
Permanent Ineff=
       F       F
Bank Sta=4976.9,5022.5
XS Rating Curve= 0 ,0
Exp/Cntr=0.3,0.1

Type RM Length L Ch R = 1 ,8930    ,451,451,451
BEGIN DESCRIPTION:
Crystal Creek 046 16.0
END DESCRIPTION:
XS GIS Cut Line= 3
      3839230.46     10127984.39      3837755.35     10127076.52
      3836741.84     10126791.96
#Sta/Elev= 30
  3267.9  238.44  3417.5  233.74  3746.8  229.05  3896.7  226.22    3999  226.63
  4070.7  223.93  4117.1  225.18  4223.3  227.55  4406.8  224.81  4412.6  225.94
    4428  224.27  4470.6   224.3  4732.8  215.09  4748.7  214.14  4812.6  215.47
  4938.1  215.12  4973.6  213.86    5000  210.92  5000.1  209.61  5000.4  209.11
  5003.9  209.11  5018.2     214  5028.6  216.72  5080.8  218.76  5148.8  220.97
  5360.9  223.34    5766  232.88  5977.4  236.13  6015.3  236.33  6052.7  239.19
#Mann= 8 ,-1 , 0
  3267.9     .17       0  3746.8     .15       0  4117.1     .17       0
  4732.8     .15       0  4973.6     .09       0  5018.2     .17       0
  5080.8     .11       0  5977.4    .125       0
Bank Sta=4973.6,5018.2
XS Rating Curve= 0 ,0
Exp/Cntr=0.3,0.1

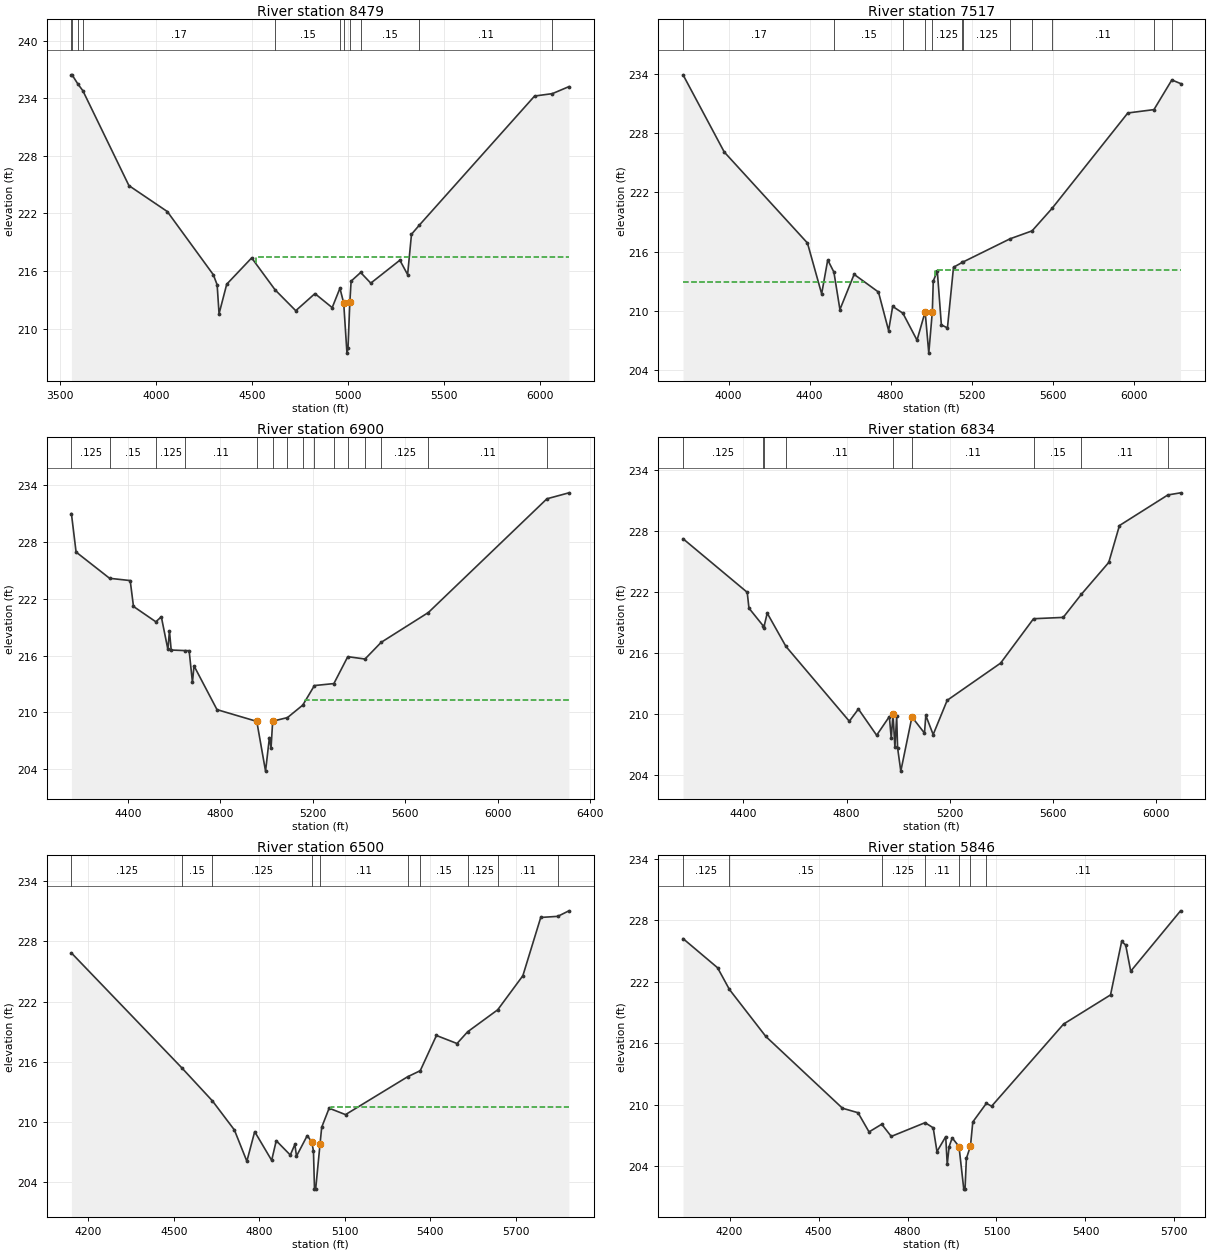
Type RM Length L Ch R = 1 ,8479    ,962,962,962
BEGIN DESCRIPTION:
Crystal Creek 046 15.0
END DESCRIPTION:
XS GIS Cut Line= 3
      3839317.83     10126761.07       3837875.5     10126788.97
      3836735.69     10126619.82
#Sta/Elev= 30
  3557.4  236.42  3560.7  236.43  3592.3  235.44    3617  234.78  3857.4  224.89
  4057.5  222.19  4297.5  215.61  4317.5  214.56  4327.5  211.54  4367.5  214.62
  4497.6  217.36  4619.9  214.03  4727.6  211.86  4827.6  213.64  4917.6  212.18
    4958   214.2  4977.6  212.66  4994.6  207.44    5000  207.94 5009.59 212.724
  5016.3  214.94  5066.1  215.84  5118.9  214.73  5270.6  217.12    5311  215.62
  5331.2  219.82  5371.6  220.76  5973.3  234.22  6065.9  234.47  6152.3   235.2
#Mann= 11 ,-1 , 0
  3557.4    .125       0  3560.7     .17       0  3592.3    .125       0
    3617     .17       0  4619.9     .15       0    4958    .125       0
  4977.6     .09       0 5009.59    .125       0  5066.1     .15       0
  5371.6     .11       0  6065.9     .15       0
#XS Ineff= 4 ,-1
  4517.6  4177.5  217.42  5016.3  5066.1  214.94  5066.1  5230.1  215.84
  5270.6  5321.1  217.12
Permanent Ineff=
       F       F       F       F
Bank Sta=4977.6,5009.59
XS Rating Curve= 0 ,0
Exp/Cntr=0.3,0.1

Type RM Length L Ch R = 1 ,7517    ,617,617,617
BEGIN DESCRIPTION:
Crystal Creek 046 14.0
END DESCRIPTION:
XS GIS Cut Line= 3
       3839240.9     10126505.24       3838018.6     10126428.52
      3836787.75     10126380.24
#Sta/Elev= 30
  3775.3  233.88  3978.7  226.07  4389.6  216.86  4459.7  211.72  4489.7  215.15
  4520.2  213.92  4549.9  210.13    4620  213.69  4740.2   211.9  4790.3     208
  4810.4  210.45  4860.8  209.76  4930.6  207.03  4970.7   209.9  4988.7  205.72
 5006.15209.9063  5010.8  213.02  5030.8  214.01  5050.8  208.58  5080.8  208.27
  5110.8  214.41    5154   214.9  5158.7  214.95  5390.3  217.29  5498.6  218.09
  5597.2  220.36  5971.5  230.02  6100.5  230.36  6188.8  233.36  6231.8     233
#Mann= 12 ,-1 , 0
  3775.3     .17       0  4520.2     .15       0  4860.8    .125       0
  4970.7     .09       0 5006.15    .125       0    5154     .15       0
  5158.7    .125       0  5390.3     .15       0  5498.6    .125       0
  5597.2     .11       0  6100.5    .125       0  6188.8     .15       0
#XS Ineff= 2 , 0
       0  4670.1  212.95  5020.8       0  214.12
Permanent Ineff=
       F       F
Bank Sta=4970.7,5006.15
XS Rating Curve= 0 ,0
Exp/Cntr=0.3,0.1

Type RM Length L Ch R = 1 ,6900    ,66,66,66
BEGIN DESCRIPTION:
Crystal Creek 046 13.0
END DESCRIPTION:
XS GIS Cut Line= 4
      3838602.91      10125437.2      3837973.33     10125999.45
      3837605.96     10126363.22      3836817.78     10126306.72
#Sta/Elev= 30
  4155.9  230.98  4176.1  226.92    4321  224.15  4410.1  223.91  4424.3  221.18
    4521  219.56  4544.7  220.09  4573.1  216.64  4579.8  218.61  4587.3  216.58
  4648.4  216.52    4665  216.51  4679.3  213.16    4686  214.91  4785.4  210.29
 4957.51209.0487  4995.4   203.8  5012.1  207.34  5019.2  206.26  5026.2  209.07
  5090.2  209.45  5156.4  210.77  5206.7  212.83  5290.9  213.04    5351  215.88
  5425.5  215.63  5495.3  217.39  5699.5  220.54  6212.1  232.54  6307.2  233.17
#Mann= 15 ,-1 , 0
  4155.9    .125       0    4321     .15       0    4521    .125       0
  4648.4     .11       0 4957.51     .09       0  5026.2     .11       0
  5090.2    .125       0  5156.4     .11       0  5206.7    .125       0
  5290.9     .15       0    5351     .11       0  5425.5     .15       0
  5495.3    .125       0  5699.5     .11       0  6212.1    .125       0
#XS Ineff= 2 , 0
       0                  5167.6       0  211.34
Permanent Ineff=
       F       F
Bank Sta=4957.51,5026.2
XS Rating Curve= 0 ,0
Exp/Cntr=0.3,0.1

Type RM Length L Ch R = 1 ,6834    ,334,334,334
BEGIN DESCRIPTION:
Mapping XS 71e46563
END DESCRIPTION:
XS GIS Cut Line= 3
      3838532.03     10125393.59      3837920.19     10125960.93
      3836855.85     10126223.68
#Sta/Elev= 30
  4165.6  227.25  4414.6  221.98  4421.4  220.42  4476.9  218.67  4478.4  218.45
  4492.3  219.93  4564.7  216.66  4810.9  209.29  4846.1  210.49  4916.9  207.91
  4966.3  209.75  4973.6   207.6  4980.4  210.03  4987.8  206.73  4994.6  209.78
  4998.2  206.67  5010.7  204.38  5053.9  209.71  5102.6  208.12  5107.7  209.86
  5136.3  207.98  5190.7  211.35    5398  215.01  5525.8  219.38    5641  219.51
  5711.6  221.79  5817.7  224.92  5859.2  228.55    6047  231.56  6096.3  231.77
#Mann= 9 ,-1 , 0
  4165.6    .125       0  4476.9     .15       0  4478.4    .125       0
  4564.7     .11       0  4980.4     .09       0  5053.9     .11       0
  5525.8     .15       0  5711.6     .11       0    6047    .125       0
#XS Ineff= 2 , 0
       0                  5190.7       0  211.35
Permanent Ineff=
       F       F
Bank Sta=4980.4,5053.9
XS Rating Curve= 0 ,0
Exp/Cntr=0.3,0.1

Type RM Length L Ch R = 1 ,6500    ,654,654,654
BEGIN DESCRIPTION:
Crystal Creek 046 12.0
END DESCRIPTION:
XS GIS Cut Line= 3
      3838499.26     10125347.28      3837746.19     10125761.55
      3836905.73     10126046.67
#Sta/Elev= 30
  4140.5  226.85  4528.6  215.38  4635.9  212.09  4712.8   209.2  4756.6  206.08
  4784.1  209.03  4843.7  206.17  4859.8  208.13  4909.1   206.7  4925.2  207.76
  4930.9  206.59  4968.7  208.64  4984.8  207.99  4990.5  207.08  4994.1   203.3
  4998.2   203.3  5013.4  207.75  5019.4  209.47  5045.5  211.37    5103  210.73
  5320.8   214.5  5365.5  215.11  5422.3  218.62  5494.6  217.82  5531.9  218.99
  5637.4  221.18  5725.8  224.58  5788.6  230.39  5848.5   230.5  5887.5  231.05
#Mann= 10 ,-1 , 0
  4140.5    .125       0  4528.6     .15       0  4635.9    .125       0
  4984.8     .09       0  5013.4     .11       0  5320.8    .125       0
  5365.5     .15       0  5531.9    .125       0  5637.4     .11       0
  5848.5    .125       0
#XS Ineff= 2 , 0
       0                    5051       0  211.48
Permanent Ineff=
       F       F
Bank Sta=4984.8,5013.4
XS Rating Curve= 0 ,0
Exp/Cntr=0.3,0.1

Type RM Length L Ch R = 1 ,5846    ,346,346,346
BEGIN DESCRIPTION:
Crystal Creek 046 11.0
END DESCRIPTION:
XS GIS Cut Line= 3
      3838461.11     10125270.94       3837529.9     10125491.62
      3836823.13     10125632.61
#Sta/Elev= 30
    4043  226.21  4159.4  223.37  4199.4  221.25  4322.1  216.67  4580.6  209.67
  4633.1  209.23  4670.2  207.36    4713  208.11  4745.2  206.92  4859.2  208.26
  4886.6  207.76  4899.3  205.44  4928.8   206.9  4933.9  204.19  4940.4  205.93
  4950.7  206.78  4973.6  205.93  4989.7  201.78  4993.9  201.78  4998.5  204.77
  5012.3  205.99  5020.1  208.33  5065.7  210.14  5083.7  209.87  5326.4  217.88
  5484.6  220.72  5522.1  225.93  5535.7  225.59  5552.7  223.03  5720.7  228.92
#Mann= 7 ,-1 , 0
    4043    .125       0  4199.4     .15       0    4713    .125       0
  4859.2     .11       0  4973.6     .09       0  5012.3     .15       0
  5065.7     .11       0
#XS Ineff= 2 , 0
       0  4633.1  209.23               0
Permanent Ineff=
       F       F
Bank Sta=4973.6,5012.3
XS Rating Curve= 0 ,0
Exp/Cntr=0.3,0.1