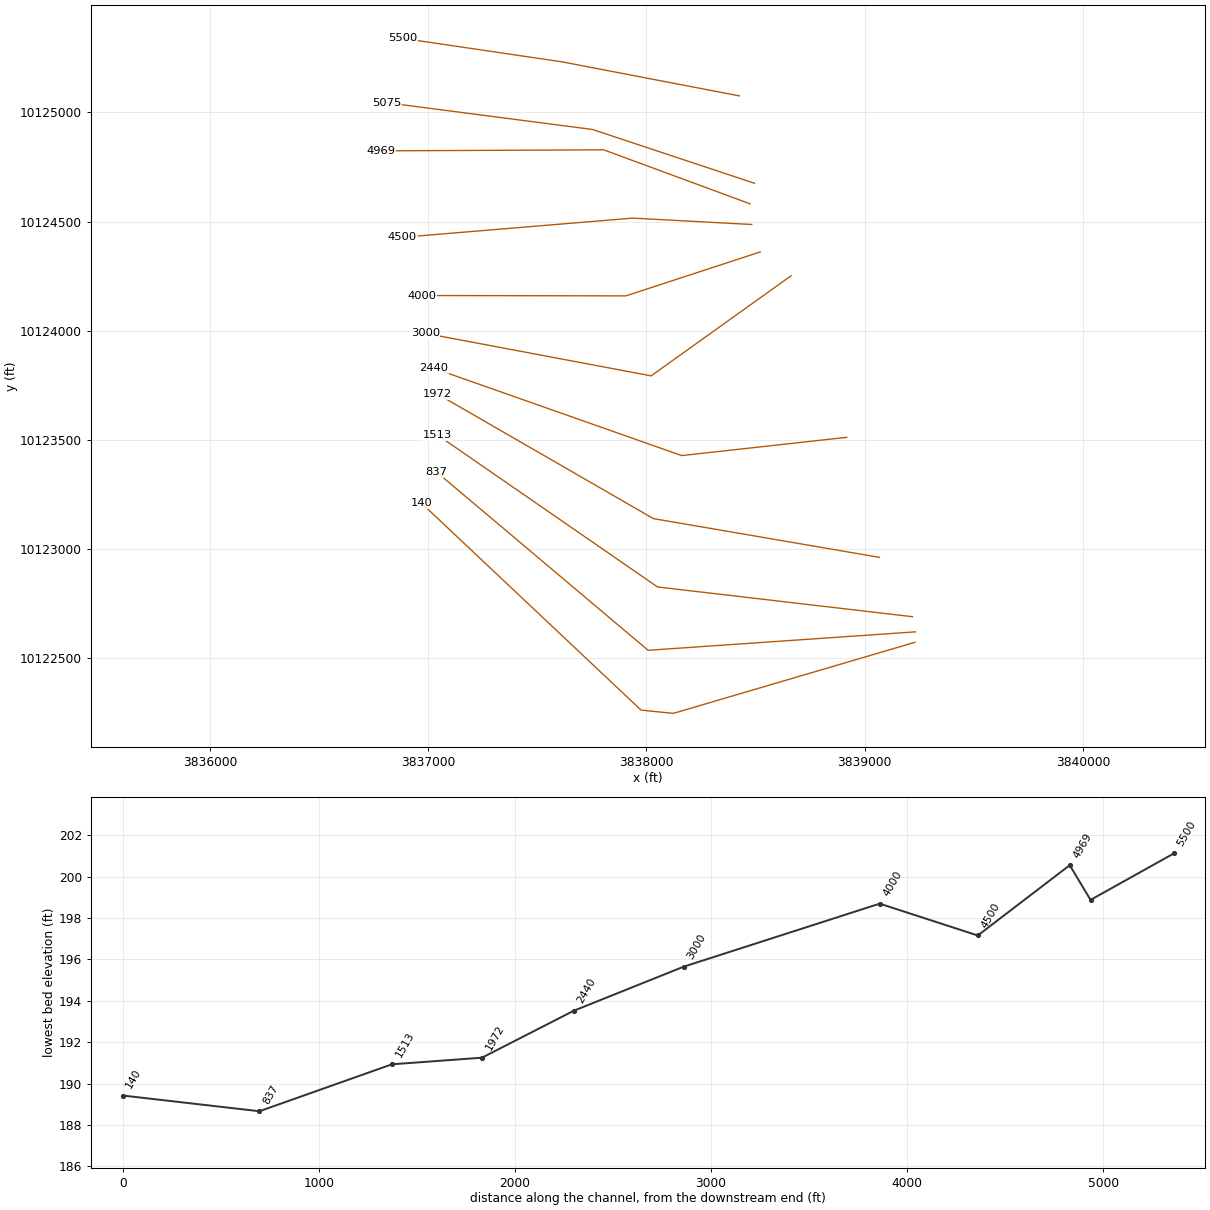
HEC-RAS study Crystal Creek 046.prj: Crystal Creek 046 Base Level Engineering

--- Crystal Creek 046.g01 (geometry) --- (continued)

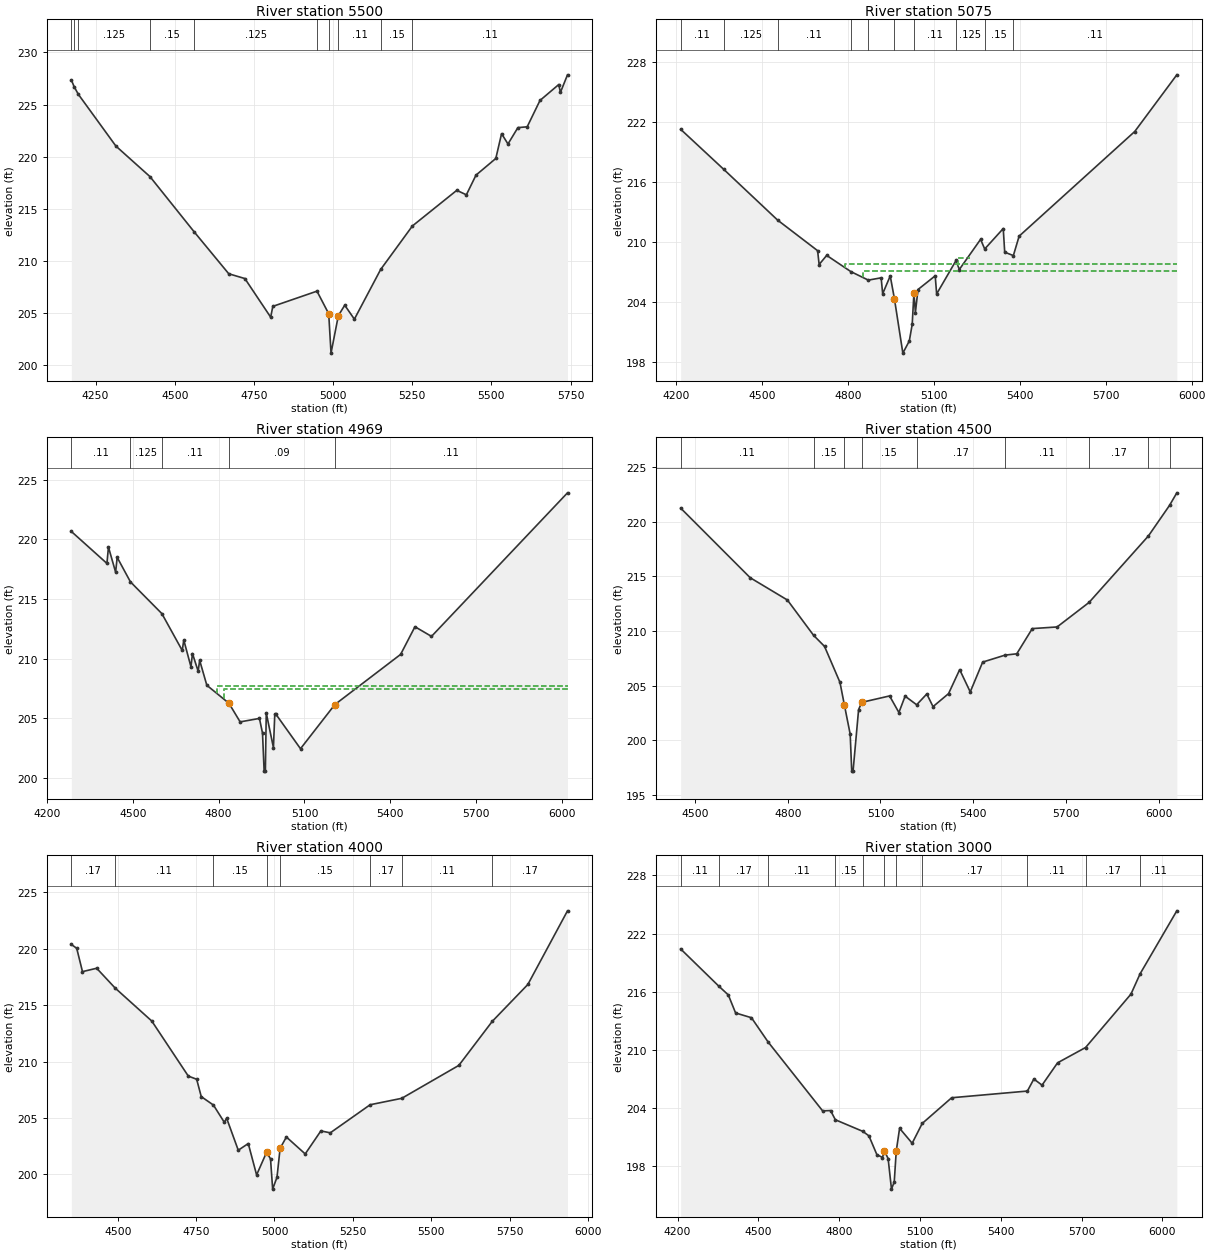
Type RM Length L Ch R = 1 ,5500    ,425,425,425
BEGIN DESCRIPTION:
Crystal Creek 046 10.0
END DESCRIPTION:
XS GIS Cut Line= 3
      3838426.06     10125075.77      3837614.39     10125231.62
      3836881.89     10125339.51
#Sta/Elev= 30
  4173.5  227.35  4182.4  226.71  4195.3  225.99  4314.2  221.01  4421.7  218.08
  4561.5  212.77  4670.6  208.75  4721.5  208.29    4803  204.58  4809.8  205.62
  4949.2  207.08  4986.3  204.91  4993.6  201.13  5016.7  204.73  5036.9  205.73
  5067.3  204.39  5150.3  209.16  5250.6  213.34  5390.7  216.76    5421  216.33
  5451.4  218.22    5514  219.82  5532.2   222.2  5552.4  221.21  5583.7  222.78
  5613.1  222.86  5653.5  225.39  5712.9  226.92    5718  226.16  5740.4  227.85
#Mann= 10 ,-1 , 0
  4173.5    .125       0  4182.4     .15       0  4195.3    .125       0
  4421.7     .15       0  4561.5    .125       0  4949.2     .12       0
  4986.3     .06       0  5016.7     .11       0  5150.3     .15       0
  5250.6     .11       0
#XS Ineff= 2 , 0
       0  4721.5  208.29               0
Permanent Ineff=
       F       F
Bank Sta=4986.3,5016.7
XS Rating Curve= 0 ,0
Exp/Cntr=0.3,0.1

Type RM Length L Ch R = 1 ,5075    ,106,106,106
BEGIN DESCRIPTION:
Mapping XS 764d4c44
END DESCRIPTION:
XS GIS Cut Line= 3
      3838495.57     10124675.24      3837752.65     10124921.92
      3836812.25     10125044.06
#Sta/Elev= 30
  4217.2  221.23  4366.8  217.25  4555.6  212.16    4695  209.11  4700.3  207.73
  4726.7  208.64    4811  207.02    4872  206.17  4916.7   206.4    4922  204.81
  4948.4  206.59  4962.9  204.33  4992.4  198.88  5014.9  200.09    5025  201.74
  5031.1  204.89  5036.2  202.93  5045.2  205.23  5105.3   206.6  5110.3  204.79
    5178  208.13  5189.4  207.23  5263.6  210.24    5278  209.28  5342.7  211.32
  5347.8  208.96    5378  208.62  5398.1  210.56  5801.5  221.01  5948.3  226.67
#Mann= 10 ,-1 , 0
  4217.2     .11       0  4366.8    .125       0  4555.6     .11       0
    4811    .125       0    4872     .11       0  4962.9     .09       0
  5031.1     .11       0    5178    .125       0    5278     .15       0
    5378     .11       0
#XS Ineff= 3 ,-1
  4853.4    4790  207.09    4790  4726.7  207.77  5184.4  5226.7  208.35
Permanent Ineff=
       F       F       F
Bank Sta=4962.9,5031.1
XS Rating Curve= 0 ,0
Exp/Cntr=0.3,0.1

Type RM Length L Ch R = 1 ,4969    ,469,469,469
BEGIN DESCRIPTION:
Crystal Creek 046 9.0
END DESCRIPTION:
XS GIS Cut Line= 3
      3838474.73     10124581.26       3837804.1     10124828.62
      3836784.61     10124823.87
#Sta/Elev= 30
  4285.2  220.66  4409.6  217.98  4414.9  219.35    4440  217.24  4445.3  218.49
  4491.8  216.43  4601.6  213.77  4672.8  210.68  4678.2  211.55  4703.3  209.31
  4708.6  210.42  4728.4  208.94  4733.7  209.85  4758.8  207.76  4836.1  206.25
  4875.2  204.69  4942.7  204.98  4953.4  203.75  4959.1  200.56  4963.4  200.56
  4966.5  205.44  4991.6  202.53  4996.3  205.34    5000  205.34  5086.2  202.44
  5206.2  206.14  5436.2  210.35  5486.3  212.67  5544.1  211.86  6019.5   223.9
#Mann= 5 ,-1 , 0
  4285.2     .11       0  4491.8    .125       0  4601.6     .11       0
  4836.1     .09       0  5206.2     .11       0
#XS Ineff= 2 ,-1
  4819.7  4794.6  207.44  4794.6  4764.1  207.72
Permanent Ineff=
       F       F
Bank Sta=4836.1,5206.2
XS Rating Curve= 0 ,0
Exp/Cntr=0.3,0.1

Type RM Length L Ch R = 1 ,4500    ,500,500,500
BEGIN DESCRIPTION:
Crystal Creek 046 8.0
END DESCRIPTION:
XS GIS Cut Line= 3
      3838482.55     10124486.43      3837936.93     10124515.68
      3836881.88     10124427.91
#Sta/Elev= 30
  4453.6  221.26  4678.6  214.88  4798.8  212.84  4883.7   209.6    4919  208.59
    4969  205.29  4983.1  203.24    5002  200.55    5007  197.16  5011.3  197.16
  5029.2  202.79  5039.2  203.46  5129.5  204.05  5159.6  202.53  5179.7  204.03
    5217  203.24  5249.9  204.23    5270  203.07  5320.2  204.26  5356.2  206.46
  5390.4  204.42  5430.6  207.15  5503.1  207.79  5540.9  207.91  5591.1  210.22
  5671.4  210.37  5774.9  212.62  5966.8  218.71  6035.4  221.52  6058.7  222.66
#Mann= 9 ,-1 , 0
  4453.6     .11       0  4883.7     .15       0  4983.1     .09       0
  5039.2     .15       0    5217     .17       0  5503.1     .11       0
  5774.9     .17       0  5966.8     .11       0  6035.4     .17       0
#XS Ineff= 2 , 0
       0                  5356.2       0  206.46
Permanent Ineff=
       F       F
Bank Sta=4983.1,5039.2
XS Rating Curve= 0 ,0
Exp/Cntr=0.3,0.1

Type RM Length L Ch R = 1 ,4000    ,1000,1000,1000
BEGIN DESCRIPTION:
Crystal Creek 046 7.0
END DESCRIPTION:
XS GIS Cut Line= 3
      3838521.62     10124360.56      3837905.87      10124159.3
      3836971.37      10124160.9
#Sta/Elev= 30
  4352.2  220.39  4369.3  220.05  4387.7  217.98    4433  218.28  4491.3  216.54
  4608.7   213.6  4725.2  208.72  4751.8  208.44  4766.5   206.9  4805.4  206.15
  4840.1  204.62  4847.4  204.99  4884.5  202.15  4916.4  202.74    4943  199.96
  4974.9  201.97  4987.4  201.38  4994.2   198.7    5008  199.75    5018  202.32
    5038  203.32    5098  201.82    5148  203.86    5178  203.69  5305.1  206.18
    5406  206.75    5588  209.67  5694.5  213.57    5808  216.84  5934.5  223.37
#Mann= 8 ,-1 , 0
  4352.2     .17       0  4491.3     .11       0  4805.4     .15       0
  4974.9     .09       0    5018     .15       0  5305.1     .17       0
    5406     .11       0  5694.5     .17       0
Bank Sta=4974.9,5018
XS Rating Curve= 0 ,0
Exp/Cntr=0.3,0.1

Type RM Length L Ch R = 1 ,3000    ,560,560,560
BEGIN DESCRIPTION:
Crystal Creek 046 6.0
END DESCRIPTION:
XS GIS Cut Line= 3
      3838663.13     10124251.63      3838021.78     10123792.75
      3836986.07     10123987.72
#Sta/Elev= 30
  4211.4  220.41  4352.8  216.58  4388.3  215.67  4415.4  213.81  4474.3  213.32
  4536.1  210.82  4738.5  203.72    4768  203.75  4785.9   202.8  4888.2   201.6
  4910.5  201.14    4940  199.21  4960.9  198.91  4967.9   199.6  4981.8   198.8
  4994.3  195.65  5004.5  196.39 5011.98199.5732  5024.4  201.92  5071.1  200.38
  5108.4  202.42  5217.7  205.07    5499  205.76    5523     207  5553.4  206.37
    5611  208.67  5715.1  210.25  5883.5  215.75  5917.6  217.85  6053.9  224.34
#Mann= 11 ,-1 , 0
  4211.4     .11       0  4352.8     .17       0  4536.1     .11       0
  4785.9     .15       0  4888.2     .11       0  4967.9     .09       0
 5011.98     .11       0  5108.4     .17       0    5499     .11       0
  5715.1     .17       0  5917.6     .11       0
Bank Sta=4967.9,5011.98
XS Rating Curve= 0 ,0
Exp/Cntr=0.3,0.1

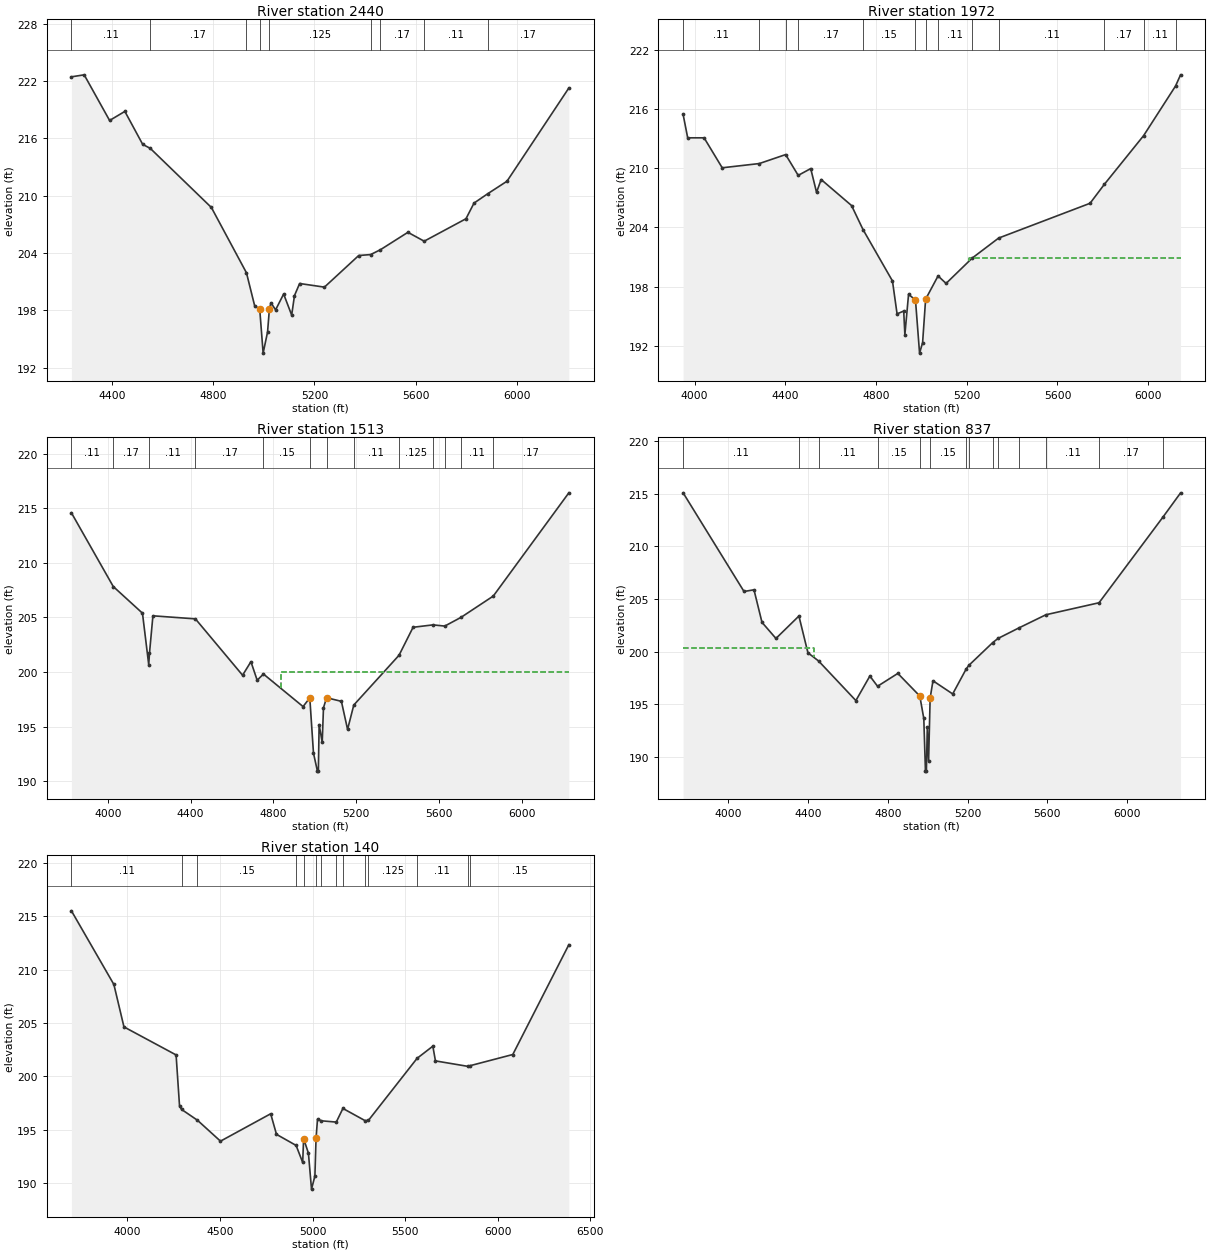
Type RM Length L Ch R = 1 ,2440    ,468,468,468
BEGIN DESCRIPTION:
Crystal Creek 046 5.0
END DESCRIPTION:
XS GIS Cut Line= 3
       3838917.9     10123511.08       3838161.7     10123427.47
      3837024.26       10123828.
#Sta/Elev= 30
  4239.2  222.45  4289.7  222.66  4390.2  217.88  4450.5  218.83    4521  215.38
    4551  214.96  4792.6  208.77  4931.3  201.93  4963.6  198.49  4983.8   198.1
  4997.2  193.52  5014.7  195.73 5022.01198.1458  5028.2  198.79  5046.5  198.05
  5078.3  199.71  5110.1   197.5  5121.1  199.54  5141.5  200.81  5239.6  200.43
  5375.1  203.74  5422.3  203.84  5461.1  204.35  5569.6  206.17    5634  205.24
  5799.2  207.59    5831  209.23  5885.2  210.21  5961.4  211.52  6205.9  221.28
#Mann= 9 ,-1 , 0
  4239.2     .11       0    4551     .17       0  4931.3     .15       0
  4983.8     .09       0 5022.01    .125       0  5422.3     .11       0
  5461.1     .17       0    5634     .11       0  5885.2     .17       0
Bank Sta=4983.8,5022.01
XS Rating Curve= 0 ,0
Exp/Cntr=0.3,0.1

Type RM Length L Ch R = 1 ,1972    ,459,459,459
BEGIN DESCRIPTION:
Crystal Creek 046 4.0
END DESCRIPTION:
XS GIS Cut Line= 3
      3839067.81     10122961.08       3838032.1     10123138.57
       3837042.2      10123709.6
#Sta/Elev= 30
  3949.2  215.46  3969.4  213.09  4041.7  213.09  4121.6  210.05  4285.2  210.48
  4401.3  211.39  4456.7  209.28  4511.9  209.97  4537.6  207.56  4557.9  208.86
    4692  206.22  4742.6  203.78  4872.4  198.57  4892.7  195.23    4922  195.52
  4927.1  193.12  4943.4  197.22  4973.9  196.63  4991.9  191.25  5005.3  192.31
  5018.6  196.72  5073.5  199.08  5108.8  198.32    5224  200.89  5340.5  202.92
  5743.8  206.45  5806.4  208.36  5979.9  213.31  6120.9  218.35  6142.8  219.48
#Mann= 13 ,-1 , 0
  3949.2     .11       0  4285.2     .17       0  4401.3     .11       0
  4456.7     .17       0  4742.6     .15       0  4973.9     .09       0
  5018.6     .15       0  5073.5     .11       0    5224    .125       0
  5340.5     .11       0  5806.4     .17       0  5979.9     .11       0
  6120.9     .17       0
#XS Ineff= 2 , 0
       0                    5211       0  200.88
Permanent Ineff=
       F       F
Bank Sta=4973.9,5018.6
XS Rating Curve= 0 ,0
Exp/Cntr=0.3,0.1

Type RM Length L Ch R = 1 ,1513    ,676,676,676
BEGIN DESCRIPTION:
Crystal Creek 046 3.0
END DESCRIPTION:
XS GIS Cut Line= 3
      3839218.68     10122689.12        3838051.     10122825.37
      3837042.18     10123522.04
#Sta/Elev= 30
  3824.4  214.58  4026.5  207.83  4167.5  205.39  4197.7  200.67  4201.2   201.7
  4217.9  205.15  4423.1  204.87  4650.8  199.71  4691.1  200.95  4721.3  199.25
  4751.5  199.82  4942.8  196.84 4975.32197.6373  4993.1  192.58  5012.1  190.93
  5016.6  190.93  5020.4  195.19  5035.3  193.57  5041.4  196.73  5056.3  197.65
  5127.9  197.32  5157.7  194.75  5187.7  196.98  5406.2  201.54    5474   204.1
  5570.1  204.32    5627  204.21  5705.6  205.01  5861.3  206.96    6226  216.41
#Mann= 13 ,-1 , 0
  3824.4     .11       0  4026.5     .17       0  4201.2     .11       0
  4423.1     .17       0  4751.5     .15       0 4975.32     .09       0
  5056.3     .15       0  5187.7     .11       0  5406.2    .125       0
  5570.1     .11       0    5627    .125       0  5705.6     .11       0
  5861.3     .17       0
#XS Ineff= 3 ,-1
  4835.3  4691.1  199.98  4691.1  4600.5  200.95  5336.8  5366.6  199.88
Permanent Ineff=
       F       F       F
Bank Sta=4975.32,5056.3
XS Rating Curve= 0 ,0
Exp/Cntr=0.3,0.1

Type RM Length L Ch R = 1 ,837     ,697,697,697
BEGIN DESCRIPTION:
Crystal Creek 046 2.0
END DESCRIPTION:
XS GIS Cut Line= 3
      3839232.59     10122619.68       3838007.8     10122535.12
      3837038.13     10123352.31
#Sta/Elev= 30
  3772.3  215.09  4077.8  205.72  4127.9  205.88    4168  202.79  4238.1  201.26
  4353.3  203.39  4398.5   199.9    4452  199.12  4639.1  195.36  4709.3  197.69
  4747.9  196.72  4849.6  197.94  4959.9  195.79  4979.9  193.66  4988.2  188.66
  4992.8  188.66  4997.5  192.81    5004  189.63  5011.7   195.6    5026  197.24
  5124.9  195.99  5192.5  198.36  5206.2  198.71  5325.9  200.87  5352.2  201.26
  5459.2  202.28  5592.5  203.51  5859.1  204.65  6179.2  212.77  6268.1  215.08
#Mann= 14 ,-1 , 0
  3772.3     .11       0  4353.3     .17       0    4452     .11       0
  4747.9     .15       0  4959.9     .09       0  5011.7     .15       0
  5192.5     .11       0  5206.2     .15       0  5325.9    .125       0
  5352.2     .11       0  5459.2    .125       0  5592.5     .11       0
  5859.1     .17       0  6179.2     .15       0
#XS Ineff= 2 , 0
       0  4428.6  200.39               0
Permanent Ineff=
       F       F
Bank Sta=4959.9,5011.7
XS Rating Curve= 0 ,0
Exp/Cntr=0.3,0.1

Type RM Length L Ch R = 1 ,140     ,0,0,0
BEGIN DESCRIPTION:
Crystal Creek 046 1.0
END DESCRIPTION:
XS GIS Cut Line= 4
      3839230.06      10122571.6      3838123.25     10122246.06
       3837975.4     10122261.07       3836968.7     10123209.93
#Sta/Elev= 30
  3697.7  215.53    3927  208.62  3981.4  204.64  4262.9  202.01  4281.4  197.24
  4292.3   196.9  4378.4  195.88  4502.6  193.92  4773.6  196.49  4804.9  194.56
  4910.9  193.52  4946.4  191.92  4951.4  194.16  4977.4  192.79    4994  189.42
  5012.3  190.64 5018.49 194.176  5026.4  195.98  5047.6  195.83  5127.8  195.71
  5163.6  196.99  5282.7  195.85  5301.4  195.87    5564  201.69  5649.1  202.83
  5663.2  201.45  5837.8  200.94  5852.4  201.01  6080.8  202.05  6383.4  212.35
#Mann= 14 ,-1 , 0
  3697.7     .11       0  4292.3     .17       0  4378.4     .15       0
  4910.9     .11       0  4951.4     .06       0 5018.49     .11       0
  5047.6    .125       0  5127.8     .11       0  5163.6    .125       0
  5282.7     .11       0  5301.4    .125       0    5564     .11       0
  5837.8     .17       0  5852.4     .15       0
Bank Sta=4951.4,5018.49
XS Rating Curve= 0 ,0
Exp/Cntr=0.3,0.1

Chan Stop Cuts=-1
Use User Specified Reach Order=0
Composite Channel Slope=5

--- Crystal Creek 046.g10 (geometry) ---

Geom Title=Existing Conditions
Program Version=4.10

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
River Reach=Crystal Creek 04,Reach-1

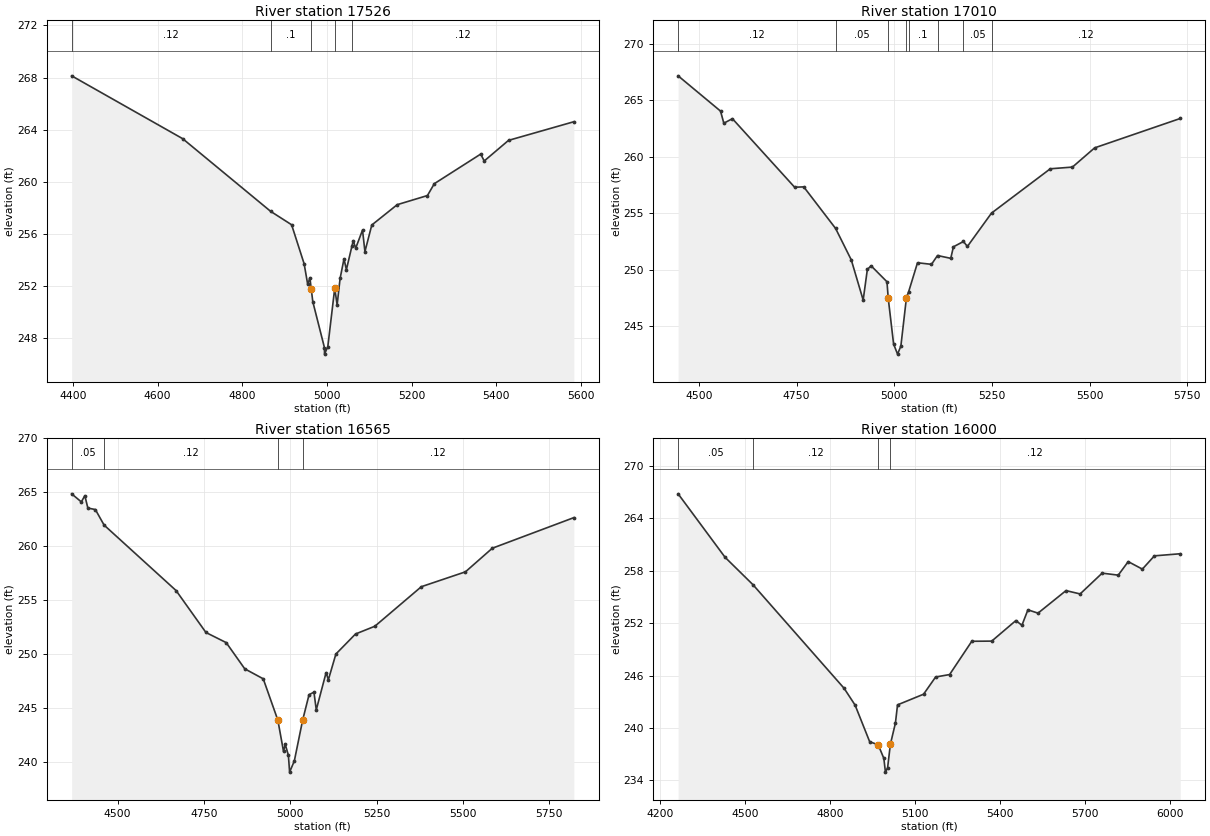
Type RM Length L Ch R = 1 ,17526   ,516,516,516
BEGIN DESCRIPTION:
Crystal Creek 046 33.0
END DESCRIPTION:
XS GIS Cut Line= 3
      3838443.79     10132892.66      3837855.35     10133025.29
      3837341.26     10133301.51
#Sta/Elev= 30
  4396.8  268.14  4659.2  263.32    4867  257.75  4916.6  256.72  4946.2  253.73
  4954.7  252.14  4959.8  252.66 4962.99 251.809  4966.7  250.82  4994.2   247.3
  4994.4   246.8  5002.2  247.38  5018.5  251.85  5024.2  250.58  5031.2   252.6
  5040.4   254.1  5046.1  253.28  5059.3   255.1  5062.3   255.5    5068  254.92
  5084.2  256.31  5089.9  254.66  5106.1   256.7  5166.2  258.26  5237.6  258.96
  5253.9  259.87  5363.5  262.14  5371.8  261.61  5429.2  263.19  5583.6  264.62
#Mann= 5 ,-1 , 0
  4396.8     .12       0    4867      .1       0 4962.99     .07       0
  5018.5      .1       0  5059.3     .12       0
Bank Sta=4962.99,5018.5
XS Rating Curve= 0 ,0
Exp/Cntr=0.3,0.1

Type RM Length L Ch R = 1 ,17010   ,445,445,445
BEGIN DESCRIPTION:
Crystal Creek 046 32.0
END DESCRIPTION:
XS GIS Cut Line= 3
      3838304.94     10132475.99       3837759.4     10132568.33
      3837217.83     10133061.09
#Sta/Elev= 30
  4446.7  267.16  4555.3  264.04  4563.7  262.97  4585.7  263.37  4744.9  257.31
  4768.3  257.34  4849.9  253.66    4890  250.88  4920.4  247.33  4931.1  250.04
  4940.7  250.36  4981.3  248.95 4984.56 247.486  4998.3  243.44  5008.4  242.55
  5016.9  243.26  5031.1  247.52  5036.9  248.08  5059.5  250.63  5095.3  250.49
  5110.7  251.27  5144.6  251.02  5151.4  252.04  5177.1  252.51  5187.2  252.07
  5248.9  255.02  5399.4  258.94  5456.1  259.09  5512.9  260.79  5732.2  263.39
#Mann= 8 ,-1 , 0
  4446.7     .12       0  4849.9     .05       0 4984.56     .07       0
  5031.1     .12       0  5036.9      .1       0  5110.7     .12       0
  5177.1     .05       0  5248.9     .12       0
Bank Sta=4984.56,5031.1
XS Rating Curve= 0 ,0
Exp/Cntr=0.3,0.1

Type RM Length L Ch R = 1 ,16565   ,565,565,565
BEGIN DESCRIPTION:
Crystal Creek 046 31.0
END DESCRIPTION:
XS GIS Cut Line= 3
      3838235.43     10132087.11      3837612.66     10132199.33
      3837062.38     10132808.75
#Sta/Elev= 30
  4367.2  264.86  4395.2  264.11  4405.4  264.69  4414.1  263.54  4435.9   263.4
  4461.1  261.96  4669.6  255.88    4756  251.99  4814.7  251.05  4868.3  248.62
  4921.9  247.69  4964.2  243.85  4980.6  240.95  4985.6  241.61  4994.7  240.59
  4998.2  239.03  5011.9  240.07 5035.77 243.826  5054.5  246.22  5068.7  246.45
  5075.4  244.81  5103.8  248.26  5110.5  247.61  5132.2  249.99    5189  251.85
    5245  252.57  5379.6  256.24  5507.3  257.62    5585  259.81  5821.1  262.65
#Mann= 4 ,-1 , 0
  4367.2     .05       0  4461.1     .12       0  4964.2     .07       0
 5035.77     .12       0
Bank Sta=4964.2,5035.77
XS Rating Curve= 0 ,0
Exp/Cntr=0.3,0.1

Type RM Length L Ch R = 1 ,16000   ,500,500,500
BEGIN DESCRIPTION:
Crystal Creek 046 30.0
END DESCRIPTION:
XS GIS Cut Line= 3
      3838263.23     10131830.16      3837528.47     10131837.08
      3836771.56     10132544.17
#Sta/Elev= 30
  4265.2   266.8  4430.6  259.54  4529.3  256.39  4850.6  244.53  4889.2  242.61
  4940.6  238.42  4970.6  238.07  4990.6  236.51  4996.1  234.94  5003.8  235.44
 5013.57 238.121  5031.4  240.56  5038.8  242.64  5130.6  243.86  5173.1  245.83
  5222.4  246.11  5300.6  249.92    5371  249.94    5456  252.29  5477.4  251.75
  5498.5  253.52  5534.1  253.14  5632.8  255.72  5682.6  255.34  5760.3  257.72
    5817  257.49  5852.1  259.04    5902  258.18  5944.5   259.7  6035.8  259.94
#Mann= 4 ,-1 , 0
  4265.2     .05       0  4529.3     .12       0  4970.6     .07       0
 5013.57     .12       0
Bank Sta=4970.6,5013.57
XS Rating Curve= 0 ,0
Exp/Cntr=0.3,0.1