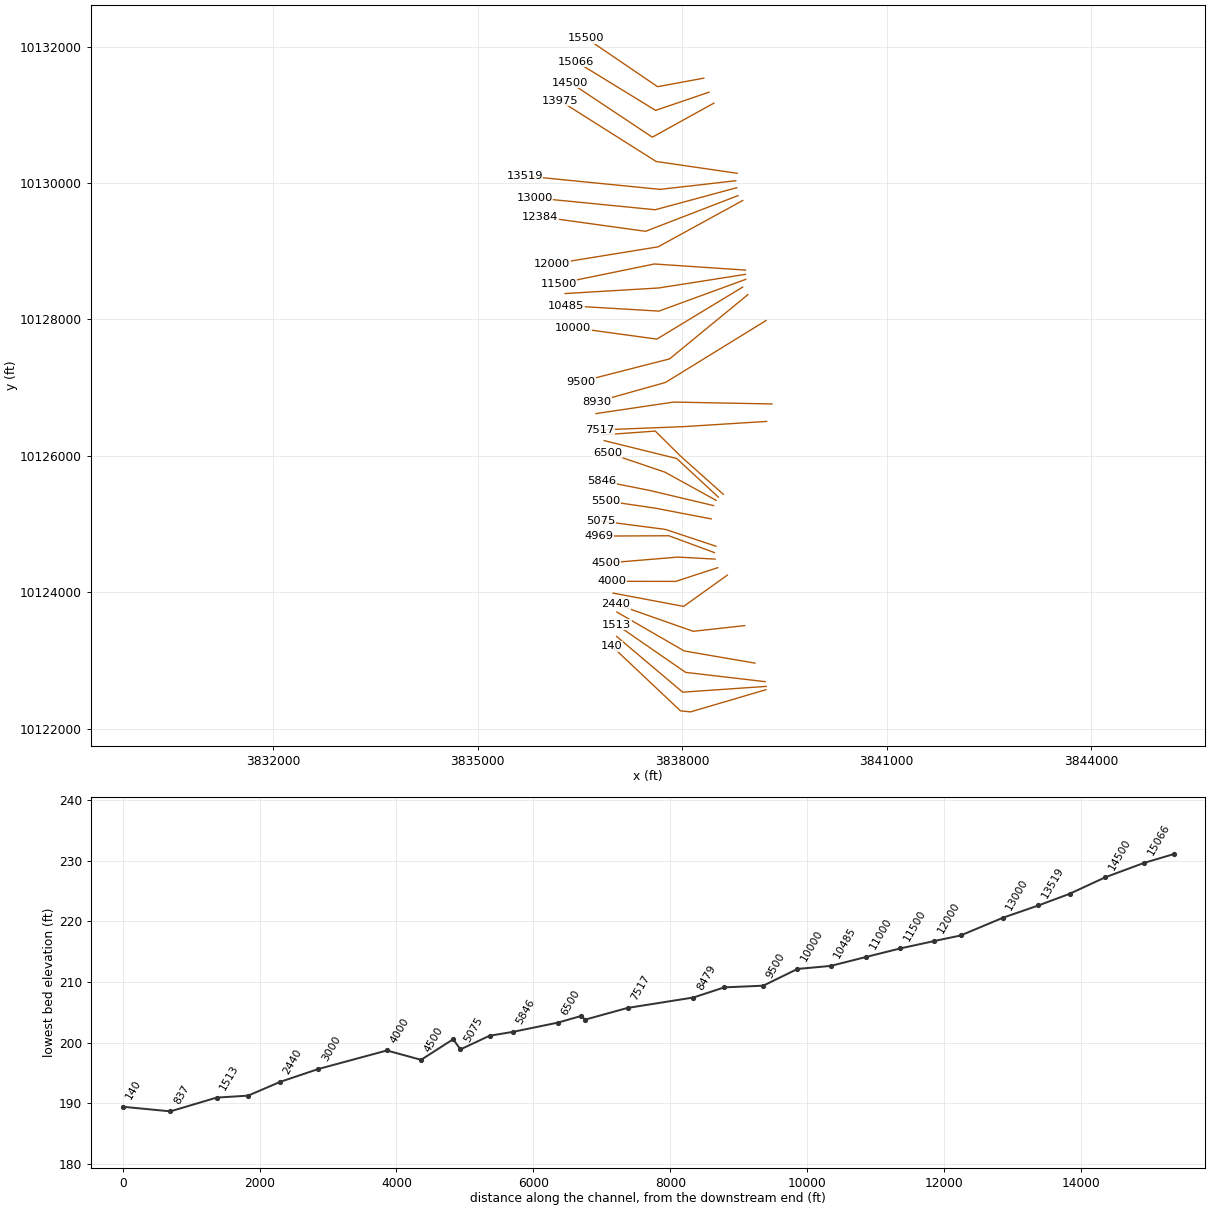
HEC-RAS study Crystal Creek 046.prj: Crystal Creek 046 Base Level Engineering

--- Crystal Creek 046.g10 (geometry) --- (continued)

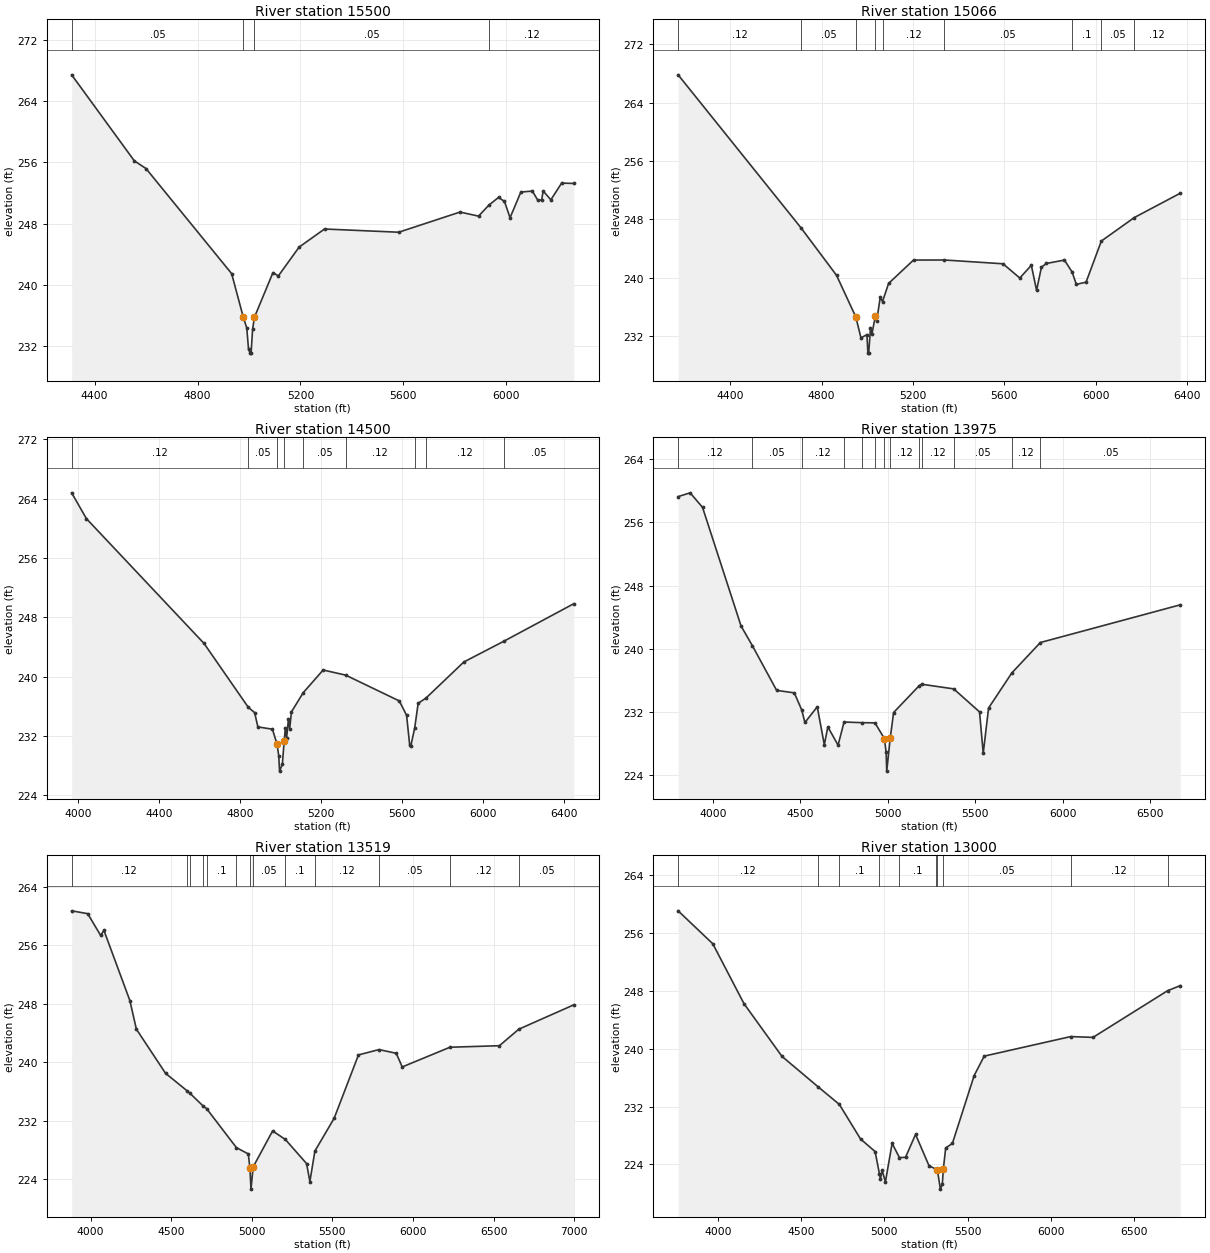
Type RM Length L Ch R = 1 ,15500   ,434,434,434
BEGIN DESCRIPTION:
Crystal Creek 046 29.0
END DESCRIPTION:
XS GIS Cut Line= 3
      3838317.51     10131538.48      3837639.57      10131413.3
      3836594.75     10132123.42
#Sta/Elev= 30
  4310.6   267.4  4554.3  256.18  4599.6  255.18  4932.7  241.47 4978.05 235.784
  4991.6  234.37  4998.3  231.63  5004.8   231.1  5008.3   231.1  5014.2  234.22
  5021.5  235.79  5093.3   241.6  5114.3  241.17  5195.1  244.93  5293.9  247.29
  5582.4  246.87  5820.7   249.5  5892.6  248.97  5933.2  250.41  5970.5  251.41
  5993.5  250.89  6015.3  248.76  6057.3  252.11  6102.1  252.24  6123.1  251.04
    6138  251.08  6144.1  252.24    6174   251.1  6215.9  253.28  6263.3  253.23
#Mann= 4 ,-1 , 0
  4310.6     .05       0 4978.05     .07       0  5021.5     .05       0
  5933.2     .12       0
Bank Sta=4978.05,5021.5
XS Rating Curve= 0 ,0
Exp/Cntr=0.3,0.1

Type RM Length L Ch R = 1 ,15066   ,566,566,566
BEGIN DESCRIPTION:
Crystal Creek 046 28.0
END DESCRIPTION:
XS GIS Cut Line= 3
      3838394.58     10131332.77      3837610.64     10131065.96
      3836441.63     10131782.03
#Sta/Elev= 30
  4171.9  267.81  4709.5  246.85  4865.6  240.32  4950.1   234.6  4972.6  231.74
  4998.7  232.19  5002.9  229.65  5006.4  229.65  5014.2  233.05  5020.1  232.21
  5035.5  234.72  5041.4  234.05  5056.8  237.29  5066.9  236.72  5093.6  239.21
  5202.6  242.41  5338.3  242.42  5594.6   241.9  5668.1  239.95  5718.6  241.69
  5741.5  238.26  5762.8  241.43  5784.1  241.94  5863.5  242.41  5897.1  240.77
  5915.6  239.08  5958.2  239.38  6025.2  245.02  6169.5  248.24  6370.9  251.58
#Mann= 9 ,-1 , 0
  4171.9     .12       0  4709.5     .05       0  4950.1     .07       0
  5035.5     .05       0  5066.9     .12       0  5338.3     .05       0
  5897.1      .1       0  6025.2     .05       0  6169.5     .12       0
Bank Sta=4950.1,5035.5
XS Rating Curve= 0 ,0
Exp/Cntr=0.3,0.1

Type RM Length L Ch R = 1 ,14500   ,525,525,525
BEGIN DESCRIPTION:
Crystal Creek 046 27.0
END DESCRIPTION:
XS GIS Cut Line= 3
      3838465.33     10131172.09      3837562.52     10130672.96
      3836356.89     10131474.21
#Sta/Elev= 30
  3968.4  264.79  4041.3  261.31    4622  244.49  4840.5  235.88  4871.7  235.17
  4887.8  233.24  4959.6  232.93  4982.5   230.9  4990.9  229.31  4994.8  227.28
  5008.6  228.21  5017.6  231.34  5023.7  233.11  5029.7  231.79  5038.7  234.29
  5044.7     233  5053.6  235.27  5111.8  237.86    5210  240.91  5321.1  240.22
  5585.9  236.74  5621.9  234.81    5637  230.85    5643   230.7  5661.9  233.09
  5679.1  236.43    5717  237.11  5904.5  241.99  6102.9   244.8  6447.6  249.85
#Mann= 9 ,-1 , 0
  3968.4     .12       0  4840.5     .05       0  4982.5     .07       0
  5017.6     .12       0  5111.8     .05       0  5321.1     .12       0
  5661.9     .05       0    5717     .12       0  6102.9     .05       0
Bank Sta=4982.5,5017.6
XS Rating Curve= 0 ,0
Exp/Cntr=0.3,0.1

Type RM Length L Ch R = 1 ,13975   ,456,456,456
BEGIN DESCRIPTION:
Crystal Creek 046 26.0
END DESCRIPTION:
XS GIS Cut Line= 3
      3838805.94      10130143.6      3837618.29     10130316.69
      3836202.71      10131210.6
#Sta/Elev= 30
  3799.8  259.25  3868.6  259.73  3939.4   257.9  4160.1  242.89  4225.1  240.39
  4363.8  234.75  4464.8  234.44  4507.4  232.27  4525.5  230.69  4596.2  232.67
  4636.6  227.88  4656.9  230.13  4715.4  227.82  4749.5  230.75  4849.6  230.67
  4926.7  230.64  4980.2  228.66  4990.3  226.96  4993.8  224.54 5013.71 228.683
  5033.2  231.95  5179.5  235.34    5193  235.53  5377.3  234.94    5525  232.03
  5546.2   226.8  5576.8  232.52  5710.3  236.97  5873.2   240.8  6674.2  245.57
#Mann= 13 ,-1 , 0
  3799.8     .12       0  4225.1     .05       0  4507.4     .12       0
  4749.5     .05       0  4849.6      .1       0  4926.7     .12       0
  4980.2     .07       0 5013.71     .12       0  5179.5     .05       0
    5193     .12       0  5377.3     .05       0  5710.3     .12       0
  5873.2     .05       0
Bank Sta=4980.2,5013.71
XS Rating Curve= 0 ,0
Exp/Cntr=0.3,0.1

Type RM Length L Ch R = 1 ,13519   ,519,519,519
BEGIN DESCRIPTION:
Crystal Creek 046 25.0
END DESCRIPTION:
XS GIS Cut Line= 3
      3838786.69     10130034.31      3837676.39     10129907.74
      3835688.35     10130105.03
#Sta/Elev= 30
  3882.5  260.73    3982  260.34  4062.5  257.36  4082.6  258.06  4243.7  248.44
  4283.9  244.53  4465.1  238.48  4597.8   236.1  4616.7  235.74  4696.7  234.03
  4719.5  233.65  4904.7   228.3  4978.4  227.44  4988.5  225.49    4995  222.62
  5008.6  225.67  5129.2  230.59  5208.1  229.42  5340.2  226.11  5360.3  223.65
  5391.4  227.83    5511  232.33  5661.8     241  5789.5  241.73  5896.2  241.22
  5933.1  239.35  6229.2  242.05    6536  242.26  6656.4  244.52  6997.8  247.86
#Mann= 13 ,-1 , 0
  3882.5     .12       0  4597.8     .05       0  4616.7     .12       0
  4696.7     .05       0  4719.5      .1       0  4904.7     .05       0
  4988.5     .07       0  5008.6     .05       0  5208.1      .1       0
  5391.4     .12       0  5789.5     .05       0  6229.2     .12       0
  6656.4     .05       0
Bank Sta=4988.5,5008.6
XS Rating Curve= 0 ,0
Exp/Cntr=0.3,0.1

Type RM Length L Ch R = 1 ,13000   ,616,616,616
BEGIN DESCRIPTION:
Crystal Creek 046 24.0
END DESCRIPTION:
XS GIS Cut Line= 3
      3838799.58     10129931.47      3837604.14     10129608.86
      3835836.26     10129783.62
#Sta/Elev= 30
  3761.8  259.03    3970  254.48  4157.2  246.21  4385.1  238.93  4603.9  234.69
  4729.7  232.29  4856.8  227.52  4944.4  225.78  4970.1  222.73  4976.5  221.97
  4985.8  223.21  5006.3   221.6  5046.5  226.91  5090.2  224.95  5126.9  224.98
  5187.2  228.15  5267.6  223.84    5307  223.37  5317.8  223.29  5336.2  220.59
    5348  221.32  5354.1 223.406  5368.1  226.28  5408.3   226.9  5538.9  236.27
  5599.2  238.96  6118.5  241.66  6252.4  241.55  6700.4     248  6776.5   248.7
#Mann= 10 ,-1 , 0
  3761.8     .12       0  4603.9     .05       0  4729.7      .1       0
  4970.1     .05       0  5090.2      .1       0    5307     .05       0
  5317.8     .07       0  5354.1     .05       0  6118.5     .12       0
  6700.4     .05       0
Bank Sta=5317.8,5354.1
XS Rating Curve= 0 ,0
Exp/Cntr=0.3,0.1

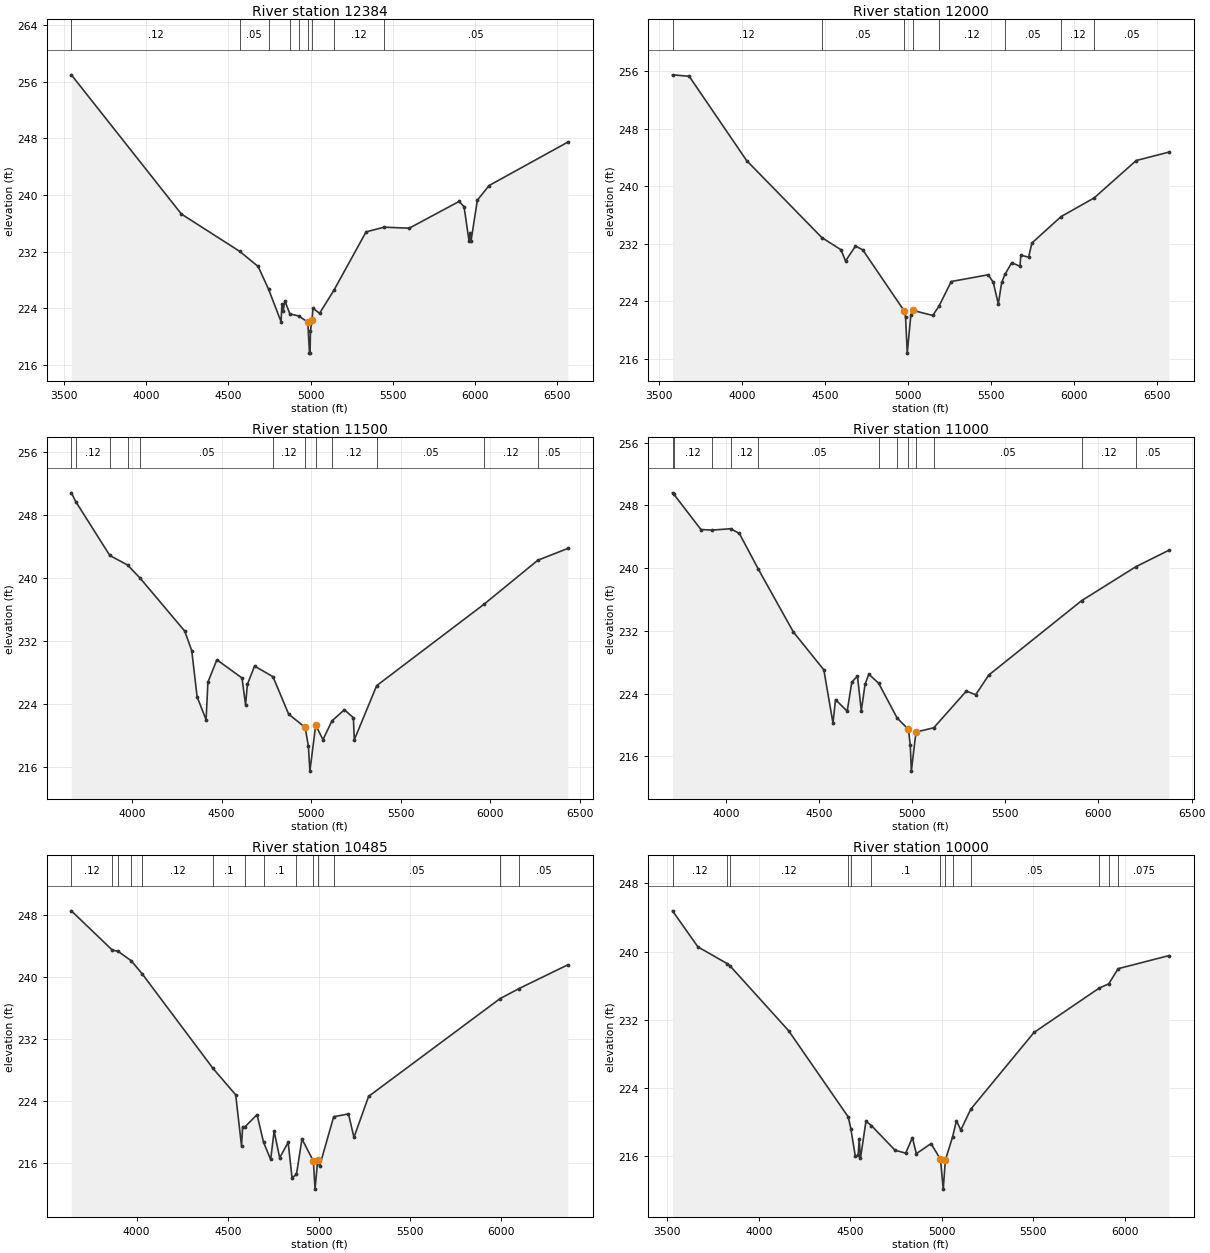
Type RM Length L Ch R = 1 ,12384   ,384,384,384
BEGIN DESCRIPTION:
Crystal Creek 046 23.0
END DESCRIPTION:
XS GIS Cut Line= 3
      3838818.87     10129815.77      3837462.46     10129292.92
      3835913.41     10129507.21
#Sta/Elev= 30
  3546.3  256.96    4215  237.31  4568.8  232.05  4681.7   229.9  4744.9   226.7
  4820.9  222.11  4826.3  224.61  4833.5  223.56  4844.2  225.06  4874.3  223.21
    4929  222.91  4983.5  222.05  4993.7  217.67  4997.2  217.67  4999.8  220.83
 5009.34 222.293  5014.7  224.02  5055.1  223.29  5143.3  226.59  5337.8  234.79
  5447.3  235.45  5600.3  235.31  5903.4  239.09  5933.4  238.34  5963.7  233.49
  5970.2  234.69  5975.3  233.44  6014.2  239.26  6084.8  241.32  6563.8  247.46
#Mann= 9 ,-1 , 0
  3546.3     .12       0  4568.8     .05       0  4744.9      .1       0
  4874.3     .05       0    4929      .1       0  4983.5     .07       0
 5009.34      .1       0  5143.3     .12       0  5447.3     .05       0
Bank Sta=4983.5,5009.34
XS Rating Curve= 0 ,0
Exp/Cntr=0.3,0.1

Type RM Length L Ch R = 1 ,12000   ,500,500,500
BEGIN DESCRIPTION:
Crystal Creek 046 22.0
END DESCRIPTION:
XS GIS Cut Line= 3
      3838889.53     10129745.04       3837646.5       10129065.
      3836093.41       10128813.
#Sta/Elev= 30
  3583.1  255.51  3683.5  255.31  4029.6  243.57  4482.6  232.85  4597.8  231.16
  4625.4  229.59  4685.1  231.66  4728.7  231.15  4979.1  222.63  4987.1  221.77
  4997.1  216.76  5018.9  222.08    5029  222.72  5150.6  222.01  5188.5  223.31
    5262  226.73  5484.9  227.67  5515.3  226.62  5545.7  223.61    5566  226.61
  5585.8  227.73  5626.7  229.36  5676.2  228.85  5681.3  230.39    5728  230.13
  5748.3   232.1  5924.3  235.78    6123  238.37  6376.4  243.58  6573.4  244.75
#Mann= 8 ,-1 , 0
  3583.1     .12       0  4482.6     .05       0  4979.1     .07       0
    5029      .1       0  5188.5     .12       0  5585.8     .05       0
  5924.3     .12       0    6123     .05       0
Bank Sta=4979.1,5029
XS Rating Curve= 0 ,0
Exp/Cntr=0.3,0.1

Type RM Length L Ch R = 1 ,11500   ,500,500,500
BEGIN DESCRIPTION:
Crystal Creek 046 21.0
END DESCRIPTION:
XS GIS Cut Line= 3
       3838928.4     10128723.99       3837592.3     10128813.65
      3836188.86     10128526.08
#Sta/Elev= 30
  3660.9  250.81  3685.7  249.69  3875.5  242.87  3974.6  241.66  4044.2  240.01
  4293.6  233.29    4333  230.81    4363  224.96  4413.1  222.04  4423.2   226.8
  4473.3  229.64  4613.6  227.34  4633.6  223.93  4643.7  226.53  4683.7  228.85
  4786.7   227.5  4874.2  222.75  4966.1  221.08  4984.4   218.7  4992.7  215.53
    5025  221.35  5065.8  219.52  5115.6  221.89  5185.2  223.31  5235.6   222.3
  5240.7   219.5  5365.7  226.37  5965.2  236.69    6265  242.26  6432.6  243.76
#Mann= 12 ,-1 , 0
  3660.9     .05       0  3685.7     .12       0  3875.5     .05       0
  3974.6     .12       0  4044.2     .05       0  4786.7     .12       0
  4966.1     .07       0    5025      .1       0  5115.6     .12       0
  5365.7     .05       0  5965.2     .12       0    6265     .05       0
Bank Sta=4966.1,5025
XS Rating Curve= 0 ,0
Exp/Cntr=0.3,0.1

Type RM Length L Ch R = 1 ,11000   ,515,515,515
BEGIN DESCRIPTION:
Crystal Creek 046 20.0
END DESCRIPTION:
XS GIS Cut Line= 3
      3838928.45      10128661.5       3837658.3     10128462.09
      3836282.74     10128380.25
#Sta/Elev= 30
  3714.3  249.61  3719.8  249.48  3866.7  244.93  3926.8  244.86  4026.1  245.03
    4073  244.43  4175.4  239.85  4362.7  231.87  4526.4  227.03  4575.3  220.25
    4589  223.24  4651.6  221.76  4676.5  225.49  4706.9  226.23  4727.2  221.82
  4747.4  225.18  4767.6  226.48  4820.4  225.33  4919.7  220.89  4980.2  219.45
  4990.3  217.39  4995.9  214.12  5020.5   219.1  5116.1  219.65    5291  224.33
  5341.1  223.86  5411.2  226.37  5910.2  235.87  6202.3  240.21    6378  242.29
#Mann= 12 ,-1 , 0
  3714.3     .05       0  3719.8     .12       0  3926.8     .05       0
  4026.1     .12       0  4175.4     .05       0  4820.4     .12       0
  4919.7      .1       0  4980.2     .07       0  5020.5      .1       0
  5116.1     .05       0  5910.2     .12       0  6202.3     .05       0
Bank Sta=4980.2,5020.5
XS Rating Curve= 0 ,0
Exp/Cntr=0.3,0.1

Type RM Length L Ch R = 1 ,10485   ,485,485,485
BEGIN DESCRIPTION:
Crystal Creek 046 19.0
END DESCRIPTION:
XS GIS Cut Line= 3
      3838933.63     10128588.58      3837659.05     10128122.58
      3836298.23     10128203.16
#Sta/Elev= 30
  3642.9  248.51  3867.2  243.45  3898.8  243.29  3970.8  242.08  4030.4  240.41
    4418  228.24  4543.4   224.8  4575.4  218.22  4581.4  220.71  4592.5  220.64
  4660.6  222.25  4696.1  218.68  4735.1  216.47    4754  220.12  4784.5  216.69
  4830.9  218.68  4852.2   214.1  4876.4  214.55  4906.6  219.11  4969.3  216.26
  4978.2  212.65  4992.9  216.45  5003.1  215.61  5080.5  221.98  5161.5  222.34
  5191.5  219.32  5271.7   224.6  5991.6  237.19  6096.4   238.5  6363.2  241.55
#Mann= 14 ,-1 , 0
  3642.9     .12       0  3867.2     .05       0  3898.8     .12       0
  3970.8     .05       0  4030.4     .12       0    4418      .1       0
  4592.5     .12       0  4696.1      .1       0  4876.4     .12       0
  4969.3     .07       0  4992.9     .12       0  5080.5     .05       0
  5991.6     .12       0  6096.4     .05       0
Bank Sta=4969.3,4992.9
XS Rating Curve= 0 ,0
Exp/Cntr=0.3,0.1

Type RM Length L Ch R = 1 ,10000   ,500,500,500
BEGIN DESCRIPTION:
Crystal Creek 046 18.0
END DESCRIPTION:
XS GIS Cut Line= 3
      3838886.76     10128474.01      3837628.19     10127712.14
      3836397.12     10127880.25
#Sta/Elev= 30
  3528.8  244.78  3667.8  240.55  3827.1   238.6  3843.1  238.33  4163.3  230.73
  4489.3  220.62  4503.5  219.25    4528  216.02  4543.5  216.13  4549.3  218.04
  4556.2  215.75  4586.2   220.1  4616.2   219.6  4745.2  216.71  4803.4  216.37
  4840.3  218.19  4861.6  216.31    4942  217.49  4993.5  215.66  5008.7  212.15
  5020.5  215.57  5059.7  218.26  5081.1  220.18  5104.6  219.08  5159.8  221.54
    5505  230.52  5860.5  235.71  5913.3  236.22  5965.2     238  6242.5  239.53
#Mann= 13 ,-1 , 0
  3528.8     .12       0  3827.1     .05       0  3843.1     .12       0
  4489.3      .1       0  4503.5     .12       0  4616.2      .1       0
  4993.5     .07       0  5020.5      .1       0  5059.7     .12       0
  5159.8     .05       0  5860.5     .12       0  5913.3     .05       0
  5965.2    .075       0
Bank Sta=4993.5,5020.5
XS Rating Curve= 0 ,0
Exp/Cntr=0.3,0.1

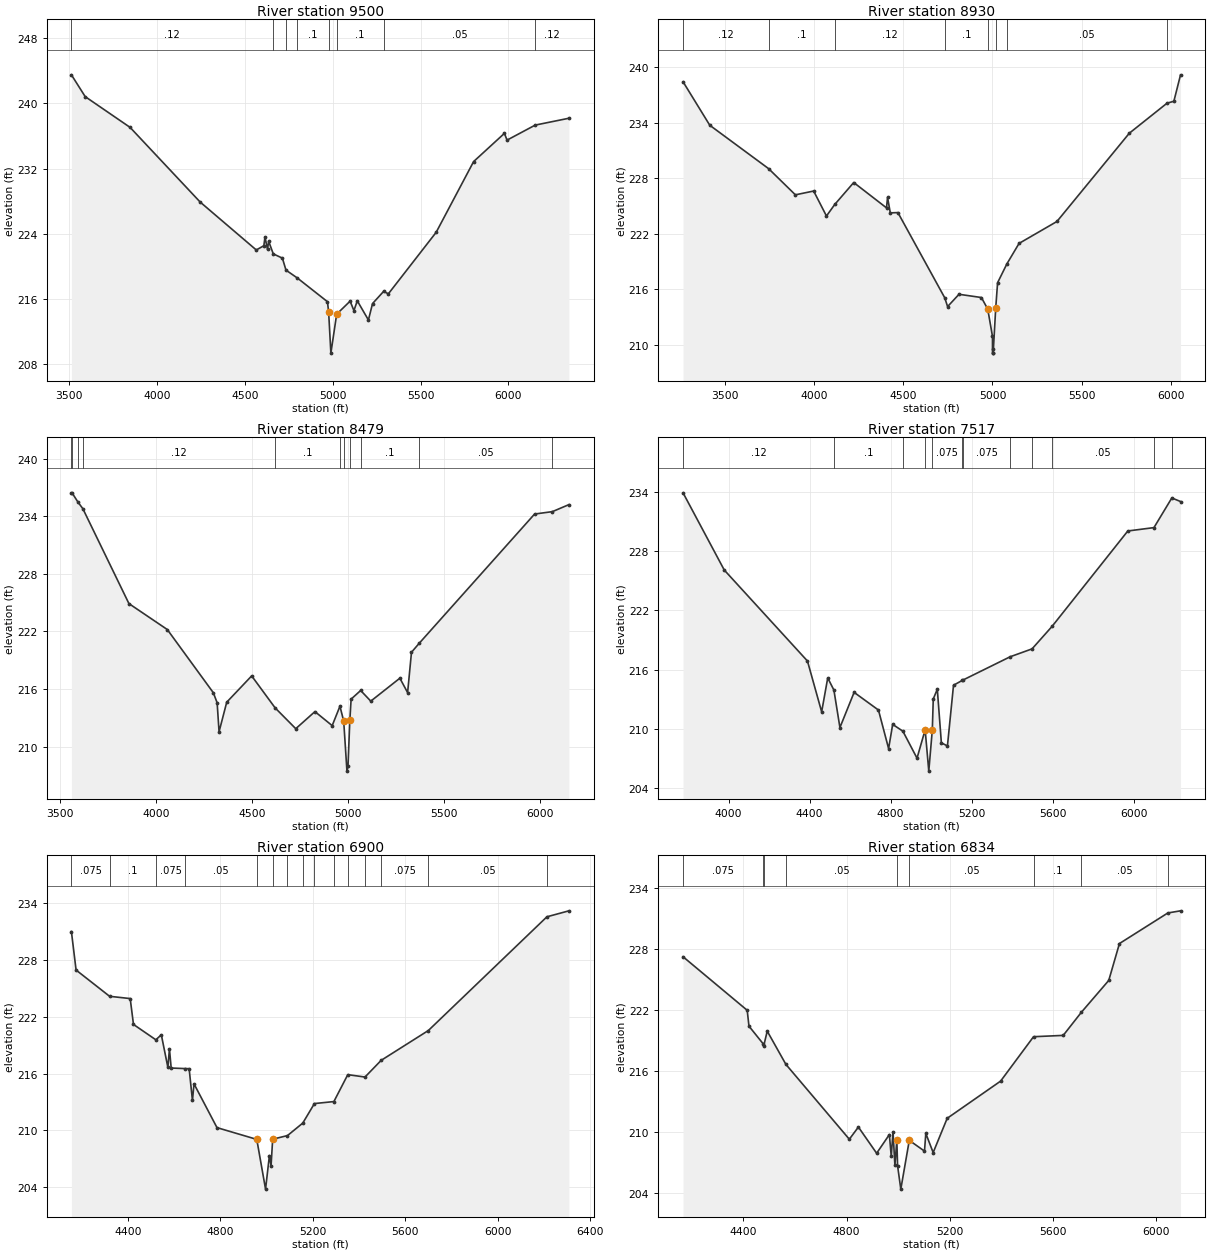
Type RM Length L Ch R = 1 ,9500    ,570,570,570
BEGIN DESCRIPTION:
Crystal Creek 046 17.0
END DESCRIPTION:
XS GIS Cut Line= 3
      3838964.87     10128364.62      3837814.75      10127421.6
      3836512.32     10127088.72
#Sta/Elev= 30
  3512.7  243.49  3591.1  240.82  3846.6  237.05  4245.6   227.9  4564.9  222.03
    4608  222.55  4614.5  223.63  4628.8  222.09  4635.3   223.1  4661.6  221.55
  4713.5  221.03    4734  219.56  4798.9  218.59  4970.1  215.69  4976.9  214.38
  4989.5  209.39  5022.5  214.16    5099  215.76  5120.7   214.6  5139.8   215.8
  5203.2  213.45  5226.6  215.46  5289.4  216.95  5316.8  216.66    5589   224.2
  5801.9  232.86  5977.3  236.32  5992.2  235.49  6152.5  237.33  6344.3  238.17
#Mann= 8 ,-1 , 0
  3512.7     .12       0  4661.6      .1       0    4734     .12       0
  4798.9      .1       0  4976.9     .07       0  5022.5      .1       0
  5289.4     .05       0  6152.5     .12       0
Bank Sta=4976.9,5022.5
XS Rating Curve= 0 ,0
Exp/Cntr=0.3,0.1

Type RM Length L Ch R = 1 ,8930    ,451,451,451
BEGIN DESCRIPTION:
Crystal Creek 046 16.0
END DESCRIPTION:
XS GIS Cut Line= 3
      3839230.46     10127984.39      3837755.35     10127076.52
      3836741.84     10126791.96
#Sta/Elev= 30
  3267.9  238.44  3417.5  233.74  3746.8  229.05  3896.7  226.22    3999  226.63
  4070.7  223.93  4117.1  225.18  4223.3  227.55  4406.8  224.81  4412.6  225.94
    4428  224.27  4470.6   224.3  4732.8  215.09  4748.7  214.14  4812.6  215.47
  4938.1  215.12  4973.6  213.86    5000  210.92  5000.1  209.61  5000.4  209.11
  5003.9  209.11  5018.2     214  5028.6  216.72  5080.8  218.76  5148.8  220.97
  5360.9  223.34    5766  232.88  5977.4  236.13  6015.3  236.33  6052.7  239.19
#Mann= 8 ,-1 , 0
  3267.9     .12       0  3746.8      .1       0  4117.1     .12       0
  4732.8      .1       0  4973.6     .07       0  5018.2     .12       0
  5080.8     .05       0  5977.4    .075       0
Bank Sta=4973.6,5018.2
XS Rating Curve= 0 ,0
Exp/Cntr=0.3,0.1

Type RM Length L Ch R = 1 ,8479    ,962,962,962
BEGIN DESCRIPTION:
Crystal Creek 046 15.0
END DESCRIPTION:
XS GIS Cut Line= 3
      3839317.83     10126761.07       3837875.5     10126788.97
      3836735.69     10126619.82
#Sta/Elev= 30
  3557.4  236.42  3560.7  236.43  3592.3  235.44    3617  234.78  3857.4  224.89
  4057.5  222.19  4297.5  215.61  4317.5  214.56  4327.5  211.54  4367.5  214.62
  4497.6  217.36  4619.9  214.03  4727.6  211.86  4827.6  213.64  4917.6  212.18
    4958   214.2  4977.6  212.66  4994.6  207.44    5000  207.94 5009.59 212.724
  5016.3  214.94  5066.1  215.84  5118.9  214.73  5270.6  217.12    5311  215.62
  5331.2  219.82  5371.6  220.76  5973.3  234.22  6065.9  234.47  6152.3   235.2
#Mann= 11 ,-1 , 0
  3557.4    .075       0  3560.7     .12       0  3592.3    .075       0
    3617     .12       0  4619.9      .1       0    4958    .075       0
  4977.6     .07       0 5009.59    .075       0  5066.1      .1       0
  5371.6     .05       0  6065.9      .1       0
Bank Sta=4977.6,5009.59
XS Rating Curve= 0 ,0
Exp/Cntr=0.3,0.1

Type RM Length L Ch R = 1 ,7517    ,617,617,617
BEGIN DESCRIPTION:
Crystal Creek 046 14.0
END DESCRIPTION:
XS GIS Cut Line= 3
       3839240.9     10126505.24       3838018.6     10126428.52
      3836787.75     10126380.24
#Sta/Elev= 30
  3775.3  233.88  3978.7  226.07  4389.6  216.86  4459.7  211.72  4489.7  215.15
  4520.2  213.92  4549.9  210.13    4620  213.69  4740.2   211.9  4790.3     208
  4810.4  210.45  4860.8  209.76  4930.6  207.03  4970.7   209.9  4988.7  205.72
 5006.15 209.906  5010.8  213.02  5030.8  214.01  5050.8  208.58  5080.8  208.27
  5110.8  214.41    5154   214.9  5158.7  214.95  5390.3  217.29  5498.6  218.09
  5597.2  220.36  5971.5  230.02  6100.5  230.36  6188.8  233.36  6231.8     233
#Mann= 12 ,-1 , 0
  3775.3     .12       0  4520.2      .1       0  4860.8    .075       0
  4970.7     .07       0 5006.15    .075       0    5154      .1       0
  5158.7    .075       0  5390.3      .1       0  5498.6    .075       0
  5597.2     .05       0  6100.5    .075       0  6188.8      .1       0
Bank Sta=4970.7,5006.15
XS Rating Curve= 0 ,0
Exp/Cntr=0.3,0.1

Type RM Length L Ch R = 1 ,6900    ,66,66,66
BEGIN DESCRIPTION:
Crystal Creek 046 13.0
END DESCRIPTION:
XS GIS Cut Line= 4
      3838602.91      10125437.2      3837973.33     10125999.45
      3837605.96     10126363.22      3836817.78     10126306.72
#Sta/Elev= 30
  4155.9  230.98  4176.1  226.92    4321  224.15  4410.1  223.91  4424.3  221.18
    4521  219.56  4544.7  220.09  4573.1  216.64  4579.8  218.61  4587.3  216.58
  4648.4  216.52    4665  216.51  4679.3  213.16    4686  214.91  4785.4  210.29
 4957.51 209.049  4995.4   203.8  5012.1  207.34  5019.2  206.26  5026.2  209.07
  5090.2  209.45  5156.4  210.77  5206.7  212.83  5290.9  213.04    5351  215.88
  5425.5  215.63  5495.3  217.39  5699.5  220.54  6212.1  232.54  6307.2  233.17
#Mann= 15 ,-1 , 0
  4155.9    .075       0    4321      .1       0    4521    .075       0
  4648.4     .05       0 4957.51     .07       0  5026.2     .05       0
  5090.2    .075       0  5156.4     .05       0  5206.7    .075       0
  5290.9      .1       0    5351     .05       0  5425.5      .1       0
  5495.3    .075       0  5699.5     .05       0  6212.1    .075       0
Bank Sta=4957.51,5026.2
XS Rating Curve= 0 ,0
Exp/Cntr=0.3,0.1

Type RM Length L Ch R = 1 ,6834    ,334,334,334
BEGIN DESCRIPTION:
Mapping XS 71e46563
END DESCRIPTION:
XS GIS Cut Line= 3
      3838532.03     10125393.59      3837920.19     10125960.93
      3836855.85     10126223.68
#Sta/Elev= 30
  4165.6  227.25  4414.6  221.98  4421.4  220.42  4476.9  218.67  4478.4  218.45
  4492.3  219.93  4564.7  216.66  4810.9  209.29  4846.1  210.49  4916.9  207.91
  4966.3  209.75  4973.6   207.6  4980.4  210.03  4987.8  206.73 4995.25 209.219
  4998.2  206.67  5010.7  204.38  5043.6  209.18  5102.6  208.12  5107.7  209.86
  5136.3  207.98  5190.7  211.35    5398  215.01  5525.8  219.38    5641  219.51
  5711.6  221.79  5817.7  224.92  5859.2  228.55    6047  231.56  6096.3  231.77
#Mann= 9 ,-1 , 0
  4165.6    .075       0  4476.9      .1       0  4478.4    .075       0
  4564.7     .05       0 4995.25     .07       0  5043.6     .05       0
  5525.8      .1       0  5711.6     .05       0    6047    .075       0
Bank Sta=4995.25,5043.6
XS Rating Curve= 0 ,0
Exp/Cntr=0.3,0.1

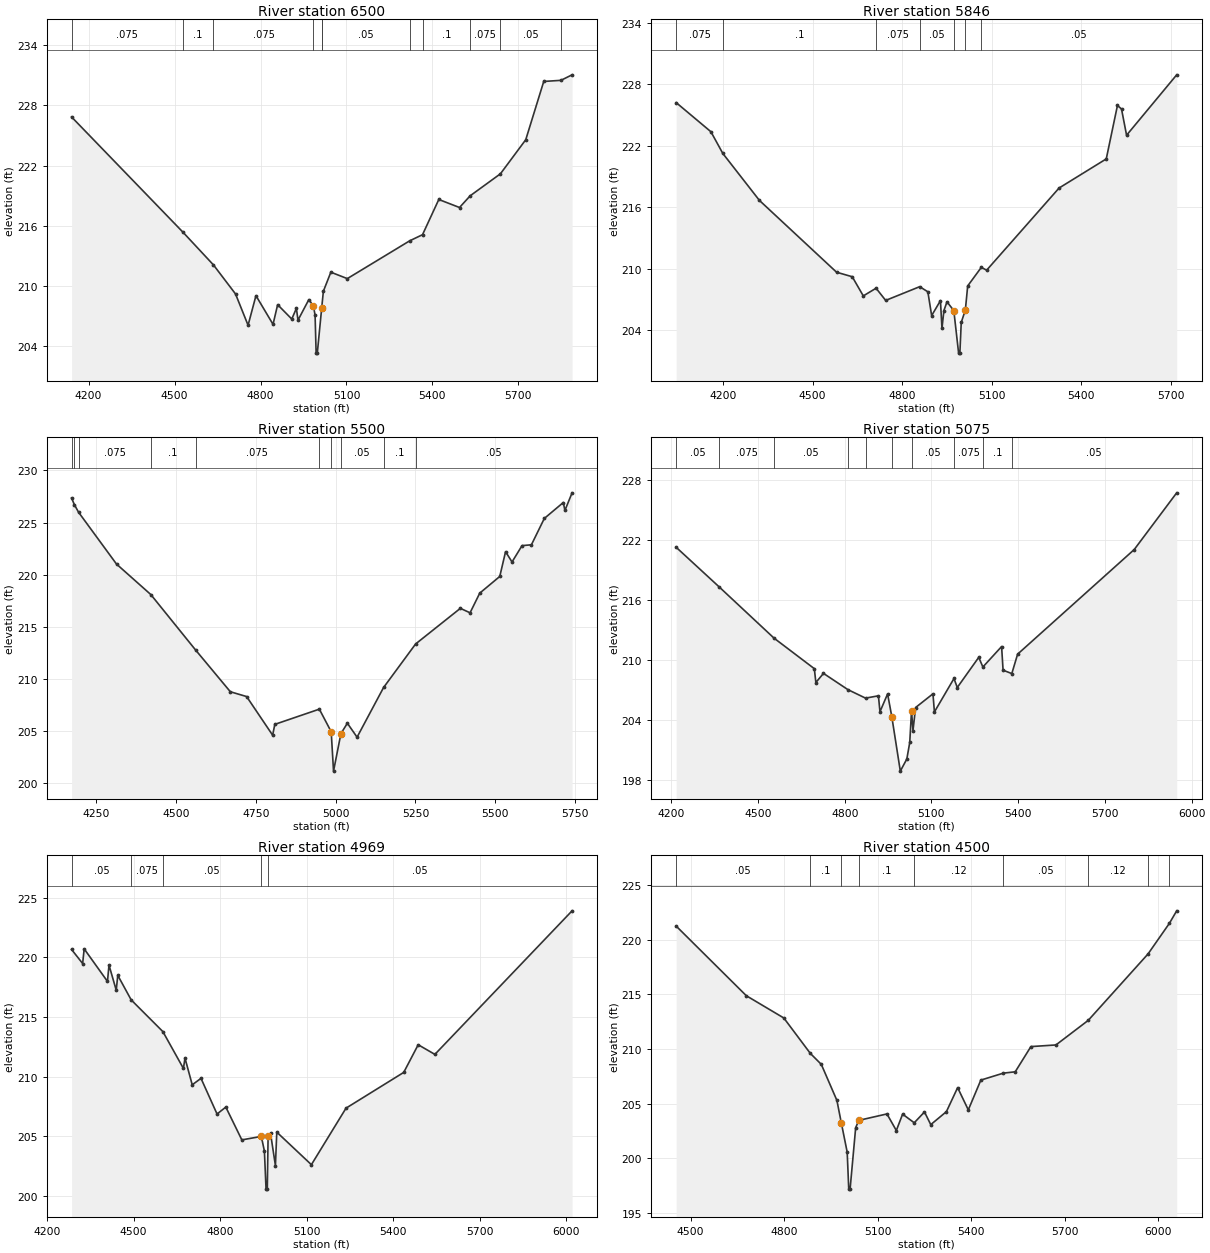
Type RM Length L Ch R = 1 ,6500    ,654,654,654
BEGIN DESCRIPTION:
Crystal Creek 046 12.0
END DESCRIPTION:
XS GIS Cut Line= 3
      3838499.26     10125347.28      3837746.19     10125761.55
      3836905.73     10126046.67
#Sta/Elev= 30
  4140.5  226.85  4528.6  215.38  4635.9  212.09  4712.8   209.2  4756.6  206.08
  4784.1  209.03  4843.7  206.17  4859.8  208.13  4909.1   206.7  4925.2  207.76
  4930.9  206.59  4968.7  208.64  4984.8  207.99  4990.5  207.08  4994.1   203.3
  4998.2   203.3  5013.4  207.75  5019.4  209.47  5045.5  211.37    5103  210.73
  5320.8   214.5  5365.5  215.11  5422.3  218.62  5494.6  217.82  5531.9  218.99
  5637.4  221.18  5725.8  224.58  5788.6  230.39  5848.5   230.5  5887.5  231.05
#Mann= 11 ,-1 , 0
  4140.5    .075       0  4528.6      .1       0  4635.9    .075       0
  4984.8     .07       0  5013.4    .075       0  5013.4     .05       0
  5320.8    .075       0  5365.5      .1       0  5531.9    .075       0
  5637.4     .05       0  5848.5    .075       0
Bank Sta=4984.8,5013.4
XS Rating Curve= 0 ,0
Exp/Cntr=0.3,0.1

Type RM Length L Ch R = 1 ,5846    ,346,346,346
BEGIN DESCRIPTION:
Crystal Creek 046 11.0
END DESCRIPTION:
XS GIS Cut Line= 3
      3838461.11     10125270.94       3837529.9     10125491.62
      3836823.13     10125632.61
#Sta/Elev= 30
    4043  226.21  4159.4  223.37  4199.4  221.25  4322.1  216.67  4580.6  209.67
  4633.1  209.23  4670.2  207.36    4713  208.11  4745.2  206.92  4859.2  208.26
  4886.6  207.76  4899.3  205.44  4928.8   206.9  4933.9  204.19  4940.4  205.93
  4950.7  206.78  4973.6  205.93  4989.7  201.78  4993.9  201.78  4998.5  204.77
  5012.3  205.99  5020.1  208.33  5065.7  210.14  5083.7  209.87  5326.4  217.88
  5484.6  220.72  5522.1  225.93  5535.7  225.59  5552.7  223.03  5720.7  228.92
#Mann= 7 ,-1 , 0
    4043    .075       0  4199.4      .1       0    4713    .075       0
  4859.2     .05       0  4973.6     .07       0  5012.3      .1       0
  5065.7     .05       0
Bank Sta=4973.6,5012.3
XS Rating Curve= 0 ,0
Exp/Cntr=0.3,0.1

Type RM Length L Ch R = 1 ,5500    ,425,425,425
BEGIN DESCRIPTION:
Crystal Creek 046 10.0
END DESCRIPTION:
XS GIS Cut Line= 3
      3838426.06     10125075.77      3837614.39     10125231.62
      3836881.89     10125339.51
#Sta/Elev= 30
  4173.5  227.35  4182.4  226.71  4195.3  225.99  4314.2  221.01  4421.7  218.08
  4561.5  212.77  4670.6  208.75  4721.5  208.29    4803  204.58  4809.8  205.62
  4949.2  207.08  4986.3  204.91  4993.6  201.13  5016.7  204.73  5036.9  205.73
  5067.3  204.39  5150.3  209.16  5250.6  213.34  5390.7  216.76    5421  216.33
  5451.4  218.22    5514  219.82  5532.2   222.2  5552.4  221.21  5583.7  222.78
  5613.1  222.86  5653.5  225.39  5712.9  226.92    5718  226.16  5740.4  227.85
#Mann= 10 ,-1 , 0
  4173.5    .075       0  4182.4      .1       0  4195.3    .075       0
  4421.7      .1       0  4561.5    .075       0  4949.2     .07       0
  4986.3     .03       0  5016.7     .05       0  5150.3      .1       0
  5250.6     .05       0
Bank Sta=4986.3,5016.7
XS Rating Curve= 0 ,0
Exp/Cntr=0.3,0.1

Type RM Length L Ch R = 1 ,5075    ,106,106,106
BEGIN DESCRIPTION:
Mapping XS 764d4c44
END DESCRIPTION:
XS GIS Cut Line= 3
      3838495.57     10124675.24      3837752.65     10124921.92
      3836812.25     10125044.06
#Sta/Elev= 30
  4217.2  221.23  4366.8  217.25  4555.6  212.16    4695  209.11  4700.3  207.73
  4726.7  208.64    4811  207.02    4872  206.17  4916.7   206.4    4922  204.81
  4948.4  206.59  4962.9  204.33  4992.4  198.88  5014.9  200.09    5025  201.74
  5031.1  204.89  5036.2  202.93  5045.2  205.23  5105.3   206.6  5110.3  204.79
    5178  208.13  5189.4  207.23  5263.6  210.24    5278  209.28  5342.7  211.32
  5347.8  208.96    5378  208.62  5398.1  210.56  5801.5  221.01  5948.3  226.67
#Mann= 10 ,-1 , 0
  4217.2     .05       0  4366.8    .075       0  4555.6     .05       0
    4811    .075       0    4872     .05       0  4962.9     .07       0
  5031.1     .05       0    5178    .075       0    5278      .1       0
    5378     .05       0
Bank Sta=4962.9,5031.1
XS Rating Curve= 0 ,0
Exp/Cntr=0.3,0.1

Type RM Length L Ch R = 1 ,4969    ,469,469,469
BEGIN DESCRIPTION:
Crystal Creek 046 9.0
END DESCRIPTION:
XS GIS Cut Line= 3
      3838474.73     10124581.26       3837804.1     10124828.62
      3836784.61     10124823.87
#Sta/Elev= 30
  4285.2  220.66  4323.6  219.48  4328.9  220.71  4409.6  217.98  4414.9  219.35
    4440  217.24  4445.3  218.49  4491.8  216.43  4601.6  213.77  4672.8  210.68
  4678.2  211.55  4703.3  209.31  4733.7  209.85  4789.3  206.86  4819.7  207.44
  4875.2  204.69  4942.7  204.98  4953.4  203.75  4959.1  200.56  4963.4  200.56
 4966.21 204.986  4974.7  205.23  4991.6  202.53  4996.3  205.34  5116.2  202.61
  5236.2  207.35  5436.2  210.35  5486.3  212.67  5544.1  211.86  6019.5   223.9
#Mann= 5 ,-1 , 0
  4285.2     .05       0  4491.8    .075       0  4601.6     .05       0
  4942.7     .07       0 4966.21     .05       0
Bank Sta=4942.7,4966.21
XS Rating Curve= 0 ,0
Exp/Cntr=0.3,0.1

Type RM Length L Ch R = 1 ,4500    ,500,500,500
BEGIN DESCRIPTION:
Crystal Creek 046 8.0
END DESCRIPTION:
XS GIS Cut Line= 3
      3838482.55     10124486.43      3837936.93     10124515.68
      3836881.88     10124427.91
#Sta/Elev= 30
  4453.6  221.26  4678.6  214.88  4798.8  212.84  4883.7   209.6    4919  208.59
    4969  205.29  4983.1  203.24    5002  200.55    5007  197.16  5011.3  197.16
  5029.2  202.79  5039.2  203.46  5129.5  204.05  5159.6  202.53  5179.7  204.03
    5217  203.24  5249.9  204.23    5270  203.07  5320.2  204.26  5356.2  206.46
  5390.4  204.42  5430.6  207.15  5503.1  207.79  5540.9  207.91  5591.1  210.22
  5671.4  210.37  5774.9  212.62  5966.8  218.71  6035.4  221.52  6058.7  222.66
#Mann= 9 ,-1 , 0
  4453.6     .05       0  4883.7      .1       0  4983.1     .07       0
  5039.2      .1       0    5217     .12       0  5503.1     .05       0
  5774.9     .12       0  5966.8     .05       0  6035.4     .12       0
Bank Sta=4983.1,5039.2
XS Rating Curve= 0 ,0
Exp/Cntr=0.3,0.1

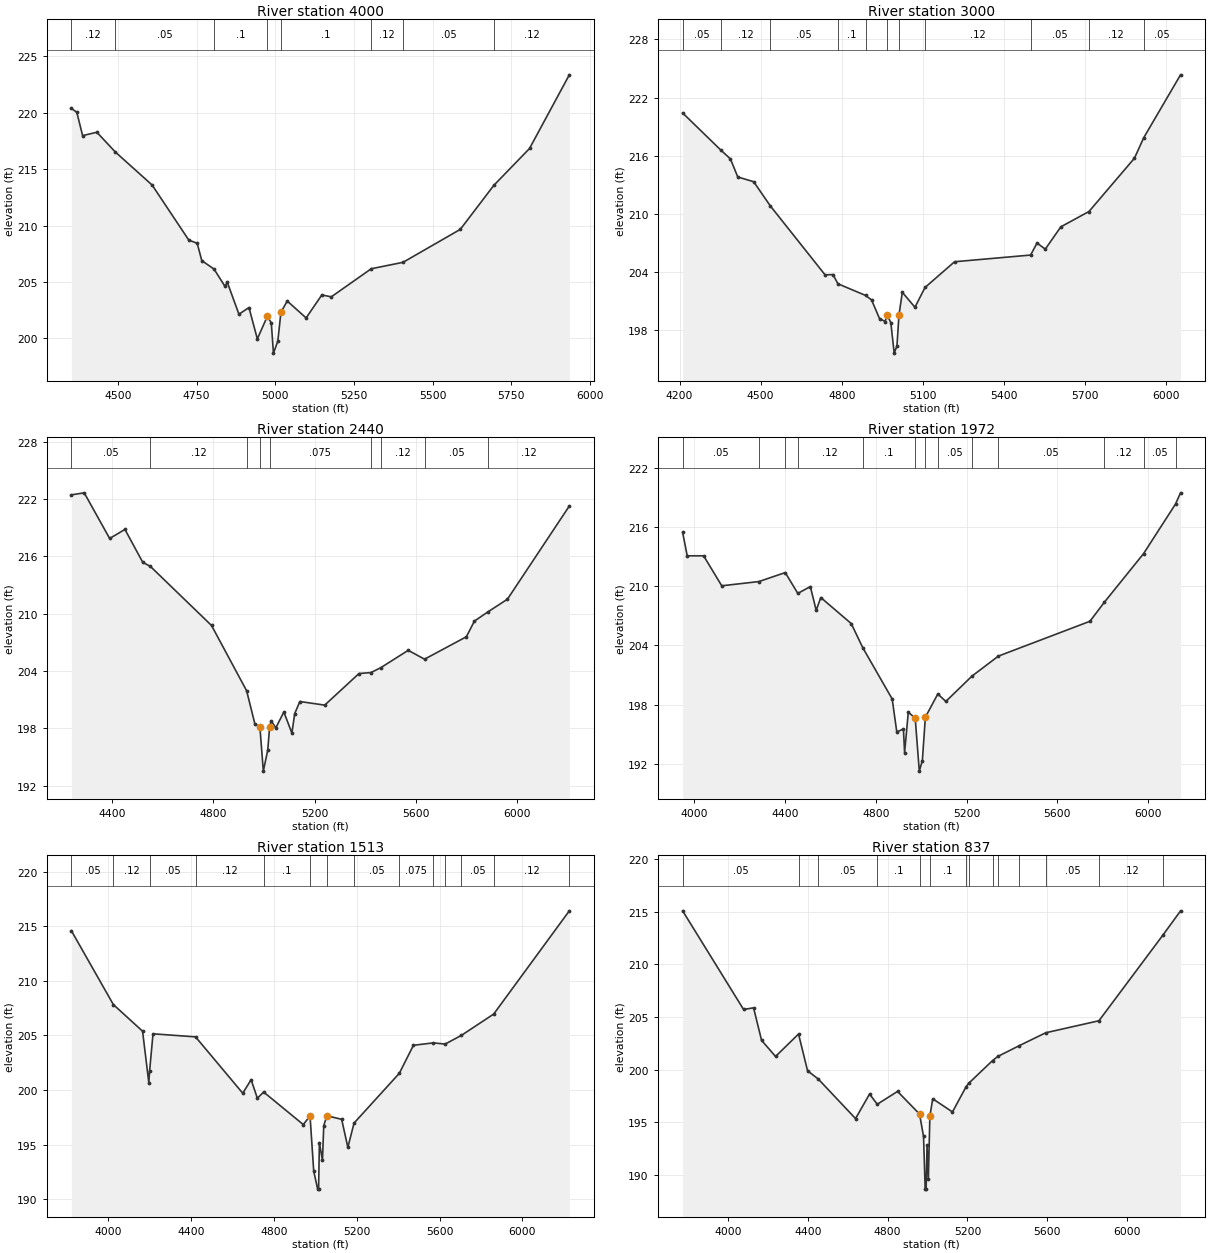
Type RM Length L Ch R = 1 ,4000    ,1000,1000,1000
BEGIN DESCRIPTION:
Crystal Creek 046 7.0
END DESCRIPTION:
XS GIS Cut Line= 3
      3838521.62     10124360.56      3837905.87      10124159.3
      3836971.37      10124160.9
#Sta/Elev= 30
  4352.2  220.39  4369.3  220.05  4387.7  217.98    4433  218.28  4491.3  216.54
  4608.7   213.6  4725.2  208.72  4751.8  208.44  4766.5   206.9  4805.4  206.15
  4840.1  204.62  4847.4  204.99  4884.5  202.15  4916.4  202.74    4943  199.96
  4974.9  201.97  4987.4  201.38  4994.2   198.7    5008  199.75    5018  202.32
    5038  203.32    5098  201.82    5148  203.86    5178  203.69  5305.1  206.18
    5406  206.75    5588  209.67  5694.5  213.57    5808  216.84  5934.5  223.37
#Mann= 8 ,-1 , 0
  4352.2     .12       0  4491.3     .05       0  4805.4      .1       0
  4974.9     .07       0    5018      .1       0  5305.1     .12       0
    5406     .05       0  5694.5     .12       0
Bank Sta=4974.9,5018
XS Rating Curve= 0 ,0
Exp/Cntr=0.3,0.1

Type RM Length L Ch R = 1 ,3000    ,560,560,560
BEGIN DESCRIPTION:
Crystal Creek 046 6.0
END DESCRIPTION:
XS GIS Cut Line= 3
      3838663.13     10124251.63      3838021.78     10123792.75
      3836986.07     10123987.72
#Sta/Elev= 30
  4211.4  220.41  4352.8  216.58  4388.3  215.67  4415.4  213.81  4474.3  213.32
  4536.1  210.82  4738.5  203.72    4768  203.75  4785.9   202.8  4888.2   201.6
  4910.5  201.14    4940  199.21  4960.9  198.91  4967.9   199.6  4981.8   198.8
  4994.3  195.65  5004.5  196.39 5011.98 199.573  5024.4  201.92  5071.1  200.38
  5108.4  202.42  5217.7  205.07    5499  205.76    5523     207  5553.4  206.37
    5611  208.67  5715.1  210.25  5883.5  215.75  5917.6  217.85  6053.9  224.34
#Mann= 11 ,-1 , 0
  4211.4     .05       0  4352.8     .12       0  4536.1     .05       0
  4785.9      .1       0  4888.2     .05       0  4967.9     .07       0
 5011.98     .05       0  5108.4     .12       0    5499     .05       0
  5715.1     .12       0  5917.6     .05       0
Bank Sta=4967.9,5011.98
XS Rating Curve= 0 ,0
Exp/Cntr=0.3,0.1

Type RM Length L Ch R = 1 ,2440    ,468,468,468
BEGIN DESCRIPTION:
Crystal Creek 046 5.0
END DESCRIPTION:
XS GIS Cut Line= 3
       3838917.9     10123511.08       3838161.7     10123427.47
      3837024.26       10123828.
#Sta/Elev= 30
  4239.2  222.45  4289.7  222.66  4390.2  217.88  4450.5  218.83    4521  215.38
    4551  214.96  4792.6  208.77  4931.3  201.93  4963.6  198.49  4983.8   198.1
  4997.2  193.52  5014.7  195.73 5022.01 198.146  5028.2  198.79  5046.5  198.05
  5078.3  199.71  5110.1   197.5  5121.1  199.54  5141.5  200.81  5239.6  200.43
  5375.1  203.74  5422.3  203.84  5461.1  204.35  5569.6  206.17    5634  205.24
  5799.2  207.59    5831  209.23  5885.2  210.21  5961.4  211.52  6205.9  221.28
#Mann= 9 ,-1 , 0
  4239.2     .05       0    4551     .12       0  4931.3      .1       0
  4983.8     .07       0 5022.01    .075       0  5422.3     .05       0
  5461.1     .12       0    5634     .05       0  5885.2     .12       0
Bank Sta=4983.8,5022.01
XS Rating Curve= 0 ,0
Exp/Cntr=0.3,0.1

Type RM Length L Ch R = 1 ,1972    ,459,459,459
BEGIN DESCRIPTION:
Crystal Creek 046 4.0
END DESCRIPTION:
XS GIS Cut Line= 3
      3839067.81     10122961.08       3838032.1     10123138.57
       3837042.2      10123709.6
#Sta/Elev= 30
  3949.2  215.46  3969.4  213.09  4041.7  213.09  4121.6  210.05  4285.2  210.48
  4401.3  211.39  4456.7  209.28  4511.9  209.97  4537.6  207.56  4557.9  208.86
    4692  206.22  4742.6  203.78  4872.4  198.57  4892.7  195.23    4922  195.52
  4927.1  193.12  4943.4  197.22  4973.9  196.63  4991.9  191.25  5005.3  192.31
  5018.6  196.72  5073.5  199.08  5108.8  198.32    5224  200.89  5340.5  202.92
  5743.8  206.45  5806.4  208.36  5979.9  213.31  6120.9  218.35  6142.8  219.48
#Mann= 13 ,-1 , 0
  3949.2     .05       0  4285.2     .12       0  4401.3     .05       0
  4456.7     .12       0  4742.6      .1       0  4973.9     .07       0
  5018.6      .1       0  5073.5     .05       0    5224    .075       0
  5340.5     .05       0  5806.4     .12       0  5979.9     .05       0
  6120.9     .12       0
Bank Sta=4973.9,5018.6
XS Rating Curve= 0 ,0
Exp/Cntr=0.3,0.1

Type RM Length L Ch R = 1 ,1513    ,676,676,676
BEGIN DESCRIPTION:
Crystal Creek 046 3.0
END DESCRIPTION:
XS GIS Cut Line= 3
      3839218.68     10122689.12        3838051.     10122825.37
      3837042.18     10123522.04
#Sta/Elev= 30
  3824.4  214.58  4026.5  207.83  4167.5  205.39  4197.7  200.67  4201.2   201.7
  4217.9  205.15  4423.1  204.87  4650.8  199.71  4691.1  200.95  4721.3  199.25
  4751.5  199.82  4942.8  196.84 4975.32 197.637  4993.1  192.58  5012.1  190.93
  5016.6  190.93  5020.4  195.19  5035.3  193.57  5041.4  196.73  5056.3  197.65
  5127.9  197.32  5157.7  194.75  5187.7  196.98  5406.2  201.54    5474   204.1
  5570.1  204.32    5627  204.21  5705.6  205.01  5861.3  206.96    6226  216.41
#Mann= 14 ,-1 , 0
  3824.4     .05       0  4026.5     .12       0  4201.2     .05       0
  4423.1     .12       0  4751.5      .1       0 4975.32     .07       0
  5056.3      .1       0  5187.7     .05       0  5406.2    .075       0
  5570.1     .05       0    5627    .075       0  5705.6     .05       0
  5861.3     .12       0    6226     .05       0
Bank Sta=4975.32,5056.3
XS Rating Curve= 0 ,0
Exp/Cntr=0.3,0.1

Type RM Length L Ch R = 1 ,837     ,697,697,697
BEGIN DESCRIPTION:
Crystal Creek 046 2.0
END DESCRIPTION:
XS GIS Cut Line= 3
      3839232.59     10122619.68       3838007.8     10122535.12
      3837038.13     10123352.31
#Sta/Elev= 30
  3772.3  215.09  4077.8  205.72  4127.9  205.88    4168  202.79  4238.1  201.26
  4353.3  203.39  4398.5   199.9    4452  199.12  4639.1  195.36  4709.3  197.69
  4747.9  196.72  4849.6  197.94  4959.9  195.79  4979.9  193.66  4988.2  188.66
  4992.8  188.66  4997.5  192.81    5004  189.63  5011.7   195.6    5026  197.24
  5124.9  195.99  5192.5  198.36  5206.2  198.71  5325.9  200.87  5352.2  201.26
  5459.2  202.28  5592.5  203.51  5859.1  204.65  6179.2  212.77  6268.1  215.08
#Mann= 14 ,-1 , 0
  3772.3     .05       0  4353.3     .12       0    4452     .05       0
  4747.9      .1       0  4959.9     .07       0  5011.7      .1       0
  5192.5     .05       0  5206.2      .1       0  5325.9    .075       0
  5352.2     .05       0  5459.2    .075       0  5592.5     .05       0
  5859.1     .12       0  6179.2      .1       0
Bank Sta=4959.9,5011.7
XS Rating Curve= 0 ,0
Exp/Cntr=0.3,0.1

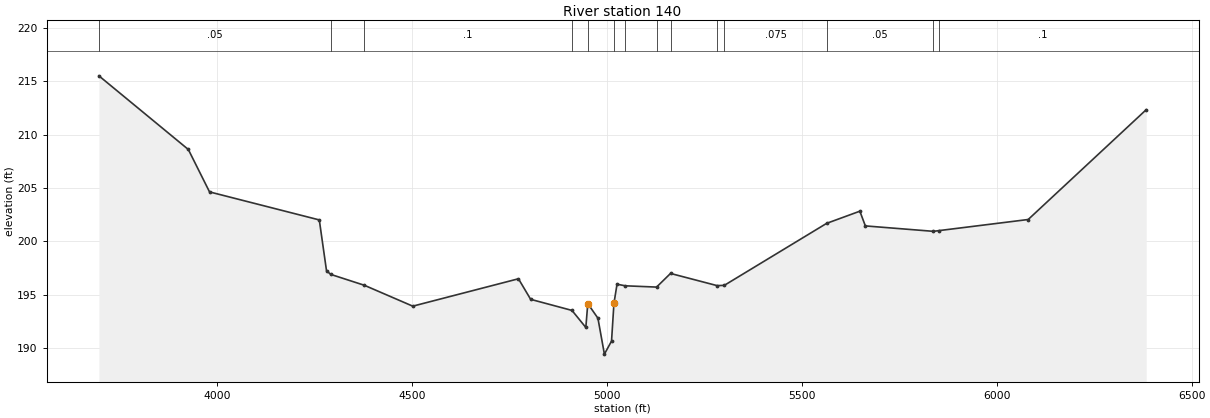
Type RM Length L Ch R = 1 ,140     ,0,0,0
BEGIN DESCRIPTION:
Crystal Creek 046 1.0
END DESCRIPTION:
XS GIS Cut Line= 4
      3839230.06      10122571.6      3838123.25     10122246.06
       3837975.4     10122261.07       3836968.7     10123209.93
#Sta/Elev= 30
  3697.7  215.53    3927  208.62  3981.4  204.64  4262.9  202.01  4281.4  197.24
  4292.3   196.9  4378.4  195.88  4502.6  193.92  4773.6  196.49  4804.9  194.56
  4910.9  193.52  4946.4  191.92  4951.4  194.16  4977.4  192.79    4994  189.42
  5012.3  190.64 5018.49 194.176  5026.4  195.98  5047.6  195.83  5127.8  195.71
  5163.6  196.99  5282.7  195.85  5301.4  195.87    5564  201.69  5649.1  202.83
  5663.2  201.45  5837.8  200.94  5852.4  201.01  6080.8  202.05  6383.4  212.35
#Mann= 14 ,-1 , 0
  3697.7     .05       0  4292.3     .12       0  4378.4      .1       0
  4910.9     .05       0  4951.4     .03       0 5018.49     .05       0
  5047.6    .075       0  5127.8     .05       0  5163.6    .075       0
  5282.7     .05       0  5301.4    .075       0    5564     .05       0
  5837.8     .12       0  5852.4      .1       0
Bank Sta=4951.4,5018.49
XS Rating Curve= 0 ,0
Exp/Cntr=0.3,0.1