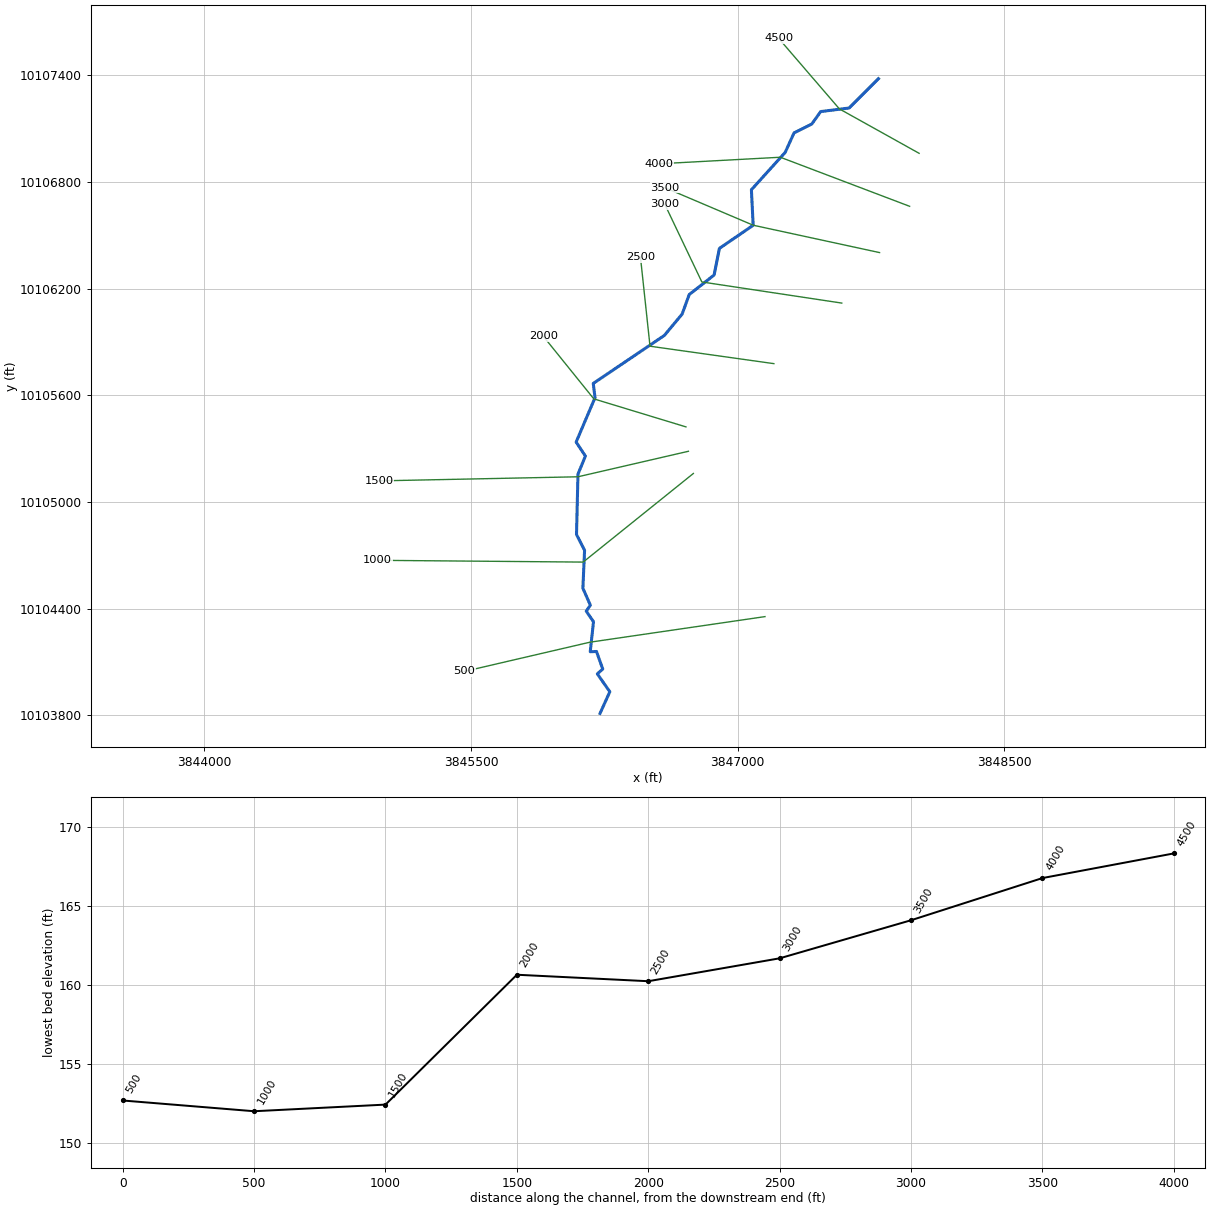
--- Crystal Creek 050.prj (project) ---

Proj Title=Crystal Creek 050 Base Level Engineering
Current Plan=p01
Default Exp/Contr=0.3,0.1
English Units
Geom File=g01
Flow File=f01
Flow File=f02
Plan File=p01
Y Axis Title=Elevation
X Axis Title(PF)=Main Channel Distance
X Axis Title(XS)=Station
BEGIN DESCRIPTION:
Crystal Creek 050
END DESCRIPTION:
DSS File=dss
DSS Export Rating Curves= 0
DSS Export Rating Curve Sorted= 0
DSS Export Volume Flow Curves= 0
DXF OffsetX= 0
DXF OffsetY= 0
DXF ScaleX= 1
DXF ScaleY= 10

--- Crystal Creek 050.p01 (plan) ---

Plan Title=Multiple Run
Program Version=4.10
Short Identifier=Multiple Run
Geom File=g01
Flow File=f01
Subcritical Flow
K Sum by GR= 0
Std Step Tol= 0.01
Critical Tol= 0.01
Num of Std Step Trials= 20
Max Error Tol= 0.3
Flow Tol Ratio= 0.001
Split Flow NTrial= 30
Split Flow Tol= 0.02
Split Flow Ratio= 0.02
Log Output Level= 0
Friction Slope Method= 1
Unsteady Friction Slope Method= 2
Unsteady Bridges Friction Slope Method= 1
Parabolic Critical Depth
Global Vel Dist= 1 , 1 , 1
Global Log Level= 0
CheckData=True
Encroach Param=-1 ,0,0, 0
BEGIN DESCRIPTION:
Multiple Run
END DESCRIPTION:
Computation Interval=1HOUR
Output Interval=1HOUR
Run HTab= 0
Run UNet= 0
Run PostProcess= 0
Run WQNet= 0
UNET Theta= 1
UNET Theta Warmup= 1
UNET ZTol= 0.02
UNET ZSATol= 0.05
UNET MxIter= 20
UNET MaxInSteps= 0
UNET DtIC= 0
UNET DtMin= 0
UNET MaxCRTS= 20
UNET WFStab= 2
UNET SFStab= 1
UNET WFX= 1
UNET SFX= 1
UNET DSS MLevel= 4
UNET DZMax Abort= 100
UNET Convert EG Bridges= 0
UNET Use Existing IB Tables=-1
UNET Froude Reduction=False
UNET Froude Limit= 1
UNET Froude Power= 10
UNET Time Slicing=0,0, 5
UNET Junction Losses=0
Instantaneous Interval=1HOUR
DSS File=dss
Write IC File= 0
Write IC File at Sim End=0
Echo Input=False
Echo Parameters=False
Echo Output=False
Write Detailed= 0
WQ AD Non Conservative
WQ ULTIMATE=-1
WQ Max Comp Step=1HOUR
WQ Output Interval=15MIN
WQ Output Selected Increments= 0
WQ Output face flow=0
WQ Output face velocity=0
WQ Output face area=0
WQ Output face dispersion=0
WQ Output cell volume=0
WQ Output cell surface area=0
WQ Output cell continuity=0
WQ Output cumulative cell continuity=0
WQ Output face conc=0
WQ Output face dconc_dx=0
WQ Output face courant=0
WQ Output face peclet=0
WQ Output face adv mass=0
WQ Output face disp mass=0
WQ Output cell mass=0
WQ Output cell source sink temp=0
WQ Output cell source sink nsm=0
WQ Output MaxMinRange=-1
WQ Daily Max Min Mean=-1
WQ Daily Range=0
WQ Daily Time=0
WQ Create Restart=0
WQ Fixed Restart=0
WQ System Summary=0
WQ Use Fixed Temperature=0
Sorting and Armoring Iterations= 10
XS Update Threshold= 0.02
Hydraulics Update Threshold= 0.02
Energy Slope Method= 1
Volume Change Method= 0
XS Weighting Method= 0
Number of US Weighted Cross Sections= 1
Number of DS Weighted Cross Sections= 1
Upstream XS Weight=0.25
Main XS Weight=0.5
Downstream XS Weight=0.25
Number of DS XS's Weighted with US Boundary= 1
Upstream Boundary Weight= 1
Weight of XSs Associated with US Boundary= 0
Number of US XS's Weighted with DS Boundary= 1
Downstream Boundary Weight= 0.5
Weight of XSs Associated with DS Boundary= 0.5
Sediment Output Level= 4
Mass or Volume Output= 0
Output Increment Type= 1
Profile and TS Output Increment= 10
XS Output Flag= 0
XS Output Increment= 10
Disregard all LS=0
Disregard all Conn=0
Disregard all Breaches=0
Disregard all Pumps=0

--- Crystal Creek 050.f01 (steady flow) ---

Flow Title=Multiple
Program Version=4.10
Number of Profiles= 7
Profile Names=10-year,25-year,50-year,1pct_min,100-year,1pct_plu,500-year
River Rch & RM=Crystal Creek 05,Reach-1         ,4500
     700     941    1266     561    1693    5113    3120
River Rch & RM=Crystal Creek 05,Reach-1         ,1500
    1667    2307    3160    1417    4280   12925    8122
River Rch & RM=Crystal Creek 05,Reach-1         ,1000
    1667    2307    3160    1417    4280   12925    8122
River Rch & RM=Crystal Creek 05,Reach-1         ,500
    1667    2307    3160    1417    4280   12925    8122
Boundary for River Rch & Prof#=Crystal Creek 05,Reach-1         , 1
Up Type= 0
Dn Type= 3
Dn Slope=0.0065
Boundary for River Rch & Prof#=Crystal Creek 05,Reach-1         , 2
Up Type= 0
Dn Type= 3
Dn Slope=0.0065
Boundary for River Rch & Prof#=Crystal Creek 05,Reach-1         , 3
Up Type= 0
Dn Type= 3
Dn Slope=0.0065
Boundary for River Rch & Prof#=Crystal Creek 05,Reach-1         , 4
Up Type= 0
Dn Type= 3
Dn Slope=0.0065
Boundary for River Rch & Prof#=Crystal Creek 05,Reach-1         , 5
Up Type= 0
Dn Type= 3
Dn Slope=0.0065
Boundary for River Rch & Prof#=Crystal Creek 05,Reach-1         , 6
Up Type= 0
Dn Type= 3
Dn Slope=0.0065
Boundary for River Rch & Prof#=Crystal Creek 05,Reach-1         , 7
Up Type= 0
Dn Type= 3
Dn Slope=0.0065
DSS Import GetInterval= 0
DSS Import GetPeak= 0
DSS Import FillOption= 0

--- Crystal Creek 050.f02 (steady flow) ---

Flow Title=Orig_BLE_Flow
Program Version=4.10
Number of Profiles= 7
Profile Names=10-year,25-year,50-year,1pct_min,100-year,1pct_plu,500-year
River Rch & RM=Crystal Creek 05,Reach-1         ,4500
     700     923    1101     431    1302    3931    1814
River Rch & RM=Crystal Creek 05,Reach-1         ,1500
    1667    2262    2748    1090    3292    9943    4722
River Rch & RM=Crystal Creek 05,Reach-1         ,1000
    1667    2262    2748    1090    3292    9943    4722
River Rch & RM=Crystal Creek 05,Reach-1         ,500
    1667    2262    2748    1090    3292    9943    4722
Boundary for River Rch & Prof#=Crystal Creek 05,Reach-1         , 1
Up Type= 0
Dn Type= 3
Dn Slope=0.007
Boundary for River Rch & Prof#=Crystal Creek 05,Reach-1         , 2
Up Type= 0
Dn Type= 3
Dn Slope=0.007
Boundary for River Rch & Prof#=Crystal Creek 05,Reach-1         , 3
Up Type= 0
Dn Type= 3
Dn Slope=0.007
Boundary for River Rch & Prof#=Crystal Creek 05,Reach-1         , 4
Up Type= 0
Dn Type= 3
Dn Slope=0.007
Boundary for River Rch & Prof#=Crystal Creek 05,Reach-1         , 5
Up Type= 0
Dn Type= 3
Dn Slope=0.007
Boundary for River Rch & Prof#=Crystal Creek 05,Reach-1         , 6
Up Type= 0
Dn Type= 3
Dn Slope=0.007
Boundary for River Rch & Prof#=Crystal Creek 05,Reach-1         , 7
Up Type= 0
Dn Type= 3
Dn Slope=0.007
DSS Import GetInterval= 0
DSS Import GetPeak= 0
DSS Import FillOption= 0

--- Crystal Creek 050.g01 (geometry) ---

Geom Title=Existing Conditions
Program Version=4.10

River Reach=Crystal Creek 05,Reach-1
Reach XY= 30
      3847793.24     10107381.86      3847628.24     10107216.86
      3847468.24     10107196.86      3847418.24     10107126.86
      3847318.24     10107076.86      3847268.24     10106966.86
      3847078.24     10106756.86      3847088.24     10106556.86
      3846898.24     10106426.86      3846868.24     10106276.86
      3846728.24     10106166.86      3846688.24     10106056.86
      3846588.24     10105936.86      3846188.24     10105666.86
      3846198.24     10105586.86      3846091.98     10105336.89
      3846144.04      10105258.1      3846102.27      10105156.3
      3846093.99     10104816.62       3846139.4     10104727.87
      3846129.89      10104514.2      3846172.05     10104418.86
      3846148.75     10104385.64      3846189.57     10104325.81
      3846171.36     10104157.04      3846206.38     10104158.39
      3846241.65     10104059.56       3846211.1     10104032.53
      3846281.52     10103931.82      3846226.47     10103810.11

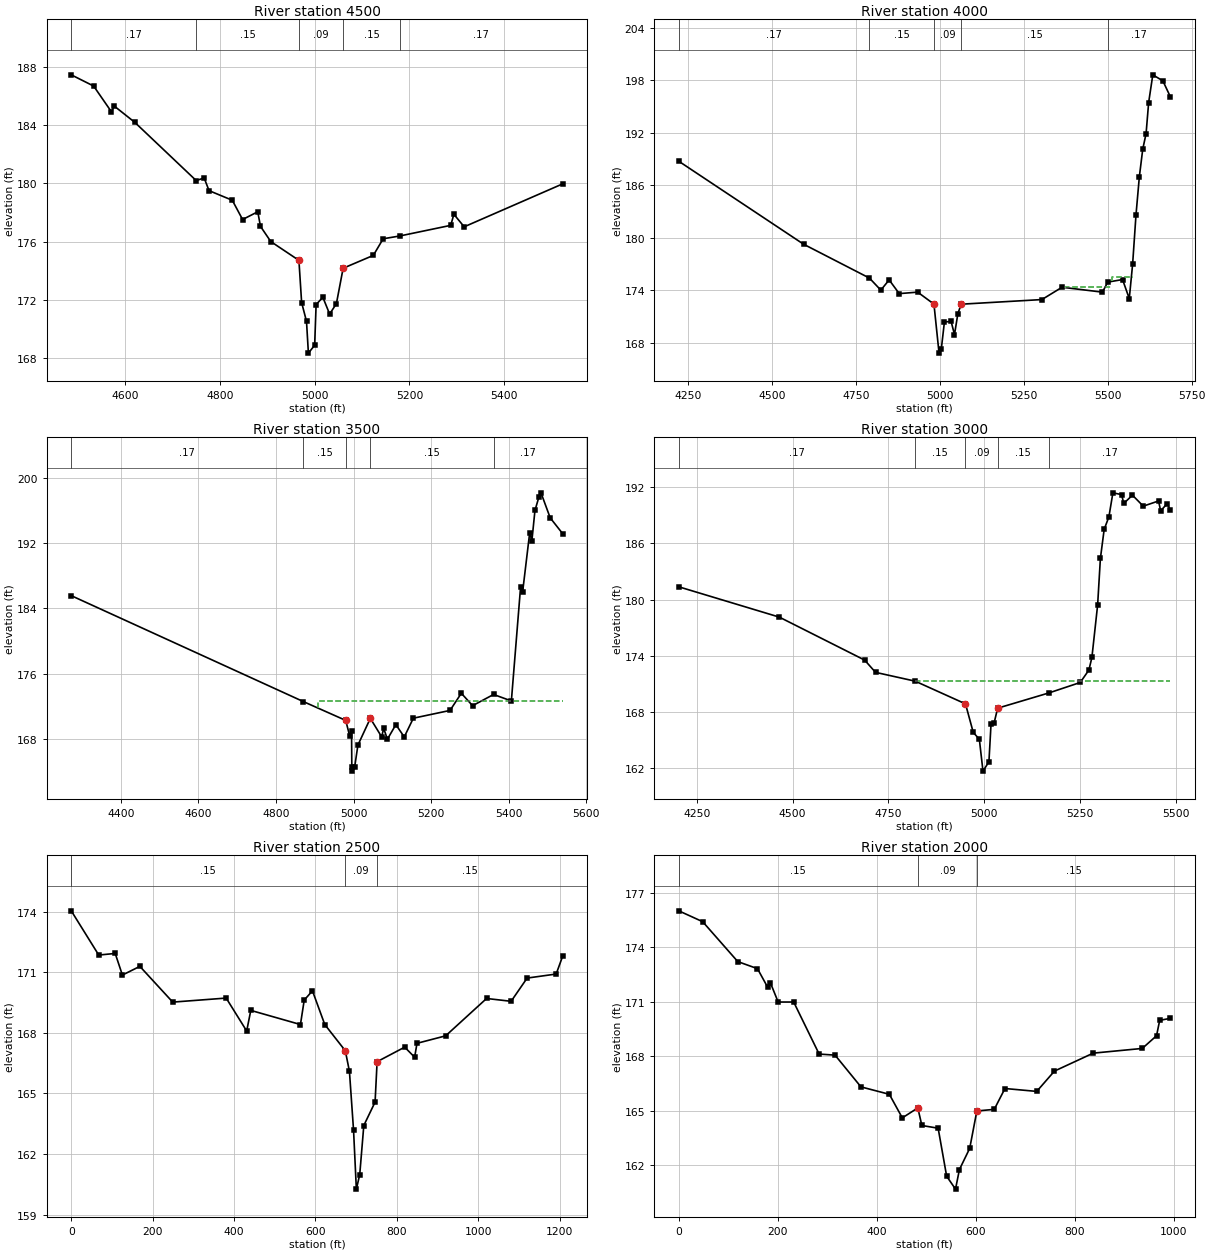
Type RM Length L Ch R = 1 ,4500    ,500,500,500
BEGIN DESCRIPTION:
Crystal Creek 050 9.0
END DESCRIPTION:
XS GIS Cut Line= 3
      3848022.01     10106961.87      3847573.26     10107211.89
      3847231.56     10107608.89
#Sta/Elev= 30
  4486.3  187.43  4533.6  186.66  4571.2  184.89    4577  185.29  4620.5  184.17
    4750  180.18  4766.8  180.36  4777.1  179.49  4826.2  178.83  4847.9  177.51
  4879.9  178.04  4885.7  177.04  4907.4     176  4966.8  174.71  4972.5  171.82
  4982.8  170.53  4986.8  168.35    5000  168.89  5003.1  171.68  5017.3  172.18
  5031.6  171.03  5045.9  171.74  5060.1  174.17  5123.8  175.05  5144.6  176.19
  5179.4  176.38  5287.2  177.11  5293.8  177.87  5315.6  177.01  5523.8  179.96
#Mann= 5 ,-1 , 0
  4486.3     .17       0    4750     .15       0  4966.8     .09       0
  5060.1     .15       0  5179.4     .17       0
Bank Sta=4966.8,5060.1
XS Rating Curve= 0 ,0
Exp/Cntr=0.3,0.1

Type RM Length L Ch R = 1 ,4000    ,500,500,500
BEGIN DESCRIPTION:
Crystal Creek 050 8.0
END DESCRIPTION:
XS GIS Cut Line= 3
      3847968.69     10106663.62      3847241.13     10106939.76
      3846555.53     10106902.72
#Sta/Elev= 30
  4221.8  188.75  4593.4  179.26  4789.8  175.38  4823.8     174  4848.6  175.17
  4878.7   173.6  4933.6  173.77  4982.1   172.4  4997.3  166.79  5004.1  167.29
  5013.3  170.36  5033.3  170.41  5043.3  168.91  5053.4  171.31  5063.3  172.39
  5303.7  172.92  5363.8  174.33    5484  173.77  5500.2  174.92  5544.1  175.21
  5564.1  173.03  5574.1  176.98  5584.1   182.6  5594.1  186.97  5604.2  190.12
  5614.2  191.92  5621.8  195.46  5634.2  198.64  5664.2  197.95  5686.6  196.12
#Mann= 5 ,-1 , 0
  4221.8     .17       0  4789.8     .15       0  4982.1     .09       0
  5063.3     .15       0  5500.2     .17       0
#XS Ineff= 3 ,-1
  4848.6  4768.9  175.17  5373.8    5514  174.35    5514  5574.1  175.47
Permanent Ineff=
       F       F       F
Bank Sta=4982.1,5063.3
XS Rating Curve= 0 ,0
Exp/Cntr=0.3,0.1

Type RM Length L Ch R = 1 ,3500    ,500,500,500
BEGIN DESCRIPTION:
Crystal Creek 050 7.0
END DESCRIPTION:
XS GIS Cut Line= 3
      3847799.45      10106403.2      3847088.24     10106557.23
      3846591.65     10106768.34
#Sta/Elev= 30
  4272.3  185.57  4870.7  172.62  4979.9  170.32  4989.8  168.47  4994.9  169.02
  4995.6  164.62  4995.9  164.12  5002.9  164.62  5011.3   167.3  5043.3  170.57
  5072.4  168.32  5077.8  169.34  5087.3  168.02  5109.1   169.8  5130.8   168.3
  5154.2  170.59  5248.8  171.54  5277.9  173.64  5306.9  172.12    5361  173.49
  5406.9   172.7  5430.6  186.59    5436  186.06  5454.2  193.29  5459.7  192.24
  5467.7  195.98  5477.9  197.63  5483.3  198.14    5507  195.08  5539.6  193.12
#Mann= 5 ,-1 , 0
  4272.3     .17       0  4870.7     .15       0  4979.9     .09       0
  5043.3     .15       0    5361     .17       0
#XS Ineff= 2 ,-1
  4908.3  4836.7  172.66  5277.9  5413.3  173.64
Permanent Ineff=
       F       F
Bank Sta=4979.9,5043.3
XS Rating Curve= 0 ,0
Exp/Cntr=0.3,0.1

Type RM Length L Ch R = 1 ,3000    ,500,500,500
BEGIN DESCRIPTION:
Crystal Creek 050 6.0
END DESCRIPTION:
XS GIS Cut Line= 3
      3847586.97     10106119.01      3846799.29     10106237.92
      3846590.44     10106675.76
#Sta/Elev= 30
  4203.4  181.36  4465.5  178.13  4687.9  173.55  4716.4  172.24  4819.8   171.3
  4950.9  168.88  4971.1  165.84    4987  165.11  4996.5  161.71    5012  162.71
  5017.5  166.73  5025.7  166.88  5034.7  168.42  5168.6  170.05    5250  171.16
  5272.7  172.49  5280.5  173.84  5295.4  179.42  5302.6  184.38  5312.5  187.49
  5324.8  188.82  5335.2  191.38  5357.9  191.19  5363.5  190.25  5386.2  191.13
  5414.4  189.96  5454.2  190.51  5459.8  189.46  5476.9  190.24  5485.1  189.51
#Mann= 5 ,-1 , 0
  4203.4     .17       0  4819.8     .15       0  4950.9     .09       0
  5034.7     .15       0  5168.6     .17       0
#XS Ineff= 2 ,-1
  4819.4  4790.4  171.31  4790.4  4768.9  171.51
Permanent Ineff=
       F       F
Bank Sta=4950.9,5034.7
XS Rating Curve= 0 ,0
Exp/Cntr=0.3,0.1

Type RM Length L Ch R = 1 ,2500    ,500,500,500
XS GIS Cut Line= 3
      3847204.79     10105778.21      3846507.66     10105876.29
       3846453.8     10106378.73
#Sta/Elev= 30
       0  174.04    67.6  171.85     108  171.93   125.7  170.86   168.6  171.29
   249.4  169.52   380.7  169.72   431.1  168.09   441.2  169.11   563.2  168.41
   572.5  169.62   592.7  170.08     623  168.41   673.5  167.11   683.6  166.09
   693.7  163.18   700.6  160.26   708.9  160.98   718.9  163.41   746.6  164.57
   751.6  166.57   819.4  167.29   843.8  166.79   849.6  167.48     920  167.85
  1020.6   169.7  1080.9  169.56  1120.2  170.71  1191.6  170.91    1208  171.82
#Mann= 3 , 0 , 0
       0     .15       0   673.5     .09       0   751.6     .15       0
Bank Sta=673.5,751.6
XS Rating Curve= 0 ,0
Exp/Cntr=0.3,0.1

Type RM Length L Ch R = 1 ,2000    ,500,500,500
XS GIS Cut Line= 3
        3846710.     10105422.31      3846191.39     10105580.02
      3845907.93     10105931.29
#Sta/Elev= 30
       0  176.02    48.3  175.42   119.2  173.22     159  172.83   179.7   171.8
     185  172.06   200.8  170.99   232.2  170.99   283.6  168.12   315.8  168.06
   368.1  166.31   425.5   165.9   451.7   164.6     483  165.15   491.2  164.18
   524.1  164.03   541.3  161.38   559.2  160.67   567.1  161.75   587.9  162.92
   602.3  164.98   637.5  165.07   659.1  166.22   723.3  166.06   759.1  167.18
   837.4  168.17   936.6  168.43   965.4  169.13   971.8  169.98   993.4  170.09
#Mann= 3 , 0 , 0
       0     .15       0     483     .09       0   602.3     .15       0
Bank Sta=483,602.3
XS Rating Curve= 0 ,0
Exp/Cntr=0.3,0.1

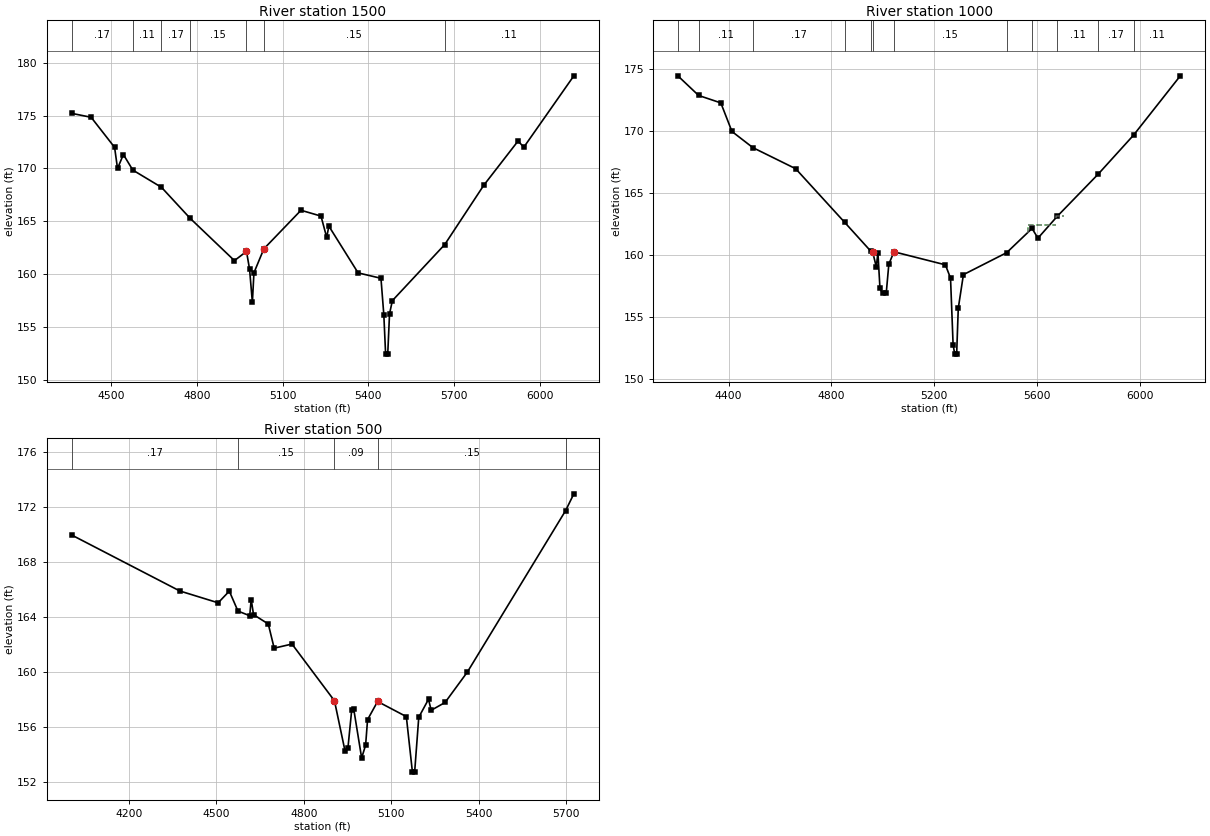
Type RM Length L Ch R = 1 ,1500    ,500,500,500
BEGIN DESCRIPTION:
Crystal Creek 050 3.0
END DESCRIPTION:
XS GIS Cut Line= 3
       3846723.9     10105285.16      3846102.08     10105141.51
      3844982.71     10105118.49
#Sta/Elev= 30
  4361.8  175.21  4429.6  174.84  4511.7     172    4522     170  4542.5  171.32
  4575.5  169.85  4675.9  168.22  4776.2  165.29  4931.3  161.29  4973.5  162.16
  4984.3  160.48  4994.1  157.34  4999.6  160.14  5034.2   162.4  5164.3  166.05
  5234.3   165.5  5254.3  163.49  5261.9  164.55  5364.3  160.13  5444.3  159.62
  5454.3  156.18  5460.6  152.45    5468  152.45  5474.3  156.26  5484.3  157.51
  5667.6  162.81  5804.4  168.42  5924.4   172.6  5944.4  172.01  6119.6  178.76
#Mann= 7 ,-1 , 0
  4361.8     .17       0  4575.5     .11       0  4675.9     .17       0
  4776.2     .15       0  4973.5     .09       0  5034.2     .15       0
  5667.6     .11       0
Bank Sta=4973.5,5034.2
XS Rating Curve= 0 ,0
Exp/Cntr=0.3,0.1

Type RM Length L Ch R = 1 ,1000    ,500,500,500
BEGIN DESCRIPTION:
Crystal Creek 050 2.0
END DESCRIPTION:
XS GIS Cut Line= 3
      3846751.67     10105160.16      3846131.39     10104661.46
      3844973.93     10104671.44
#Sta/Elev= 30
  4204.1  174.41  4283.4  172.86  4369.8  172.26    4413  169.96  4494.3  168.66
    4661  166.96  4852.1  162.63  4953.2  160.32  4960.2  160.29  4974.6  159.06
    4981  160.19    4989  157.32  4999.1  156.94  5013.5  156.98  5023.5  159.28
  5043.5  160.27  5243.5  159.22  5263.5  158.15  5273.5   152.8  5279.8  152.03
  5287.3  152.03  5293.6  155.72  5313.6  158.43  5481.9   160.2  5580.6  162.15
  5603.6  161.37  5679.3  163.14  5837.8  166.52  5975.4  169.66  6157.5  174.44
#Mann= 12 ,-1 , 0
  4204.1     .17       0  4283.4     .11       0  4494.3     .17       0
  4852.1     .15       0  4953.2     .12       0  4960.2     .09       0
  5043.5     .15       0  5481.9     .15       0  5580.6     .17       0
  5679.3     .11       0  5837.8     .17       0  5975.4     .11       0
#XS Ineff= 2 ,-1
  5563.6  5673.6  162.42  5673.6  5703.6  163.12
Permanent Ineff=
       F       F
Bank Sta=4960.2,5043.5
XS Rating Curve= 0 ,0
Exp/Cntr=0.3,0.1

Type RM Length L Ch R = 1 ,500     ,0,0,0
BEGIN DESCRIPTION:
Crystal Creek 050 1.0
END DESCRIPTION:
XS GIS Cut Line= 3
      3847154.48      10104354.6      3846169.35      10104210.6
      3845462.52     10104046.16
#Sta/Elev= 30
  4004.4  169.96  4374.9  165.89  4506.3  165.03  4544.5  165.88  4574.1  164.43
  4614.5  164.09  4619.5  165.27  4627.6  164.17  4678.1  163.49  4698.3  161.73
  4759.4  162.03 4905.02   157.9  4940.9  154.28    4951  154.43  4964.2  157.25
  4971.2  157.28  4998.2  153.74  5011.8  154.67  5018.5  156.53  5052.9  157.85
  5151.4  156.75  5172.3  152.71  5179.9  152.71    5194   156.7  5227.4  158.01
  5236.6  157.21  5284.3  157.78  5360.9     160  5697.5  171.74  5725.7  172.96
#Mann= 5 ,-1 , 0
  4004.4     .17       0  4574.1     .15       0 4905.02     .09       0
  5052.9     .15       0  5697.5     .11       0
Bank Sta=4905.02,5052.9
XS Rating Curve= 0 ,0
Exp/Cntr=0.3,0.1

Chan Stop Cuts=-1
Use User Specified Reach Order=0
Composite Channel Slope=5

--- Crystal Creek 050.g10 (geometry) ---

Geom Title=Existing Conditions
Program Version=4.10

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
River Reach=Crystal Creek 05,Reach-1

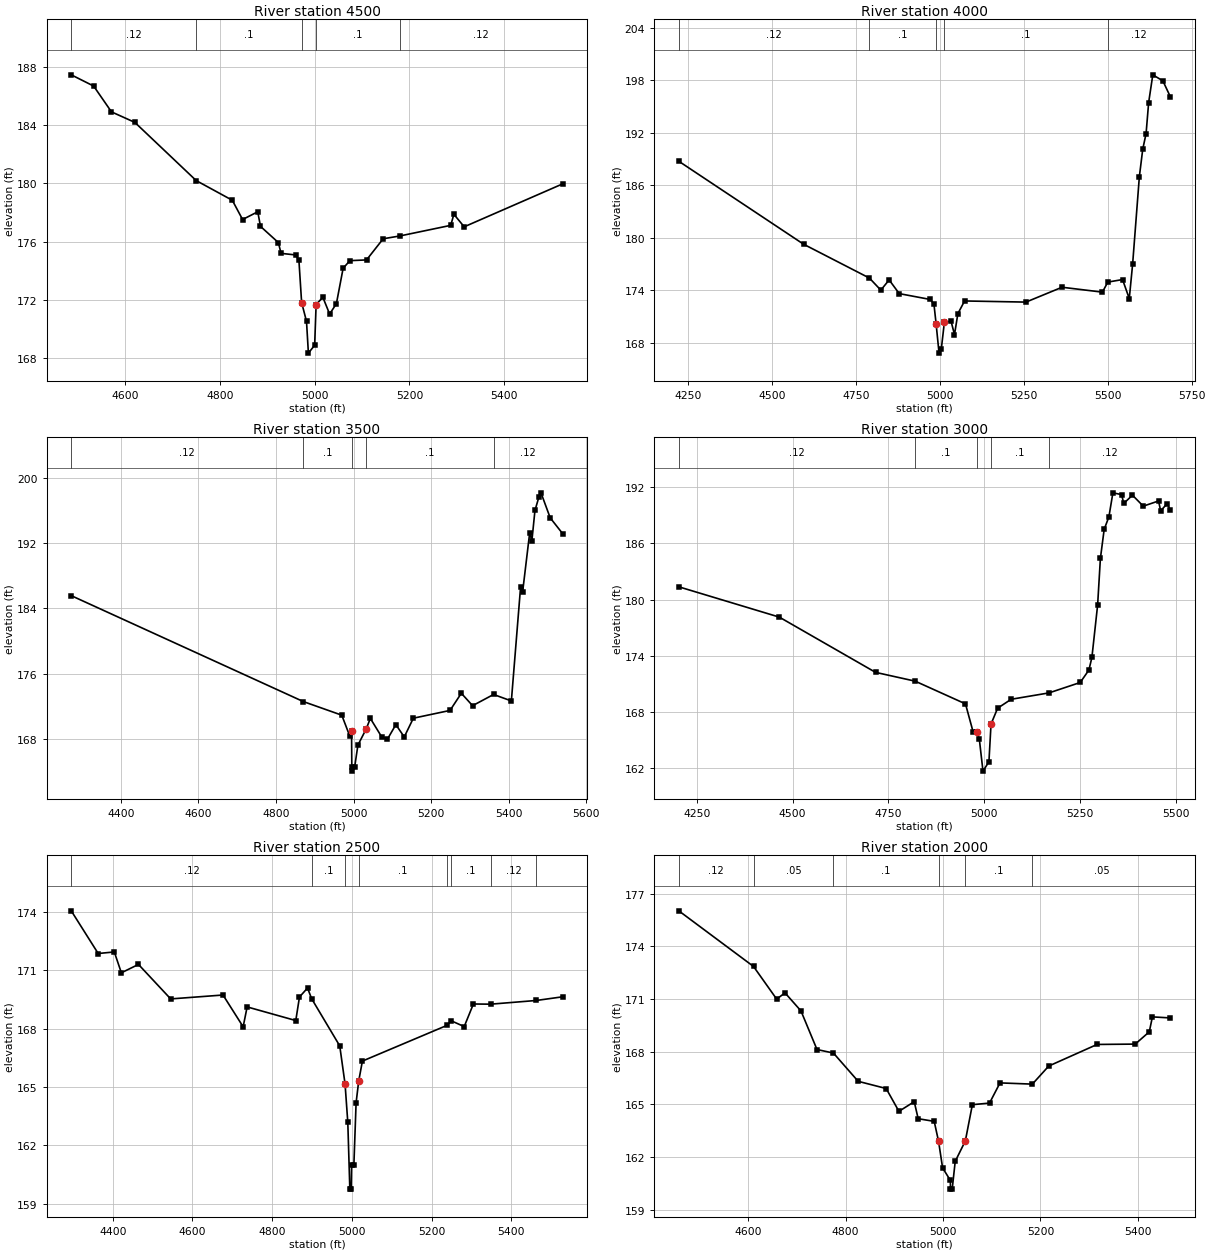
Type RM Length L Ch R = 1 ,4500    ,500,500,500
BEGIN DESCRIPTION:
Crystal Creek 050 9.0
END DESCRIPTION:
XS GIS Cut Line= 3
      3848022.01     10106961.87      3847573.26     10107211.89
      3847231.56     10107608.89
#Sta/Elev= 30
  4486.3  187.43  4533.6  186.66  4571.2  184.89  4620.5  184.17    4750  180.18
  4826.2  178.83  4847.9  177.51  4879.9  178.04  4885.7  177.04  4923.4  175.93
  4929.1  175.19  4960.4  175.08  4966.8  174.71  4972.5  171.82  4982.8  170.53
  4986.8  168.35    5000  168.89  5003.1  171.68  5017.3  172.18  5031.6  171.03
  5045.9  171.74  5060.1  174.17  5074.4  174.69  5109.5  174.74  5144.6  176.19
  5179.4  176.38  5287.2  177.11  5293.8  177.87  5315.6  177.01  5523.8  179.96
#Mann= 5 ,-1 , 0
  4486.3     .12       0    4750      .1       0  4972.5     .07       0
  5003.1      .1       0  5179.4     .12       0
Bank Sta=4972.5,5003.1
XS Rating Curve= 0 ,0
Exp/Cntr=0.3,0.1

Type RM Length L Ch R = 1 ,4000    ,500,500,500
BEGIN DESCRIPTION:
Crystal Creek 050 8.0
END DESCRIPTION:
XS GIS Cut Line= 3
      3847968.69     10106663.62      3847241.13     10106939.76
      3846555.53     10106902.72
#Sta/Elev= 30
  4221.8  188.75  4593.4  179.26  4789.8  175.38  4823.8     174  4848.6  175.17
  4878.7   173.6  4971.4  172.93  4982.1   172.4  4988.5  170.15  4997.3  166.79
  5004.1  167.29  5013.3  170.36  5033.3  170.41  5043.3  168.91  5053.4  171.31
  5073.4  172.76  5256.2  172.63  5363.8  174.33    5484  173.77  5500.2  174.92
  5544.1  175.21  5564.1  173.03  5574.1  176.98  5594.1  186.97  5604.2  190.12
  5614.2  191.92  5621.8  195.46  5634.2  198.64  5664.2  197.95  5686.6  196.12
#Mann= 5 ,-1 , 0
  4221.8     .12       0  4789.8      .1       0  4988.5     .07       0
  5013.3      .1       0  5500.2     .12       0
Bank Sta=4988.5,5013.3
XS Rating Curve= 0 ,0
Exp/Cntr=0.3,0.1

Type RM Length L Ch R = 1 ,3500    ,500,500,500
BEGIN DESCRIPTION:
Crystal Creek 050 7.0
END DESCRIPTION:
XS GIS Cut Line= 3
      3847799.45      10106403.2      3847088.24     10106557.23
      3846591.65     10106768.34
#Sta/Elev= 30
  4272.3  185.57  4870.7  172.62  4969.7  170.96  4989.8  168.47  4994.9  169.02
  4995.6  164.62  4995.9  164.12  5002.9  164.62  5011.3   167.3    5033  169.31
  5043.3  170.57  5072.4  168.32  5087.3  168.02  5109.1   169.8  5130.8   168.3
  5154.2  170.59  5248.8  171.54  5277.9  173.64  5306.9  172.12    5361  173.49
  5406.9   172.7  5430.6  186.59    5436  186.06  5454.2  193.29  5459.7  192.24
  5467.7  195.98  5477.9  197.63  5483.3  198.14    5507  195.08  5539.6  193.12
#Mann= 5 ,-1 , 0
  4272.3     .12       0  4870.7      .1       0  4995.6     .07       0
    5033      .1       0    5361     .12       0
Bank Sta=4994.9,5033
XS Rating Curve= 0 ,0
Exp/Cntr=0.3,0.1

Type RM Length L Ch R = 1 ,3000    ,500,500,500
BEGIN DESCRIPTION:
Crystal Creek 050 6.0
END DESCRIPTION:
XS GIS Cut Line= 3
      3847586.97     10106119.01      3846799.29     10106237.92
      3846590.44     10106675.76
#Sta/Elev= 30
  4203.4  181.36  4465.5  178.13  4716.4  172.24  4819.8   171.3  4950.9  168.88
  4971.1  165.84  4981.2  165.86    4987  165.11  4996.5  161.71    5012  162.71
  5017.5  166.73  5034.7  168.42    5070  169.37  5168.6  170.05    5250  171.16
  5272.7  172.49  5280.5  173.84  5295.4  179.42  5302.6  184.38  5312.5  187.49
  5324.8  188.82  5335.2  191.38  5357.9  191.19  5363.5  190.25  5386.2  191.13
  5414.4  189.96  5454.2  190.51  5459.8  189.46  5476.9  190.24  5485.1  189.51
#Mann= 5 ,-1 , 0
  4203.4     .12       0  4819.8      .1       0  4981.2     .07       0
  5017.5      .1       0  5168.6     .12       0
Bank Sta=4981.2,5017.5
XS Rating Curve= 0 ,0
Exp/Cntr=0.3,0.1

Type RM Length L Ch R = 1 ,2500    ,500,500,500
BEGIN DESCRIPTION:
Crystal Creek 050 5.0
END DESCRIPTION:
XS GIS Cut Line= 3
       3847204.8     10105778.21      3846507.66     10105876.29
      3846245.79     10106336.04
#Sta/Elev= 30
    4296  174.04  4363.6  171.85    4404  171.93  4421.7  170.86  4464.6  171.29
  4545.4  169.52  4676.7  169.72  4727.2  168.09  4737.2  169.11  4859.2  168.41
  4868.5  169.62  4888.7  170.08    4899  169.53  4969.5  167.11 4982.88 165.145
  4989.7  163.18  4994.8  159.76  4998.3  159.76  4999.2  160.98  5004.9  160.98
  5010.5  164.19    5017   165.3  5026.3  166.33  5238.2  168.16  5248.9   168.4
  5281.7   168.1  5304.7  169.26  5347.9  169.25  5462.5  169.44  5529.1  169.63
#Mann= 8 ,-1 , 0
    4296     .12       0    4899      .1       0 4982.88     .07       0
    5017      .1       0  5238.2     .12       0  5248.9      .1       0
  5347.9     .12       0  5462.5     .05       0
Bank Sta=4982.88,5017
XS Rating Curve= 0 ,0
Exp/Cntr=0.3,0.1

Type RM Length L Ch R = 1 ,2000    ,500,500,500
BEGIN DESCRIPTION:
Crystal Creek 050 4.0
END DESCRIPTION:
XS GIS Cut Line= 3
      3846710.04     10105422.29      3846191.39     10105580.02
      3845898.37     10105943.13
#Sta/Elev= 30
  4457.9  176.02  4611.3  172.85  4658.8  170.99  4675.8  171.35  4708.6  170.32
  4741.5  168.12  4775.2  167.92    4826  166.31  4883.4   165.9  4909.6   164.6
    4941  165.15  4949.1  164.18    4982  164.03 4990.99 162.883  4999.2  161.38
  5015.1  160.67  5015.4  160.17  5018.9  160.17  5025.1  161.75  5045.9  162.92
  5060.3  164.98  5095.5  165.07    5117  166.22  5183.4  166.15    5217  167.18
  5316.2  168.41  5394.5  168.43  5423.3  169.13  5429.7  169.98  5466.6  169.92
#Mann= 6 ,-1 , 0
  4457.9     .12       0  4611.3     .05       0  4775.2      .1       0
 4990.99     .07       0  5045.9      .1       0  5183.4     .05       0
Bank Sta=4990.99,5045.9
XS Rating Curve= 0 ,0
Exp/Cntr=0.3,0.1

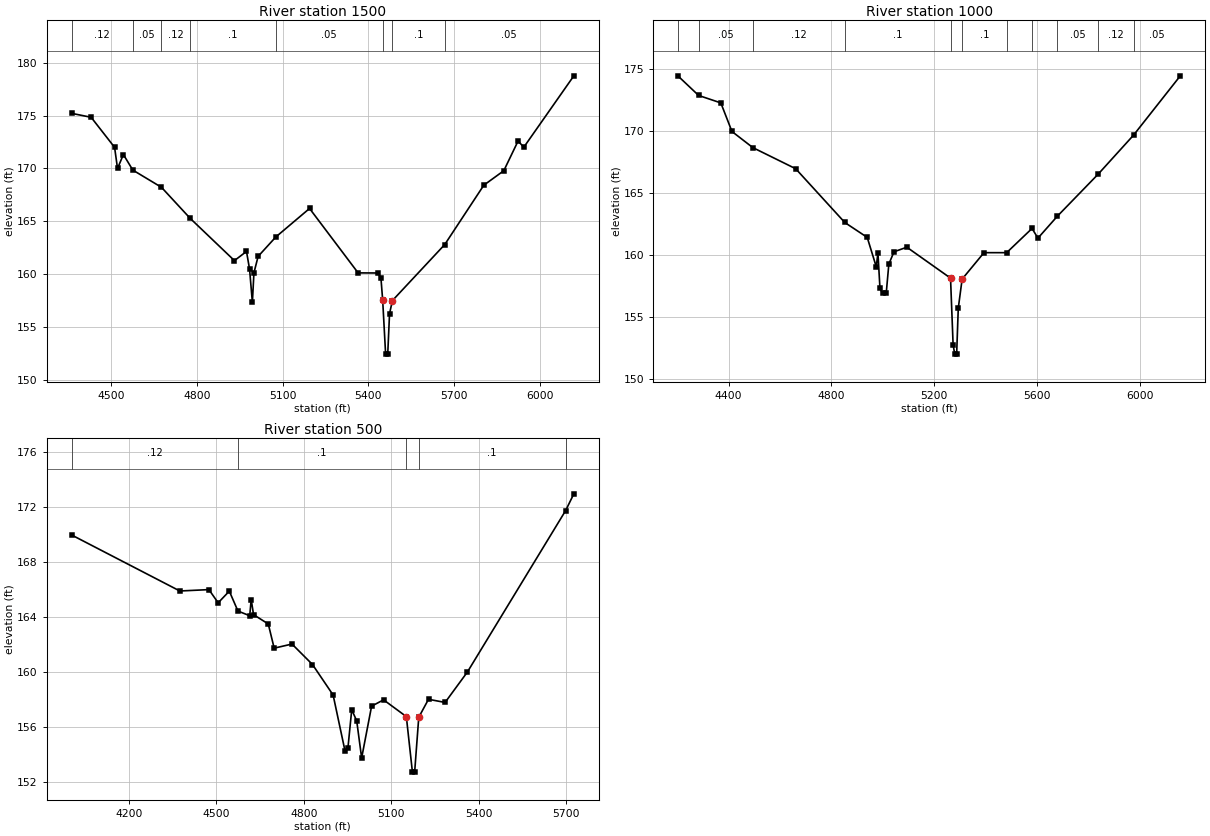
Type RM Length L Ch R = 1 ,1500    ,500,500,500
BEGIN DESCRIPTION:
Crystal Creek 050 3.0
END DESCRIPTION:
XS GIS Cut Line= 3
       3846723.9     10105285.16      3846102.08     10105141.51
      3844982.71     10105118.49
#Sta/Elev= 30
  4361.8  175.21  4429.6  174.84  4511.7     172    4522     170  4542.5  171.32
  4575.5  169.85  4675.9  168.22  4776.2  165.29  4931.3  161.29  4973.5  162.16
  4984.3  160.48  4994.1  157.34  4999.6  160.14  5014.2  161.69    5076  163.52
  5194.3  166.22  5364.3  160.13  5434.3  160.12  5444.3  159.62 5450.31 157.553
  5460.6  152.45    5468  152.45  5474.3  156.26  5484.3  157.51  5667.6  162.81
  5804.4  168.42  5874.4  169.79  5924.4   172.6  5944.4  172.01  6119.6  178.76
#Mann= 8 ,-1 , 0
  4361.8     .12       0  4575.5     .05       0  4675.9     .12       0
  4776.2      .1       0    5076     .05       0 5450.31     .07       0
  5484.3      .1       0  5667.6     .05       0
Bank Sta=5450.31,5484.3
XS Rating Curve= 0 ,0
Exp/Cntr=0.3,0.1

Type RM Length L Ch R = 1 ,1000    ,500,500,500
BEGIN DESCRIPTION:
Crystal Creek 050 2.0
END DESCRIPTION:
XS GIS Cut Line= 3
      3846751.67     10105160.16      3846131.39     10104661.46
      3844973.93     10104671.44
#Sta/Elev= 30
  4204.1  174.41  4283.4  172.86  4369.8  172.26    4413  169.96  4494.3  168.66
    4661  166.96  4852.1  162.63  4939.4  161.43  4974.6  159.06    4981  160.19
    4989  157.32  4999.1  156.94  5013.5  156.98  5023.5  159.28  5043.5  160.27
  5093.5  160.64  5263.5  158.15  5273.5   152.8  5279.8  152.03  5287.3  152.03
  5293.6  155.72 5308.63 158.072  5393.6   160.2  5481.9   160.2  5580.6  162.15
  5603.6  161.37  5679.3  163.14  5837.8  166.52  5975.4  169.66  6157.5  174.44
#Mann= 11 ,-1 , 0
  4204.1     .12       0  4283.4     .05       0  4494.3     .12       0
  4852.1      .1       0  5263.5     .07       0 5308.63      .1       0
  5481.9      .1       0  5580.6     .12       0  5679.3     .05       0
  5837.8     .12       0  5975.4     .05       0
Bank Sta=5263.5,5308.63
XS Rating Curve= 0 ,0
Exp/Cntr=0.3,0.1

Type RM Length L Ch R = 1 ,500     ,0,0,0
BEGIN DESCRIPTION:
Crystal Creek 050 1.0
END DESCRIPTION:
XS GIS Cut Line= 3
      3847154.48      10104354.6      3846169.35      10104210.6
      3845462.52     10104046.16
#Sta/Elev= 30
  4004.4  169.96  4374.9  165.89  4474.6  165.99  4506.3  165.03  4544.5  165.88
  4574.1  164.43  4614.5  164.09  4619.5  165.27  4627.6  164.17  4678.1  163.49
  4698.3  161.73  4759.4  162.03  4829.7  160.54  4900.4  158.32  4940.9  154.28
    4951  154.43  4964.2  157.25  4981.3  156.44  4998.2  153.74  5032.3  157.51
  5073.4  157.97  5151.4  156.75  5172.3  152.71  5179.9  152.71    5194   156.7
  5227.4  158.01  5284.3  157.78  5360.9     160  5697.5  171.74  5725.7  172.96
#Mann= 5 ,-1 , 0
  4004.4     .12       0  4574.1      .1       0  5151.4     .07       0
    5194      .1       0  5697.5     .05       0
Bank Sta=5151.4,5194
XS Rating Curve= 0 ,0
Exp/Cntr=0.3,0.1