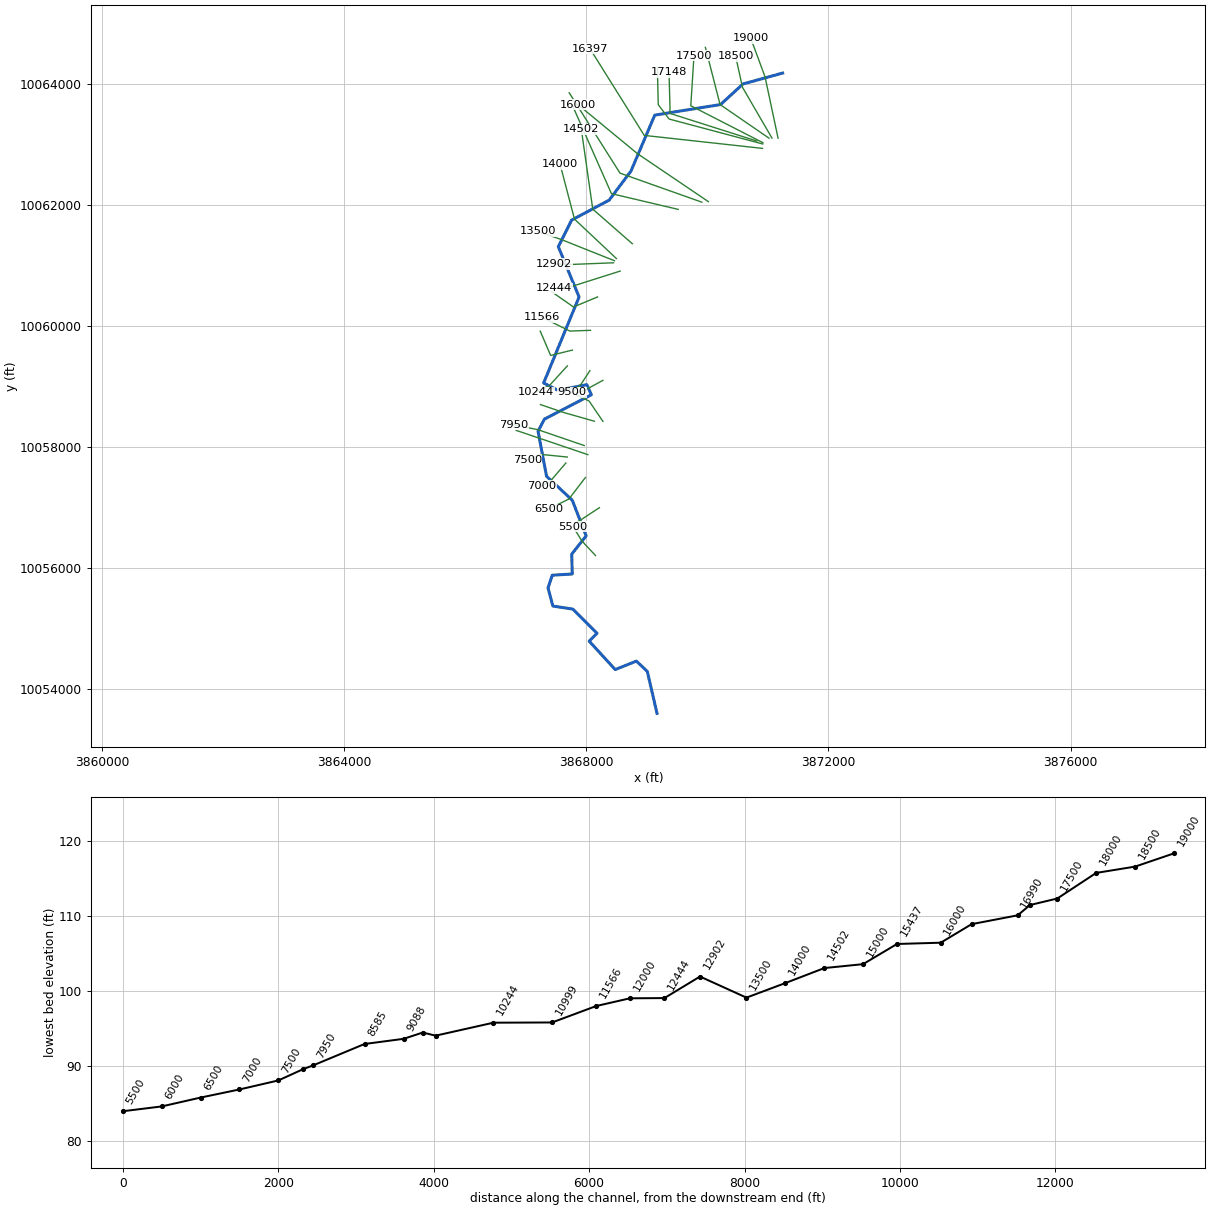
--- Crystal Creek 053.prj (project) ---

Proj Title=Crystal Creek 053 Base Level Engineering
Current Plan=p01
Default Exp/Contr=0.3,0.1
English Units
Geom File=g01
Flow File=f01
Flow File=f02
Plan File=p01
Y Axis Title=Elevation
X Axis Title(PF)=Main Channel Distance
X Axis Title(XS)=Station
BEGIN DESCRIPTION:
Crystal Creek 053
END DESCRIPTION:
DSS File=dss
DSS Export Rating Curves= 0
DSS Export Rating Curve Sorted= 0
DSS Export Volume Flow Curves= 0
DXF OffsetX= 0
DXF OffsetY= 0
DXF ScaleX= 1
DXF ScaleY= 10

--- Crystal Creek 053.p01 (plan) ---

Plan Title=Multiple Run
Program Version=4.10
Short Identifier=Multiple Run
Geom File=g01
Flow File=f01
Subcritical Flow
K Sum by GR= 0
Std Step Tol= 0.01
Critical Tol= 0.01
Num of Std Step Trials= 20
Max Error Tol= 0.3
Flow Tol Ratio= 0.001
Split Flow NTrial= 30
Split Flow Tol= 0.02
Split Flow Ratio= 0.02
Log Output Level= 0
Friction Slope Method= 1
Unsteady Friction Slope Method= 2
Unsteady Bridges Friction Slope Method= 1
Parabolic Critical Depth
Global Vel Dist= 1 , 1 , 1
Global Log Level= 0
CheckData=True
Encroach Param=-1 ,0,0, 0
BEGIN DESCRIPTION:
Multiple Run
END DESCRIPTION:
Computation Interval=1HOUR
Output Interval=1HOUR
Run HTab= 0
Run UNet= 0
Run PostProcess= 0
Run WQNet= 0
UNET Theta= 1
UNET Theta Warmup= 1
UNET ZTol= 0.02
UNET ZSATol= 0.05
UNET MxIter= 20
UNET MaxInSteps= 0
UNET DtIC= 0
UNET DtMin= 0
UNET MaxCRTS= 20
UNET WFStab= 2
UNET SFStab= 1
UNET WFX= 1
UNET SFX= 1
UNET DSS MLevel= 4
UNET DZMax Abort= 100
UNET Convert EG Bridges= 0
UNET Use Existing IB Tables=-1
UNET Froude Reduction=False
UNET Froude Limit= 1
UNET Froude Power= 10
UNET Time Slicing=0,0, 5
UNET Junction Losses=0
Instantaneous Interval=1HOUR
DSS File=dss
Write IC File= 0
Write IC File at Sim End=0
Echo Input=False
Echo Parameters=False
Echo Output=False
Write Detailed= 0
WQ AD Non Conservative
WQ ULTIMATE=-1
WQ Max Comp Step=1HOUR
WQ Output Interval=15MIN
WQ Output Selected Increments= 0
WQ Output face flow=0
WQ Output face velocity=0
WQ Output face area=0
WQ Output face dispersion=0
WQ Output cell volume=0
WQ Output cell surface area=0
WQ Output cell continuity=0
WQ Output cumulative cell continuity=0
WQ Output face conc=0
WQ Output face dconc_dx=0
WQ Output face courant=0
WQ Output face peclet=0
WQ Output face adv mass=0
WQ Output face disp mass=0
WQ Output cell mass=0
WQ Output cell source sink temp=0
WQ Output cell source sink nsm=0
WQ Output MaxMinRange=-1
WQ Daily Max Min Mean=-1
WQ Daily Range=0
WQ Daily Time=0
WQ Create Restart=0
WQ Fixed Restart=0
WQ System Summary=0
WQ Use Fixed Temperature=0
Sorting and Armoring Iterations= 10
XS Update Threshold= 0.02
Hydraulics Update Threshold= 0.02
Energy Slope Method= 1
Volume Change Method= 0
XS Weighting Method= 0
Number of US Weighted Cross Sections= 1
Number of DS Weighted Cross Sections= 1
Upstream XS Weight=0.25
Main XS Weight=0.5
Downstream XS Weight=0.25
Number of DS XS's Weighted with US Boundary= 1
Upstream Boundary Weight= 1
Weight of XSs Associated with US Boundary= 0
Number of US XS's Weighted with DS Boundary= 1
Downstream Boundary Weight= 0.5
Weight of XSs Associated with DS Boundary= 0.5
Sediment Output Level= 4
Mass or Volume Output= 0
Output Increment Type= 1
Profile and TS Output Increment= 10
XS Output Flag= 0
XS Output Increment= 10
Disregard all LS=0
Disregard all Conn=0
Disregard all Breaches=0
Disregard all Pumps=0

--- Crystal Creek 053.f01 (steady flow) ---

Flow Title=Multiple
Program Version=4.10
Number of Profiles= 7
Profile Names=10-year,25-year,50-year,1pct_min,100-year,1pct_plu,500-year
River Rch & RM=Crystal Creek 05,Reach-1         ,19000
     662     875    1165     509    1537    4642    2764
River Rch & RM=Crystal Creek 05,Reach-1         ,9088
     847    1135    1523     671    2025    6115    3700
Boundary for River Rch & Prof#=Crystal Creek 05,Reach-1         , 1
Up Type= 0
Dn Type= 3
Dn Slope=0.005
Boundary for River Rch & Prof#=Crystal Creek 05,Reach-1         , 2
Up Type= 0
Dn Type= 3
Dn Slope=0.005
Boundary for River Rch & Prof#=Crystal Creek 05,Reach-1         , 3
Up Type= 0
Dn Type= 3
Dn Slope=0.005
Boundary for River Rch & Prof#=Crystal Creek 05,Reach-1         , 4
Up Type= 0
Dn Type= 3
Dn Slope=0.005
Boundary for River Rch & Prof#=Crystal Creek 05,Reach-1         , 5
Up Type= 0
Dn Type= 3
Dn Slope=0.005
Boundary for River Rch & Prof#=Crystal Creek 05,Reach-1         , 6
Up Type= 0
Dn Type= 3
Dn Slope=0.005
Boundary for River Rch & Prof#=Crystal Creek 05,Reach-1         , 7
Up Type= 0
Dn Type= 3
Dn Slope=0.005
DSS Import GetInterval= 0
DSS Import GetPeak= 0
DSS Import FillOption= 0

--- Crystal Creek 053.f02 (steady flow) ---

Flow Title=Orig_BLE_Flow
Program Version=4.10
Number of Profiles= 7
Profile Names=10-year,25-year,50-year,1pct_min,100-year,1pct_plu,500-year
River Rch & RM=Crystal Creek 05,Reach-1         ,19000
     662     858    1013     391    1182    3570    1607
River Rch & RM=Crystal Creek 05,Reach-1         ,9088
     847    1113    1324     516    1558    4704    2151
Boundary for River Rch & Prof#=Crystal Creek 05,Reach-1         , 1
Up Type= 0
Dn Type= 3
Dn Slope=0.005
Boundary for River Rch & Prof#=Crystal Creek 05,Reach-1         , 2
Up Type= 0
Dn Type= 3
Dn Slope=0.005
Boundary for River Rch & Prof#=Crystal Creek 05,Reach-1         , 3
Up Type= 0
Dn Type= 3
Dn Slope=0.005
Boundary for River Rch & Prof#=Crystal Creek 05,Reach-1         , 4
Up Type= 0
Dn Type= 3
Dn Slope=0.005
Boundary for River Rch & Prof#=Crystal Creek 05,Reach-1         , 5
Up Type= 0
Dn Type= 3
Dn Slope=0.005
Boundary for River Rch & Prof#=Crystal Creek 05,Reach-1         , 6
Up Type= 0
Dn Type= 3
Dn Slope=0.005
Boundary for River Rch & Prof#=Crystal Creek 05,Reach-1         , 7
Up Type= 0
Dn Type= 3
Dn Slope=0.005
DSS Import GetInterval= 0
DSS Import GetPeak= 0
DSS Import FillOption= 0

--- Crystal Creek 053.g01 (geometry) ---

Geom Title=Existing Conditions
Program Version=4.10

River Reach=Crystal Creek 05,Reach-1
Reach XY= 30
      3871243.24     10064186.86      3870588.24     10064006.86
      3870218.24     10063666.86      3869131.24      10063491.8
      3868738.24     10062566.86      3868378.24     10062086.86
      3867758.24     10061756.86      3867538.24     10061316.86
      3867881.38     10060485.47      3867295.45      10059063.6
      3867532.43     10058943.81      3868008.85     10059036.25
      3868084.51     10058869.59      3867308.24     10058466.86
      3867203.58     10058266.77      3867343.55     10057522.44
      3867768.24     10057126.86      3867998.24     10056536.86
      3867759.61     10056235.49      3867768.24     10055906.86
      3867438.24     10055886.86      3867368.24     10055676.86
      3867448.24     10055376.86      3867778.24     10055326.86
      3868178.24     10054926.86      3868048.24     10054796.86
      3868478.24     10054326.86      3868828.24     10054466.86
      3869008.24     10054296.86      3869168.24     10053603.06

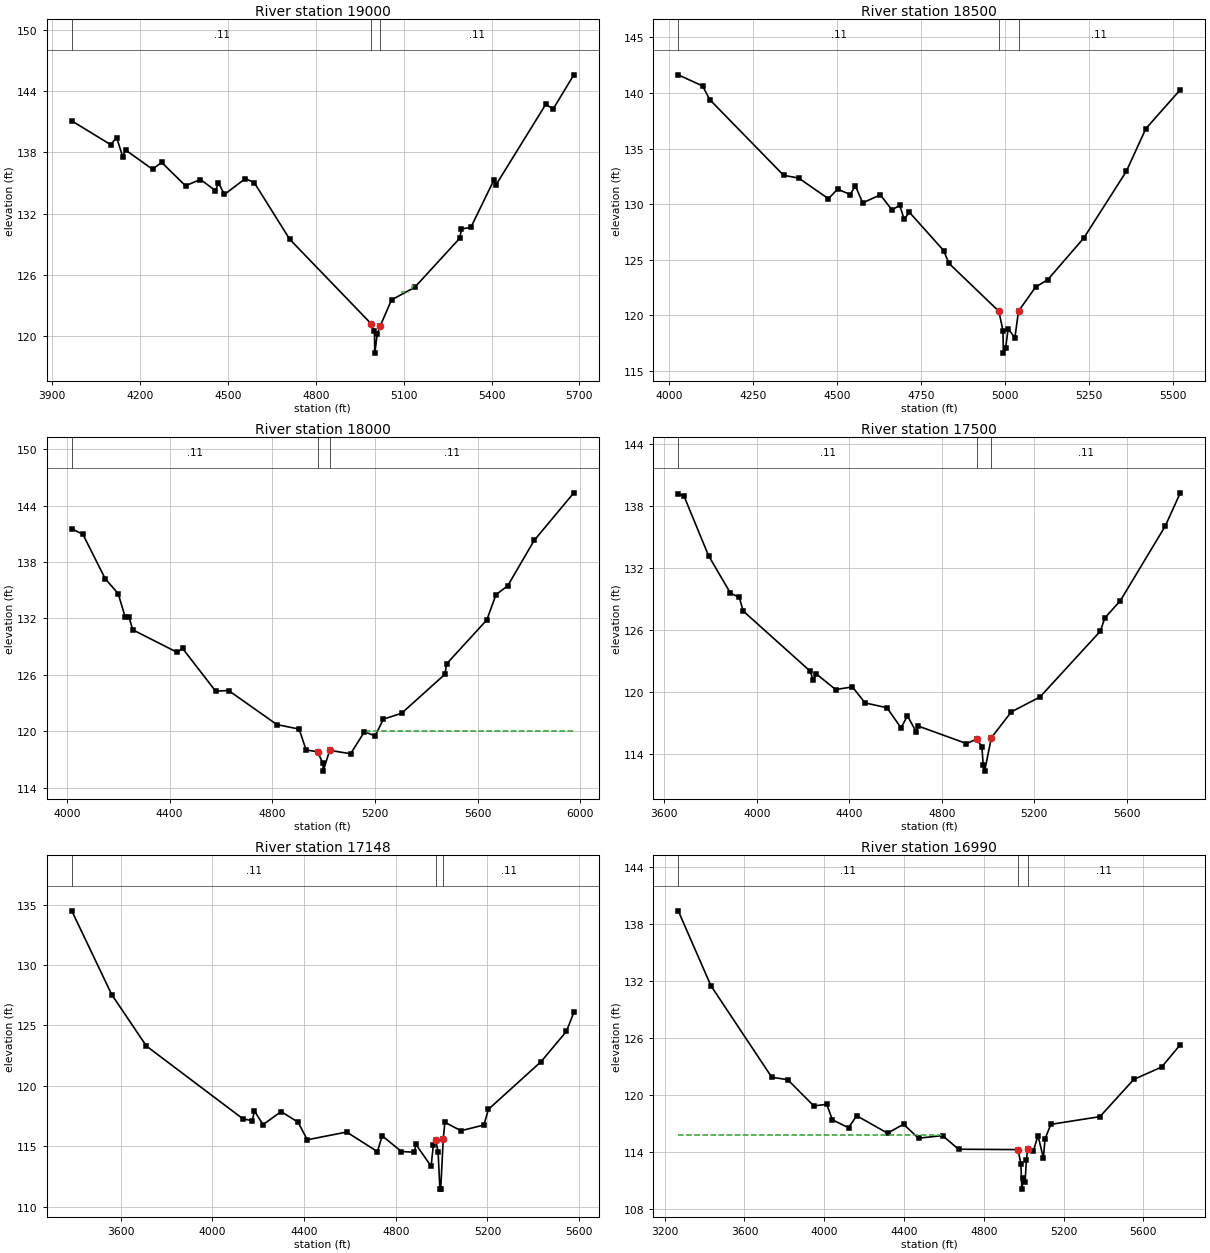
Type RM Length L Ch R = 1 ,19000   ,500,500,500
BEGIN DESCRIPTION:
Crystal Creek 053 37.0
END DESCRIPTION:
XS GIS Cut Line= 3
      3871167.85     10063111.08      3870953.48     10064122.11
      3870717.86     10064761.05
#Sta/Elev= 30
  3966.5  141.09  4099.4  138.76  4119.8  139.46  4140.3  137.59  4150.5  138.23
  4242.5  136.35  4273.2  137.03  4354.9  134.74    4406  135.35  4457.2  134.26
  4467.4  135.02  4487.8  133.89  4559.4  135.44    4590  135.03  4710.7   129.5
  4988.7  121.23    5000  120.47  5001.3  118.35  5009.6  120.23  5020.2  121.04
  5058.6  123.57  5137.5  124.79  5291.4   129.6  5297.3  130.51  5329.3  130.66
  5407.8  135.29  5414.6   134.8  5585.1  142.71  5610.3  142.25    5681   145.6
#Mann= 3 , 0 , 0
  3966.5     .11       0  4988.7     .09       0  5020.2     .11       0
#XS Ineff= 2 ,-1
  5094.8  5119.4  124.29  5126.8  5144.6  124.89
Permanent Ineff=
       F       F
Bank Sta=4988.7,5020.2
XS Rating Curve= 0 ,0
Exp/Cntr=0.3,0.1

Type RM Length L Ch R = 1 ,18500   ,500,500,500
BEGIN DESCRIPTION:
Crystal Creek 053 36.0
END DESCRIPTION:
XS GIS Cut Line= 3
      3871067.85     10063111.08      3870580.24     10063951.47
      3870467.84     10064461.12
#Sta/Elev= 30
  4028.4  141.63  4100.8  140.63  4122.4  139.39  4341.8  132.59  4386.8  132.34
  4475.1  130.48  4502.4  131.35  4539.7  130.86  4555.4  131.64    4577  130.11
  4629.6  130.83  4664.3  129.47  4687.4   129.9  4700.3  128.63  4716.1  129.26
  4817.9  125.82  4833.6  124.67 4982.18120.3526  4994.3  118.62  4995.6  116.59
  5002.4  117.09  5009.8  118.79  5029.8  117.96  5040.6  120.37  5091.8  122.55
  5127.4  123.19  5235.1  126.96  5361.2  132.94  5419.4  136.79  5521.9  140.29
#Mann= 3 , 0 , 0
  4028.4     .11       0 4982.18     .09       0  5040.6     .11       0
Bank Sta=4982.18,5040.6
XS Rating Curve= 0 ,0
Exp/Cntr=0.3,0.1

Type RM Length L Ch R = 1 ,18000   ,500,500,500
BEGIN DESCRIPTION:
Crystal Creek 053 35.0
END DESCRIPTION:
XS GIS Cut Line= 3
      3871017.88     10063111.05      3870209.77     10063666.86
      3869967.85     10064611.07
#Sta/Elev= 30
  4019.2  141.52  4062.5  140.94  4149.1  136.23  4199.9  134.63  4226.9  132.17
  4241.8  132.15  4256.7  130.78  4429.9  128.38  4450.8   128.8  4579.3  124.26
  4630.1  124.32  4818.2   120.7  4904.8  120.22  4931.8     118  4976.5  117.81
  4997.4  116.58  4998.3  115.75  5023.8  117.96  5105.4   117.6  5159.2  119.94
  5200.5  119.49    5233  121.28  5303.7   121.9  5472.6  126.05  5479.2  127.16
  5635.7  131.83  5671.3  134.51  5717.3  135.47  5819.9  140.28  5974.7  145.35
#Mann= 3 , 0 , 0
  4019.2     .11       0  4976.5     .09       0  5023.8     .11       0
#XS Ineff= 2 , 0
       0                  5169.5       0  120.06
Permanent Ineff=
       F       F
Bank Sta=4976.5,5023.8
XS Rating Curve= 0 ,0
Exp/Cntr=0.3,0.1

Type RM Length L Ch R = 1 ,17500   ,352,352,352
BEGIN DESCRIPTION:
Crystal Creek 053 34.0
END DESCRIPTION:
XS GIS Cut Line= 3
      3870918.17     10063035.69      3869726.33     10063646.86
       3869779.3     10064476.37
#Sta/Elev= 30
  3660.6  139.21  3686.2  138.93  3791.6   133.2    3886  129.58  3924.7  129.16
  3941.3  127.84  4229.9  122.04  4245.3  121.13  4257.7  121.75  4340.8  120.24
  4413.9  120.49  4468.4  118.94  4562.8  118.48  4623.8  116.53  4651.6  117.69
  4690.3   116.1    4696  116.72  4906.7  115.01  4951.1  115.44  4973.3  114.72
  4978.9  112.97  4985.3  112.34  5014.2  115.57  5100.8  118.08  5224.7  119.52
  5485.2  125.88  5505.2  127.18  5571.7  128.83  5765.8  136.05  5831.2  139.28
#Mann= 3 , 0 , 0
  3660.6     .11       0  4951.1     .09       0  5014.2     .11       0
#XS Ineff= 2 , 0
       0  4651.6  117.69               0
Permanent Ineff=
       F       F
Bank Sta=4951.1,5014.2
XS Rating Curve= 0 ,0
Exp/Cntr=0.3,0.1

Type RM Length L Ch R = 1 ,17148   ,158,158,158
BEGIN DESCRIPTION:
Mapping XS 80c55c3d
END DESCRIPTION:
XS GIS Cut Line= 4
      3870818.09     10063063.02      3869382.42     10063520.17
      3869382.75     10063606.97      3869366.79     10064203.56
#Sta/Elev= 30
  3386.6  134.48  3560.7  127.56  3712.2   123.3    4132   117.3    4174  117.11
  4183.4  117.94  4220.9   116.8  4299.9  117.88  4373.4  117.01  4414.2  115.55
  4585.8  116.19    4720  114.57  4740.7  115.88  4824.6  114.58  4881.1  114.52
  4887.6  115.17  4954.2  113.37  4964.2  115.14  4974.2  115.52  4984.7  114.54
  4992.5  111.47    4996  111.47 5007.22  115.62  5014.2     117  5084.2   116.3
  5184.3  116.77  5204.3  118.07  5434.4  122.02  5544.4  124.51  5576.9  126.08
#Mann= 3 , 0 , 0
  3386.6     .11       0  4974.2     .09       0 5007.22     .11       0
#XS Ineff= 2 , 0
       0  4585.8  116.19               0
Permanent Ineff=
       F       F
Bank Sta=4974.2,5007.22
XS Rating Curve= 0 ,0
Exp/Cntr=0.3,0.1

Type RM Length L Ch R = 1 ,16990   ,593,593,593
BEGIN DESCRIPTION:
Crystal Creek 053 33.0
END DESCRIPTION:
XS GIS Cut Line= 4
      3870914.73     10063014.84      3869367.72     10063427.47
      3869189.04     10063664.15      3869174.09     10064284.23
#Sta/Elev= 30
  3267.8   139.4  3431.6  131.52  3736.8  121.88    3817  121.62  3947.6  118.86
  4012.4  119.03  4040.8   117.4  4122.3  116.56  4162.4  117.83  4317.6  115.99
  4397.8  116.93  4472.9  115.46  4593.2  115.74  4673.4   114.3    4972  114.26
  4986.2  112.75    4991   110.1  4999.1  111.26  5007.4  110.81  5013.6  113.18
 5020.41114.2795    5049  114.11  5071.9  115.74    5099  113.39  5107.3  115.39
  5136.4  116.92  5382.4  117.73  5552.5  121.65  5692.5  122.96  5785.7  125.31
#Mann= 3 , 0 , 0
  3267.8     .11       0    4972     .09       0 5020.41     .11       0
#XS Ineff= 2 , 0
       0    4588  115.77  5071.9       0  115.74
Permanent Ineff=
       F       F
Bank Sta=4972,5020.41
XS Rating Curve= 0 ,0
Exp/Cntr=0.3,0.1

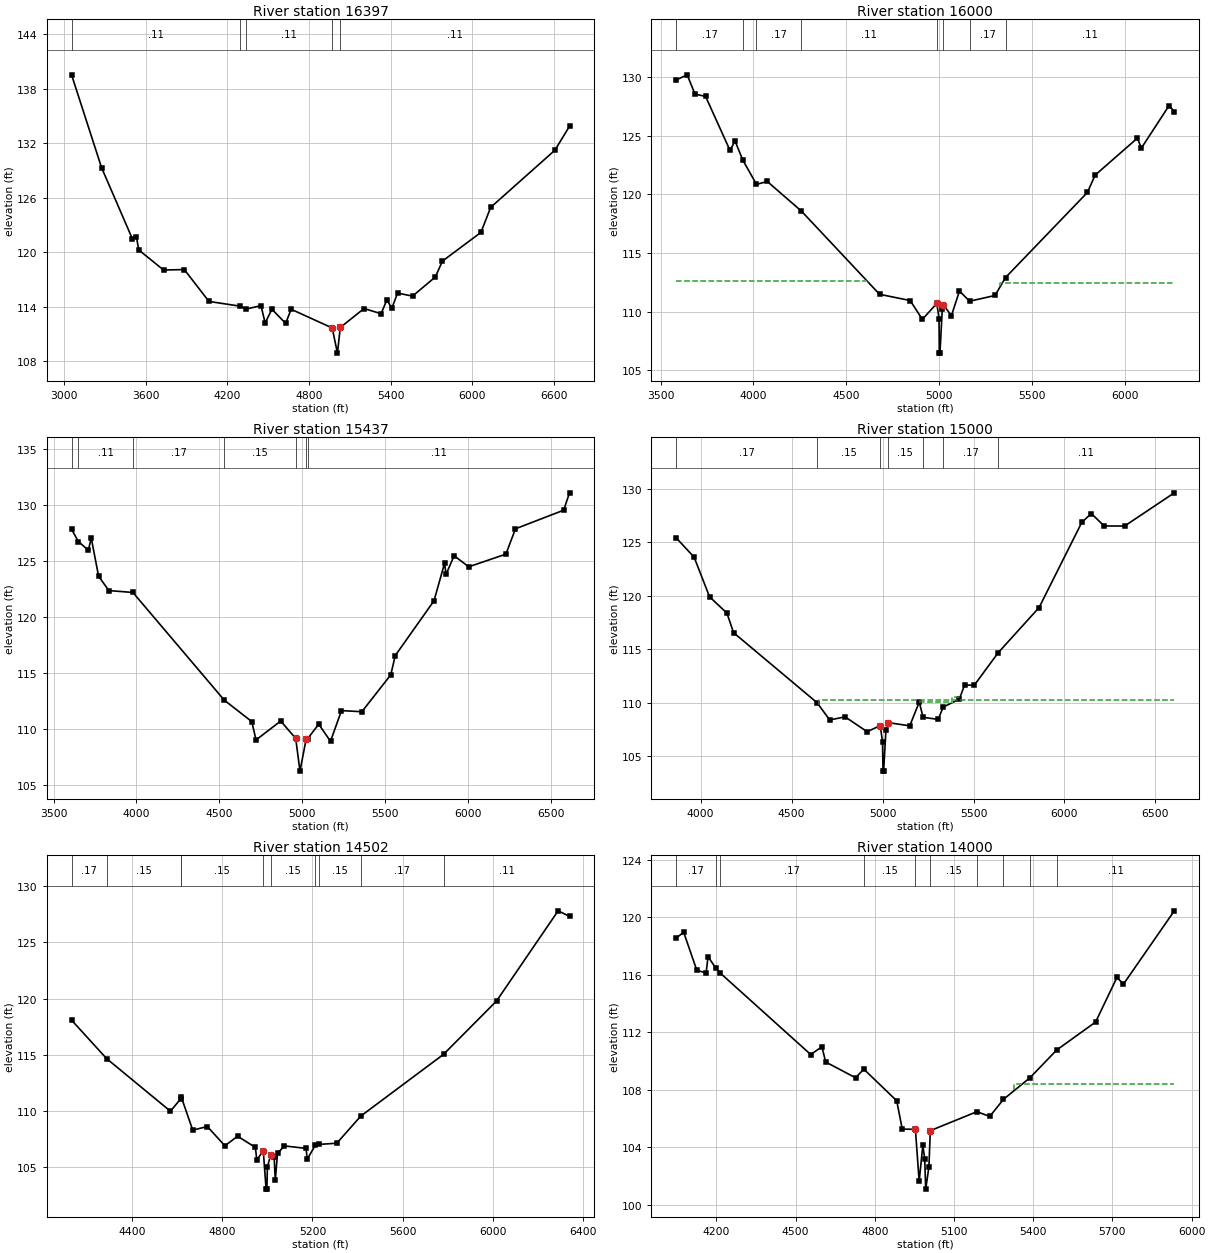
Type RM Length L Ch R = 1 ,16397   ,397,397,397
BEGIN DESCRIPTION:
Crystal Creek 053 32.0
END DESCRIPTION:
XS GIS Cut Line= 3
      3870911.22     10062941.93      3868957.88     10063156.42
      3868060.32     10064592.17
#Sta/Elev= 30
  3055.4  139.56  3275.8  129.34  3501.4  121.53  3531.6  121.75  3549.1  120.28
  3731.2  118.07  3883.7  118.12  4064.8  114.61  4289.3   114.1    4338  113.77
  4447.1  114.15  4477.3  112.24  4527.6  113.75  4628.2  112.19  4668.4  113.75
  4970.2  111.69  5008.7  108.92 5029.49111.7439  5204.3  113.83  5329.2  113.26
  5371.7  114.78  5408.3  113.87  5450.7  115.53  5560.4   115.2  5727.8   117.3
  5779.7  119.05  6062.7  122.21  6134.5  124.97  6606.3  131.26  6713.7   133.9
#Mann= 5 ,-1 , 0
  3055.4     .11       0  4289.3     .17       0    4338     .11       0
  4970.2     .09       0 5029.49     .11       0
#XS Ineff= 2 , 0
       0  4668.4  113.75  5204.3       0  113.83
Permanent Ineff=
       F       F
Bank Sta=4970.2,5029.49
XS Rating Curve= 0 ,0
Exp/Cntr=0.3,0.1

Type RM Length L Ch R = 1 ,16000   ,563,563,563
BEGIN DESCRIPTION:
Crystal Creek 053 31.0
END DESCRIPTION:
XS GIS Cut Line= 3
      3870017.88     10062061.05        3868846.     10062854.63
      3867867.87     10063661.06
#Sta/Elev= 30
  3584.7  129.77  3643.1   130.2  3685.1  128.55  3742.1  128.36  3873.8  123.75
  3900.8  124.56  3942.2  122.94  4016.5  120.85  4074.5   121.1  4258.6  118.57
  4679.6  111.47  4844.4  110.94  4910.3  109.33  4988.2   110.7    5000   109.4
  5001.4  106.45  5004.9  106.45  5017.5  110.19    5024  110.54    5067  109.66
    5110  111.75  5164.6  110.88  5301.6  111.37  5358.2   112.9  5799.3  120.16
    5841  121.64    6069   124.8  6089.9  123.94  6239.7  127.58  6267.7  127.06
#Mann= 8 ,-1 , 0
  3584.7     .17       0  3942.2     .11       0  4016.5     .17       0
  4258.6     .11       0  4988.2     .09       0    5024     .11       0
  5164.6     .17       0  5358.2     .11       0
#XS Ineff= 2 , 0
       0  4622.7  112.57  5330.2       0  112.45
Permanent Ineff=
       F       F
Bank Sta=4988.2,5024
XS Rating Curve= 0 ,0
Exp/Cntr=0.3,0.1

Type RM Length L Ch R = 1 ,15437   ,437,437,437
BEGIN DESCRIPTION:
Crystal Creek 053 30.0
END DESCRIPTION:
XS GIS Cut Line= 3
      3869909.77     10062052.61      3868557.36     10062532.63
      3867717.88     10063861.03
#Sta/Elev= 30
  3608.3  127.86  3649.6  126.76  3709.7  125.99  3727.1  127.08  3771.5  123.67
  3833.2  122.39  3978.7  122.22  4530.4  112.61  4696.4   110.7    4722  109.06
    4871  110.75 4961.61109.1967  4987.4  106.28  5025.3  109.19  5033.8  109.18
  5100.7  110.47  5171.7  108.94  5237.9  111.68  5360.9  111.58  5535.5  114.87
  5562.6  116.59  5796.6  121.48  5860.2  124.82  5869.6  123.84  5917.9   125.5
  6006.1  124.51  6230.7  125.64  6288.4   127.9  6579.4  129.56  6614.8  131.11
#Mann= 7 ,-1 , 0
  3608.3     .17       0  3649.6     .11       0  3978.7     .17       0
  4530.4     .15       0 4961.61     .09       0  5025.3     .15       0
  5033.8     .11       0
#XS Ineff= 2 , 0
       0                  5237.9       0  111.68
Permanent Ineff=
       F       F
Bank Sta=4961.61,5025.3
XS Rating Curve= 0 ,0
Exp/Cntr=0.3,0.1

Type RM Length L Ch R = 1 ,15000   ,498,498,498
BEGIN DESCRIPTION:
Crystal Creek 053 29.0
END DESCRIPTION:
XS GIS Cut Line= 3
      3869518.27     10061933.68      3868415.38       10062194.
      3867767.86     10063661.06
#Sta/Elev= 30
  3866.8  125.41  3964.6  123.61  4049.2  119.91  4144.7  118.38  4181.3  116.55
  4639.9     110  4709.8  108.38  4794.2  108.67  4915.3  107.28  4987.2  107.85
    5000  106.35  5002.5  103.59    5006  103.59  5018.7  107.45  5027.6  108.14
  5149.6  107.83  5201.7  110.05    5223  108.63  5305.9  108.43  5333.1  109.58
  5422.4  110.34  5451.2  111.67  5503.3  111.61  5635.9  114.68  5860.3   118.9
  6095.6  126.89  6147.7   127.7  6217.7  126.54  6330.3  126.53  6603.6  129.64
#Mann= 7 ,-1 , 0
  3866.8     .17       0  4639.9     .15       0  4987.2     .09       0
  5027.6     .15       0    5223     .11       0  5333.1     .17       0
  5635.9     .11       0
#XS Ineff= 3 ,-1
  4648.1  4596.7  110.23  5201.7  5381.3  110.05  5381.3  5427.9  110.54
Permanent Ineff=
       F       F       F
Bank Sta=4987.2,5027.6
XS Rating Curve= 0 ,0
Exp/Cntr=0.3,0.1

Type RM Length L Ch R = 1 ,14502   ,502,502,502
BEGIN DESCRIPTION:
Crystal Creek 053 28.0
END DESCRIPTION:
XS GIS Cut Line= 3
      3868760.49     10061365.96      3868106.89     10061938.21
      3867917.85     10063261.06
#Sta/Elev= 30
  4133.2  118.08  4288.6  114.66  4571.1  109.99  4615.9  111.08  4618.4  111.29
  4669.8  108.31  4734.4  108.63  4812.2  106.92  4868.2  107.77    4947  106.78
  4953.6  105.66  4982.1  106.48  4994.6  103.07  4998.1  103.07  5000.3  105.04
  5014.9   106.1  5030.2  105.93  5035.3  103.86  5045.2  106.25  5075.5  106.91
  5171.6  106.69  5176.7  105.72  5212.2  106.96  5228.9  107.04  5307.8  107.15
    5414  109.56  5780.2  115.04    6015  119.78  6287.7  127.79  6338.2   127.3
#Mann= 10 ,-1 , 0
  4133.2     .17       0  4288.6     .15       0  4615.9     .17       0
  4618.4     .15       0  4982.1     .09       0  5014.9     .15       0
  5212.2     .17       0  5228.9     .15       0    5414     .17       0
  5780.2     .11       0
Bank Sta=4982.1,5014.9
XS Rating Curve= 0 ,0
Exp/Cntr=0.3,0.1

Type RM Length L Ch R = 1 ,14000   ,500,500,500
BEGIN DESCRIPTION:
Crystal Creek 053 27.0
END DESCRIPTION:
XS GIS Cut Line= 3
      3868497.44      10061121.2      3867804.75     10061773.38
      3867568.08     10062677.31
#Sta/Elev= 30
  4048.6  118.55  4076.3  118.95  4126.1   116.3  4161.3  116.12  4168.6  117.25
  4197.6  116.46  4213.5  116.13  4557.4  110.44  4599.9  110.98    4614  109.92
  4727.3  108.82  4758.5  109.42  4883.1  107.22  4904.1  105.25  4953.9  105.23
  4968.1  101.61    4982  104.11  4989.1   103.2  4992.9  101.07  5005.1  102.62
  5010.3  105.14  5186.8  106.46  5235.4  106.13  5287.5  107.32  5388.2  108.83
  5488.8  110.75  5636.3   112.7  5717.1   115.8  5741.9  115.34  5934.4  120.44
#Mann= 10 ,-1 , 0
  4048.6     .17       0  4197.6     .15       0  4213.5     .17       0
  4758.5     .15       0  4953.9     .09       0  5010.3     .15       0
  5186.8     .11       0  5287.5     .15       0  5388.2     .17       0
  5488.8     .11       0
#XS Ineff= 2 , 0
       0                  5328.5       0  108.42
Permanent Ineff=
       F       F
Bank Sta=4953.9,5010.3
XS Rating Curve= 0 ,0
Exp/Cntr=0.3,0.1

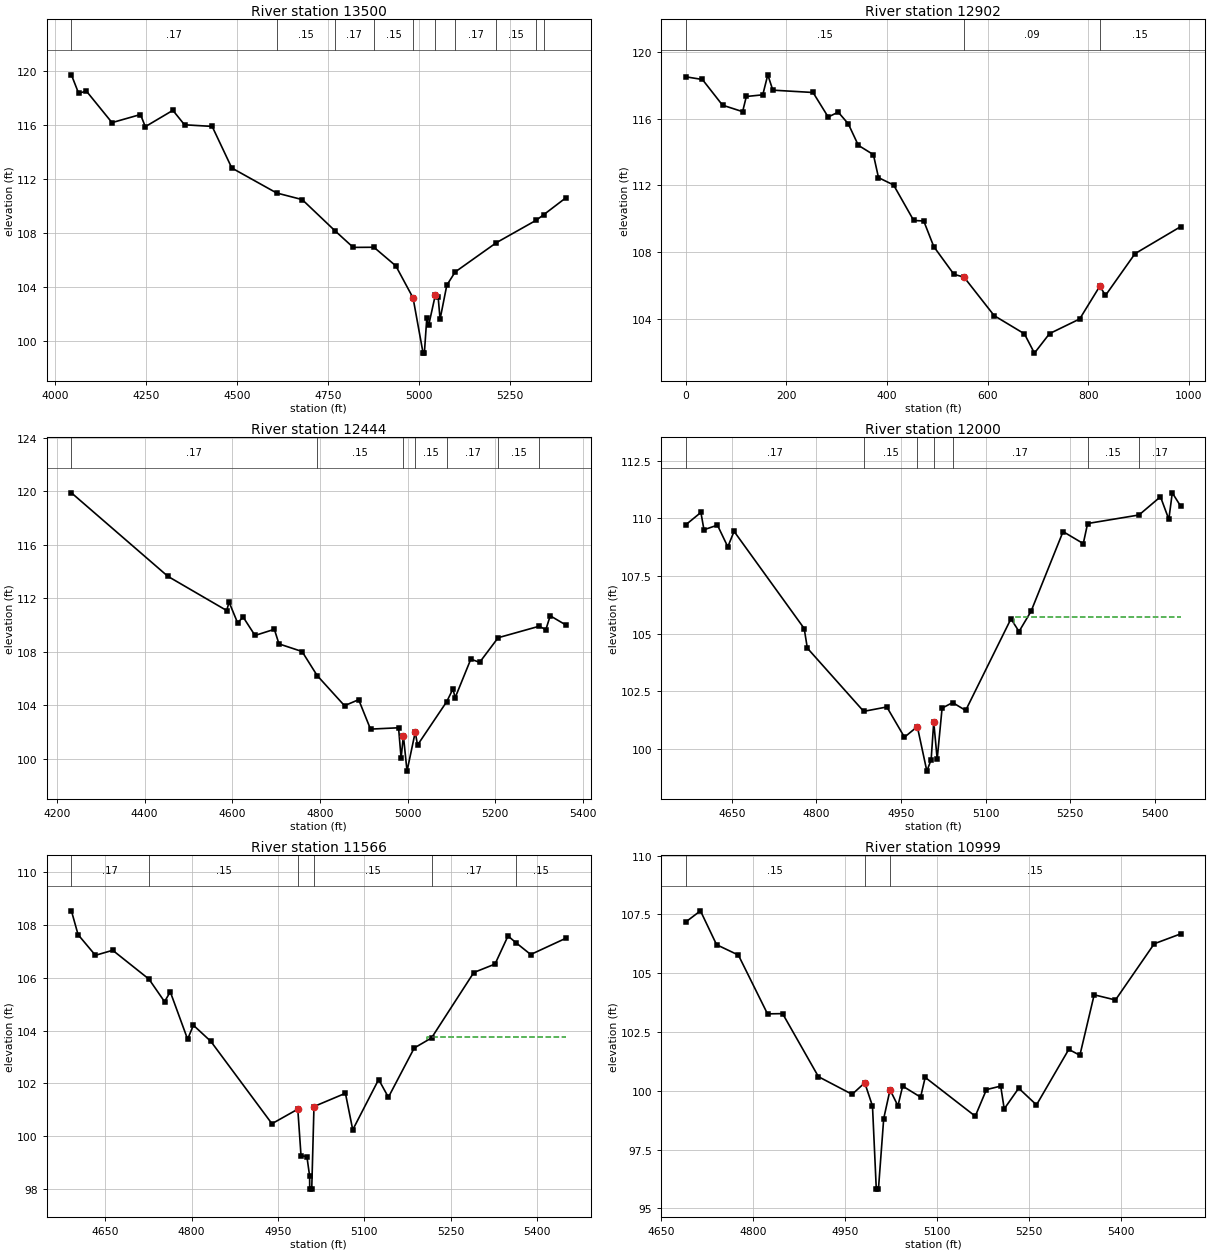
Type RM Length L Ch R = 1 ,13500   ,598,598,598
BEGIN DESCRIPTION:
Crystal Creek 053 26.0
END DESCRIPTION:
XS GIS Cut Line= 3
      3868466.18     10061084.73      3867579.69     10061438.32
      3867197.97      10061569.1
#Sta/Elev= 30
  4045.6  119.74  4065.3  118.38  4086.9  118.53    4157   116.2  4235.2   116.8
  4248.4   115.9  4324.1  117.11    4356  116.04  4431.9  115.92  4485.8  112.84
  4608.8  110.99    4679   110.5  4768.2  108.21    4819  106.96  4875.9  106.97
    4936  105.59 4983.25 103.221  5010.8   99.13  5014.3   99.13  5020.9   101.7
  5026.1  101.19  5044.2  103.41  5052.1   103.3  5057.4  101.64  5075.9  104.16
  5098.8  105.14    5212  107.31  5321.2  108.97  5341.3  109.37  5403.5  110.65
#Mann= 10 ,-1 , 0
  4045.6     .17       0  4608.8     .15       0  4768.2     .17       0
  4875.9     .15       0 4983.25     .09       0  5044.2     .15       0
  5098.8     .17       0    5212     .15       0  5321.2     .17       0
  5341.3     .15       0
Bank Sta=4983.25,5044.2
XS Rating Curve= 0 ,0
Exp/Cntr=0.3,0.1

Type RM Length L Ch R = 1 ,12902   ,458,458,458
XS GIS Cut Line= 3
      3868450.59     10061050.86      3867718.82     10061022.22
      3867467.12     10061032.07
#Sta/Elev= 30
       0  118.52    32.8  118.36    72.8  116.82   112.8  116.43   120.2  117.34
   152.9  117.44   162.9  118.64   172.9  117.72   252.9  117.58     283  116.11
     303   116.4     323   115.7     343  114.41     373  113.85   383.1  112.47
   413.1  112.03   453.1   109.9   473.1  109.87   493.1  108.33   533.1  106.67
   553.2   106.5   613.2  104.19   673.3   103.1   693.3  101.94   723.3  103.11
   783.3  103.99   823.4  105.96   834.6   105.4   893.4  107.91   984.2  109.53
#Mann= 3 , 0 , 0
       0     .15       0   553.2     .09       0   823.4     .15       0
Bank Sta=553.2,823.4
XS Rating Curve= 0 ,0
Exp/Cntr=0.3,0.1

Type RM Length L Ch R = 1 ,12444   ,444,444,444
BEGIN DESCRIPTION:
Crystal Creek 053 24.0
END DESCRIPTION:
XS GIS Cut Line= 3
      3868559.11     10060913.71      3867760.48     10060660.24
      3867471.73     10060627.39
#Sta/Elev= 30
  4233.2  119.87  4453.2  113.63  4587.5  111.07  4592.7  111.71  4612.2  110.16
    4625  110.58    4652  109.21  4696.1  109.67  4706.6  108.58  4759.3  108.01
  4793.8  106.21  4856.1  103.96  4888.4  104.41  4915.4  102.21  4979.4  102.31
  4985.2  100.04  4990.4  101.72  4998.7   99.07  5017.4  101.98  5022.7  101.02
  5089.2  104.26  5103.4  105.21  5108.5  104.56  5144.2  107.44  5164.3   107.2
  5206.5  109.04  5300.2   109.9  5315.3  109.64  5325.3  110.68  5361.7  109.98
#Mann= 7 ,-1 , 0
  4233.2     .17       0  4793.8     .15       0  4990.4     .09       0
  5017.4     .15       0  5089.2     .17       0  5206.5     .15       0
  5300.2     .17       0
Bank Sta=4990.4,5017.4
XS Rating Curve= 0 ,0
Exp/Cntr=0.3,0.1

Type RM Length L Ch R = 1 ,12000   ,434,434,434
BEGIN DESCRIPTION:
Crystal Creek 053 23.0
END DESCRIPTION:
XS GIS Cut Line= 3
      3868186.65     10060486.61      3867788.38     10060320.82
      3867422.97     10060576.18
#Sta/Elev= 30
  4568.6  109.72  4595.2  110.25  4600.6   109.5  4624.5   109.7  4642.9  108.76
    4654  109.43  4778.3  105.22  4783.9  104.37  4883.8  101.63  4924.8  101.82
  4956.1  100.51  4978.9  100.97  4995.8   99.04  5003.4   99.54    5008  101.17
  5014.1   99.56  5022.8  101.77  5041.5  102.01  5064.6  101.67  5144.9  105.64
  5159.2  105.09  5180.6  105.97  5237.3  109.42  5273.1   108.9  5280.8  109.77
  5371.9  110.14    5410  110.93  5424.8  109.95  5430.9   111.1  5445.8  110.52
#Mann= 7 ,-1 , 0
  4568.6     .17       0  4883.8     .15       0  4978.9     .09       0
    5008     .15       0  5041.5     .17       0  5280.8     .15       0
  5371.9     .17       0
#XS Ineff= 2 , 0
       0                    5151       0  105.72
Permanent Ineff=
       F       F
Bank Sta=4978.9,5008
XS Rating Curve= 0 ,0
Exp/Cntr=0.3,0.1

Type RM Length L Ch R = 1 ,11566   ,567,567,567
BEGIN DESCRIPTION:
Crystal Creek 053 22.0
END DESCRIPTION:
XS GIS Cut Line= 3
      3868069.48     10059934.54      3867729.23     10059922.39
      3867263.97     10060151.55
#Sta/Elev= 30
  4591.4  108.52    4603  107.62  4633.1  106.84  4663.1  107.03  4726.1  105.94
  4753.1  105.09  4763.1  105.46  4793.2  103.67  4803.2   104.2  4833.5  103.59
  4939.6  100.48  4984.5  101.03  4990.1   99.27  5000.3   99.24    5005   98.51
  5005.2   98.01  5008.7   98.01  5012.6  101.13  5067.2  101.63  5079.9  100.25
  5124.9  102.15  5141.8  101.48  5186.7  103.34  5216.7  103.72  5290.1  106.19
    5327  106.51  5349.5  107.57  5363.1  107.32  5388.9  106.87  5450.5  107.49
#Mann= 6 ,-1 , 0
  4591.4     .17       0  4726.1     .15       0  4984.5     .09       0
  5012.6     .15       0  5216.7     .17       0  5363.1     .15       0
#XS Ineff= 2 , 0
       0  4803.2   104.2  5209.1       0  103.77
Permanent Ineff=
       F       F
Bank Sta=4984.5,5012.6
XS Rating Curve= 0 ,0
Exp/Cntr=0.3,0.1

Type RM Length L Ch R = 1 ,10999   ,755,755,755
BEGIN DESCRIPTION:
Crystal Creek 053 21.0
END DESCRIPTION:
XS GIS Cut Line= 3
      3867770.86     10059608.14      3867411.52     10059519.61
      3867239.65     10059920.66
#Sta/Elev= 30
  4690.3  107.18    4714  107.65  4740.3  106.21  4775.8  105.77  4823.3  103.27
  4847.9  103.28  4906.3   100.6  4961.2   99.85  4981.8  100.34  4994.4   99.35
  5000.6   95.82  5004.1   95.82  5012.7   98.82    5023  100.04  5035.9   99.36
  5043.6   100.2  5072.8   99.73  5080.3  100.57  5161.9   98.92  5180.1  100.05
  5203.4   100.2  5209.1   99.23  5232.7  100.11  5261.7    99.4  5314.3  101.76
  5332.4  101.51  5355.7  104.08  5390.4  103.86  5453.6  106.25  5496.7  106.67
#Mann= 3 , 0 , 0
  4690.3     .15       0  4981.8     .09       0    5023     .15       0
Bank Sta=4981.8,5023
XS Rating Curve= 0 ,0
Exp/Cntr=0.3,0.1

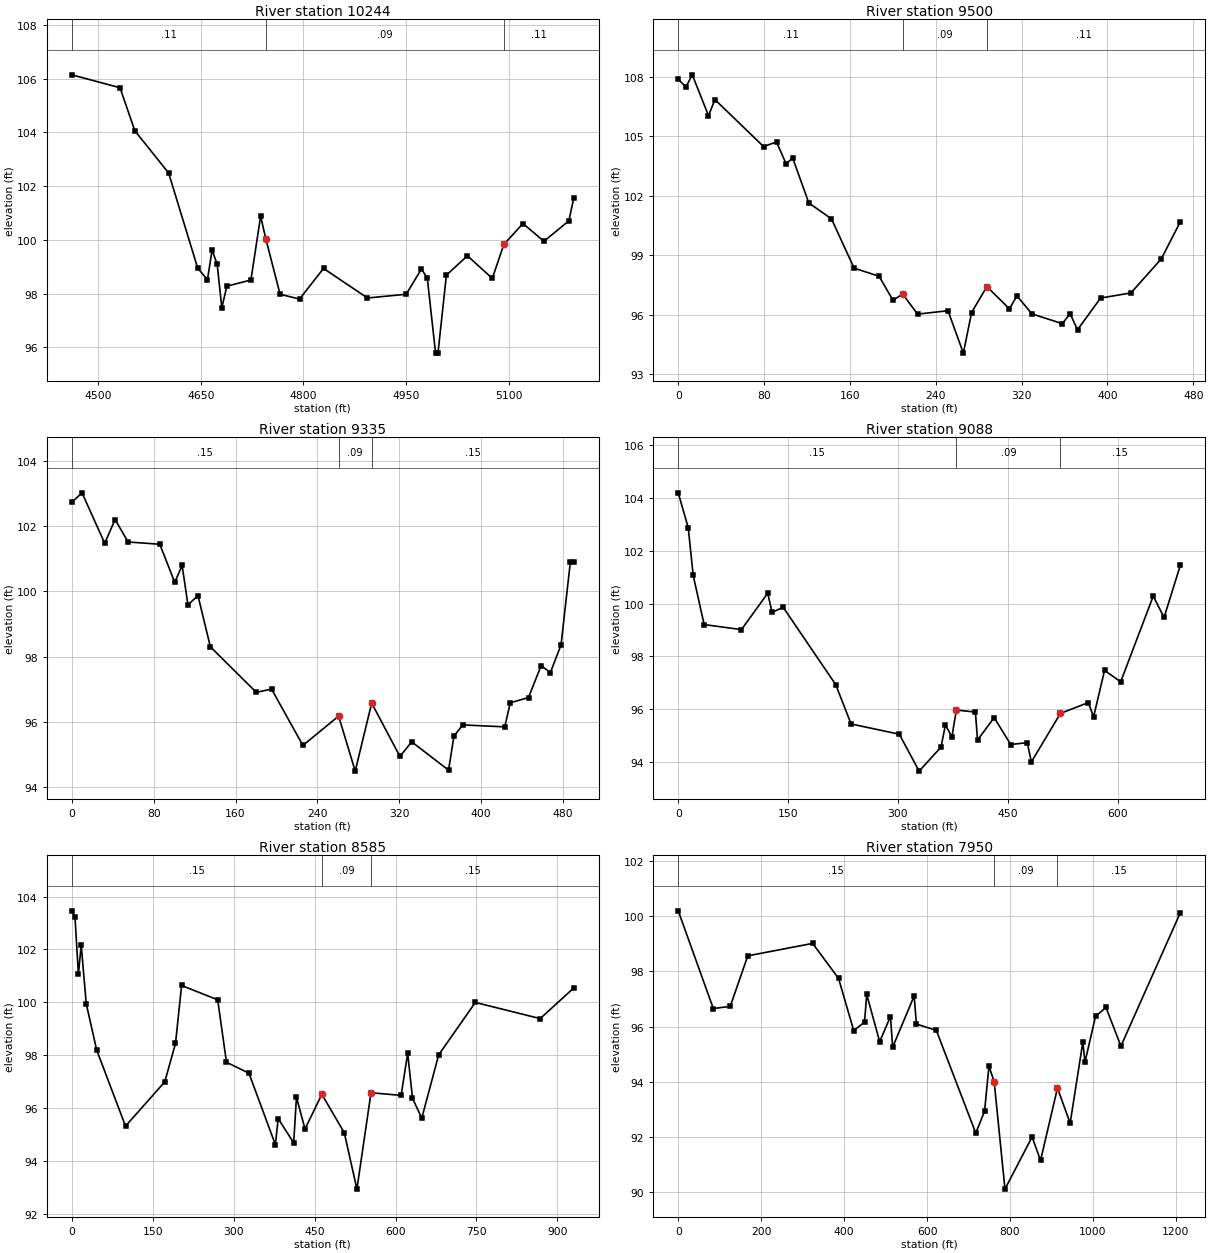
Type RM Length L Ch R = 1 ,10244   ,744,744,744
BEGIN DESCRIPTION:
Crystal Creek 053 19.0
END DESCRIPTION:
XS GIS Cut Line= 3
      3867687.12     10059346.67      3867392.75     10059023.58
      3867168.77     10058911.59
#Sta/Elev= 30
  4461.6  106.14  4532.1  105.66  4553.7  104.06  4603.1  102.49  4645.6   98.95
  4659.8   98.52  4666.6   99.62    4674    99.1  4680.8   97.48  4688.2   98.28
  4723.3   98.51  4737.5  100.88    4745  100.05  4765.9   97.98  4794.3    97.8
  4829.4   98.94  4893.6   97.84  4950.2   97.98  4972.5   98.92    4981   98.58
  4993.1   95.79  4996.6   95.79  5008.9   98.69  5039.6   99.41    5076   98.57
  5092.8   99.83  5120.7  100.61  5151.4   99.95  5187.8  100.71  5195.1  101.57
#Mann= 3 , 0 , 0
  4461.6     .11       0    4745     .09       0  5092.8     .11       0
Bank Sta=4745,5092.8
XS Rating Curve= 0 ,0
Exp/Cntr=0.3,0.1

Type RM Length L Ch R = 1 ,9500    ,165,165,165
XS GIS Cut Line= 3
       3868059.5     10059267.78      3867913.69     10059044.55
      3867766.82     10058906.95
#Sta/Elev= 30
       0  107.89     7.1  107.49    13.1  108.11    28.2  106.05    34.2  106.86
    79.5  104.49    91.6  104.72   100.6  103.61   106.6  103.92   121.7  101.64
   142.8  100.84   163.9   98.35   187.2   97.94   200.1   96.73   209.2   97.04
     223   96.03   251.4    96.2   265.7   94.06   273.4   96.11   287.6   97.42
   308.6    96.3   315.7   96.95   329.6   96.04   357.9   95.55   365.2   96.05
   372.1   95.24   393.6   96.84   421.9    97.1   450.2   98.82   467.9  100.69
#Mann= 3 , 0 , 0
       0     .11       0   209.2     .09       0   287.6     .11       0
Bank Sta=209.2,287.6
XS Rating Curve= 0 ,0
Exp/Cntr=0.3,0.1

Type RM Length L Ch R = 1 ,9335    ,247,247,247
XS GIS Cut Line= 3
      3868276.17      10059108.4       3867984.5     10058949.55
      3867836.38     10058893.44
#Sta/Elev= 30
       0  102.74      10  103.03    32.2  101.48    42.3  102.21      55  101.52
      86  101.45   100.6  100.28   107.8   100.8   113.5   99.59   123.3   99.87
   135.4    98.3   180.3    96.9   195.2      97   225.8   95.27   260.7   96.17
   276.9   94.48     293   96.57   320.6   94.93   332.1   95.38   368.1   94.51
   373.4   95.56     382    95.9     423   95.84   428.4   96.58   446.2   96.74
   458.5   97.72   467.6   97.51     478   98.36   487.1  100.91   490.5  100.91
#Mann= 3 , 0 , 0
       0     .15       0   260.7     .09       0     293     .15       0
Bank Sta=260.7,293
XS Rating Curve= 0 ,0
Exp/Cntr=0.3,0.1

Type RM Length L Ch R = 1 ,9088    ,503,503,503
XS GIS Cut Line= 3
      3868274.71     10058429.71      3868046.75     10058765.42
      3867793.53     10058886.98
#Sta/Elev= 30
       0   104.2    13.7  102.87    20.4  101.07    35.4    99.2    86.3   99.01
   122.2  100.39   128.2   99.66   143.2   99.86   215.1   96.92     236   95.43
   301.9   95.04   328.9   93.64   358.8   94.55   364.8   95.39   373.7   94.94
   379.8   95.96   405.8   95.88   408.7   94.82   431.4   95.67     454   94.65
   476.6   94.72   482.2   93.99   521.9   95.83   559.9   96.24   567.2    95.7
   582.1   97.46   604.2   97.03   648.6  100.28   663.4   99.47   685.6  101.45
#Mann= 3 , 0 , 0
       0     .15       0   379.8     .09       0   521.9     .15       0
Bank Sta=379.8,521.9
XS Rating Curve= 0 ,0
Exp/Cntr=0.3,0.1

Type RM Length L Ch R = 1 ,8585    ,659,659,659
XS GIS Cut Line= 3
      3868133.63     10058432.43      3867629.07     10058575.66
      3867243.44     10058707.01
#Sta/Elev= 30
       0  103.46       6  103.21    12.3  101.06    17.5  102.17    26.8   99.95
    46.2    98.2    99.6   95.33   172.3      97   192.2   98.45   203.5  100.64
   270.4   100.1   286.7   97.74   328.3   97.33   377.3   94.63   382.5   95.61
   411.2    94.7   416.4   96.42   432.2   95.22   463.4   96.53     505   95.08
   528.4   92.95   554.5   96.59   610.3   96.49   622.5   98.08   631.4   96.38
   648.6   95.63   679.9   98.02   747.9     100     868   99.39   930.4  100.55
#Mann= 3 , 0 , 0
       0     .15       0   463.4     .09       0   554.5     .15       0
Bank Sta=463.4,554.5
XS Rating Curve= 0 ,0
Exp/Cntr=0.3,0.1

Type RM Length L Ch R = 1 ,7950    ,128,128,128
XS GIS Cut Line= 3
      3867966.46     10058029.86      3867204.31     10058291.37
      3866807.52     10058371.68
#Sta/Elev= 30
       0  100.19    84.6   96.65   125.4   96.73   167.7   98.56   324.1   99.01
   386.6   97.74   423.2   95.85   449.2   96.16   454.5   97.16   485.7   95.45
   511.7   96.36     517   95.25   568.9   97.11   574.2   96.09   622.3   95.86
   717.4   92.14   738.6   92.93   749.2   94.56   761.8      94   787.8   90.11
   853.2      92   873.6   91.15   914.4   93.77     945    92.5   975.6   95.44
   980.7   94.71  1006.2   96.37  1031.4   96.69  1067.4   95.29  1210.6  100.12
#Mann= 3 , 0 , 0
       0     .15       0   761.8     .09       0   914.4     .15       0
Bank Sta=761.8,914.4
XS Rating Curve= 0 ,0
Exp/Cntr=0.3,0.1

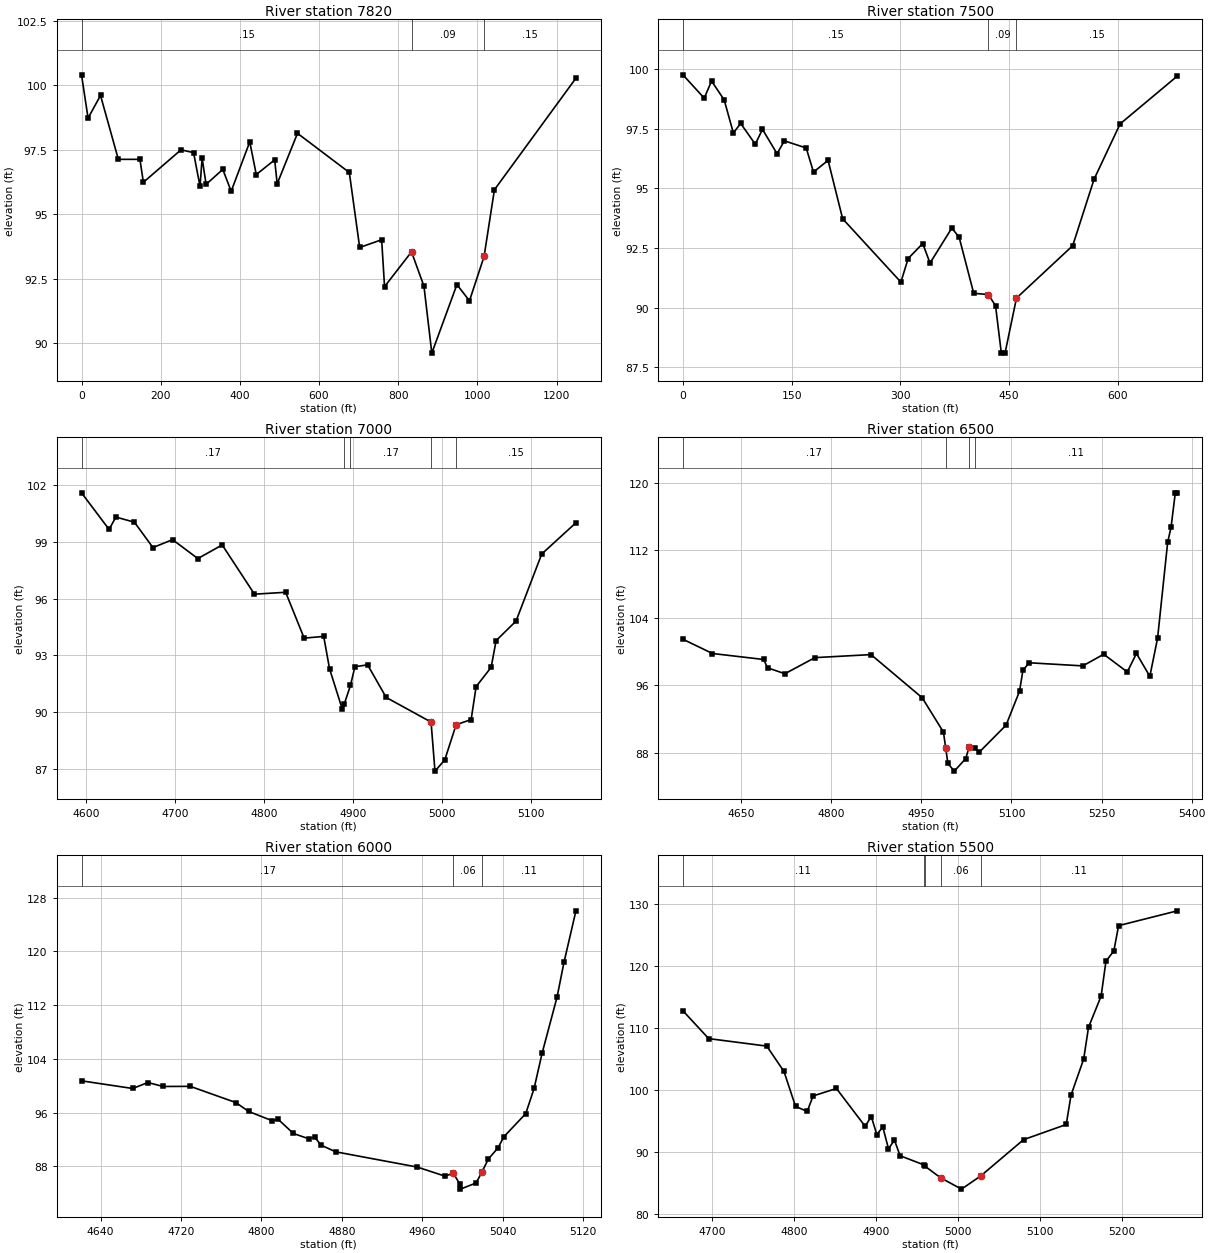
Type RM Length L Ch R = 1 ,7820    ,323,323,323
XS GIS Cut Line= 2
      3868025.91     10057879.87      3866843.11     10058280.52
#Sta/Elev= 30
       0  100.41    16.6   98.73      48   99.61      93   97.13   147.5   97.13
   156.3   96.24   251.3    97.5     283   97.39   299.4   96.08   304.6   97.18
   314.7   96.16   356.9   96.74     378   95.89     425   97.81   441.4   96.54
   487.9   97.11   494.2   96.18   545.5   98.14   676.4   96.62   702.6   93.71
   758.1   94.01   765.4   92.19   833.5   93.54   864.9   92.21   884.8   89.61
   948.2   92.27   979.9   91.64  1016.8   93.36  1042.9   95.95  1248.8  100.28
#Mann= 3 , 0 , 0
       0     .15       0   833.5     .09       0  1016.8     .15       0
Bank Sta=833.5,1016.8
XS Rating Curve= 0 ,0
Exp/Cntr=0.3,0.1

Type RM Length L Ch R = 1 ,7500    ,500,500,500
XS GIS Cut Line= 3
      3867687.14     10057840.22      3867246.99      10057883.9
      3867024.76     10057793.42
#Sta/Elev= 30
       0   99.77    29.4   98.79    39.5   99.51    56.9   98.72    69.6   97.33
    79.7   97.73    99.8   96.86   109.8   97.48   129.9   96.46     140      97
   170.1    96.7   180.2   95.69   200.3   96.18   220.4   93.73   300.8   91.07
   310.8   92.06   330.9   92.69     341   91.87   371.1   93.34   381.2   92.95
   401.3    90.6   421.4   90.55   431.4   90.08   439.4   88.09   444.5   88.09
   460.3    90.4   537.9    92.6   567.4   95.39   603.3   97.71   682.3   99.72
#Mann= 3 , 0 , 0
       0     .15       0   421.4     .09       0   460.3     .15       0
Bank Sta=421.4,460.3
XS Rating Curve= 0 ,0
Exp/Cntr=0.3,0.1

Type RM Length L Ch R = 1 ,7000    ,500,500,500
BEGIN DESCRIPTION:
Crystal Creek 053 13.0
END DESCRIPTION:
XS GIS Cut Line= 3
      3867662.14     10057740.61      3867398.88     10057432.45
      3867263.31     10057365.95
#Sta/Elev= 30
  4594.7  101.58  4625.7   99.65  4633.4   100.3  4654.2  100.03  4675.1   98.69
  4697.1   99.11  4725.6   98.11    4753   98.83  4789.3   96.23  4824.4   96.33
  4845.2   93.91  4867.2      94  4873.8   92.29  4888.1   90.16  4890.4   90.44
  4897.3   91.41  4902.3    92.4  4916.6    92.5  4937.5   90.78    4988   89.48
  4992.4   86.89  5003.4   87.48  5016.2   89.34  5033.1   89.61  5038.7   91.35
  5055.6   92.37  5061.2   93.78  5083.6   94.81  5112.5   98.35    5151     100
#Mann= 5 ,-1 , 0
  4594.7     .17       0  4890.4     .15       0  4897.3     .17       0
    4988     .09       0  5016.2     .15       0
Bank Sta=4988,5016.2
XS Rating Curve= 0 ,0
Exp/Cntr=0.3,0.1

Type RM Length L Ch R = 1 ,6500    ,500,500,500
BEGIN DESCRIPTION:
Crystal Creek 053 12.0
END DESCRIPTION:
XS GIS Cut Line= 3
      3867985.31     10057501.86      3867713.85     10057146.86
      3867376.81     10056979.74
#Sta/Elev= 30
  4553.1  101.46  4602.3   99.77  4687.6   99.06  4693.9   98.07  4722.9   97.37
  4772.8   99.28  4866.2   99.64  4951.4   94.52  4986.8   90.44 4990.4988.58492
  4994.2   86.72  5004.9   85.81  5023.9    87.3  5029.4   88.64  5038.7   88.55
  5046.3   88.05  5091.1   91.27  5113.5    95.3  5119.1   97.77  5129.5   98.67
  5218.8    98.3  5253.6   99.68  5292.9   97.58  5308.1   99.78  5330.4   97.06
  5343.3  101.59  5360.1  112.98  5365.7  114.74  5372.8  118.84  5376.2  118.84
#Mann= 4 ,-1 , 0
  4553.1     .17       0 4990.49     .06       0  5029.4     .17       0
  5038.7     .11       0
Bank Sta=4990.49,5029.4
XS Rating Curve= 0 ,0
Exp/Cntr=0.3,0.1

Type RM Length L Ch R = 1 ,6000    ,500,500,500
BEGIN DESCRIPTION:
Crystal Creek 053 11.0
END DESCRIPTION:
XS GIS Cut Line= 3
       3868216.7      10057003.2      3867900.19      10056794.9
      3867801.38     10056740.92
#Sta/Elev= 30
  4621.1  100.74    4672    99.6  4687.1  100.49  4702.2    99.9  4729.2   99.92
  4774.5   97.51  4787.3   96.18  4810.6   94.81  4816.6   95.01  4831.7   92.91
  4846.8   92.13  4852.8   92.39  4859.1   91.18  4873.8   90.18  4954.9   87.91
  4982.3   86.57  4990.8   86.99  4997.3   85.34  4997.8   84.63  5013.4   85.55
  5019.1   87.16  5025.5    89.1  5035.2   90.78  5040.9   92.41  5062.7   95.86
    5071    99.6  5078.9  104.81  5093.8  113.17  5100.7  118.35  5112.6  126.03
#Mann= 3 , 0 , 0
  4621.1     .17       0  4990.8     .06       0  5019.1     .11       0
Bank Sta=4990.8,5019.1
XS Rating Curve= 0 ,0
Exp/Cntr=0.3,0.1

Type RM Length L Ch R = 1 ,5500    ,501,501,501
BEGIN DESCRIPTION:
Crystal Creek 053 10.0
END DESCRIPTION:
XS GIS Cut Line= 3
      3868152.83     10056211.55       3867924.4     10056456.86
      3867784.36     10056685.48
#Sta/Elev= 30
  4664.8  112.77  4696.2  108.28  4767.1  107.07  4788.1  102.98  4802.2   97.34
  4816.4   96.53  4823.7   99.03  4852.1  100.23  4887.2   94.12  4894.6   95.71
  4901.4    92.8  4908.7   94.02  4915.6   90.51  4922.9   91.89  4929.8   89.38
  4958.5   87.92  4959.6   87.75  4979.1   85.83  5004.7   83.99  5028.4   86.14
  5080.4   91.97  5132.5   94.42  5138.4   99.17  5153.8  104.98  5159.7   110.1
  5175.1  115.15    5181  120.78  5190.6  122.42  5196.4  126.51  5268.1   128.9
#Mann= 5 ,-1 , 0
  4664.8     .11       0  4958.5     .17       0  4959.6     .11       0
  4979.1     .06       0  5028.4     .11       0
Bank Sta=4979.1,5028.4
XS Rating Curve= 0 ,0
Exp/Cntr=0.3,0.1