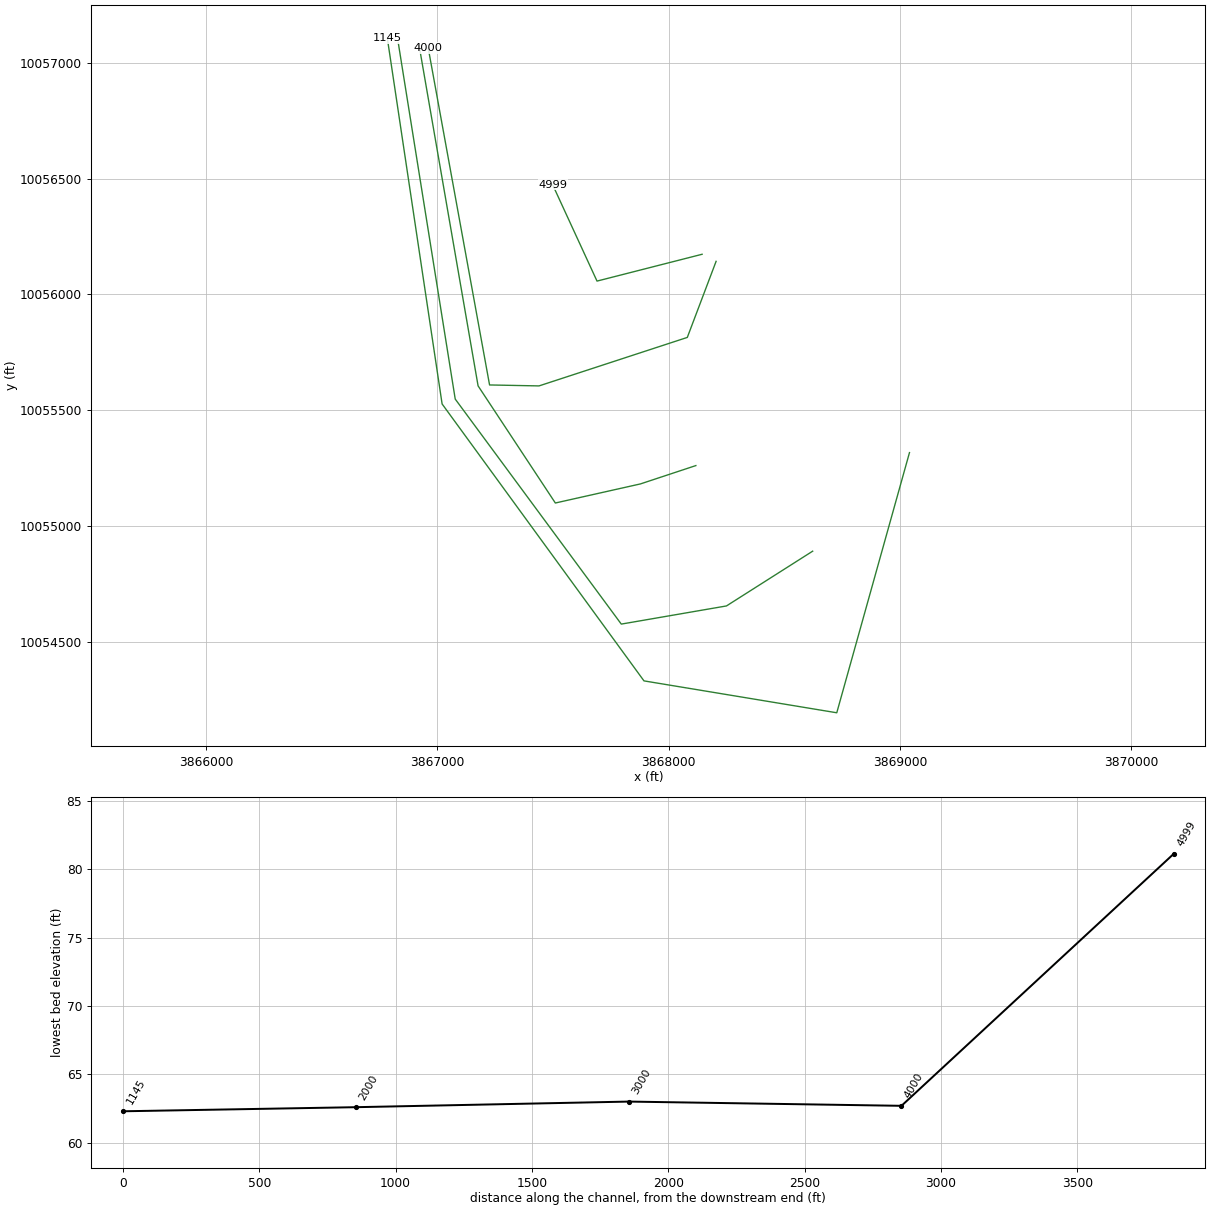
HEC-RAS study Crystal Creek 053.prj: Crystal Creek 053 Base Level Engineering

--- Crystal Creek 053.g01 (geometry) --- (continued)

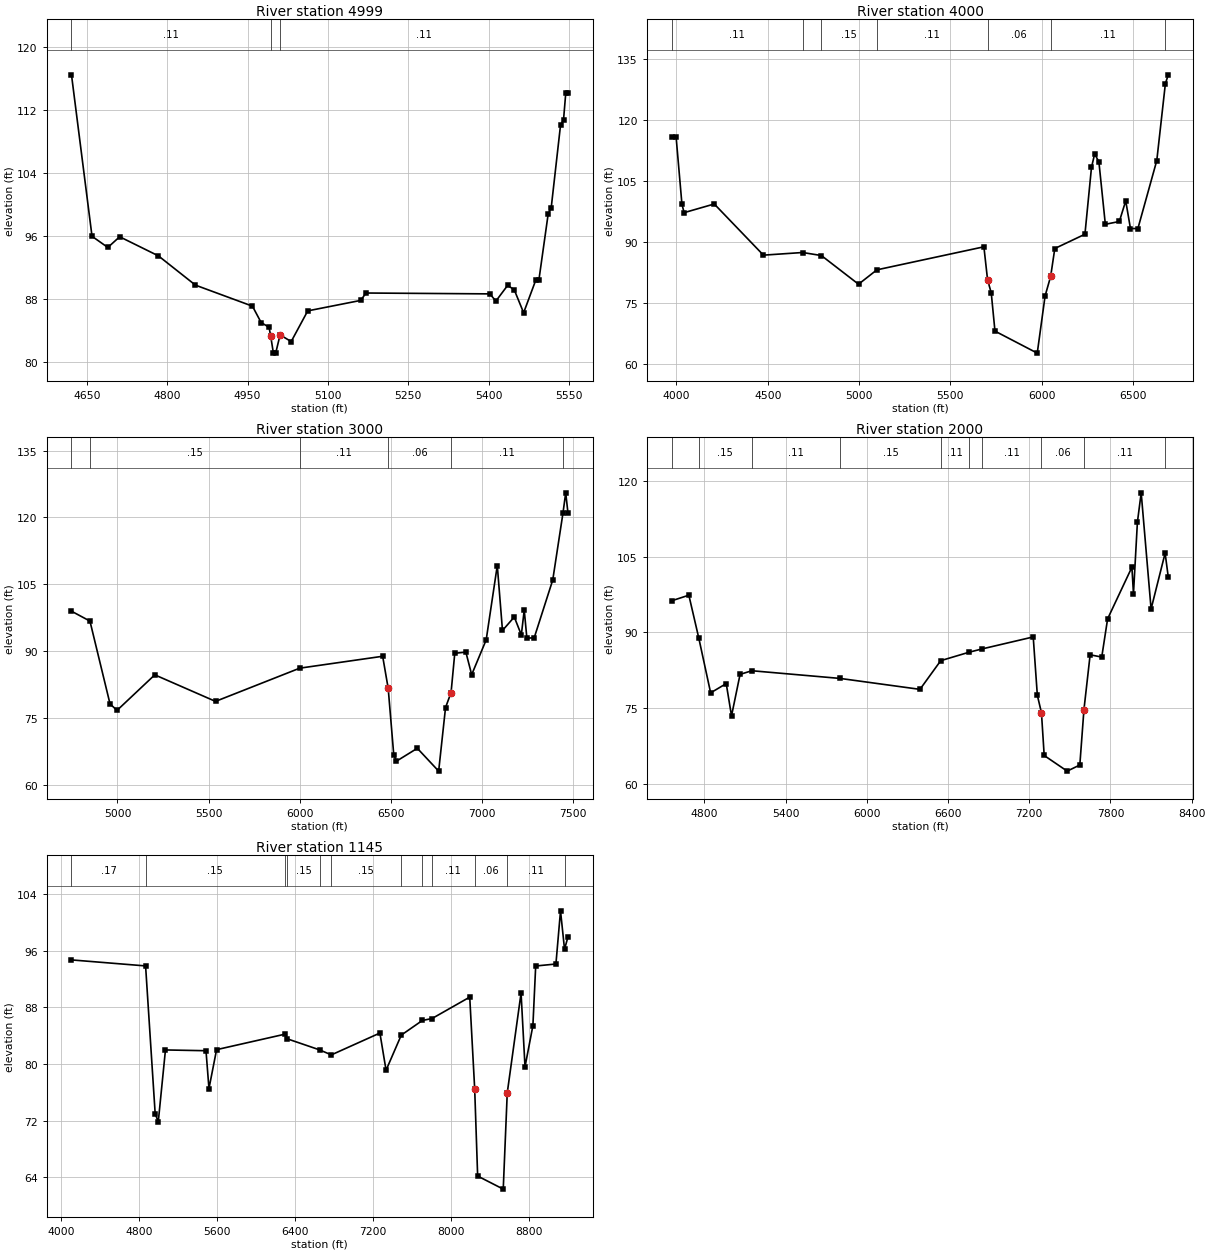
Type RM Length L Ch R = 1 ,4999    ,999,999,999
BEGIN DESCRIPTION:
Crystal Creek 053 9.0
END DESCRIPTION:
XS GIS Cut Line= 3
        3868145.     10056173.74      3867690.62     10056057.87
       3867499.2     10056473.26
#Sta/Elev= 30
  4621.5  116.52  4659.8      96  4689.3   94.58  4711.4   95.94  4783.7   93.51
  4852.8   89.79  4959.1   87.12  4975.4   85.03  4990.1   84.44 4993.0983.35666
  4998.2   81.15  5002.5   81.15  5010.7   83.47  5031.4   82.62  5062.3   86.52
  5161.1   87.85    5171   88.79  5402.2   88.68  5413.3   87.76  5435.3   89.76
  5447.6    89.2  5465.1   86.28  5488.1   90.49  5493.6   90.45    5511   98.88
  5516.5   99.59    5534  110.15  5539.5  110.76  5543.8  114.27  5547.8  114.27
#Mann= 3 , 0 , 0
  4621.5     .11       0 4993.09     .09       0  5010.7     .11       0
Bank Sta=4993.09,5010.7
XS Rating Curve= 0 ,0
Exp/Cntr=0.3,0.1

Type RM Length L Ch R = 1 ,4000    ,1000,1000,1000
BEGIN DESCRIPTION:
Crystal Creek 053 8.0
END DESCRIPTION:
XS GIS Cut Line= 5
      3868205.38     10056143.16      3868080.94     10055814.59
      3867439.93     10055605.17      3867226.21      10055609.3
      3866961.02     10057064.57
#Sta/Elev= 30
  3974.3  115.91  3997.9  115.86    4030   99.24    4042   97.21  4206.9   99.34
  4476.2   86.77  4691.2   87.42  4793.7   86.67    4997   79.63  5097.5   83.16
  5683.5   88.82  5703.5   80.75  5723.8   77.47  5744.1   68.11  5975.7    62.7
  6018.6   76.74  6049.1   81.55  6071.8    88.4  6236.8   91.91  6272.7  108.34
  6290.1  111.63  6313.3  109.69  6348.5   94.35  6425.2   95.04  6460.2  100.11
  6486.1   93.31  6526.8    93.3  6630.3  110.02  6677.3  128.89    6693  131.07
#Mann= 7 ,-1 , 0
  3974.3     .11       0  4691.2     .17       0  4793.7     .15       0
  5097.5     .11       0  5703.5     .06       0  6049.1     .11       0
  6677.3     .17       0
Bank Sta=5703.5,6049.1
XS Rating Curve= 0 ,0
Exp/Cntr=0.3,0.1

Type RM Length L Ch R = 1 ,3000    ,1000,1000,1000
BEGIN DESCRIPTION:
Crystal Creek 053 6.0
END DESCRIPTION:
XS GIS Cut Line= 5
      3868117.88     10055261.08      3867878.24     10055181.87
      3867510.54     10055099.47      3867176.58     10055605.27
      3866921.96     10057073.23
#Sta/Elev= 30
  4747.6   98.92  4848.9    96.7  4959.1   78.11  4997.6   76.65  5204.8   84.63
  5538.2   78.67  6000.7   86.13  6455.7    88.8  6486.1   81.59  6516.6   66.67
  6531.6   65.25  6645.9   68.14  6763.1   63.01  6800.8   77.27  6831.2   80.66
  6851.5   89.47  6912.4   89.73  6944.4   84.67    7024   92.49  7084.9  109.18
  7113.4   94.59  7178.2   97.62  7216.9    93.6  7232.8   99.17  7247.3   92.89
  7287.4   92.93  7389.4  105.94  7445.7  121.02  7460.5   125.5  7472.8  121.02
#Mann= 6 ,-1 , 0
  4747.6     .17       0  4848.9     .15       0  6000.7     .11       0
  6486.1     .06       0  6831.2     .11       0  7445.7     .17       0
Bank Sta=6486.1,6831.2
XS Rating Curve= 0 ,0
Exp/Cntr=0.3,0.1

Type RM Length L Ch R = 1 ,2000    ,855,855,855
BEGIN DESCRIPTION:
Crystal Creek 053 4.0
END DESCRIPTION:
XS GIS Cut Line= 5
      3868622.85     10054891.46      3868250.18     10054654.92
      3867795.54     10054576.51      3867077.76     10055548.29
       3866831.7     10057086.15
#Sta/Elev= 30
  4558.6   96.27  4684.7   97.37  4758.2   88.89  4845.7   78.07  4960.9    79.9
    5000   73.52  5063.2   81.72    5150   82.44  5802.3   80.92  6392.4   78.76
  6545.9   84.43  6755.3    86.1  6854.3   86.77  7229.3   89.12  7259.7   77.58
  7290.1   74.14  7310.3   65.69  7480.2    62.6  7573.6   63.81    7604   74.74
  7649.8   85.59  7735.6   85.14  7778.9   92.69  7958.4   102.9    7970   97.66
    7999  111.78    8027   117.6  8100.2   94.64  8203.8  105.68  8226.9  101.01
#Mann= 10 ,-1 , 0
  4558.6     .17       0  4758.2     .15       0    5150     .11       0
  5802.3     .15       0  6545.9     .11       0  6755.3     .17       0
  6854.3     .11       0  7290.1     .06       0    7604     .11       0
  8203.8     .17       0
Bank Sta=7290.1,7604
XS Rating Curve= 0 ,0
Exp/Cntr=0.3,0.1

Type RM Length L Ch R = 1 ,1145    ,0,0,0
BEGIN DESCRIPTION:
Crystal Creek 053 2.0
END DESCRIPTION:
XS GIS Cut Line= 5
      3869041.33     10055317.13      3868726.99     10054193.52
      3867893.62     10054331.25      3867021.05     10055527.21
      3866784.33      10057106.4
#Sta/Elev= 30
  4110.2   94.71  4869.7   93.86    4968   72.95  4999.8   71.84  5073.3   81.98
  5488.9   81.87  5519.3   76.52  5597.3   82.02  6298.5   84.21  6322.2   83.55
  6653.2   81.99  6773.5   81.28  7271.5   84.37  7334.5   79.11  7490.6   84.08
  7706.8   86.15  7805.7   86.42  8192.2   89.45    8243   76.45  8273.3   64.15
  8535.6    62.3  8576.7    75.9  8718.3   90.03  8758.7   79.59  8839.6   85.41
  8868.2   93.85  9075.6   94.13  9122.7  101.65  9163.8   96.23  9198.9   97.94
#Mann= 12 ,-1 , 0
  4110.2     .17       0  4869.7     .15       0  6298.5     .11       0
  6322.2     .15       0  6653.2     .11       0  6773.5     .15       0
  7490.6     .11       0  7706.8     .17       0  7805.7     .11       0
    8243     .06       0  8576.7     .11       0  9163.8     .17       0
Bank Sta=8243,8576.7
XS Rating Curve= 0 ,0
Exp/Cntr=0.3,0.1

Chan Stop Cuts=-1
Use User Specified Reach Order=0
Composite Channel Slope=5

--- Crystal Creek 053.g10 (geometry) ---

Geom Title=Existing Conditions
Program Version=4.10

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
River Reach=Crystal Creek 05,Reach-1

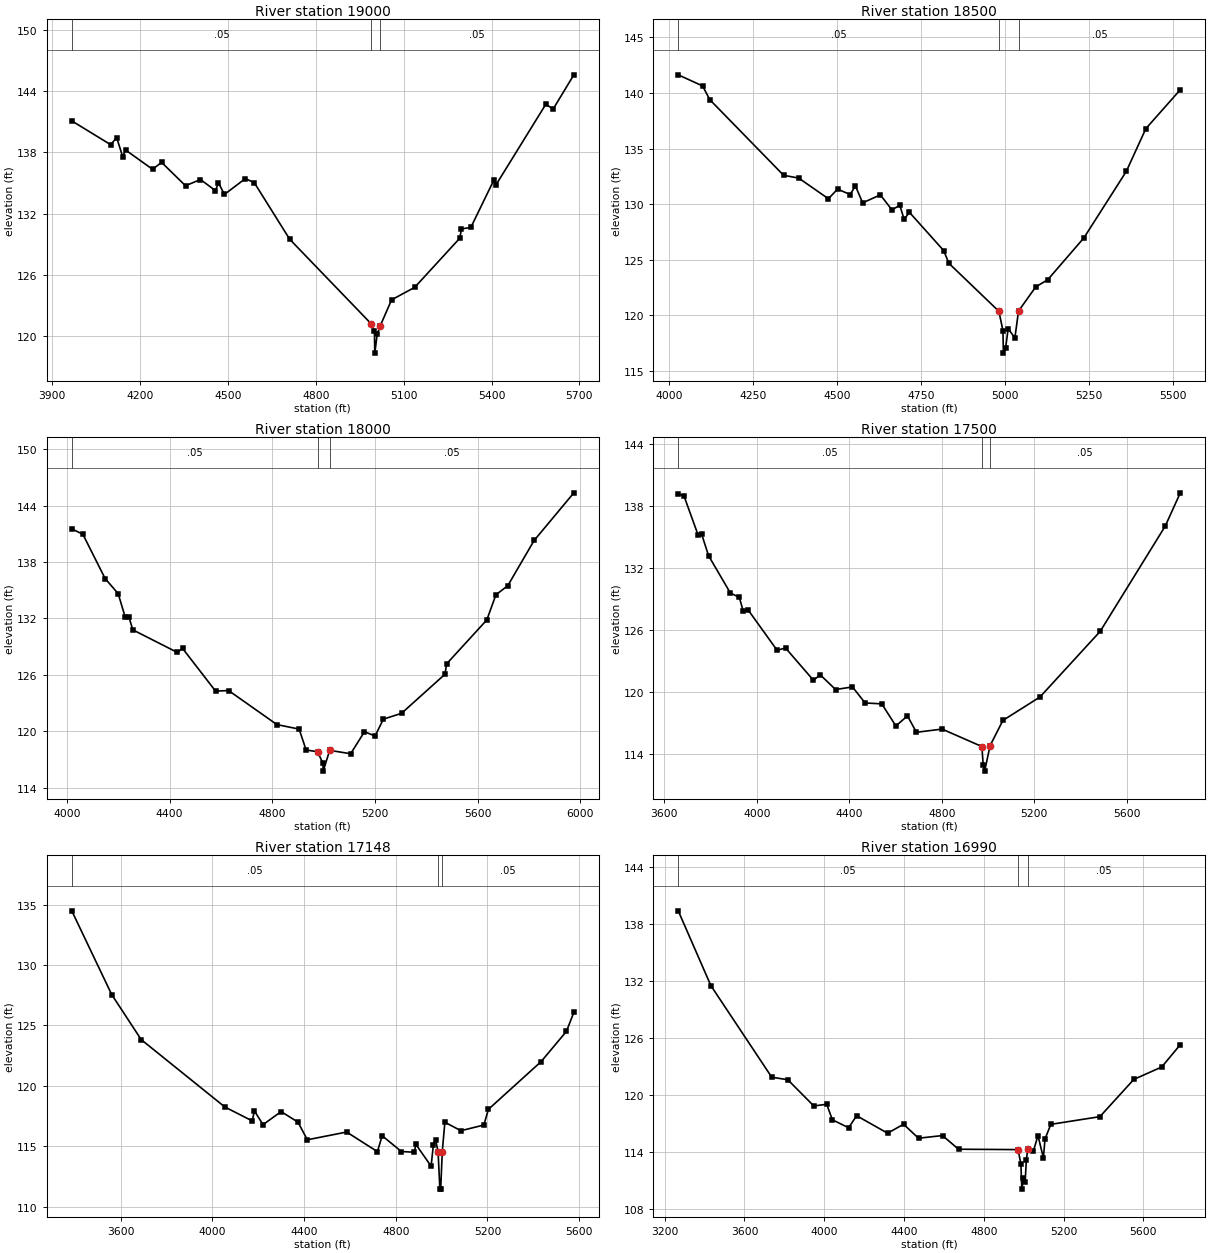
Type RM Length L Ch R = 1 ,19000   ,500,500,500
BEGIN DESCRIPTION:
Crystal Creek 053 37.0
END DESCRIPTION:
XS GIS Cut Line= 3
      3871167.85     10063111.08      3870953.48     10064122.11
      3870717.86     10064761.05
#Sta/Elev= 30
  3966.5  141.09  4099.4  138.76  4119.8  139.46  4140.3  137.59  4150.5  138.23
  4242.5  136.35  4273.2  137.03  4354.9  134.74    4406  135.35  4457.2  134.26
  4467.4  135.02  4487.8  133.89  4559.4  135.44    4590  135.03  4710.7   129.5
  4988.7  121.23    5000  120.47  5001.3  118.35  5009.6  120.23  5020.2  121.04
  5058.6  123.57  5137.5  124.79  5291.4   129.6  5297.3  130.51  5329.3  130.66
  5407.8  135.29  5414.6   134.8  5585.1  142.71  5610.3  142.25    5681   145.6
#Mann= 3 , 0 , 0
  3966.5     .05       0  4988.7     .07       0  5020.2     .05       0
Bank Sta=4988.7,5020.2
XS Rating Curve= 0 ,0
Exp/Cntr=0.3,0.1

Type RM Length L Ch R = 1 ,18500   ,500,500,500
BEGIN DESCRIPTION:
Crystal Creek 053 36.0
END DESCRIPTION:
XS GIS Cut Line= 3
      3871067.85     10063111.08      3870580.24     10063951.47
      3870467.84     10064461.12
#Sta/Elev= 30
  4028.4  141.63  4100.8  140.63  4122.4  139.39  4341.8  132.59  4386.8  132.34
  4475.1  130.48  4502.4  131.35  4539.7  130.86  4555.4  131.64    4577  130.11
  4629.6  130.83  4664.3  129.47  4687.4   129.9  4700.3  128.63  4716.1  129.26
  4817.9  125.82  4833.6  124.67 4982.18 120.353  4994.3  118.62  4995.6  116.59
  5002.4  117.09  5009.8  118.79  5029.8  117.96  5040.6  120.37  5091.8  122.55
  5127.4  123.19  5235.1  126.96  5361.2  132.94  5419.4  136.79  5521.9  140.29
#Mann= 3 , 0 , 0
  4028.4     .05       0 4982.18     .07       0  5040.6     .05       0
Bank Sta=4982.18,5040.6
XS Rating Curve= 0 ,0
Exp/Cntr=0.3,0.1

Type RM Length L Ch R = 1 ,18000   ,500,500,500
BEGIN DESCRIPTION:
Crystal Creek 053 35.0
END DESCRIPTION:
XS GIS Cut Line= 3
      3871017.88     10063111.05      3870209.77     10063666.86
      3869967.85     10064611.07
#Sta/Elev= 30
  4019.2  141.52  4062.5  140.94  4149.1  136.23  4199.9  134.63  4226.9  132.17
  4241.8  132.15  4256.7  130.78  4429.9  128.38  4450.8   128.8  4579.3  124.26
  4630.1  124.32  4818.2   120.7  4904.8  120.22  4931.8     118  4976.5  117.81
  4997.4  116.58  4998.3  115.75  5023.8  117.96  5105.4   117.6  5159.2  119.94
  5200.5  119.49    5233  121.28  5303.7   121.9  5472.6  126.05  5479.2  127.16
  5635.7  131.83  5671.3  134.51  5717.3  135.47  5819.9  140.28  5974.7  145.35
#Mann= 3 , 0 , 0
  4019.2     .05       0  4976.5     .07       0  5023.8     .05       0
Bank Sta=4976.5,5023.8
XS Rating Curve= 0 ,0
Exp/Cntr=0.3,0.1

Type RM Length L Ch R = 1 ,17500   ,352,352,352
BEGIN DESCRIPTION:
Crystal Creek 053 34.0
END DESCRIPTION:
XS GIS Cut Line= 3
      3870918.17     10063035.69      3869726.33     10063646.86
       3869779.3     10064476.37
#Sta/Elev= 30
  3660.6  139.21  3686.2  138.93  3747.2  135.15  3762.1  135.26  3791.6   133.2
    3886  129.58  3924.7  129.16  3941.3  127.84  3963.5  127.92    4088  124.04
  4124.5  124.26  4245.3  121.13  4274.2  121.67  4340.8  120.24  4413.9  120.49
  4468.4  118.94  4540.6  118.85  4601.6  116.71  4651.6  117.69  4690.3   116.1
  4801.3  116.41  4973.3  114.72  4978.9  112.97  4985.3  112.34  5008.9 114.814
  5064.3  117.25  5224.7  119.52  5485.2  125.88  5765.8  136.05  5831.2  139.28
#Mann= 3 , 0 , 0
  3660.6     .05       0  4973.3     .07       0  5008.9     .05       0
Bank Sta=4973.3,5008.9
XS Rating Curve= 0 ,0
Exp/Cntr=0.3,0.1

Type RM Length L Ch R = 1 ,17148   ,158,158,158
BEGIN DESCRIPTION:
Mapping XS 80c55c3d
END DESCRIPTION:
XS GIS Cut Line= 4
      3870818.09     10063063.02      3869382.42     10063520.17
      3869382.75     10063606.97      3869366.79     10064203.56
#Sta/Elev= 30
  3386.6  134.48  3560.7  127.56  3689.6  123.83  4054.5  118.26    4174  117.11
  4183.4  117.94  4220.9   116.8  4299.9  117.88  4373.4  117.01  4414.2  115.55
  4585.8  116.19    4720  114.57  4740.7  115.88  4824.6  114.58  4881.1  114.52
  4887.6  115.17  4954.2  113.37  4964.2  115.14  4974.2  115.52  4984.7  114.54
  4992.5  111.47    4996  111.47 5002.92 114.574  5014.2     117  5084.2   116.3
  5184.3  116.77  5204.3  118.07  5434.4  122.02  5544.4  124.51  5576.9  126.08
#Mann= 3 , 0 , 0
  3386.6     .05       0  4984.7     .07       0 5002.92     .05       0
Bank Sta=4984.7,5002.92
XS Rating Curve= 0 ,0
Exp/Cntr=0.3,0.1

Type RM Length L Ch R = 1 ,16990   ,593,593,593
BEGIN DESCRIPTION:
Crystal Creek 053 33.0
END DESCRIPTION:
XS GIS Cut Line= 4
      3870914.73     10063014.84      3869367.72     10063427.47
      3869189.04     10063664.15      3869174.09     10064284.23
#Sta/Elev= 30
  3267.8   139.4  3431.6  131.52  3736.8  121.88    3817  121.62  3947.6  118.86
  4012.4  119.03  4040.8   117.4  4122.3  116.56  4162.4  117.83  4317.6  115.99
  4397.8  116.93  4472.9  115.46  4593.2  115.74  4673.4   114.3    4972  114.26
  4986.2  112.75    4991   110.1  4999.1  111.26  5007.4  110.81  5013.6  113.18
 5020.41  114.28    5049  114.11  5071.9  115.74    5099  113.39  5107.3  115.39
  5136.4  116.92  5382.4  117.73  5552.5  121.65  5692.5  122.96  5785.7  125.31
#Mann= 3 , 0 , 0
  3267.8     .05       0    4972     .07       0 5020.41     .05       0
Bank Sta=4972,5020.41
XS Rating Curve= 0 ,0
Exp/Cntr=0.3,0.1

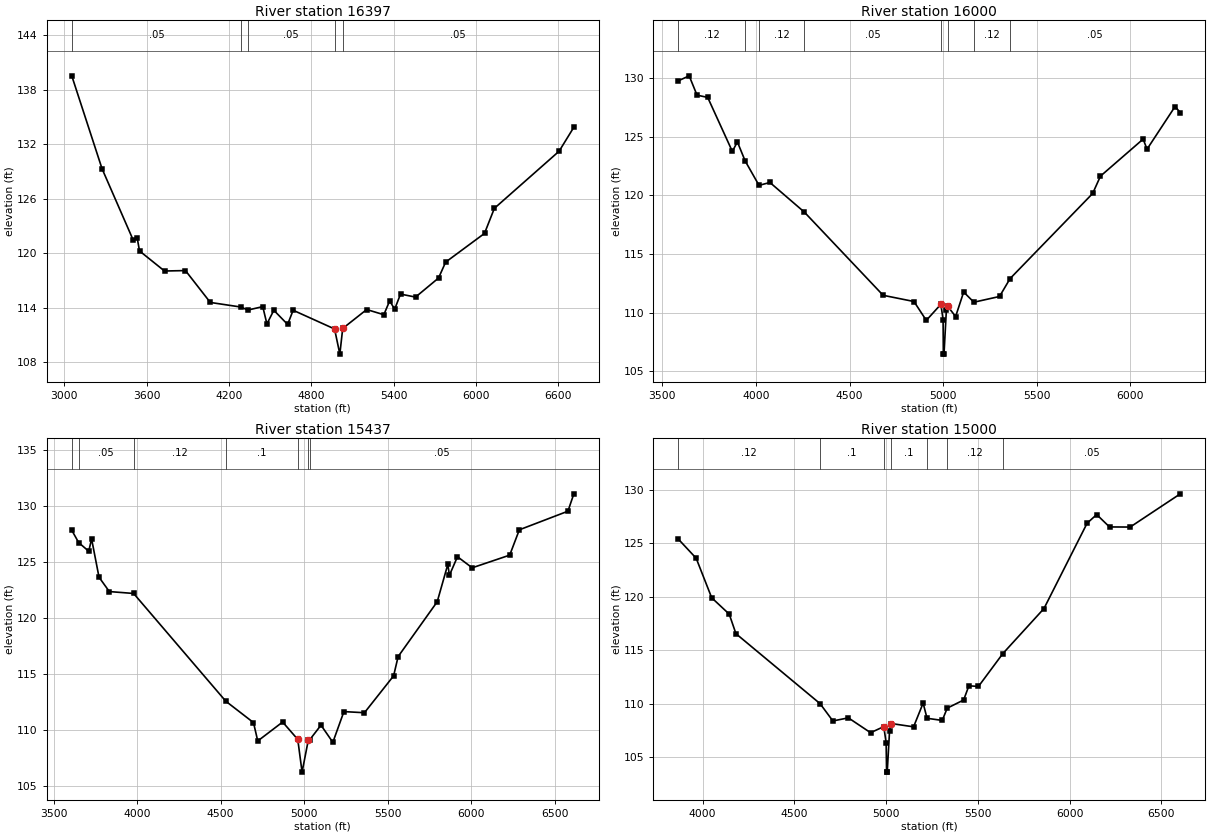
Type RM Length L Ch R = 1 ,16397   ,397,397,397
BEGIN DESCRIPTION:
Crystal Creek 053 32.0
END DESCRIPTION:
XS GIS Cut Line= 3
      3870911.22     10062941.93      3868957.88     10063156.42
      3868060.32     10064592.17
#Sta/Elev= 30
  3055.4  139.56  3275.8  129.34  3501.4  121.53  3531.6  121.75  3549.1  120.28
  3731.2  118.07  3883.7  118.12  4064.8  114.61  4289.3   114.1    4338  113.77
  4447.1  114.15  4477.3  112.24  4527.6  113.75  4628.2  112.19  4668.4  113.75
  4970.2  111.69  5008.7  108.92 5029.49 111.744  5204.3  113.83  5329.2  113.26
  5371.7  114.78  5408.3  113.87  5450.7  115.53  5560.4   115.2  5727.8   117.3
  5779.7  119.05  6062.7  122.21  6134.5  124.97  6606.3  131.26  6713.7   133.9
#Mann= 5 ,-1 , 0
  3055.4     .05       0  4289.3     .12       0    4338     .05       0
  4970.2     .07       0 5029.49     .05       0
Bank Sta=4970.2,5029.49
XS Rating Curve= 0 ,0
Exp/Cntr=0.3,0.1

Type RM Length L Ch R = 1 ,16000   ,563,563,563
BEGIN DESCRIPTION:
Crystal Creek 053 31.0
END DESCRIPTION:
XS GIS Cut Line= 3
      3870017.88     10062061.05        3868846.     10062854.63
      3867867.87     10063661.06
#Sta/Elev= 30
  3584.7  129.77  3643.1   130.2  3685.1  128.55  3742.1  128.36  3873.8  123.75
  3900.8  124.56  3942.2  122.94  4016.5  120.85  4074.5   121.1  4258.6  118.57
  4679.6  111.47  4844.4  110.94  4910.3  109.33  4988.2   110.7    5000   109.4
  5001.4  106.45  5004.9  106.45  5017.5  110.19    5024  110.54    5067  109.66
    5110  111.75  5164.6  110.88  5301.6  111.37  5358.2   112.9  5799.3  120.16
    5841  121.64    6069   124.8  6089.9  123.94  6239.7  127.58  6267.7  127.06
#Mann= 8 ,-1 , 0
  3584.7     .12       0  3942.2     .05       0  4016.5     .12       0
  4258.6     .05       0  4988.2     .07       0    5024     .05       0
  5164.6     .12       0  5358.2     .05       0
Bank Sta=4988.2,5024
XS Rating Curve= 0 ,0
Exp/Cntr=0.3,0.1

Type RM Length L Ch R = 1 ,15437   ,437,437,437
BEGIN DESCRIPTION:
Crystal Creek 053 30.0
END DESCRIPTION:
XS GIS Cut Line= 3
      3869909.77     10062052.61      3868557.36     10062532.63
      3867717.88     10063861.03
#Sta/Elev= 30
  3608.3  127.86  3649.6  126.76  3709.7  125.99  3727.1  127.08  3771.5  123.67
  3833.2  122.39  3978.7  122.22  4530.4  112.61  4696.4   110.7    4722  109.06
    4871  110.75 4961.61 109.197  4987.4  106.28  5025.3  109.19  5033.8  109.18
  5100.7  110.47  5171.7  108.94  5237.9  111.68  5360.9  111.58  5535.5  114.87
  5562.6  116.59  5796.6  121.48  5860.2  124.82  5869.6  123.84  5917.9   125.5
  6006.1  124.51  6230.7  125.64  6288.4   127.9  6579.4  129.56  6614.8  131.11
#Mann= 7 ,-1 , 0
  3608.3     .12       0  3649.6     .05       0  3978.7     .12       0
  4530.4      .1       0 4961.61     .07       0  5025.3      .1       0
  5033.8     .05       0
Bank Sta=4961.61,5025.3
XS Rating Curve= 0 ,0
Exp/Cntr=0.3,0.1

Type RM Length L Ch R = 1 ,15000   ,498,498,498
BEGIN DESCRIPTION:
Crystal Creek 053 29.0
END DESCRIPTION:
XS GIS Cut Line= 3
      3869518.27     10061933.68      3868415.38       10062194.
      3867767.86     10063661.06
#Sta/Elev= 30
  3866.8  125.41  3964.6  123.61  4049.2  119.91  4144.7  118.38  4181.3  116.55
  4639.9     110  4709.8  108.38  4794.2  108.67  4915.3  107.28  4987.2  107.85
    5000  106.35  5002.5  103.59    5006  103.59  5018.7  107.45  5027.6  108.14
  5149.6  107.83  5201.7  110.05    5223  108.63  5305.9  108.43  5333.1  109.58
  5422.4  110.34  5451.2  111.67  5503.3  111.61  5635.9  114.68  5860.3   118.9
  6095.6  126.89  6147.7   127.7  6217.7  126.54  6330.3  126.53  6603.6  129.64
#Mann= 7 ,-1 , 0
  3866.8     .12       0  4639.9      .1       0  4987.2     .07       0
  5027.6      .1       0    5223     .05       0  5333.1     .12       0
  5635.9     .05       0
Bank Sta=4987.2,5027.6
XS Rating Curve= 0 ,0
Exp/Cntr=0.3,0.1