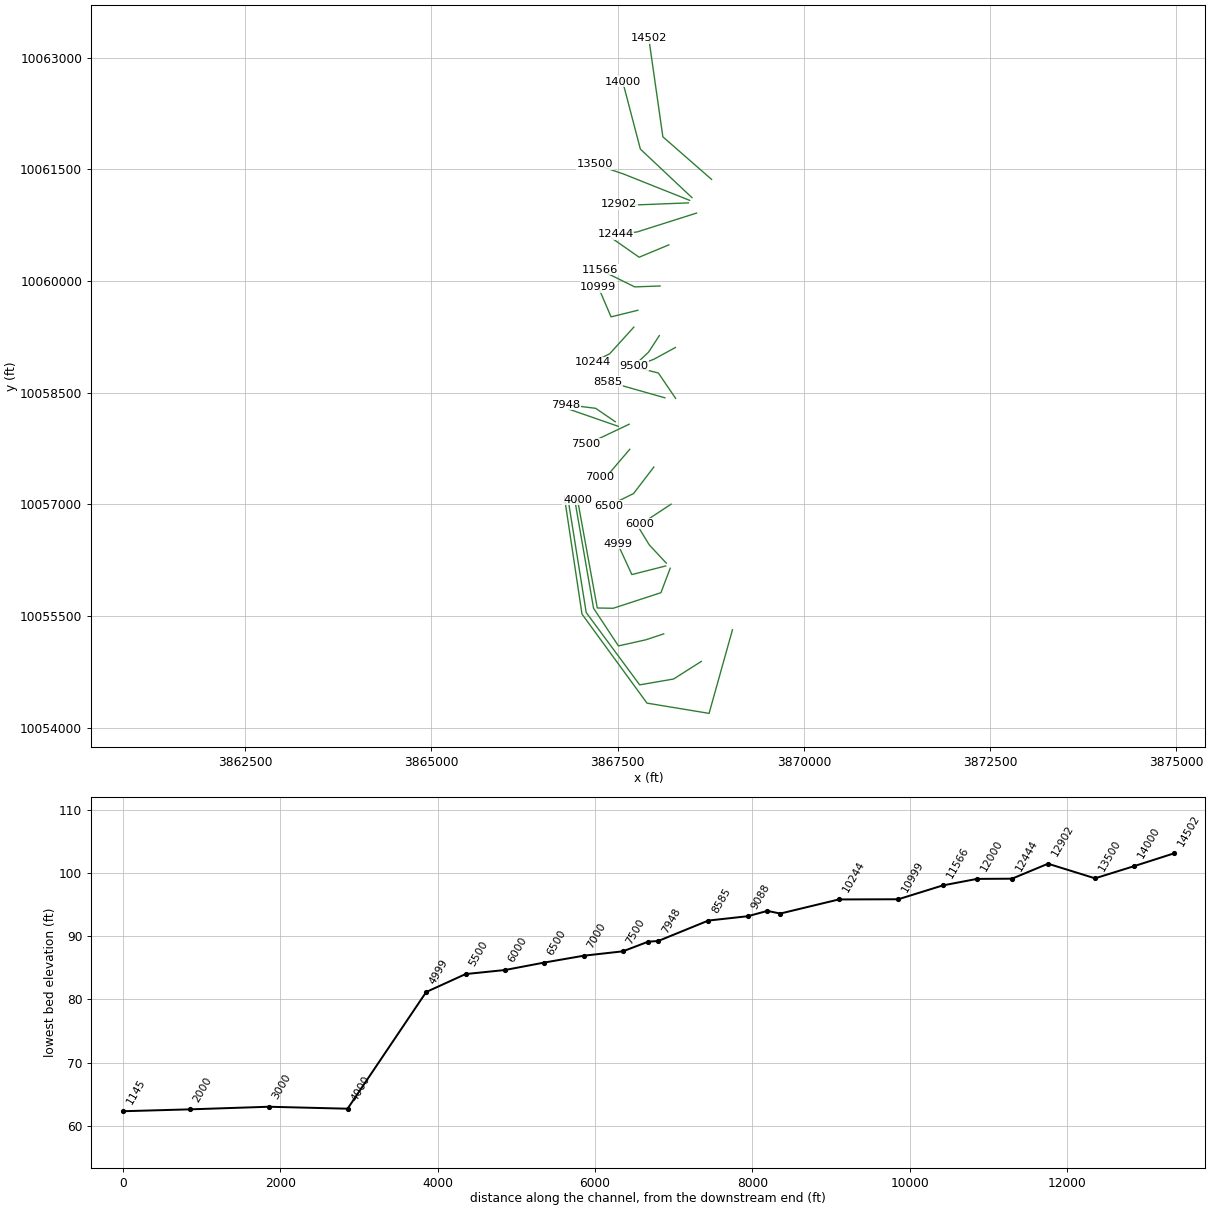
HEC-RAS study Crystal Creek 053.prj: Crystal Creek 053 Base Level Engineering

--- Crystal Creek 053.g10 (geometry) --- (continued)

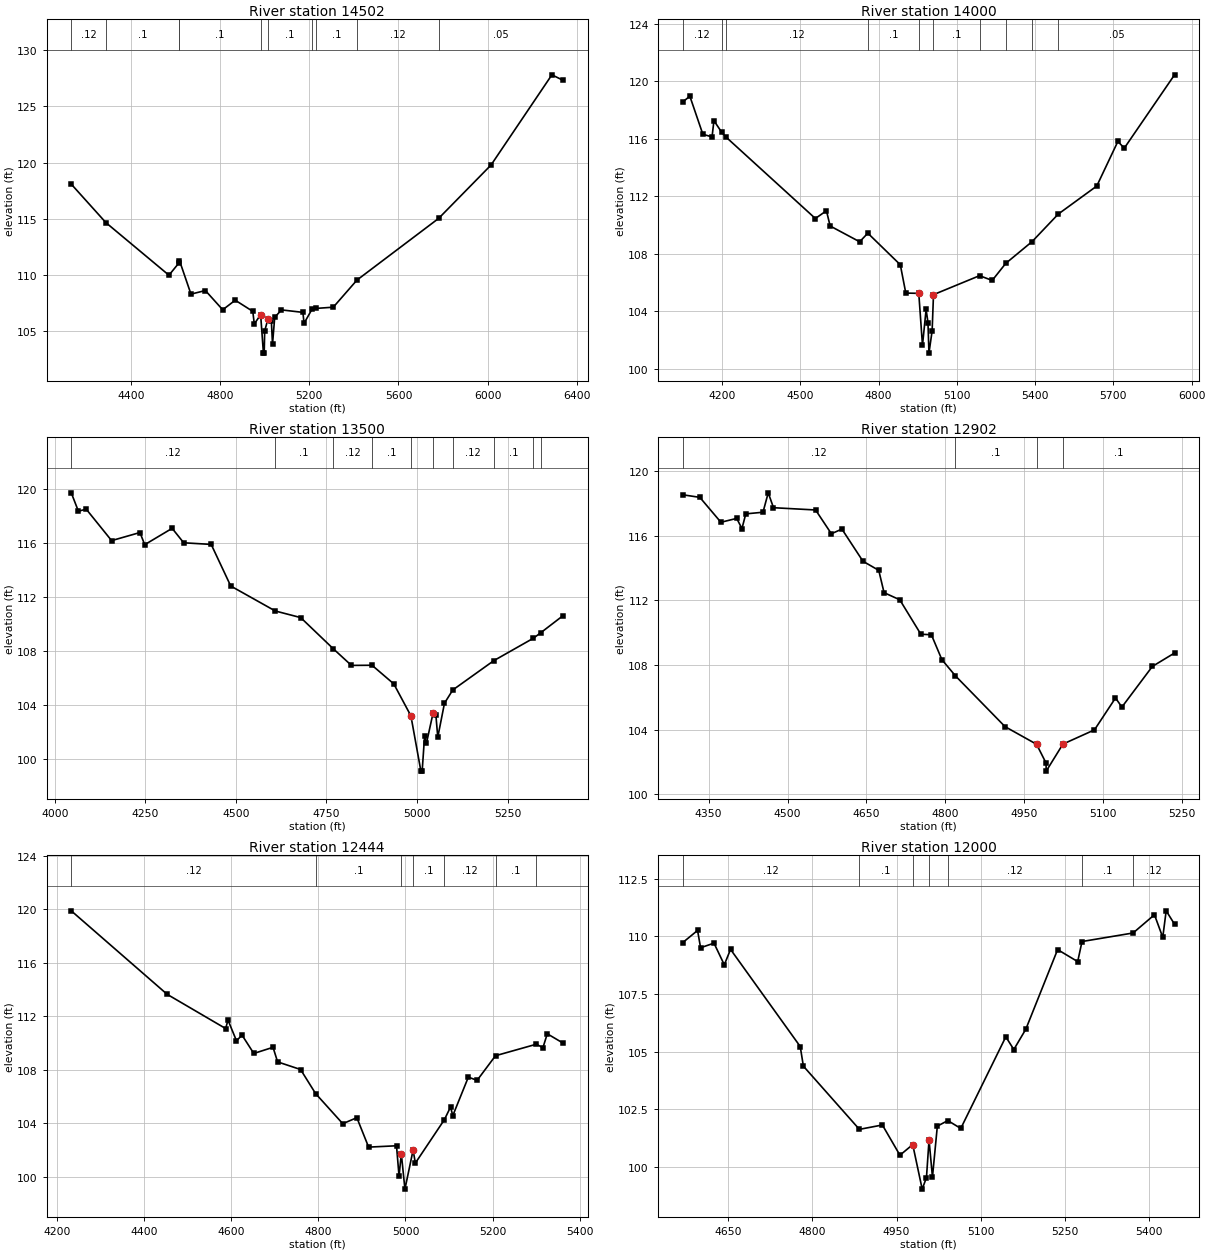
Type RM Length L Ch R = 1 ,14502   ,502,502,502
BEGIN DESCRIPTION:
Crystal Creek 053 28.0
END DESCRIPTION:
XS GIS Cut Line= 3
      3868760.49     10061365.96      3868106.89     10061938.21
      3867917.85     10063261.06
#Sta/Elev= 30
  4133.2  118.08  4288.6  114.66  4571.1  109.99  4615.9  111.08  4618.4  111.29
  4669.8  108.31  4734.4  108.63  4812.2  106.92  4868.2  107.77    4947  106.78
  4953.6  105.66  4982.1  106.48  4994.6  103.07  4998.1  103.07  5000.3  105.04
  5014.9   106.1  5030.2  105.93  5035.3  103.86  5045.2  106.25  5075.5  106.91
  5171.6  106.69  5176.7  105.72  5212.2  106.96  5228.9  107.04  5307.8  107.15
    5414  109.56  5780.2  115.04    6015  119.78  6287.7  127.79  6338.2   127.3
#Mann= 10 ,-1 , 0
  4133.2     .12       0  4288.6      .1       0  4615.9     .12       0
  4618.4      .1       0  4982.1     .07       0  5014.9      .1       0
  5212.2     .12       0  5228.9      .1       0    5414     .12       0
  5780.2     .05       0
Bank Sta=4982.1,5014.9
XS Rating Curve= 0 ,0
Exp/Cntr=0.3,0.1

Type RM Length L Ch R = 1 ,14000   ,500,500,500
BEGIN DESCRIPTION:
Crystal Creek 053 27.0
END DESCRIPTION:
XS GIS Cut Line= 3
      3868497.44      10061121.2      3867804.75     10061773.38
      3867568.08     10062677.31
#Sta/Elev= 30
  4048.6  118.55  4076.3  118.95  4126.1   116.3  4161.3  116.12  4168.6  117.25
  4197.6  116.46  4213.5  116.13  4557.4  110.44  4599.9  110.98    4614  109.92
  4727.3  108.82  4758.5  109.42  4883.1  107.22  4904.1  105.25  4953.9  105.23
  4968.1  101.61    4982  104.11  4989.1   103.2  4992.9  101.07  5005.1  102.62
  5010.3  105.14  5186.8  106.46  5235.4  106.13  5287.5  107.32  5388.2  108.83
  5488.8  110.75  5636.3   112.7  5717.1   115.8  5741.9  115.34  5934.4  120.44
#Mann= 10 ,-1 , 0
  4048.6     .12       0  4197.6      .1       0  4213.5     .12       0
  4758.5      .1       0  4953.9     .07       0  5010.3      .1       0
  5186.8     .05       0  5287.5      .1       0  5388.2     .12       0
  5488.8     .05       0
Bank Sta=4953.9,5010.3
XS Rating Curve= 0 ,0
Exp/Cntr=0.3,0.1

Type RM Length L Ch R = 1 ,13500   ,598,598,598
BEGIN DESCRIPTION:
Crystal Creek 053 26.0
END DESCRIPTION:
XS GIS Cut Line= 3
      3868466.18     10061084.73      3867579.69     10061438.32
      3867197.97      10061569.1
#Sta/Elev= 30
  4045.6  119.74  4065.3  118.38  4086.9  118.53    4157   116.2  4235.2   116.8
  4248.4   115.9  4324.1  117.11    4356  116.04  4431.9  115.92  4485.8  112.84
  4608.8  110.99    4679   110.5  4768.2  108.21    4819  106.96  4875.9  106.97
    4936  105.59 4983.25 103.221  5010.8   99.13  5014.3   99.13  5020.9   101.7
  5026.1  101.19  5044.2  103.41  5052.1   103.3  5057.4  101.64  5075.9  104.16
  5098.8  105.14    5212  107.31  5321.2  108.97  5341.3  109.37  5403.5  110.65
#Mann= 10 ,-1 , 0
  4045.6     .12       0  4608.8      .1       0  4768.2     .12       0
  4875.9      .1       0 4983.25     .07       0  5044.2      .1       0
  5098.8     .12       0    5212      .1       0  5321.2     .12       0
  5341.3      .1       0
Bank Sta=4983.25,5044.2
XS Rating Curve= 0 ,0
Exp/Cntr=0.3,0.1

Type RM Length L Ch R = 1 ,12902   ,458,458,458
BEGIN DESCRIPTION:
Crystal Creek 053 25.0
END DESCRIPTION:
XS GIS Cut Line= 3
      3868450.56     10061050.86      3867718.82     10061022.22
      3867515.67     10061030.03
#Sta/Elev= 30
  4300.5  118.52  4333.2  118.36  4373.3  116.82  4403.3  117.06  4413.3  116.43
  4420.6  117.34  4453.3  117.44  4463.3  118.64  4473.3  117.72  4553.4  117.58
  4583.4  116.11  4603.4   116.4  4643.5  114.41  4673.5  113.85  4683.6  112.47
  4713.5  112.03  4753.6   109.9  4773.6  109.87  4793.6  108.33  4819.3  107.33
  4913.7  104.19  4973.7   103.1  4991.7  101.94    4992  101.44  5023.8  103.11
  5083.8  103.99  5123.8  105.96    5136   105.4  5193.9  107.91  5236.1  108.74
#Mann= 4 ,-1 , 0
  4300.5     .12       0  4819.3      .1       0  4973.7     .03       0
  5023.8      .1       0
Bank Sta=4973.7,5023.8
XS Rating Curve= 0 ,0
Exp/Cntr=0.3,0.1

Type RM Length L Ch R = 1 ,12444   ,444,444,444
BEGIN DESCRIPTION:
Crystal Creek 053 24.0
END DESCRIPTION:
XS GIS Cut Line= 3
      3868559.11     10060913.71      3867760.48     10060660.24
      3867471.73     10060627.39
#Sta/Elev= 30
  4233.2  119.87  4453.2  113.63  4587.5  111.07  4592.7  111.71  4612.2  110.16
    4625  110.58    4652  109.21  4696.1  109.67  4706.6  108.58  4759.3  108.01
  4793.8  106.21  4856.1  103.96  4888.4  104.41  4915.4  102.21  4979.4  102.31
  4985.2  100.04  4990.4  101.72  4998.7   99.07  5017.4  101.98  5022.7  101.02
  5089.2  104.26  5103.4  105.21  5108.5  104.56  5144.2  107.44  5164.3   107.2
  5206.5  109.04  5300.2   109.9  5315.3  109.64  5325.3  110.68  5361.7  109.98
#Mann= 7 ,-1 , 0
  4233.2     .12       0  4793.8      .1       0  4990.4     .07       0
  5017.4      .1       0  5089.2     .12       0  5206.5      .1       0
  5300.2     .12       0
Bank Sta=4990.4,5017.4
XS Rating Curve= 0 ,0
Exp/Cntr=0.3,0.1

Type RM Length L Ch R = 1 ,12000   ,434,434,434
BEGIN DESCRIPTION:
Crystal Creek 053 23.0
END DESCRIPTION:
XS GIS Cut Line= 3
      3868186.65     10060486.61      3867788.38     10060320.82
      3867422.97     10060576.18
#Sta/Elev= 30
  4568.6  109.72  4595.2  110.25  4600.6   109.5  4624.5   109.7  4642.9  108.76
    4654  109.43  4778.3  105.22  4783.9  104.37  4883.8  101.63  4924.8  101.82
  4956.1  100.51  4978.9  100.97  4995.8   99.04  5003.4   99.54    5008  101.17
  5014.1   99.56  5022.8  101.77  5041.5  102.01  5064.6  101.67  5144.9  105.64
  5159.2  105.09  5180.6  105.97  5237.3  109.42  5273.1   108.9  5280.8  109.77
  5371.9  110.14    5410  110.93  5424.8  109.95  5430.9   111.1  5445.8  110.52
#Mann= 7 ,-1 , 0
  4568.6     .12       0  4883.8      .1       0  4978.9     .07       0
    5008      .1       0  5041.5     .12       0  5280.8      .1       0
  5371.9     .12       0
Bank Sta=4978.9,5008
XS Rating Curve= 0 ,0
Exp/Cntr=0.3,0.1

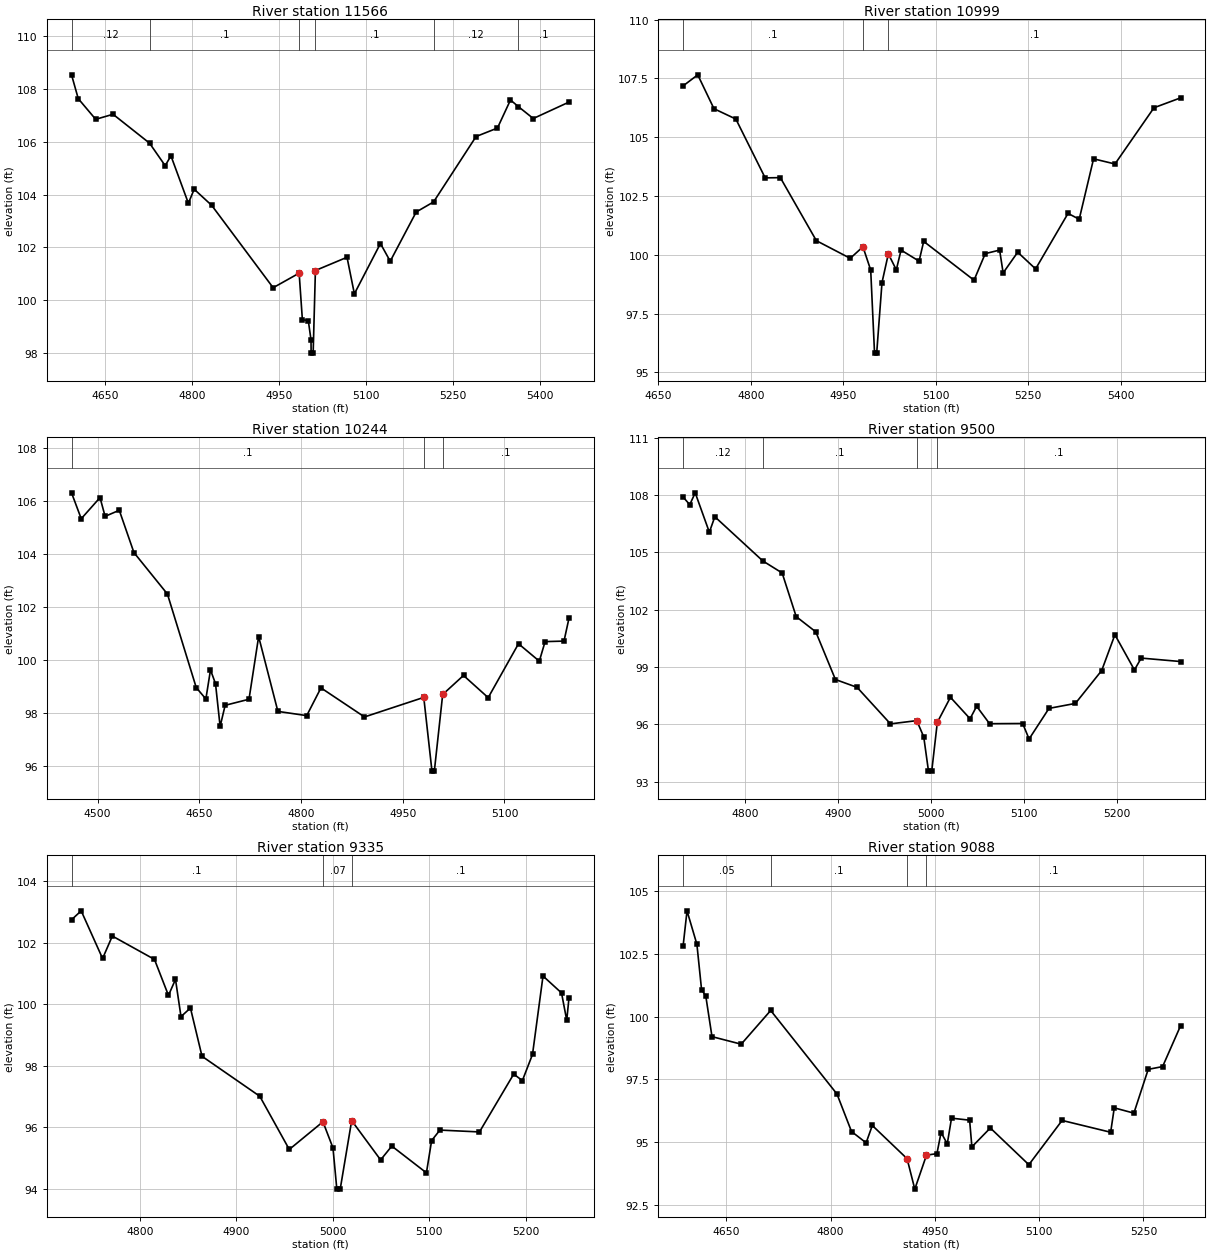
Type RM Length L Ch R = 1 ,11566   ,567,567,567
BEGIN DESCRIPTION:
Crystal Creek 053 22.0
END DESCRIPTION:
XS GIS Cut Line= 3
      3868069.48     10059934.54      3867729.23     10059922.39
      3867263.97     10060151.55
#Sta/Elev= 30
  4591.4  108.52    4603  107.62  4633.1  106.84  4663.1  107.03  4726.1  105.94
  4753.1  105.09  4763.1  105.46  4793.2  103.67  4803.2   104.2  4833.5  103.59
  4939.6  100.48  4984.5  101.03  4990.1   99.27  5000.3   99.24    5005   98.51
  5005.2   98.01  5008.7   98.01  5012.6  101.13  5067.2  101.63  5079.9  100.25
  5124.9  102.15  5141.8  101.48  5186.7  103.34  5216.7  103.72  5290.1  106.19
    5327  106.51  5349.5  107.57  5363.1  107.32  5388.9  106.87  5450.5  107.49
#Mann= 6 ,-1 , 0
  4591.4     .12       0  4726.1      .1       0  4984.5     .07       0
  5012.6      .1       0  5216.7     .12       0  5363.1      .1       0
Bank Sta=4984.5,5012.6
XS Rating Curve= 0 ,0
Exp/Cntr=0.3,0.1

Type RM Length L Ch R = 1 ,10999   ,755,755,755
BEGIN DESCRIPTION:
Crystal Creek 053 21.0
END DESCRIPTION:
XS GIS Cut Line= 3
      3867770.86     10059608.14      3867411.52     10059519.61
      3867239.65     10059920.66
#Sta/Elev= 30
  4690.3  107.18    4714  107.65  4740.3  106.21  4775.8  105.77  4823.3  103.27
  4847.9  103.28  4906.3   100.6  4961.2   99.85  4981.8  100.34  4994.4   99.35
  5000.6   95.82  5004.1   95.82  5012.7   98.82    5023  100.04  5035.9   99.36
  5043.6   100.2  5072.8   99.73  5080.3  100.57  5161.9   98.92  5180.1  100.05
  5203.4   100.2  5209.1   99.23  5232.7  100.11  5261.7    99.4  5314.3  101.76
  5332.4  101.51  5355.7  104.08  5390.4  103.86  5453.6  106.25  5496.7  106.67
#Mann= 3 , 0 , 0
  4690.3      .1       0  4981.8     .07       0    5023      .1       0
Bank Sta=4981.8,5023
XS Rating Curve= 0 ,0
Exp/Cntr=0.3,0.1

Type RM Length L Ch R = 1 ,10244   ,744,744,744
BEGIN DESCRIPTION:
Crystal Creek 053 19.0
END DESCRIPTION:
XS GIS Cut Line= 3
      3867716.99     10059381.68      3867392.75     10059023.58
      3867168.77     10058911.59
#Sta/Elev= 30
  4461.6  106.32  4475.9  105.34  4503.6  106.14  4511.1  105.43    4532  105.66
  4553.6  104.06    4603  102.49  4645.5   98.95  4659.7   98.52  4666.5   99.62
  4673.9    99.1  4680.7   97.48  4688.1   98.28  4723.3   98.51  4737.5  100.88
  4765.9   98.05  4808.4   97.89  4829.4   98.94  4893.6   97.84    4981   98.58
  4993.1   95.79  4996.6   95.79  5008.9   98.69  5039.6   99.41    5076   98.57
  5120.7  100.61  5151.4   99.95  5159.9  100.69  5187.8  100.71  5195.1  101.57
#Mann= 3 , 0 , 0
  4461.6      .1       0    4981     .07       0  5008.9      .1       0
Bank Sta=4981,5008.9
XS Rating Curve= 0 ,0
Exp/Cntr=0.3,0.1

Type RM Length L Ch R = 1 ,9500    ,165,165,165
BEGIN DESCRIPTION:
Crystal Creek 053 18.0
END DESCRIPTION:
XS GIS Cut Line= 3
      3868059.48     10059267.75      3867913.69     10059044.55
      3867717.82     10058861.04
#Sta/Elev= 30
  4733.4  107.89  4740.5  107.49  4746.4  108.11  4761.6  106.05  4767.5  106.86
  4819.1  104.55  4839.9  103.92    4855  101.64  4876.1  100.84  4897.2   98.35
  4920.5   97.94  4956.4   96.03  4984.7    96.2  4992.2   95.35  4997.3   93.56
  5000.8   93.56  5006.8   96.11  5020.9   97.42    5042    96.3  5049.1   96.95
    5063   96.04  5098.6   96.05  5105.5   95.24  5126.9   96.84  5155.3    97.1
  5183.6   98.82  5197.8  100.69  5218.8   98.85  5226.1   99.47  5268.4   99.29
#Mann= 4 ,-1 , 0
  4733.4     .12       0  4819.1      .1       0  4984.7     .07       0
  5006.8      .1       0
Bank Sta=4984.7,5006.8
XS Rating Curve= 0 ,0
Exp/Cntr=0.3,0.1

Type RM Length L Ch R = 1 ,9335    ,247,247,247
BEGIN DESCRIPTION:
Mapping XS e22fd0c4
END DESCRIPTION:
XS GIS Cut Line= 3
      3868276.14     10059108.39       3867984.5     10058949.55
       3867812.7     10058884.47
#Sta/Elev= 30
  4729.1  102.74  4739.1  103.03  4761.3  101.48  4771.4  102.21  4815.1  101.45
  4829.6  100.28  4836.9   100.8  4842.6   99.59  4852.4   99.87  4864.4    98.3
  4924.3      97  4954.9   95.27  4989.8   96.17  5000.2   95.32  5004.2   93.98
  5007.7   93.98  5019.6  96.208  5049.6   94.93  5061.2   95.38  5097.1   94.51
  5102.5   95.56  5111.1    95.9  5152.1   95.84  5187.6   97.72  5196.6   97.51
  5207.1   98.36    5218  100.91  5237.2  100.36  5242.6   99.47  5244.9  100.19
#Mann= 3 , 0 , 0
  4729.1      .1       0  4989.8     .07       0  5019.6      .1       0
Bank Sta=4989.8,5019.6
XS Rating Curve= 0 ,0
Exp/Cntr=0.3,0.1

Type RM Length L Ch R = 1 ,9088    ,503,503,503
BEGIN DESCRIPTION:
Crystal Creek 053 17.0
END DESCRIPTION:
XS GIS Cut Line= 3
      3868278.14     10058424.66      3868046.75     10058765.42
       3867752.8     10058840.16
#Sta/Elev= 30
  4588.1  102.81  4593.7   104.2  4607.9  102.87  4614.6  101.07  4620.7  100.81
  4629.6    99.2  4671.6    98.9    4714  100.24  4809.3   96.92  4830.2   95.43
  4851.2   94.98  4860.1   95.67  4910.1   94.35  4921.2   93.14    4938   94.49
    4953   94.55    4959   95.39  4967.9   94.94    4974   95.96    5000   95.88
  5003.3   94.82  5029.8   95.57  5085.2   94.11    5133   95.87  5202.8    95.4
    5208   96.37  5236.2   96.16  5256.8    97.9  5277.5   98.01  5303.3   99.63
#Mann= 4 ,-1 , 0
  4588.1     .05       0    4714      .1       0  4910.1     .03       0
    4938      .1       0
Bank Sta=4910.1,4938
XS Rating Curve= 0 ,0
Exp/Cntr=0.3,0.1

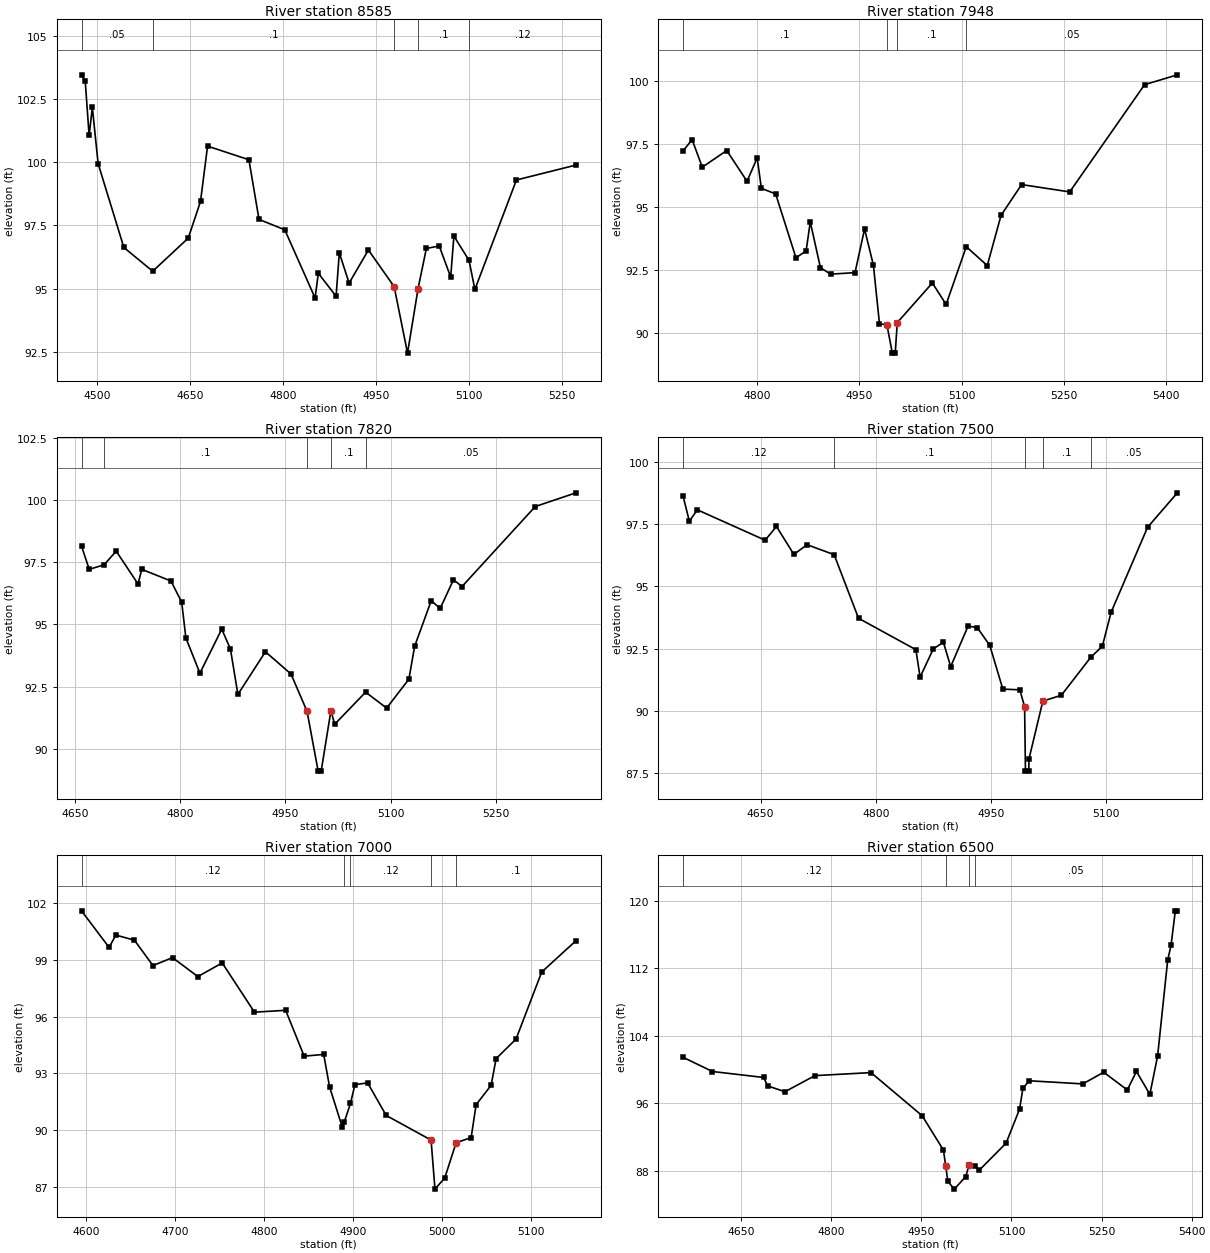
Type RM Length L Ch R = 1 ,8585    ,637,637,637
BEGIN DESCRIPTION:
Crystal Creek 053 16.0
END DESCRIPTION:
XS GIS Cut Line= 3
      3868133.67     10058432.42      3867629.07     10058575.66
      3867365.43     10058650.52
#Sta/Elev= 30
  4474.6  103.46  4480.6  103.21  4486.9  101.06  4492.1  102.17  4501.4   99.95
    4543   96.63  4589.6   95.69    4647      97  4666.8   98.45  4678.2  100.64
    4745   100.1  4761.3   97.74  4802.9   97.33  4851.9   94.63  4857.1   95.61
  4885.8    94.7    4891   96.42  4906.8   95.22    4938   96.53  4979.6   95.08
  5001.2   92.45 5018.24  95.006  5031.6   96.59  5052.4   96.69  5070.9   95.46
  5076.1   97.08  5100.5   96.12    5110   94.97  5177.1    99.3  5273.2   99.89
#Mann= 5 ,-1 , 0
  4474.6     .05       0  4589.6      .1       0  4979.6     .07       0
 5018.24      .1       0  5100.5     .12       0
Bank Sta=4979.6,5018.24
XS Rating Curve= 0 ,0
Exp/Cntr=0.3,0.1

Type RM Length L Ch R = 1 ,7948    ,128,128,128
BEGIN DESCRIPTION:
Crystal Creek 053 15.0
END DESCRIPTION:
XS GIS Cut Line= 3
      3867467.85     10058111.08      3867204.31     10058291.37
      3866801.02     10058341.51
#Sta/Elev= 30
  4691.1   97.23  4704.6   97.68  4719.5   96.59  4755.4   97.25  4785.2   96.03
  4800.1   96.96  4806.2   95.75  4827.2   95.53    4857      93  4871.9   93.27
    4878   94.42  4892.9   92.61  4907.8   92.35  4943.7   92.41  4957.7   94.14
  4970.7    92.7  4979.6   90.38 4990.51  90.347  4998.4   89.22  5002.7   89.22
  5005.7   90.43  5057.2      92  5077.4   91.15    5107   93.44  5137.8   92.69
    5158   94.68  5188.2    95.9  5258.8   95.61  5368.7   99.86  5416.8  100.25
#Mann= 4 ,-1 , 0
  4691.1      .1       0 4990.51     .07       0  5005.7      .1       0
    5107     .05       0
Bank Sta=4990.51,5005.7
XS Rating Curve= 0 ,0
Exp/Cntr=0.3,0.1

Type RM Length L Ch R = 1 ,7820    ,320,320,320
BEGIN DESCRIPTION:
Mapping XS 0591a54d
END DESCRIPTION:
XS GIS Cut Line= 2
      3867508.23     10058049.41      3866843.14     10058280.51
#Sta/Elev= 30
  4659.7   98.14  4670.7   97.21  4691.8   97.39  4709.1   97.94  4740.2   96.62
  4745.5   97.21  4787.1   96.74  4802.4   95.89  4808.3   94.46  4828.3   93.04
  4859.4   94.81  4871.8   94.01  4882.4   92.19  4921.6    93.9    4958   93.01
 4980.86  91.513  4996.7   89.11    5001   89.11  5014.9   91.54  5020.2   90.99
  5064.3   92.28  5094.2   91.64  5125.9    92.8  5134.1   94.12  5157.7   95.95
  5170.5   95.64  5189.4   96.79  5201.6   96.52  5305.9   99.73  5363.8  100.28
#Mann= 5 ,-1 , 0
  4659.7     .12       0  4691.8      .1       0 4980.86     .07       0
  5014.9      .1       0  5064.3     .05       0
Bank Sta=4980.86,5014.9
XS Rating Curve= 0 ,0
Exp/Cntr=0.3,0.1

Type RM Length L Ch R = 1 ,7500    ,500,500,500
BEGIN DESCRIPTION:
Crystal Creek 053 14.0
END DESCRIPTION:
XS GIS Cut Line= 3
      3867654.72      10058077.6      3867246.99      10057883.9
      3867067.83     10057811.06
#Sta/Elev= 30
  4548.6   98.64    4557   97.61  4567.3   98.07  4655.8   96.85  4670.6    97.4
  4693.3   96.28  4710.5   96.67  4745.8   96.27  4777.6   93.72  4852.4   92.46
  4857.9   91.36  4875.1   92.49  4888.3   92.76  4897.8   91.78  4920.5   93.41
  4932.6   93.34  4948.8   92.63  4965.8   90.88    4988   90.85  4994.2   90.17
  4995.3   87.59  4999.6   87.59    5000   88.09    5018    90.4  5042.1   90.63
  5080.6   92.16  5095.6    92.6    5107   93.96  5154.6   97.37  5193.4   98.75
#Mann= 5 ,-1 , 0
  4548.6     .12       0  4745.8      .1       0  4994.2     .07       0
    5018      .1       0  5080.6     .05       0
Bank Sta=4994.2,5018
XS Rating Curve= 0 ,0
Exp/Cntr=0.3,0.1

Type RM Length L Ch R = 1 ,7000    ,500,500,500
BEGIN DESCRIPTION:
Crystal Creek 053 13.0
END DESCRIPTION:
XS GIS Cut Line= 3
      3867662.14     10057740.61      3867398.88     10057432.45
      3867263.31     10057365.95
#Sta/Elev= 30
  4594.7  101.58  4625.7   99.65  4633.4   100.3  4654.2  100.03  4675.1   98.69
  4697.1   99.11  4725.6   98.11    4753   98.83  4789.3   96.23  4824.4   96.33
  4845.2   93.91  4867.2      94  4873.8   92.29  4888.1   90.16  4890.4   90.44
  4897.3   91.41  4902.3    92.4  4916.6    92.5  4937.5   90.78    4988   89.48
  4992.4   86.89  5003.4   87.48  5016.2   89.34  5033.1   89.61  5038.7   91.35
  5055.6   92.37  5061.2   93.78  5083.6   94.81  5112.5   98.35    5151     100
#Mann= 5 ,-1 , 0
  4594.7     .12       0  4890.4      .1       0  4897.3     .12       0
    4988     .07       0  5016.2      .1       0
Bank Sta=4988,5016.2
XS Rating Curve= 0 ,0
Exp/Cntr=0.3,0.1

Type RM Length L Ch R = 1 ,6500    ,500,500,500
BEGIN DESCRIPTION:
Crystal Creek 053 12.0
END DESCRIPTION:
XS GIS Cut Line= 3
      3867985.31     10057501.86      3867713.85     10057146.86
      3867376.81     10056979.74
#Sta/Elev= 30
  4553.1  101.46  4602.3   99.77  4687.6   99.06  4693.9   98.07  4722.9   97.37
  4772.8   99.28  4866.2   99.64  4951.4   94.52  4986.8   90.44 4990.49  88.585
  4994.2   86.72  5004.9   85.81  5023.9    87.3  5029.4   88.64  5038.7   88.55
  5046.3   88.05  5091.1   91.27  5113.5    95.3  5119.1   97.77  5129.5   98.67
  5218.8    98.3  5253.6   99.68  5292.9   97.58  5308.1   99.78  5330.4   97.06
  5343.3  101.59  5360.1  112.98  5365.7  114.74  5372.8  118.84  5376.2  118.84
#Mann= 4 ,-1 , 0
  4553.1     .12       0 4990.49     .03       0  5029.4     .12       0
  5038.7     .05       0
Bank Sta=4990.49,5029.4
XS Rating Curve= 0 ,0
Exp/Cntr=0.3,0.1

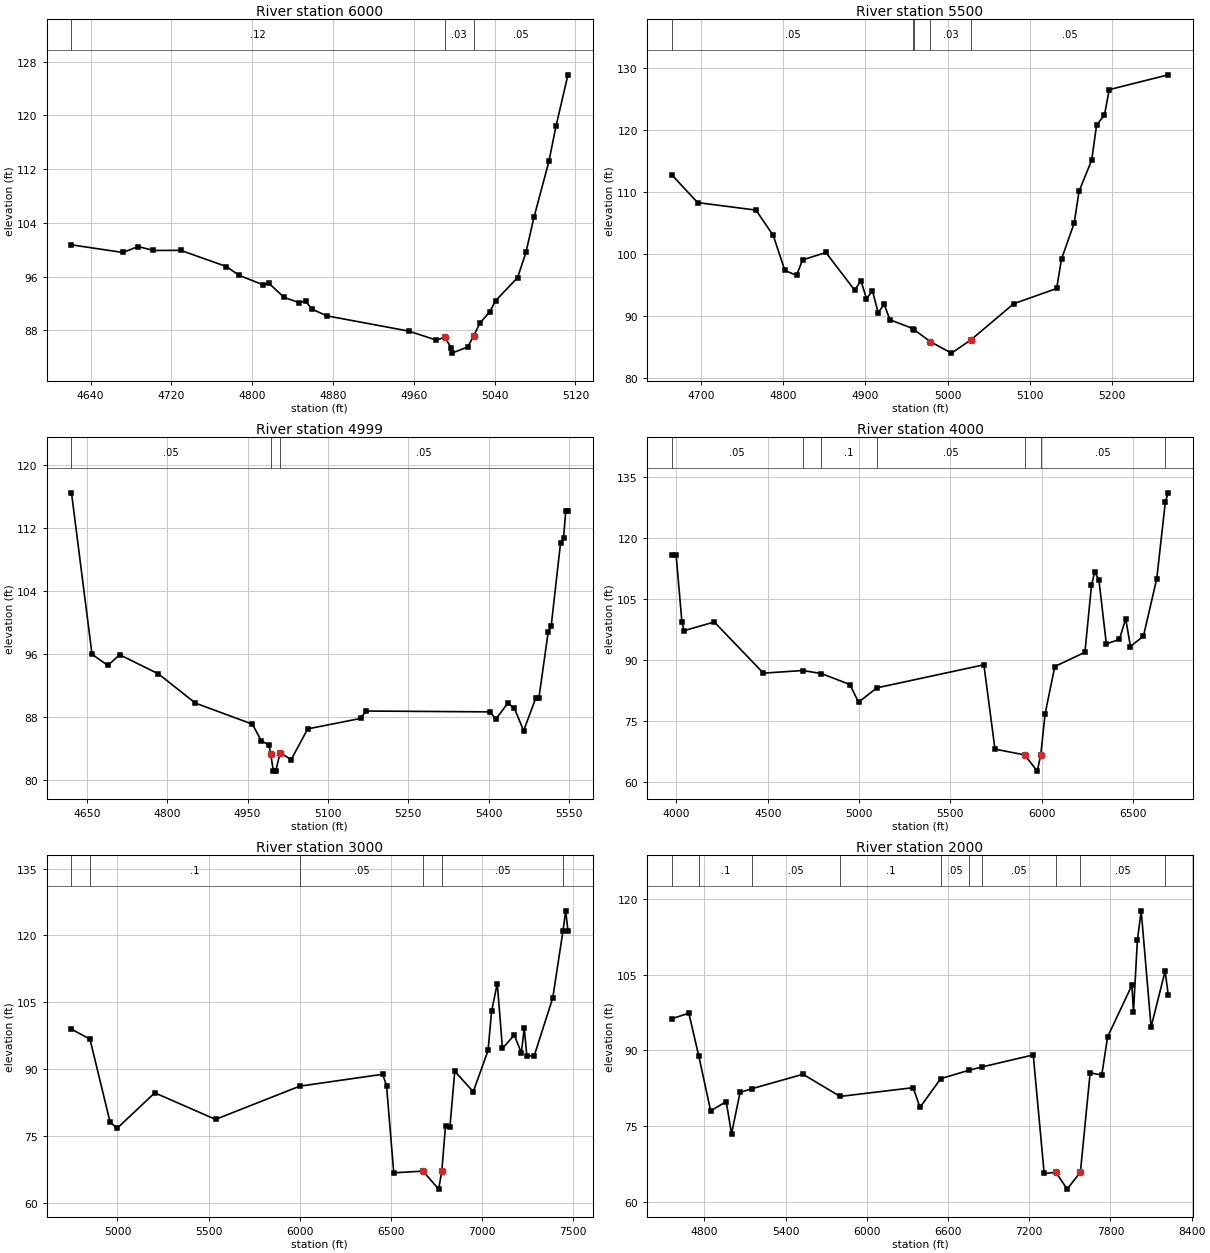
Type RM Length L Ch R = 1 ,6000    ,500,500,500
BEGIN DESCRIPTION:
Crystal Creek 053 11.0
END DESCRIPTION:
XS GIS Cut Line= 3
       3868216.7      10057003.2      3867900.19      10056794.9
      3867801.38     10056740.92
#Sta/Elev= 30
  4621.1  100.74    4672    99.6  4687.1  100.49  4702.2    99.9  4729.2   99.92
  4774.5   97.51  4787.3   96.18  4810.6   94.81  4816.6   95.01  4831.7   92.91
  4846.8   92.13  4852.8   92.39  4859.1   91.18  4873.8   90.18  4954.9   87.91
  4982.3   86.57  4990.8   86.99  4997.3   85.34  4997.8   84.63  5013.4   85.55
  5019.1   87.16  5025.5    89.1  5035.2   90.78  5040.9   92.41  5062.7   95.86
    5071    99.6  5078.9  104.81  5093.8  113.17  5100.7  118.35  5112.6  126.03
#Mann= 3 , 0 , 0
  4621.1     .12       0  4990.8     .03       0  5019.1     .05       0
Bank Sta=4990.8,5019.1
XS Rating Curve= 0 ,0
Exp/Cntr=0.3,0.1

Type RM Length L Ch R = 1 ,5500    ,501,501,501
BEGIN DESCRIPTION:
Crystal Creek 053 10.0
END DESCRIPTION:
XS GIS Cut Line= 3
      3868152.83     10056211.55       3867924.4     10056456.86
      3867784.36     10056685.48
#Sta/Elev= 30
  4664.8  112.77  4696.2  108.28  4767.1  107.07  4788.1  102.98  4802.2   97.34
  4816.4   96.53  4823.7   99.03  4852.1  100.23  4887.2   94.12  4894.6   95.71
  4901.4    92.8  4908.7   94.02  4915.6   90.51  4922.9   91.89  4929.8   89.38
  4958.5   87.92  4959.6   87.75  4979.1   85.83  5004.7   83.99  5028.4   86.14
  5080.4   91.97  5132.5   94.42  5138.4   99.17  5153.8  104.98  5159.7   110.1
  5175.1  115.15    5181  120.78  5190.6  122.42  5196.4  126.51  5268.1   128.9
#Mann= 5 ,-1 , 0
  4664.8     .05       0  4958.5     .12       0  4959.6     .05       0
  4979.1     .03       0  5028.4     .05       0
Bank Sta=4979.1,5028.4
XS Rating Curve= 0 ,0
Exp/Cntr=0.3,0.1

Type RM Length L Ch R = 1 ,4999    ,999,999,999
BEGIN DESCRIPTION:
Crystal Creek 053 9.0
END DESCRIPTION:
XS GIS Cut Line= 3
        3868145.     10056173.74      3867690.62     10056057.87
       3867499.2     10056473.26
#Sta/Elev= 30
  4621.5  116.52  4659.8      96  4689.3   94.58  4711.4   95.94  4783.7   93.51
  4852.8   89.79  4959.1   87.12  4975.4   85.03  4990.1   84.44 4993.09  83.357
  4998.2   81.15  5002.5   81.15  5010.7   83.47  5031.4   82.62  5062.3   86.52
  5161.1   87.85    5171   88.79  5402.2   88.68  5413.3   87.76  5435.3   89.76
  5447.6    89.2  5465.1   86.28  5488.1   90.49  5493.6   90.45    5511   98.88
  5516.5   99.59    5534  110.15  5539.5  110.76  5543.8  114.27  5547.8  114.27
#Mann= 3 , 0 , 0
  4621.5     .05       0 4993.09     .07       0  5010.7     .05       0
Bank Sta=4993.09,5010.7
XS Rating Curve= 0 ,0
Exp/Cntr=0.3,0.1

Type RM Length L Ch R = 1 ,4000    ,1000,1000,1000
BEGIN DESCRIPTION:
Crystal Creek 053 8.0
END DESCRIPTION:
XS GIS Cut Line= 5
      3868205.38     10056143.16      3868080.94     10055814.59
      3867439.93     10055605.17      3867226.21      10055609.3
      3866961.02     10057064.57
#Sta/Elev= 30
  3974.3  115.91  3997.9  115.86    4030   99.24    4042   97.21  4206.9   99.34
  4476.2   86.77  4691.2   87.42  4793.7   86.67  4949.6   83.98    4997   79.63
  5097.5   83.16  5683.5   88.82  5744.1   68.11  5906.9   66.68  5975.7    62.7
 5995.02  66.757  6018.6   76.74  6071.8    88.4  6236.8   91.91  6272.7  108.34
  6290.1  111.63  6313.3  109.69    6354   93.97  6425.2   95.04  6460.2  100.11
  6486.1   93.31  6557.3   95.88  6630.3  110.02  6677.3  128.89    6693  131.07
#Mann= 7 ,-1 , 0
  3974.3     .05       0  4691.2     .12       0  4793.7      .1       0
  5097.5     .05       0  5906.9     .03       0 5995.02     .05       0
  6677.3     .12       0
Bank Sta=5906.9,5995.02
XS Rating Curve= 0 ,0
Exp/Cntr=0.3,0.1

Type RM Length L Ch R = 1 ,3000    ,1000,1000,1000
BEGIN DESCRIPTION:
Crystal Creek 053 6.0
END DESCRIPTION:
XS GIS Cut Line= 5
      3868117.88     10055261.08      3867878.24     10055181.87
      3867510.54     10055099.47      3867176.58     10055605.27
      3866921.96     10057073.23
#Sta/Elev= 30
  4747.6   98.92  4848.9    96.7  4959.1   78.11  4997.6   76.65  5204.8   84.63
  5538.2   78.67  6000.7   86.13  6455.7    88.8  6476.9   86.27  6516.6   66.67
  6676.8  67.056  6763.1   63.01  6780.5   67.12  6800.8   77.27    6825   77.01
  6851.5   89.47    6953   84.88  7034.2   94.14  7053.7  102.97  7084.9  109.18
  7113.4   94.59  7178.2   97.62  7216.9    93.6  7232.8   99.17  7247.3   92.89
  7287.4   92.93  7389.4  105.94  7445.7  121.02  7460.5   125.5  7472.8  121.02
#Mann= 6 ,-1 , 0
  4747.6     .12       0  4848.9      .1       0  6000.7     .05       0
  6676.8     .03       0  6780.5     .05       0  7445.7     .12       0
Bank Sta=6676.8,6780.5
XS Rating Curve= 0 ,0
Exp/Cntr=0.3,0.1

Type RM Length L Ch R = 1 ,2000    ,855,855,855
BEGIN DESCRIPTION:
Crystal Creek 053 4.0
END DESCRIPTION:
XS GIS Cut Line= 5
      3868622.85     10054891.46      3868250.18     10054654.92
      3867795.54     10054576.51      3867077.76     10055548.29
       3866831.7     10057086.15
#Sta/Elev= 30
  4558.6   96.27  4684.7   97.37  4758.2   88.89  4845.7   78.07  4960.9    79.9
    5000   73.52  5063.2   81.72    5150   82.44  5528.1    85.3  5802.3   80.92
  6342.3   82.65  6392.4   78.76  6545.9   84.43  6755.3    86.1  6854.3   86.77
  7229.3   89.12  7310.3   65.69  7396.6   65.92  7480.2    62.6 7578.02  65.976
  7649.8   85.59  7735.6   85.14  7778.9   92.69  7958.4   102.9    7970   97.66
    7999  111.78    8027   117.6  8100.2   94.64  8203.8  105.68  8226.9  101.01
#Mann= 10 ,-1 , 0
  4558.6     .12       0  4758.2      .1       0    5150     .05       0
  5802.3      .1       0  6545.9     .05       0  6755.3     .12       0
  6854.3     .05       0  7396.6     .03       0 7578.02     .05       0
  8203.8     .12       0
Bank Sta=7396.6,7578.02
XS Rating Curve= 0 ,0
Exp/Cntr=0.3,0.1

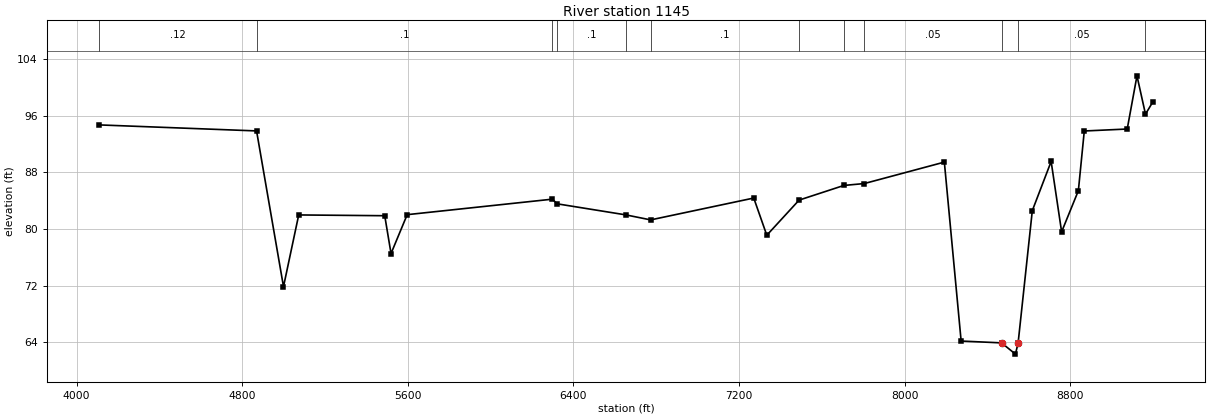
Type RM Length L Ch R = 1 ,1145    ,0,0,0
BEGIN DESCRIPTION:
Crystal Creek 053 2.0
END DESCRIPTION:
XS GIS Cut Line= 5
      3869041.33     10055317.13      3868726.99     10054193.52
      3867893.62     10054331.25      3867021.05     10055527.21
      3866784.33      10057106.4
#Sta/Elev= 30
  4110.2   94.71  4869.7   93.86  4999.8   71.84  5073.3   81.98  5488.9   81.87
  5519.3   76.52  5597.3   82.02  6298.5   84.21  6322.2   83.55  6653.2   81.99
  6773.5   81.28  7271.5   84.37  7334.5   79.11  7490.6   84.08  7706.8   86.15
  7805.7   86.42  8192.2   89.45  8273.3   64.15  8468.7   63.89  8535.6    62.3
 8548.54  63.873  8617.1   82.59  8708.1   89.54  8758.7   79.59  8839.6   85.41
  8868.2   93.85  9075.6   94.13  9122.7  101.65  9163.8   96.23  9198.9   97.94
#Mann= 12 ,-1 , 0
  4110.2     .12       0  4869.7      .1       0  6298.5     .05       0
  6322.2      .1       0  6653.2     .05       0  6773.5      .1       0
  7490.6     .05       0  7706.8     .12       0  7805.7     .05       0
  8468.7     .03       0 8548.54     .05       0  9163.8     .12       0
Bank Sta=8468.7,8548.54
XS Rating Curve= 0 ,0
Exp/Cntr=0.3,0.1