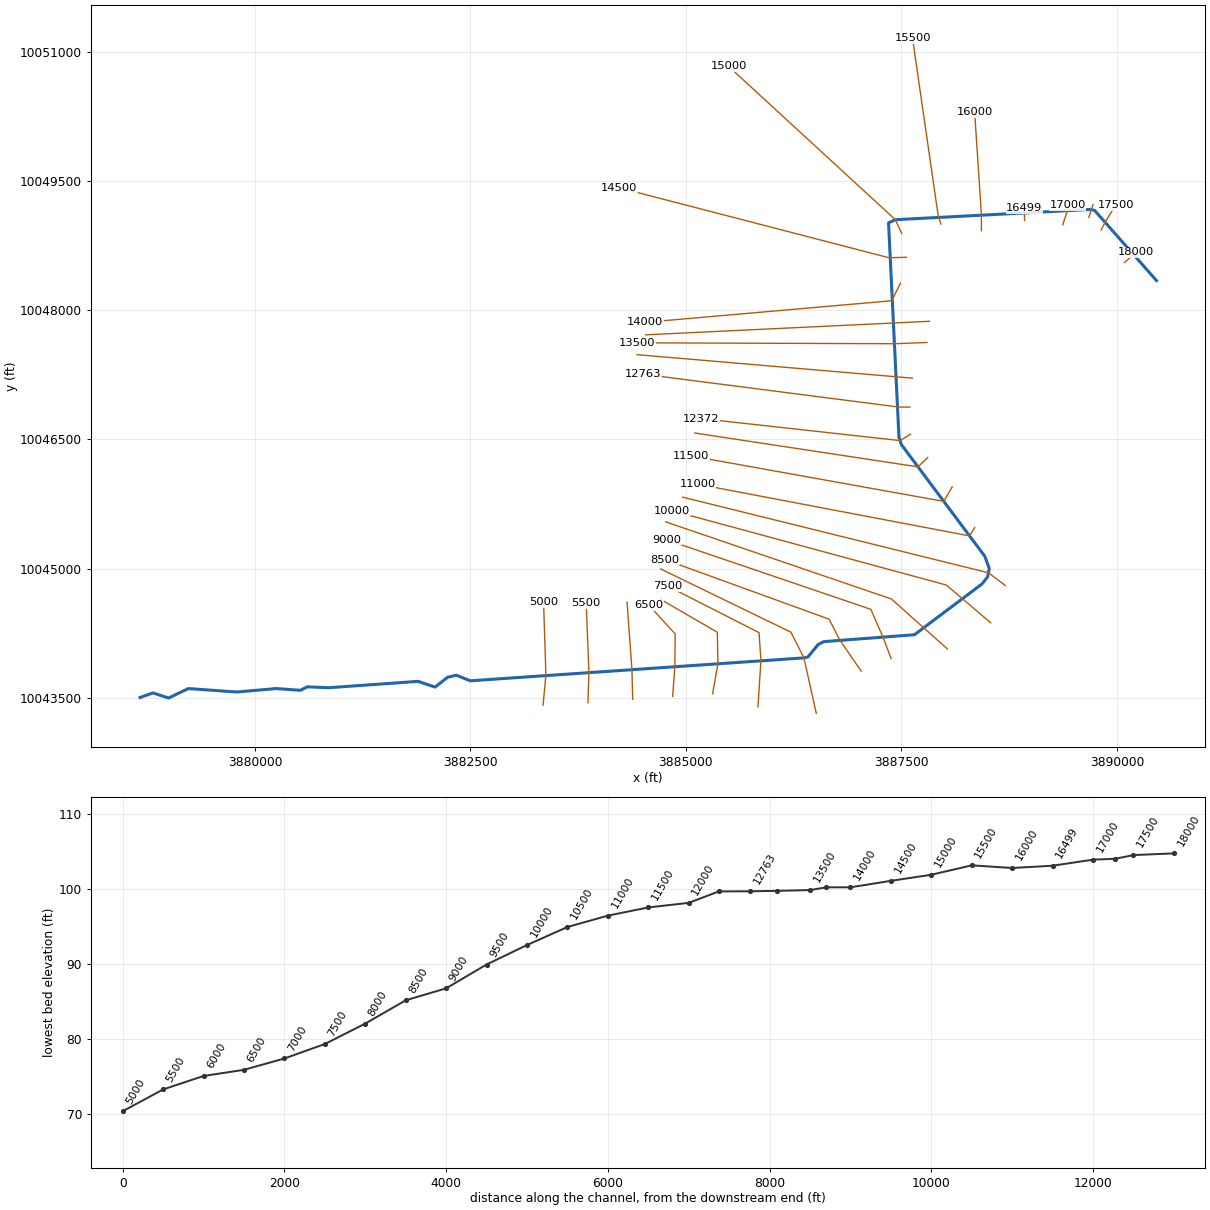
--- Crystal Creek 054.prj (project) ---

Proj Title=Crystal Creek 054 Base Level Engineering
Current Plan=p01
Default Exp/Contr=0.3,0.1
English Units
Geom File=g01
Flow File=f01
Plan File=p01
Y Axis Title=Elevation
X Axis Title(PF)=Main Channel Distance
X Axis Title(XS)=Station
BEGIN DESCRIPTION:
Crystal Creek 054
END DESCRIPTION:
DSS Export Rating Curves= 0
DSS Export Rating Curve Sorted= 0
DSS Export Volume Flow Curves= 0
DXF OffsetX= 0
DXF OffsetY= 0
DXF ScaleX= 1
DXF ScaleY= 10

--- Crystal Creek 054.p01 (plan) ---

Plan Title=Multiple Run
Short Identifier=Multiple
Geom File=g01
Flow File=f01
Subcritical Flow
K Sum by GR= 0
Std Step Tol= 0.01
Critical Tol= 0.01
Num of Std Step Trials= 20
Max Error Tol= 0.3
Flow Tol Ratio= 0.001
Split Flow NTrial= 30
Split Flow Tol= 0.02
Split Flow Ratio= 0.02
Log Output Level= 0
Friction Slope Method= 1
Unsteady Friction Slope Method= 2
Unsteady Bridges Friction Slope Method= 1
Parabolic Critical Depth
Global Vel Dist=  1 , 1 , 1
Global Log Level= 0
CheckData=True
Encroach Param= -1, 0, 0, 0
BEGIN DESCRIPTION:
Multiple Run
END DESCRIPTION:

--- Crystal Creek 054.f01 (steady flow) ---

Flow Title=Multiple
Program Version=4.10
Number of Profiles= 7
Profile Names=10-year,25-year,50-year,1pct_min,100-year,1pct_plu,500-year
River Rch & RM=Crystal Creek 05,Reach-1         ,18000
     134     157     191      77     233     704     354
River Rch & RM=Crystal Creek 05,Reach-1         ,15500
     350     428     539     223     673    2032    1082
River Rch & RM=Crystal Creek 05,Reach-1         ,12372
     761     992    1306     563    1700    5134    2977
River Rch & RM=Crystal Creek 05,Reach-1         ,2500
    1187    1609    2175     963    2909    8785    5382
Boundary for River Rch & Prof#=Crystal Creek 05,Reach-1         , 1
Up Type= 0
Dn Type= 3
Dn Slope=0.005
Boundary for River Rch & Prof#=Crystal Creek 05,Reach-1         , 2
Up Type= 0
Dn Type= 3
Dn Slope=0.005
Boundary for River Rch & Prof#=Crystal Creek 05,Reach-1         , 3
Up Type= 0
Dn Type= 3
Dn Slope=0.005
Boundary for River Rch & Prof#=Crystal Creek 05,Reach-1         , 4
Up Type= 0
Dn Type= 3
Dn Slope=0.005
Boundary for River Rch & Prof#=Crystal Creek 05,Reach-1         , 5
Up Type= 0
Dn Type= 3
Dn Slope=0.005
Boundary for River Rch & Prof#=Crystal Creek 05,Reach-1         , 6
Up Type= 0
Dn Type= 3
Dn Slope=0.005
Boundary for River Rch & Prof#=Crystal Creek 05,Reach-1         , 7
Up Type= 0
Dn Type= 3
Dn Slope=0.005
DSS Import GetInterval= 0
DSS Import GetPeak= 0
DSS Import FillOption= 0

--- Crystal Creek 054.g01 (geometry) ---

Geom Title=Existing Conditions
Program Version=4.10

River Reach=Crystal Creek 05,Reach-1
Reach XY= 30
      3890460.63     10048342.86      3889742.57     10049158.13
      3889696.04     10049169.25      3887432.15      10049050.5
       3887351.6     10049014.38      3887472.47     10046525.86
      3887499.62     10046440.53      3888469.29     10045141.17
      3888520.12      10044999.2      3888499.29     10044901.98
      3888436.79     10044822.12      3887652.06     10044231.84
      3886599.98     10044151.98      3886534.01     10044117.26
      3886416.53      10043973.6      3886366.62     10043962.75
      3882498.23     10043696.84      3882337.76     10043762.01
      3882235.76     10043738.14      3882091.45      10043624.2
      3881893.96     10043690.39      3880858.23     10043616.84
      3880608.23     10043626.84      3880528.23     10043586.84
      3880248.23     10043606.84      3879788.23     10043566.84
      3879228.23     10043606.84      3878998.23     10043496.84
      3878818.23     10043556.84        3878668.     10043502.85

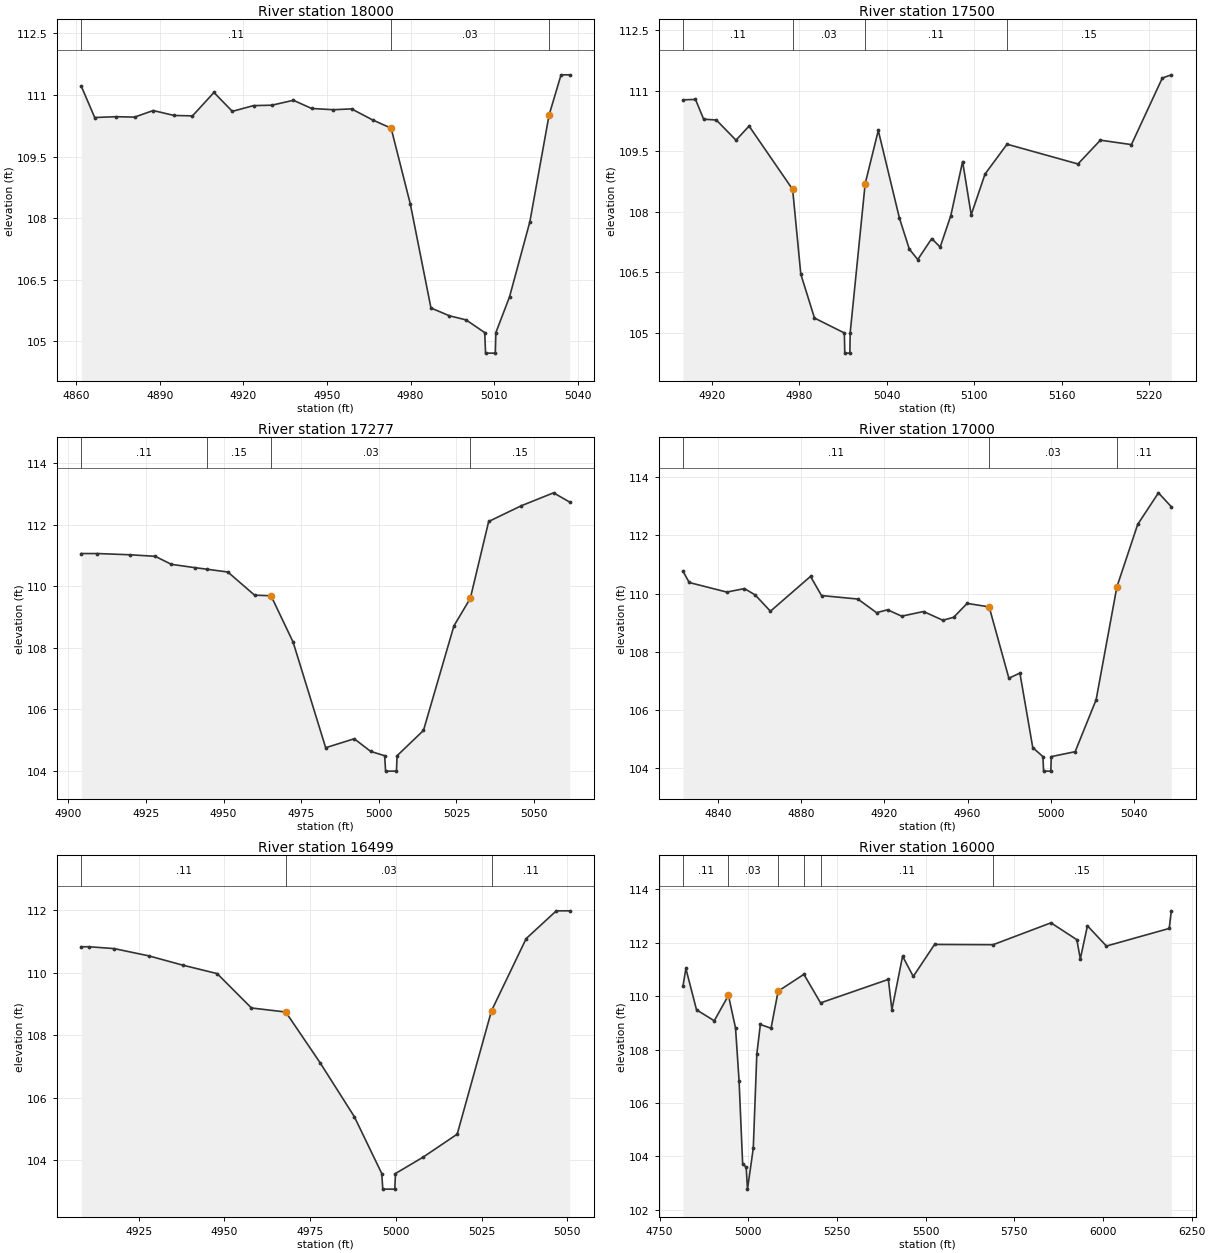
Type RM Length L Ch R = 1 ,18000   ,500,500,500
BEGIN DESCRIPTION:
Crystal Creek 054 36.0
END DESCRIPTION:
XS GIS Cut Line= 3
      3890088.29     10048553.74      3890193.08     10048643.85
      3890218.75     10048670.63
#Sta/Elev= 30
  4861.8  111.21  4866.6  110.45  4874.3  110.47  4880.9  110.46  4887.6  110.62
  4895.1   110.5  4901.7  110.49  4909.4  111.06    4916   110.6  4923.6  110.74
  4930.2  110.75  4937.9  110.87  4944.5  110.67  4952.2  110.64  4958.8  110.66
  4966.4  110.39    4973  110.19  4979.9  108.34  4987.3  105.81  4993.9  105.62
  4999.9  105.52  5006.6  105.21  5006.9  104.71  5010.4  104.71  5010.6  105.21
  5015.5  106.08  5022.8  107.91  5029.7  110.51    5034  111.49  5037.1  111.49
#Mann= 3 , 0 , 0
  4861.8     .11       0    4973     .03       0  5029.7     .11       0
Bank Sta=4973,5029.7
XS Rating Curve= 0 ,0
Exp/Cntr=0.3,0.1

Type RM Length L Ch R = 1 ,17500   ,223,223,223
BEGIN DESCRIPTION:
Crystal Creek 054 35.0
END DESCRIPTION:
XS GIS Cut Line= 3
      3889817.84     10048930.63      3889863.24     10049019.62
      3889986.99     10049219.87
#Sta/Elev= 30
  4900.1  110.77  4908.7  110.78  4914.3  110.29    4923  110.27  4936.5  109.77
  4945.5  110.12  4975.4  108.55    4981  106.45  4990.4  105.36  5010.9  104.99
  5011.2  104.49  5014.7  104.49  5014.9  104.99  5025.2  108.69  5034.2  110.01
  5048.7  107.84  5055.5  107.07  5061.3  106.81  5070.9  107.33  5076.7  107.12
    5084   107.9  5092.1  109.24    5098  107.92  5107.5  108.93  5122.6  109.67
  5171.3  109.18  5186.7  109.77    5208  109.66  5229.2  111.31  5235.4  111.39
#Mann= 4 ,-1 , 0
  4900.1     .11       0  4975.4     .03       0  5025.2     .11       0
  5122.6     .15       0
Bank Sta=4975.4,5025.2
XS Rating Curve= 0 ,0
Exp/Cntr=0.3,0.1

Type RM Length L Ch R = 1 ,17277   ,277,277,277
BEGIN DESCRIPTION:
Mapping XS b3f5bbd9
END DESCRIPTION:
XS GIS Cut Line= 2
       3889674.7     10049076.14      3889722.89     10049225.88
#Sta/Elev= 25
  4904.2  111.06  4909.4  111.06  4919.9  111.02    4928  110.97  4933.2  110.71
  4940.9   110.6  4944.8  110.55  4951.4  110.46    4960  109.71  4965.3  109.69
  4972.4  108.19  4982.9  104.76  4992.1  105.05  4997.4  104.64  5001.9   104.5
  5002.2     104  5005.7     104  5005.9   104.5  5014.4  105.32  5024.2  108.71
  5029.5  109.61  5035.4   112.1  5045.9  112.61  5056.3  113.03  5061.5  112.73
#Mann= 4 ,-1 , 0
  4904.2     .11       0  4944.8     .15       0  4965.3     .03       0
  5029.5     .15       0
Bank Sta=4965.3,5029.5
XS Rating Curve= 0 ,0
Exp/Cntr=0.3,0.1

Type RM Length L Ch R = 1 ,17000   ,501,501,501
BEGIN DESCRIPTION:
Crystal Creek 054 34.0
END DESCRIPTION:
XS GIS Cut Line= 3
      3889372.61     10048991.05      3889427.79     10049159.23
      3889429.87      10049217.3
#Sta/Elev= 30
    4823  110.77    4826  110.38  4844.1  110.05  4852.6  110.17  4857.8  109.95
  4865.1  109.39  4884.4  110.59  4889.7  109.93  4907.2  109.81  4916.2  109.34
  4921.5  109.44  4928.3  109.22  4938.8  109.38  4948.1  109.08  4953.3  109.18
  4959.8  109.66  4970.4  109.54  4979.9  107.08  4985.2  107.26  4991.4  104.69
  4996.3  104.38  4996.6  103.88  5000.1  103.88  5000.3  104.38  5011.8  104.55
  5021.9  106.34  5031.9  110.23  5041.9  112.38  5051.9  113.47  5058.1  112.99
#Mann= 3 , 0 , 0
    4823     .11       0  4970.4     .03       0  5031.9     .11       0
Bank Sta=4970.4,5031.9
XS Rating Curve= 0 ,0
Exp/Cntr=0.3,0.1

Type RM Length L Ch R = 1 ,16499   ,499,499,499
BEGIN DESCRIPTION:
Crystal Creek 054 33.0
END DESCRIPTION:
XS GIS Cut Line= 2
      3888929.91     10049041.46      3888926.49     10049183.82
#Sta/Elev= 20
  4908.3  110.83  4910.6  110.83  4917.9  110.77  4927.9  110.54  4937.9  110.24
  4947.9  109.97  4957.9  108.87  4967.9  108.74  4977.9  107.12  4987.9  105.39
  4995.9  103.57  4996.2  103.07  4999.7  103.07  4999.9  103.57  5007.9  104.09
  5017.9  104.83  5027.9  108.78    5038  111.09  5046.8  111.98  5050.7  111.98
#Mann= 3 , 0 , 0
  4908.3     .11       0  4967.9     .03       0  5027.9     .11       0
Bank Sta=4967.9,5027.9
XS Rating Curve= 0 ,0
Exp/Cntr=0.3,0.1

Type RM Length L Ch R = 1 ,16000   ,500,500,500
BEGIN DESCRIPTION:
Crystal Creek 054 32.0
END DESCRIPTION:
XS GIS Cut Line= 3
      3888428.96     10048922.91      3888429.15     10049107.11
      3888350.69     10050297.03
#Sta/Elev= 30
  4815.8  110.37    4824  111.04    4854  109.49    4904  109.08    4944  110.03
    4964  108.81    4974  106.82    4984  103.73    4994  103.59  4997.7  102.77
    5014   104.3    5024  107.83    5034  108.94  5064.1   108.8  5084.1  110.19
  5156.7  110.82  5203.7  109.75  5394.8  110.63  5404.8  109.49  5434.9   111.5
    5465  110.74  5525.1  111.94  5690.1  111.93  5853.2  112.75    5926  112.12
    5936   111.4    5956  112.64  6009.4  111.88  6186.5  112.54  6192.5   113.2
#Mann= 6 ,-1 , 0
  4815.8     .11       0    4944     .03       0  5084.1     .11       0
  5156.7     .15       0  5203.7     .11       0  5690.1     .15       0
Bank Sta=4944,5084.1
XS Rating Curve= 0 ,0
Exp/Cntr=0.3,0.1

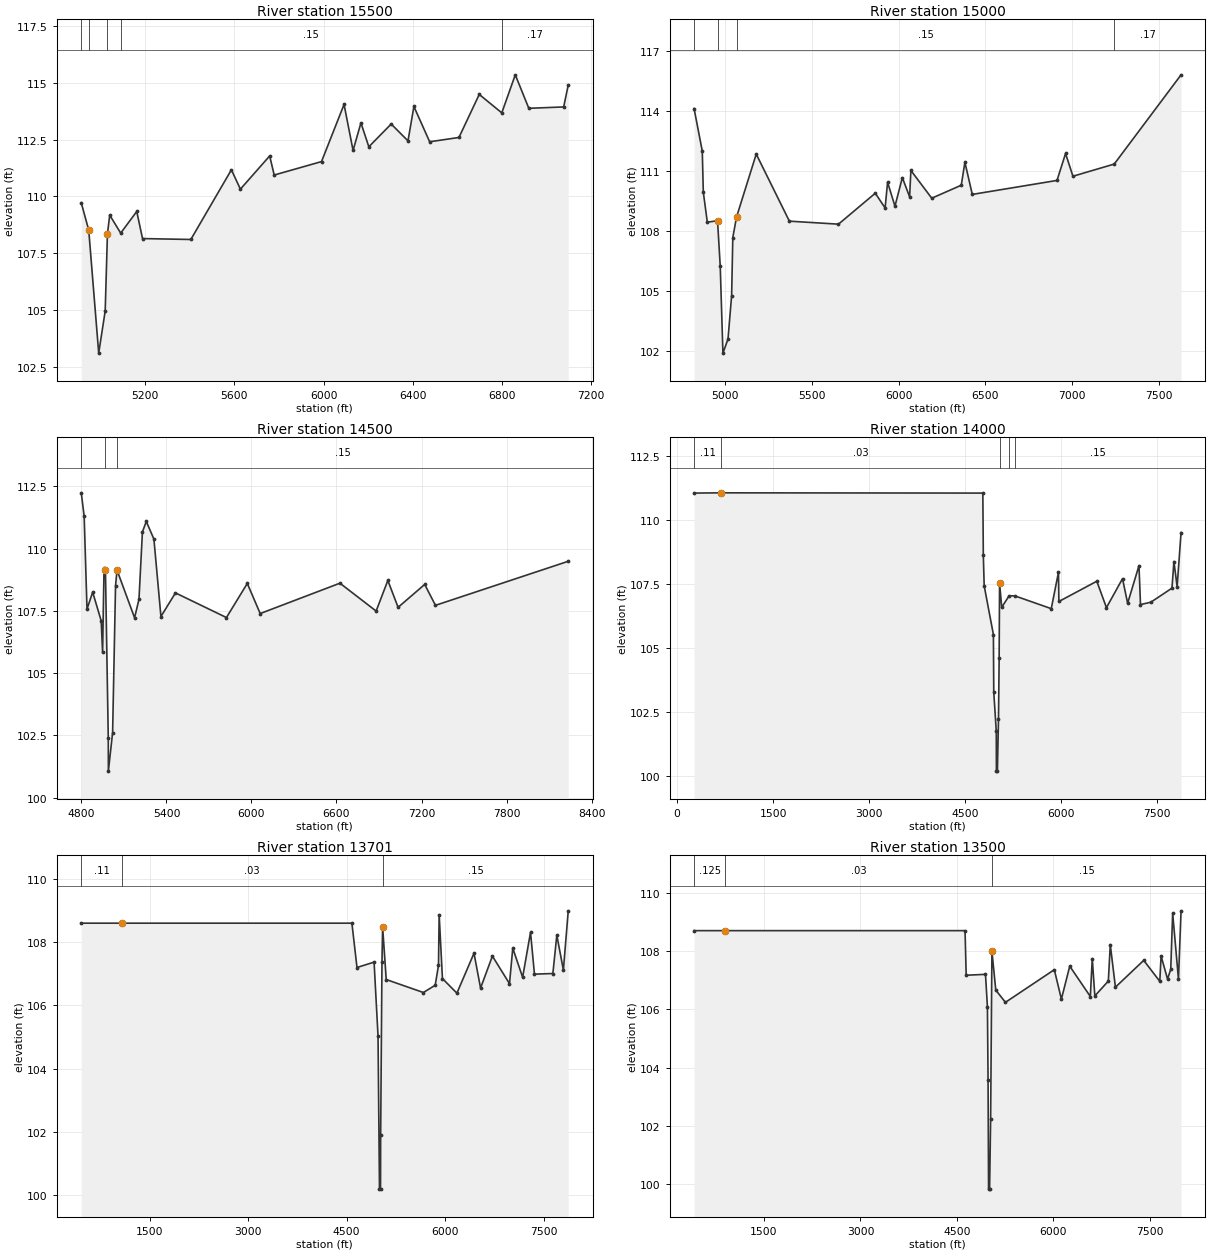
Type RM Length L Ch R = 1 ,15500   ,500,500,500
BEGIN DESCRIPTION:
Crystal Creek 054 31.0
END DESCRIPTION:
XS GIS Cut Line= 3
      3887961.15     10048999.81      3887929.88     10049080.24
      3887629.89     10051156.08
#Sta/Elev= 30
  4913.7  109.72  4947.2  108.52  4991.9  103.12    5021  104.97  5031.1  108.36
  5041.3  109.18  5090.5  108.39  5162.5  109.34  5188.4  108.15    5405  108.11
  5586.9  111.17  5627.3  110.32  5758.6  111.78  5778.8  110.94    5991  111.53
  6092.1  114.04  6132.5  112.02  6167.8  113.23  6203.2  112.18  6303.4  113.18
  6378.8  112.44  6405.3  113.95    6476   112.4  6607.4  112.59  6698.3  114.48
  6799.4  113.67  6859.9  115.34  6920.6  113.87  7076.9  113.93  7097.4  114.89
#Mann= 5 ,-1 , 0
  4913.7     .11       0  4947.2     .03       0  5031.1     .11       0
  5090.5     .15       0  6799.4     .17       0
Bank Sta=4947.2,5031.1
XS Rating Curve= 0 ,0
Exp/Cntr=0.3,0.1

Type RM Length L Ch R = 1 ,15000   ,500,500,500
BEGIN DESCRIPTION:
Crystal Creek 054 30.0
END DESCRIPTION:
XS GIS Cut Line= 3
      3887505.35     10048888.24      3887430.78      10049050.3
      3885496.31     10050830.02
#Sta/Elev= 30
  4821.6  114.12  4868.8  111.99  4874.8  109.93  4897.8  108.43  4956.8   108.5
  4972.2  106.24  4987.9  101.87    5017  102.57    5038  104.75  5044.8  107.66
  5066.4  108.69  5179.8  111.84  5370.9  108.48  5653.9  108.33    5866  109.88
  5922.7  109.14  5936.9  110.43  5979.4  109.23    6022  110.66  6063.9   109.7
  6071.3  111.02  6191.5  109.63  6361.7  110.28  6382.6  111.43  6425.2  109.82
  6913.5  110.52  6962.8  111.87  7005.3  110.73  7243.3  111.34  7628.6  115.81
#Mann= 4 ,-1 , 0
  4821.6     .11       0  4956.8     .03       0  5066.4     .15       0
  7243.3     .17       0
Bank Sta=4956.8,5066.4
XS Rating Curve= 0 ,0
Exp/Cntr=0.3,0.1

Type RM Length L Ch R = 1 ,14500   ,500,500,500
BEGIN DESCRIPTION:
Crystal Creek 054 29.0
END DESCRIPTION:
XS GIS Cut Line= 3
      3887558.36     10048614.35      3887357.35     10048608.54
      3884225.63     10049421.46
#Sta/Elev= 30
  4798.9  112.24  4819.4   111.3  4839.4  107.57  4879.4  108.25  4939.5   107.1
  4949.5  105.83  4959.5  109.21  4969.5  109.12  4989.5   102.4  4990.2  101.06
  5020.1  102.61  5040.8   108.5  5051.2 109.135  5175.1  107.22  5206.1  107.96
  5230.5  110.67  5257.8  111.09  5311.6  110.38  5361.1  107.27  5463.5  108.22
  5823.4  107.23  5970.6   108.6  6061.6  107.39  6624.3  108.61  6879.8  107.49
  6962.4  108.72  7034.8  107.64  7222.5  108.56  7298.4  107.72  8235.5  109.49
#Mann= 3 , 0 , 0
  4798.9     .11       0  4969.5     .03       0  5051.2     .15       0
Bank Sta=4969.5,5051.2
XS Rating Curve= 0 ,0
Exp/Cntr=0.3,0.1

Type RM Length L Ch R = 1 ,14000   ,299,299,299
BEGIN DESCRIPTION:
Crystal Creek 054 28.0
END DESCRIPTION:
XS GIS Cut Line= 3
      3887489.37     10048313.66      3887389.31     10048109.56
      3884526.47     10047858.84
#Sta/Elev= 30
   265.6  111.05  690.91  111.06  4776.9  111.05  4784.3  108.63  4797.9  107.43
  4941.8  105.53  4947.4  103.29  4986.8  101.76  4988.7   100.2  5004.1   100.2
  5021.5  102.24  5031.6  104.61  5038.3  107.55  5071.7  106.59  5186.5  107.04
  5275.5  107.04    5846  106.54  5958.5  107.96  5965.1  106.82  6557.4  107.61
    6708  106.58  6958.9  107.71  7039.2  106.75  7216.3  108.22    7240   106.7
  7400.6  106.79  7731.9  107.34    7762  108.38  7812.2   107.4  7873.8  109.51
#Mann= 5 ,-1 , 0
   265.6     .11       0  690.91     .03       0  5038.3     .15       0
  5186.5     .11       0  5275.5     .15       0
Bank Sta=690.91,5038.3
XS Rating Curve= 0 ,0
Exp/Cntr=0.3,0.1

Type RM Length L Ch R = 1 ,13701   ,201,201,201
BEGIN DESCRIPTION:
Mapping XS 72cd2136
END DESCRIPTION:
XS GIS Cut Line= 2
       3887825.3     10047870.97      3884533.94     10047713.94
#Sta/Elev= 30
     458   108.6 1077.27   108.6  4580.1   108.6  4657.6   107.2  4917.9  107.37
    4978  105.04  5000.1   100.2    5016   100.2    5018   101.9  5038.1  107.37
  5048.1  108.48  5102.8  106.82  5668.8  106.41    5849  106.64    5899  107.27
  5909.1  108.87  5959.1  106.85  6179.4  106.39  6439.7  107.65  6539.8  106.55
    6720  107.56  6980.3  106.69  7030.3  107.81  7180.5  106.89  7300.6  108.31
  7360.7  106.99    7641  107.01  7701.1  108.22  7801.2  107.12  7875.2  108.99
#Mann= 3 , 0 , 0
     458     .11       0 1077.27     .03       0  5048.1     .15       0
Bank Sta=1077.27,5048.1
XS Rating Curve= 0 ,0
Exp/Cntr=0.3,0.1

Type RM Length L Ch R = 1 ,13500   ,407,407,407
BEGIN DESCRIPTION:
Crystal Creek 054 27.0
END DESCRIPTION:
XS GIS Cut Line= 3
       3887797.9     10047624.91      3887421.28     10047610.59
       3884437.3     10047621.06
#Sta/Elev= 30
     413   108.7     900   108.7  4625.6   108.7  4643.2  107.17  4943.4   107.2
  4973.4  106.09  4983.4  103.57  4991.3   99.83  5007.2   99.83  5023.4  102.25
  5043.4  107.99  5103.4  106.66  5253.4  106.24  6013.4  107.36  6123.4  106.35
  6253.4  107.48  6573.4  106.44  6603.4  107.74  6643.4  106.46  6853.4  106.97
  6883.4  108.22  6963.4  106.76  7403.4  107.68  7653.4  106.96  7673.4  107.83
  7773.4  107.04  7823.4  107.37  7853.4   109.3  7943.4  107.04    7984  109.38
#Mann= 3 , 0 , 0
     413    .125       0     900     .03       0  5043.4     .15       0
Bank Sta=900,5043.4
XS Rating Curve= 0 ,0
Exp/Cntr=0.3,0.1

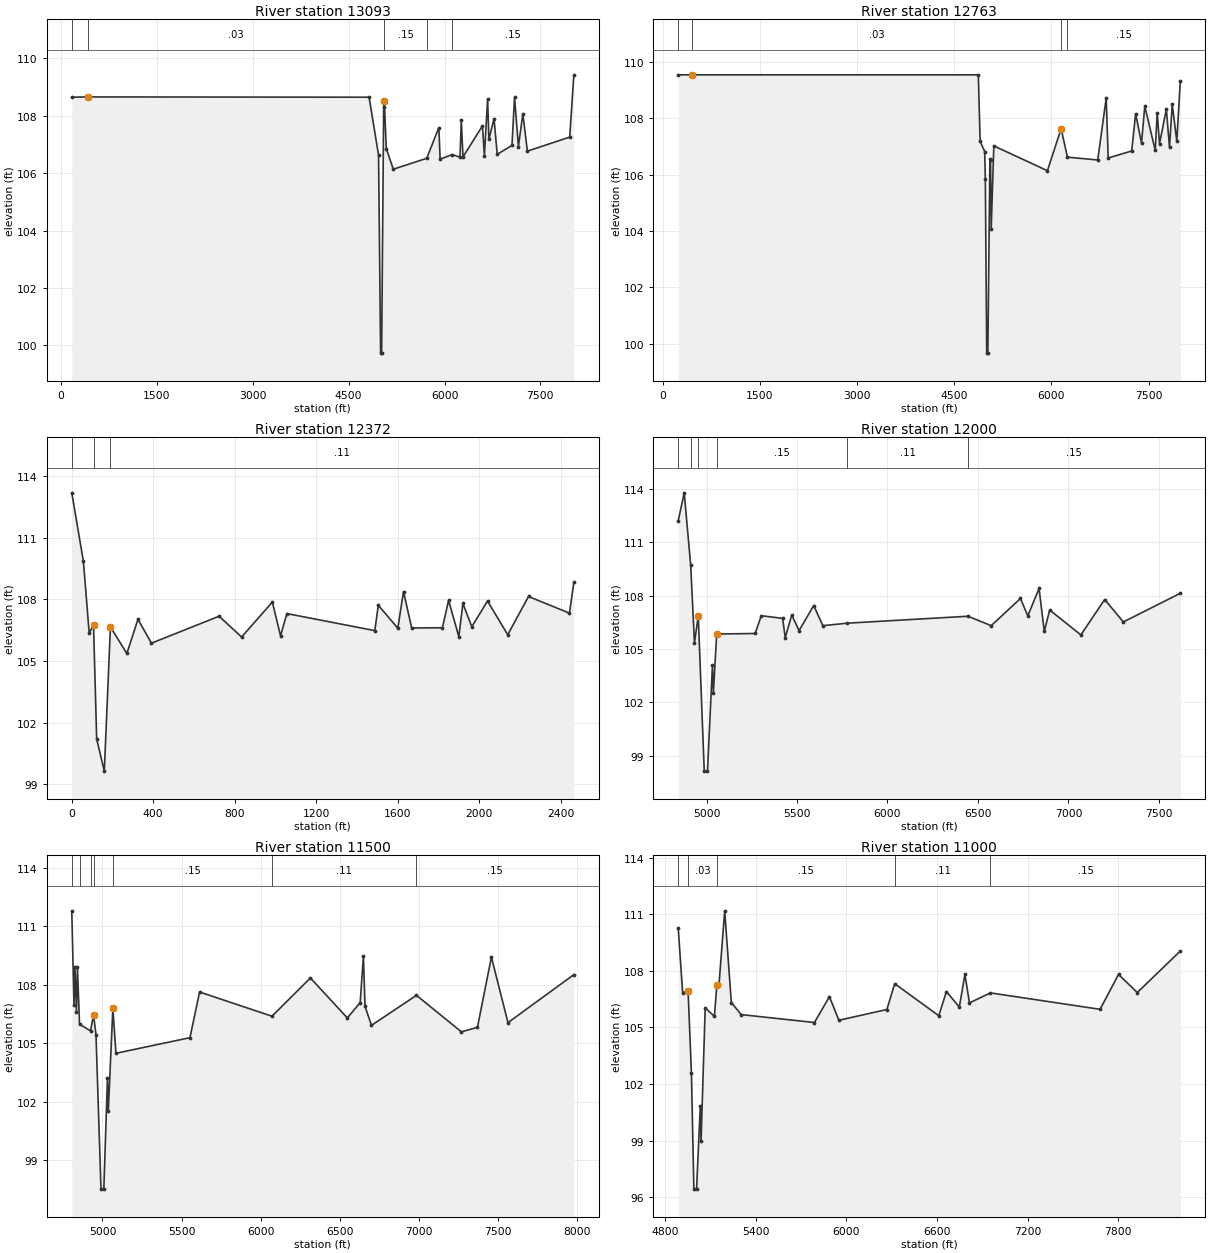
Type RM Length L Ch R = 1 ,13093   ,330,330,330
BEGIN DESCRIPTION:
Mapping XS d51cff92
END DESCRIPTION:
XS GIS Cut Line= 2
      3887627.43      10047210.8      3884433.56     10047483.59
#Sta/Elev= 30
   168.4  108.65   416.9  108.66  4820.1  108.65  4967.9  106.63  5000.1   99.73
  5016.1   99.73  5048.2  108.32  5058.3  108.51  5088.4  106.86  5198.8  106.14
  5721.9  106.52  5911.3  107.59  5931.4  106.49  6120.5  106.65  6242.6  106.56
  6262.6  107.85  6288.8  106.57  6593.8  107.65  6623.9  106.61  6674.1  108.59
  6694.2  107.18  6774.5   107.9  6824.7  106.66  7055.5  106.97  7095.6  108.65
  7155.9  106.93  7225.5  108.07  7296.4  106.77  7958.8  107.26  8023.3  109.43
#Mann= 5 ,-1 , 0
   168.4     .11       0   416.9     .03       0  5058.3     .15       0
  5721.9     .11       0  6120.5     .15       0
Bank Sta=416.9,5058.3
XS Rating Curve= 0 ,0
Exp/Cntr=0.3,0.1

Type RM Length L Ch R = 1 ,12763   ,391,391,391
BEGIN DESCRIPTION:
Crystal Creek 054 26.0
END DESCRIPTION:
XS GIS Cut Line= 3
      3887599.67     10046874.44      3887468.37     10046875.47
      3884504.22     10047256.95
#Sta/Elev= 30
   242.7  109.54  459.72  109.54  4872.1  109.54  4900.5  107.18  4970.5  106.82
  4980.5  105.83  5001.8   99.67  5019.4   99.67  5050.9  106.55    5061  106.52
  5071.1  104.08  5111.4  107.02  5938.2  106.14  6149.9  107.63  6247.4  106.62
  6714.5  106.52  6845.6  108.72  6875.9  106.59  7238.8  106.84  7299.3  108.16
  7390.1  107.12  7440.5  108.43  7601.8  106.86    7632  108.19  7667.8   107.1
  7773.2  108.32  7821.8  106.97  7863.9  108.49  7934.5  107.19  7988.6  109.31
#Mann= 4 ,-1 , 0
   242.7     .11       0  459.72     .03       0  6149.9     .11       0
  6247.4     .15       0
Bank Sta=459.72,6149.9
XS Rating Curve= 0 ,0
Exp/Cntr=0.3,0.1

Type RM Length L Ch R = 1 ,12372   ,372,372,372
XS GIS Cut Line= 3
      3887606.56      10046560.2      3887485.13     10046486.06
      3885176.59     10046741.34
#Sta/Elev= 30
       0  113.18    57.1  109.85    85.5  106.36   106.8  106.76   122.3  101.21
   159.7   99.65   189.8  106.66   270.3  105.37     325  107.03   391.1  105.87
   723.1  107.18   833.8  106.17   984.7  107.87  1024.9  106.23  1056.2  107.31
  1487.7  106.48    1505  107.71  1600.8   106.6  1628.6  108.38  1668.8  106.61
  1819.7  106.62  1849.9  107.95  1900.2  106.19  1920.3   107.8  1963.8  106.67
  2041.1  107.92  2140.3  106.28  2242.3  108.14  2443.5  107.33  2464.9  108.84
#Mann= 3 , 0 , 0
       0     .11       0   106.8     .03       0   189.8     .11       0
Bank Sta=106.8,189.8
XS Rating Curve= 0 ,0
Exp/Cntr=0.3,0.1

Type RM Length L Ch R = 1 ,12000   ,500,500,500
BEGIN DESCRIPTION:
Crystal Creek 054 24.0
END DESCRIPTION:
XS GIS Cut Line= 3
       3887806.2     10046289.36      3887693.36     10046180.92
      3885104.49      10046573.7
#Sta/Elev= 30
  4843.5  112.21  4876.5  113.78  4912.3  109.72  4933.1  105.35  4954.2  106.85
  4987.3   98.13  5005.2   98.13  5032.6  104.09  5037.7  102.52  5056.1  105.84
  5268.5  105.87  5302.5  106.87  5420.3  106.72  5434.9  105.64  5470.8  106.91
  5511.3  106.03  5592.2  107.44  5642.8  106.31  5777.9  106.45  6444.8  106.84
  6573.3  106.31  6735.1  107.84  6775.6  106.86  6837.8   108.4  6866.6  105.99
  6896.5  107.19  7068.9  105.79  7200.4  107.78  7303.8  106.52  7618.5  108.13
#Mann= 6 ,-1 , 0
  4843.5     .17       0  4912.3     .15       0  4954.2     .03       0
  5056.1     .15       0  5777.9     .11       0  6444.8     .15       0
Bank Sta=4954.2,5056.1
XS Rating Curve= 0 ,0
Exp/Cntr=0.3,0.1

Type RM Length L Ch R = 1 ,11500   ,500,500,500
BEGIN DESCRIPTION:
Crystal Creek 054 23.0
END DESCRIPTION:
XS GIS Cut Line= 3
      3888090.05     10045948.18       3887992.4      10045780.2
       3885057.7     10046308.06
#Sta/Elev= 30
  4805.7  111.78  4819.9  106.97  4825.6   108.9  4835.6   106.6  4841.4   108.9
  4854.8  105.97  4924.4  105.63  4943.2  106.45  4958.9  105.44  4990.6   97.52
  5008.5   97.52  5031.6  103.23  5036.7   101.5  5065.6  106.78  5085.2  104.48
  5553.3  105.28  5614.3  107.62  6072.2  106.38  6315.3  108.34    6549  106.29
  6630.3  107.08  6650.6  109.47  6660.8  106.89  6701.4  105.91  6986.2  107.45
  7270.4  105.58    7372  105.81  7460.3  109.41  7565.1  106.05  7981.8  108.51
#Mann= 7 ,-1 , 0
  4805.7     .17       0  4854.8     .15       0  4924.4     .11       0
  4943.2     .03       0  5065.6     .15       0  6072.2     .11       0
  6986.2     .15       0
Bank Sta=4943.2,5065.6
XS Rating Curve= 0 ,0
Exp/Cntr=0.3,0.1

Type RM Length L Ch R = 1 ,11000   ,500,500,500
BEGIN DESCRIPTION:
Crystal Creek 054 22.0
END DESCRIPTION:
XS GIS Cut Line= 3
       3888350.5     10045476.88      3888291.44     10045379.49
      3885135.76     10045979.94
#Sta/Elev= 30
  4886.1  110.26  4915.3  106.84  4951.4  106.93  4973.5  102.58  4989.7   96.43
  5007.6   96.43  5032.2  100.83  5037.3   98.98  5064.7  106.03  5125.8  105.59
  5141.7  107.23  5156.3  107.28  5193.9  111.18  5237.8  106.32  5303.3  105.68
  5788.4  105.26  5887.7  106.63  5950.3  105.38  6268.3  105.95  6320.2  107.32
    6612  105.62  6662.9   106.9  6748.3  106.08  6785.1  107.81  6815.6   106.3
  6954.4  106.83  7680.8  105.96    7803  107.81  7927.2  106.85  8212.3  109.05
#Mann= 5 ,-1 , 0
  4886.1     .11       0  4951.4     .03       0  5141.7     .15       0
  6320.2     .11       0  6954.4     .15       0
Bank Sta=4951.4,5141.7
XS Rating Curve= 0 ,0
Exp/Cntr=0.3,0.1

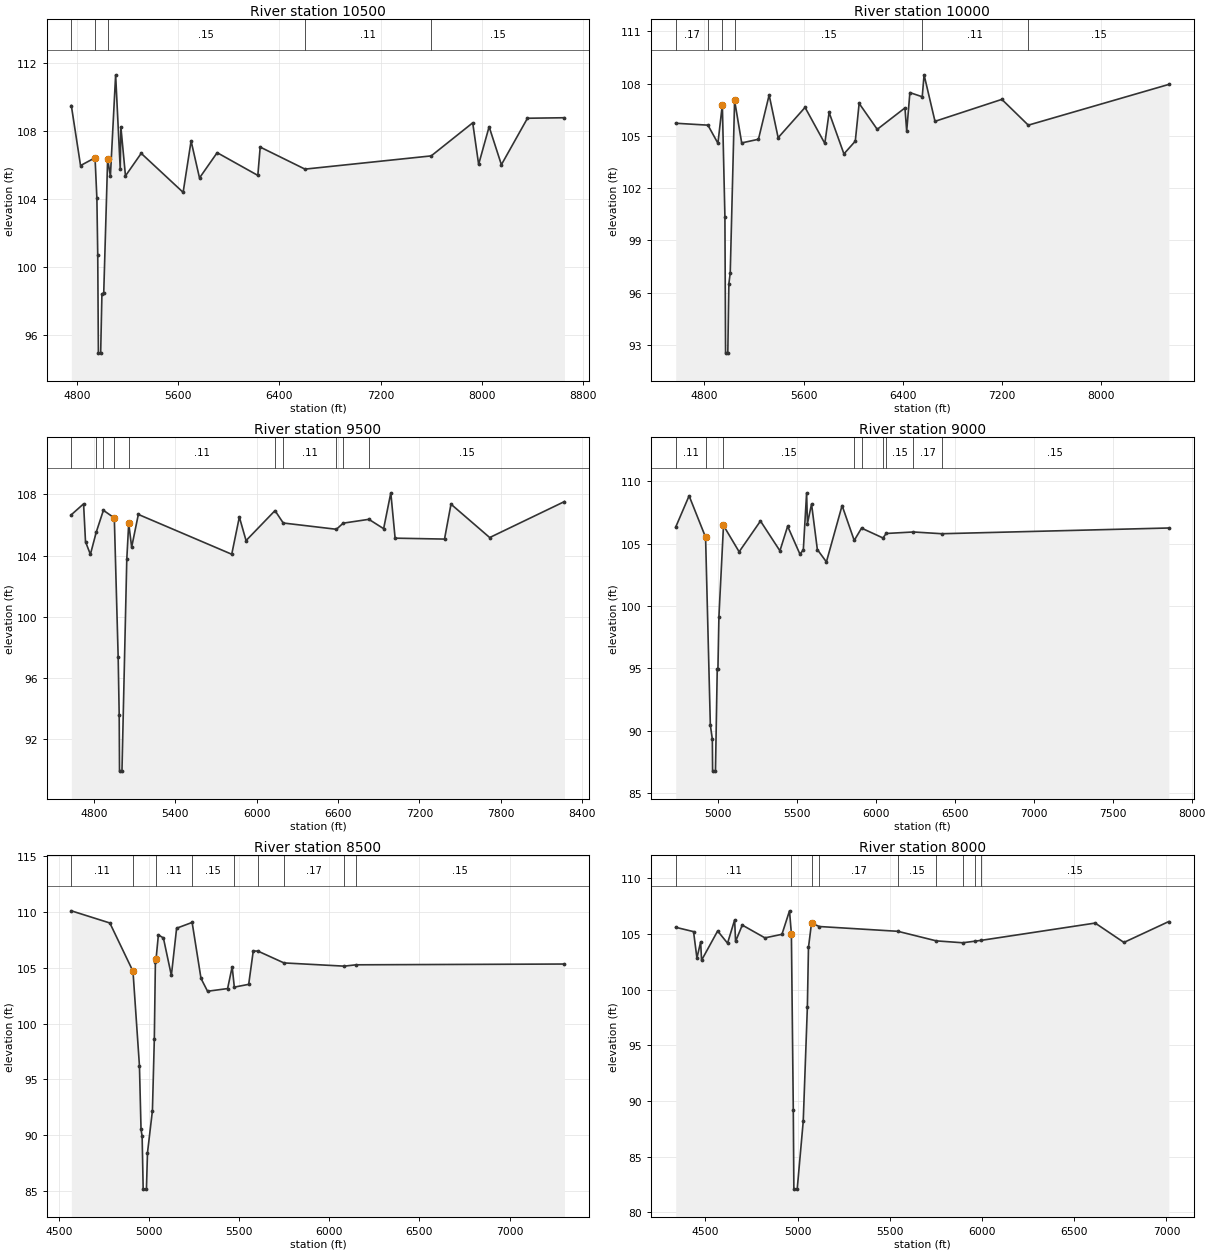
Type RM Length L Ch R = 1 ,10500   ,500,500,500
BEGIN DESCRIPTION:
Crystal Creek 054 21.0
END DESCRIPTION:
XS GIS Cut Line= 3
      3888704.67     10044804.98      3888509.88     10044951.43
      3884963.94     10045828.89
#Sta/Elev= 30
  4756.3  109.52  4829.2  105.98  4943.7  106.44  4958.3  104.04    4965  100.73
  4970.1   94.92  4988.1   94.92  4998.1   98.41  5012.4   98.47  5043.3  106.37
    5065  105.35  5106.4  111.33  5142.7  105.78  5147.8  108.26  5184.1  105.37
  5308.4   106.7  5639.7   104.4  5702.6  107.43  5769.1  105.25  5908.6  106.74
  6229.9   105.4  6248.6  107.07  6602.5  105.77  7599.9  106.55  7927.8   108.5
  7974.6  106.05  8057.4  108.27  8154.4  106.03  8360.4  108.77  8652.9   108.8
#Mann= 5 ,-1 , 0
  4756.3     .11       0  4943.7     .03       0  5043.3     .15       0
  6602.5     .11       0  7599.9     .15       0
Bank Sta=4943.7,5043.3
XS Rating Curve= 0 ,0
Exp/Cntr=0.3,0.1

Type RM Length L Ch R = 1 ,10000   ,500,500,500
BEGIN DESCRIPTION:
Crystal Creek 054 20.0
END DESCRIPTION:
XS GIS Cut Line= 4
      3888536.86     10044370.62      3888208.48     10044650.38
      3888021.24      10044809.2      3884838.92     10045672.64
#Sta/Elev= 30
  4568.6  105.72  4828.3  105.61  4908.9  104.57  4944.4  106.79  4965.2  100.36
  4970.5   92.52  4988.5   92.52  4997.1    96.5  5008.1   97.13  5043.2  107.03
  5100.4  104.59  5235.5   104.8  5321.6  107.34  5394.1  104.89    5611  106.63
  5770.3  104.56  5804.9  106.34  5924.3  103.96  6015.8  104.69  6046.9  106.86
  6192.7  105.37  6416.1   106.6  6430.2  105.27  6455.9  107.48  6555.4  107.24
  6570.2   108.5  6658.2  105.83    7197  107.09  7410.1  105.61  8542.9  107.95
#Mann= 6 ,-1 , 0
  4568.6     .17       0  4828.3     .15       0  4944.4     .03       0
  5043.2     .15       0  6555.4     .11       0  7410.1     .15       0
Bank Sta=4944.4,5043.2
XS Rating Curve= 0 ,0
Exp/Cntr=0.3,0.1

Type RM Length L Ch R = 1 ,9500    ,500,500,500
BEGIN DESCRIPTION:
Crystal Creek 054 19.0
END DESCRIPTION:
XS GIS Cut Line= 4
      3888033.07     10044068.32      3887759.09     10044312.35
      3887385.77     10044646.61        3884766.     10045542.43
#Sta/Elev= 30
  4633.1  106.67  4723.5  107.38  4737.7  104.91  4773.7  104.08  4816.9  105.53
  4869.6  106.96  4950.1  106.46  4978.6   97.36  4986.1   93.59  4988.5   89.93
  5006.5   89.93  5042.1  103.76  5056.3  106.11    5078  104.55  5127.3  106.69
    5816  104.09  5872.2  106.52  5921.6  104.98  6135.1  106.94  6195.8  106.13
    6588  105.72  6637.9  106.12  6827.3  106.37  6936.2  105.76  6989.1   108.1
  7020.8  105.14  7385.1  105.08  7432.9  107.36  7718.3  105.18  8269.8  107.53
#Mann= 10 ,-1 , 0
  4633.1     .17       0  4816.9     .11       0  4869.6     .17       0
  4950.1     .03       0  5056.3     .11       0  6135.1     .17       0
  6195.8     .11       0    6588     .17       0  6637.9     .11       0
  6827.3     .15       0
Bank Sta=4950.1,5056.3
XS Rating Curve= 0 ,0
Exp/Cntr=0.3,0.1

Type RM Length L Ch R = 1 ,9000    ,500,500,500
BEGIN DESCRIPTION:
Crystal Creek 054 18.0
END DESCRIPTION:
XS GIS Cut Line= 4
      3887381.99     10043954.16      3887287.04     10044204.13
      3887146.19     10044526.81       3884776.4      10045334.1
#Sta/Elev= 30
  4732.6  106.33  4817.4  108.84  4921.8  105.52    4952   90.45  4964.6   89.32
  4966.3   86.76  4984.4   86.76  4995.7   94.97    5000   94.97  5006.3   99.14
  5035.2  106.46  5134.3  104.35  5269.4  106.82  5392.6  104.43  5441.5   106.4
  5519.4  104.16  5540.8  104.51  5561.6  109.08  5566.9  106.62  5592.9  108.18
  5629.6  104.53    5687  103.54  5786.3  108.06  5863.1  105.26  5909.5  106.25
  6045.3  105.46  6065.5  105.82  6237.9  105.94  6417.9   105.8  7855.6  106.26
#Mann= 9 ,-1 , 0
  4732.6     .11       0  4921.8     .03       0  5035.2     .15       0
  5863.1     .17       0  5909.5     .15       0  6045.3     .17       0
  6065.5     .15       0  6237.9     .17       0  6417.9     .15       0
Bank Sta=4921.8,5035.2
XS Rating Curve= 0 ,0
Exp/Cntr=0.3,0.1

Type RM Length L Ch R = 1 ,8500    ,500,500,500
BEGIN DESCRIPTION:
Crystal Creek 054 17.0
END DESCRIPTION:
XS GIS Cut Line= 4
      3887033.93      10043809.7      3886788.48     10044166.29
      3886661.81     10044412.23      3884755.52     10045104.96
#Sta/Elev= 30
  4567.1  110.12  4780.9  109.03  4909.4   104.7  4945.3   96.22  4954.1   90.52
  4960.2   89.91    4966   85.17  4984.1   85.17  4989.9   88.43  5017.3    92.2
  5027.9   98.63  5033.8  105.52  5037.4105.7771  5050.4  107.96  5078.2  107.69
  5122.5  104.33  5151.6  108.56  5237.8  109.08    5287  104.06  5323.4  102.91
  5434.7  103.15    5460   105.1    5472  103.28  5551.8  103.53  5577.1  106.52
    5603  106.51  5747.6  105.45  6082.4  105.16  6147.1  105.28  7304.9  105.35
#Mann= 9 ,-1 , 0
  4567.1     .11       0  4909.4     .03       0  5037.4     .11       0
  5237.8     .15       0    5472     .17       0    5603     .15       0
  5747.6     .17       0  6082.4     .11       0  6147.1     .15       0
Bank Sta=4909.4,5037.4
XS Rating Curve= 0 ,0
Exp/Cntr=0.3,0.1

Type RM Length L Ch R = 1 ,8000    ,500,500,500
BEGIN DESCRIPTION:
Crystal Creek 054 16.0
END DESCRIPTION:
XS GIS Cut Line= 4
      3886513.28     10043318.81      3886369.82     10043963.44
      3886219.11     10044261.19      3884708.69     10044995.56
#Sta/Elev= 30
  4339.6   105.6  4436.4  105.21  4454.6  102.84  4474.8  104.28  4479.9  102.64
    4567  105.27  4620.7  104.17  4659.1  106.26  4664.2  104.33  4700.5   105.8
  4823.4  104.65  4915.6  104.97  4956.6  107.08  4966.8  105.01  4977.1   89.21
  4980.2   82.07  4998.3   82.07    5031   88.17  5053.4   98.43  5059.4  103.79
  5075.9105.9752  5118.1  105.67  5543.9  105.24  5752.6  104.38  5895.3  104.21
  5961.2  104.35  5997.2  104.43  6613.8  105.98  6769.5  104.24  7013.2  106.12
#Mann= 9 ,-1 , 0
  4339.6     .11       0  4966.8     .03       0  5075.9     .11       0
  5118.1     .17       0  5543.9     .15       0  5752.6     .11       0
  5895.3     .15       0  5961.2     .11       0  5997.2     .15       0
Bank Sta=4966.8,5075.9
XS Rating Curve= 0 ,0
Exp/Cntr=0.3,0.1

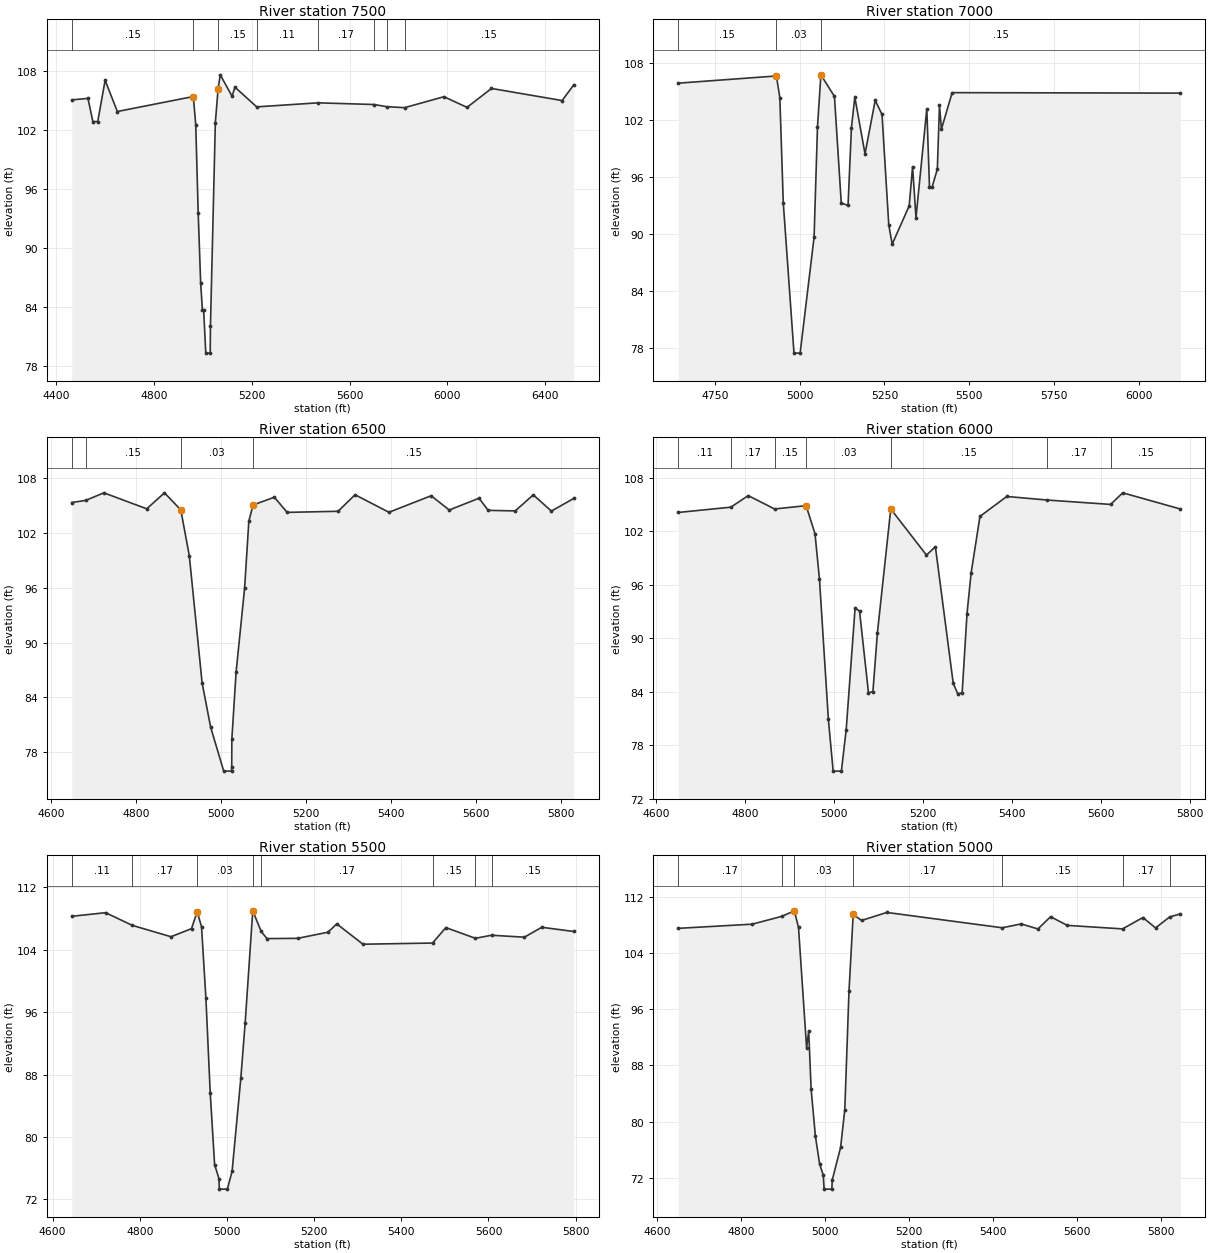
Type RM Length L Ch R = 1 ,7500    ,500,500,500
BEGIN DESCRIPTION:
Crystal Creek 054 15.0
END DESCRIPTION:
XS GIS Cut Line= 4
      3885836.66     10043394.96      3885870.94     10043930.67
      3885849.31     10044255.98      3884788.36     10044796.86
#Sta/Elev= 30
  4463.2  105.03  4529.4  105.18  4549.5  102.83  4569.5  102.83  4599.6  107.01
  4649.7  103.85  4960.3  105.37  4970.3  102.53  4980.4   93.52  4990.4   86.46
  4997.7   83.68  5002.7   83.68  5011.4   79.35  5029.5   79.35  5030.5   82.13
  5050.5  102.73  5061.6106.1086  5070.6  107.57  5118.8   105.4  5130.7  106.32
  5219.6  104.32  5469.9  104.73  5699.4  104.56  5751.3  104.34  5824.4  104.24
  5985.5  105.35  6080.1  104.27    6180  106.19    6469  104.96  6516.9  106.57
#Mann= 8 ,-1 , 0
  4463.2     .15       0  4960.3     .03       0  5061.6     .15       0
  5219.6     .11       0  5469.9     .17       0  5699.4     .15       0
  5751.3     .17       0  5824.4     .15       0
Bank Sta=4960.3,5061.6
XS Rating Curve= 0 ,0
Exp/Cntr=0.3,0.1

Type RM Length L Ch R = 1 ,7000    ,500,500,500
BEGIN DESCRIPTION:
Crystal Creek 054 14.0
END DESCRIPTION:
XS GIS Cut Line= 4
      3885310.48     10043546.31      3885371.98     10043898.38
      3885364.94     10044261.19       3884708.7     10044641.39
#Sta/Elev= 30
  4642.6  105.92  4931.7  106.68  4941.8   104.4    4952   93.28  4983.5   77.43
  5001.6   77.43  5042.7   89.66  5052.7   101.3  5062.7   106.8  5102.7  104.52
  5122.7   93.28  5142.7   93.01  5152.7  101.23  5162.7  104.44  5192.7   98.46
  5222.7   104.1  5242.7  102.63  5262.7   90.95  5272.7   88.93  5322.8   92.97
  5332.8   97.09  5342.8   91.72  5374.7  103.21  5382.6   94.93  5390.5   94.99
  5405.7   96.84    5412  103.58  5417.8  101.07  5449.3  104.92  6121.3  104.87
#Mann= 3 , 0 , 0
  4642.6     .15       0  4931.7     .03       0  5062.7     .15       0
Bank Sta=4931.7,5062.7
XS Rating Curve= 0 ,0
Exp/Cntr=0.3,0.1

Type RM Length L Ch R = 1 ,6500    ,500,500,500
BEGIN DESCRIPTION:
Crystal Creek 054 13.0
END DESCRIPTION:
XS GIS Cut Line= 4
      3884846.94     10043515.09      3884873.01     10043866.33
      3884876.13     10044240.44      3884569.34      10044577.5
#Sta/Elev= 30
  4647.8  105.33  4680.6  105.56  4723.3  106.39  4824.3  104.64  4866.1  106.39
  4904.5  104.52  4924.5   99.51  4954.6    85.6  4974.7   80.74  5005.6   75.92
  5023.9   75.92  5024.4   76.42  5024.7   79.45  5034.7   86.75  5054.7   95.94
  5064.7  103.29  5074.7  105.06  5124.8  105.91  5154.8  104.25  5274.8  104.37
  5314.8  106.18  5394.6  104.26  5493.9  106.07  5536.5  104.51  5606.7   105.8
  5628.3  104.47  5691.9  104.41  5734.4  106.17    5777  104.39  5829.9  105.78
#Mann= 4 ,-1 , 0
  4647.8     .11       0  4680.6     .15       0  4904.5     .03       0
  5074.7     .15       0
Bank Sta=4904.5,5074.7
XS Rating Curve= 0 ,0
Exp/Cntr=0.3,0.1

Type RM Length L Ch R = 1 ,6000    ,500,500,500
BEGIN DESCRIPTION:
Crystal Creek 054 12.0
END DESCRIPTION:
XS GIS Cut Line= 3
       3884383.4     10043483.81      3884374.04     10043834.28
      3884318.06     10044610.17
#Sta/Elev= 30
  4649.4   104.1  4767.6  104.69  4806.7  105.99  4865.9  104.49  4936.8  104.86
  4956.8  101.72  4966.8   96.64  4986.8   80.94  4997.6    75.1  5016.1    75.1
  5026.9   79.73  5046.9   93.38  5056.9   93.04    5077   83.88    5087   84.02
    5097   90.57  5127.1  104.49  5207.3   99.32  5227.4  100.25  5267.5   84.94
  5277.5   83.79  5287.5   83.85  5298.5   92.76  5307.6   97.28  5327.6  103.66
  5387.8  105.89  5479.2  105.49  5621.2     105  5648.5   106.3  5777.9  104.49
#Mann= 7 ,-1 , 0
  4649.4     .11       0  4767.6     .17       0  4865.9     .15       0
  4936.8     .03       0  5127.1     .15       0  5479.2     .17       0
  5621.2     .15       0
Bank Sta=4936.8,5127.1
XS Rating Curve= 0 ,0
Exp/Cntr=0.3,0.1

Type RM Length L Ch R = 1 ,5500    ,500,500,500
BEGIN DESCRIPTION:
Crystal Creek 054 11.0
END DESCRIPTION:
XS GIS Cut Line= 3
      3883864.44     10043443.49      3883875.26     10043799.33
      3883844.11     10044594.52
#Sta/Elev= 30
    4644  108.29  4721.6  108.75  4783.1  107.12  4871.7  105.67  4918.7  106.71
  4931.7  108.87  4941.7  106.94  4951.7   97.81  4961.7   85.58  4971.7   76.45
  4981.7   74.66  4982.5   73.31    5001   73.31  5011.8    75.6  5031.8   87.53
  5041.8   94.64  5059.2  108.99  5078.5  106.35  5091.8  105.43  5161.9  105.46
  5231.9  106.25  5251.9  107.32    5312  104.71  5471.7  104.86  5502.1  106.84
    5570  105.47    5607  105.86  5682.3  105.61  5722.3  106.88  5795.8  106.34
#Mann= 8 ,-1 , 0
    4644     .11       0  4783.1     .17       0  4931.7     .03       0
  5059.2     .15       0  5078.5     .17       0  5471.7     .15       0
    5570     .17       0    5607     .15       0
Bank Sta=4931.7,5059.2
XS Rating Curve= 0 ,0
Exp/Cntr=0.3,0.1

Type RM Length L Ch R = 1 ,5000    ,500,500,500
BEGIN DESCRIPTION:
Crystal Creek 054 10.0
END DESCRIPTION:
XS GIS Cut Line= 3
       3883343.6     10043415.75      3883376.55     10043763.49
      3883349.31     10044610.15
#Sta/Elev= 30
  4650.7   107.5  4826.8  108.09  4897.9  109.21  4927.3  109.99  4937.3  107.63
  4956.6   90.48  4961.6   92.92  4967.4   84.58  4977.5   77.97  4987.5   74.01
  4996.3   72.39  4998.3   70.41  5016.8   70.41  5017.6   71.69  5037.6   76.34
  5047.6   81.73  5057.6   98.57  5067.6  109.48  5087.6  108.62  5147.7  109.76
  5422.8  107.58  5467.8  108.13  5507.8  107.41  5537.9  109.15  5577.9  107.92
  5709.5  107.42    5758  109.04    5788  107.56  5821.8  109.12  5847.1  109.55
#Mann= 7 ,-1 , 0
  4650.7     .17       0  4897.9     .15       0  4927.3     .03       0
  5067.6     .17       0  5422.8     .15       0  5709.5     .17       0
  5821.8     .15       0
Bank Sta=4927.3,5067.6
XS Rating Curve= 0 ,0
Exp/Cntr=0.3,0.1