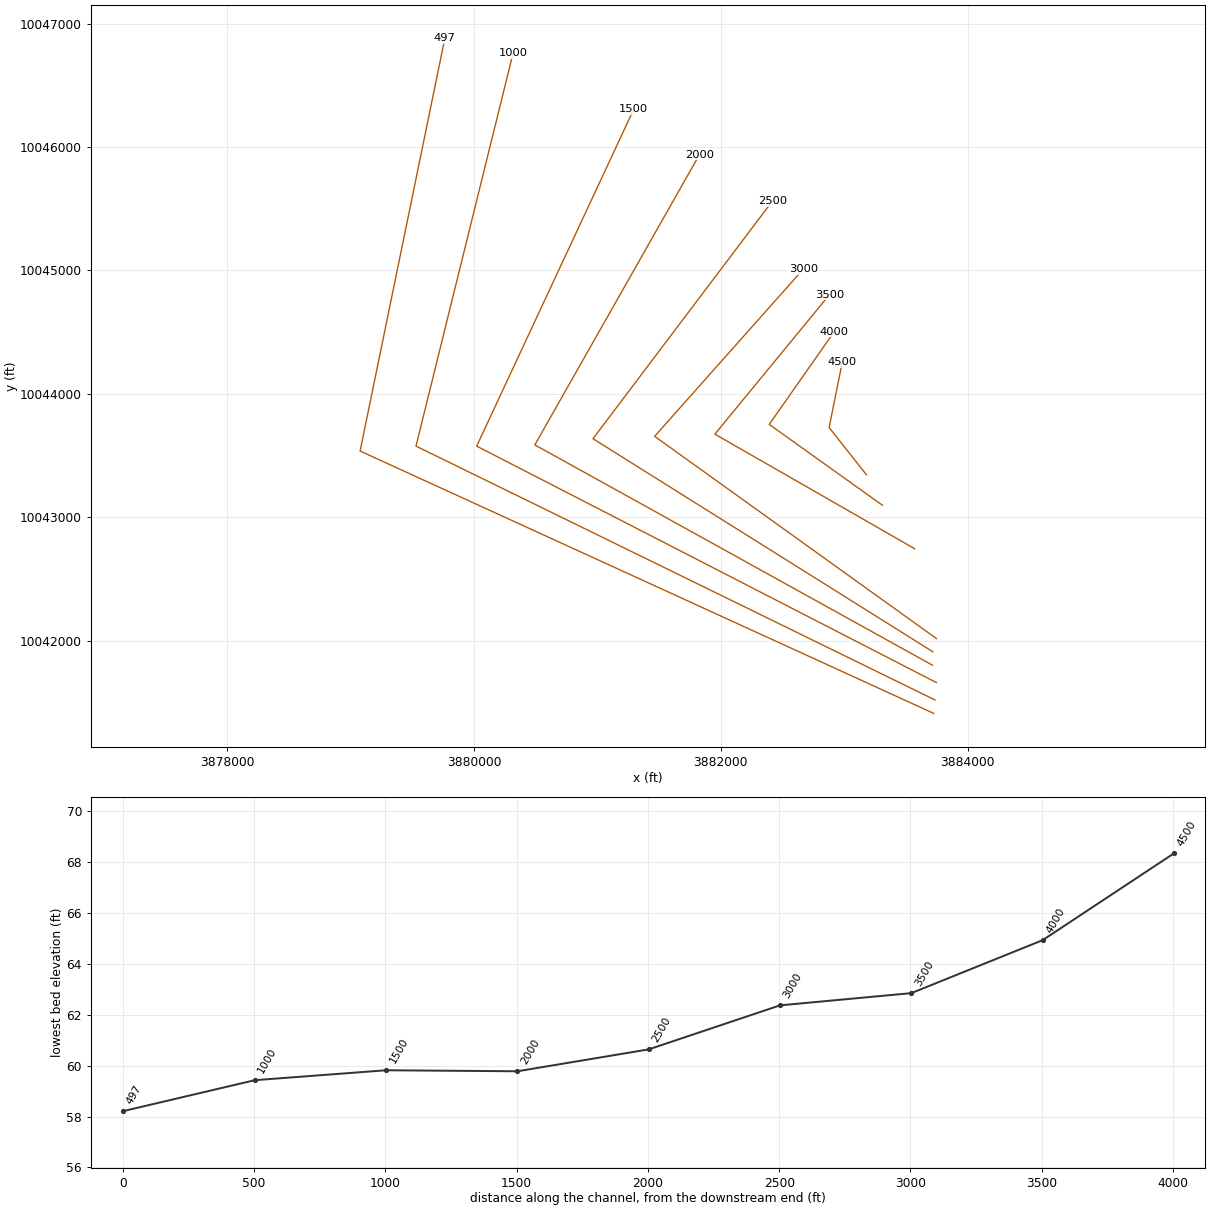
HEC-RAS study Crystal Creek 054.prj: Crystal Creek 054 Base Level Engineering

--- Crystal Creek 054.g01 (geometry) --- (continued)

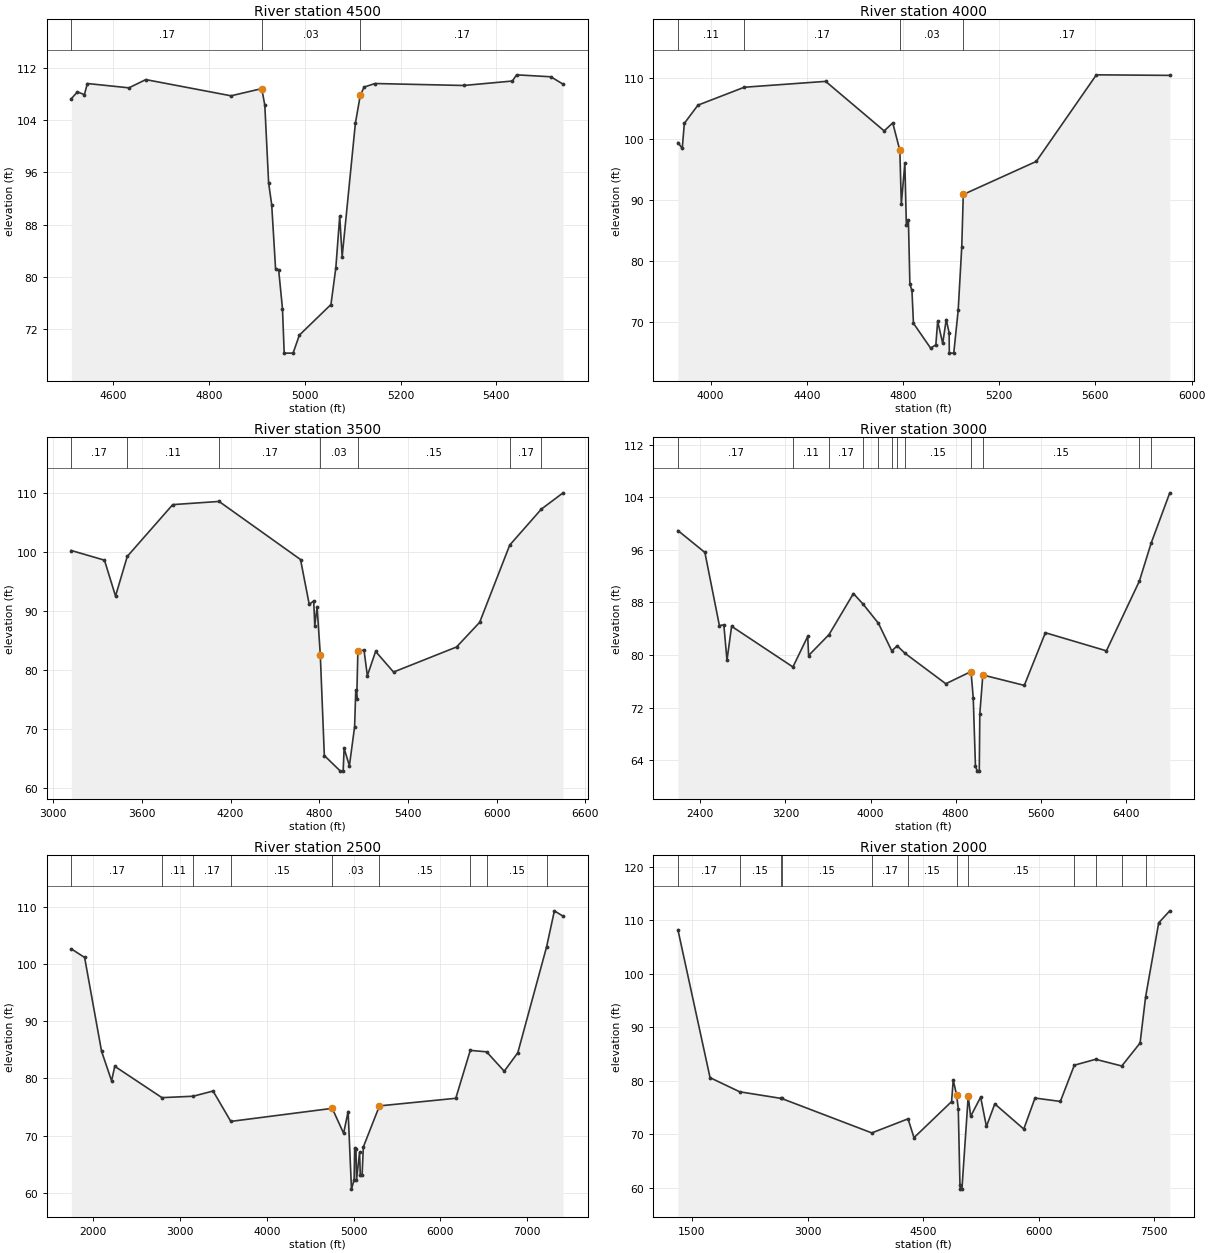
Type RM Length L Ch R = 1 ,4500    ,500,500,500
BEGIN DESCRIPTION:
Crystal Creek 054 9.0
END DESCRIPTION:
XS GIS Cut Line= 3
      3883179.96     10043344.81      3882877.83     10043727.65
      3882984.61     10044256.18
#Sta/Elev= 30
  4512.3  107.27  4525.2  108.32  4539.7   107.9    4546   109.6  4632.7  108.94
  4667.9   110.2  4845.9  107.72    4910  108.82  4916.4  106.29  4924.4   94.37
  4930.8   91.04  4938.9   81.22  4945.3    81.1  4953.3   75.14  4956.9   68.34
  4975.4   68.34  4988.6    71.1  5054.5   75.78  5064.7   81.39  5072.8   89.29
  5077.9   83.11  5105.5  103.51  5115.7  107.78  5123.6  109.05  5146.3   109.6
  5331.7   109.3  5433.2  109.98  5442.2  110.93  5513.6  110.63  5539.2   109.5
#Mann= 3 , 0 , 0
  4512.3     .17       0    4910     .03       0  5115.7     .17       0
Bank Sta=4910,5115.7
XS Rating Curve= 0 ,0
Exp/Cntr=0.3,0.1

Type RM Length L Ch R = 1 ,4000    ,500,500,500
BEGIN DESCRIPTION:
Crystal Creek 054 8.0
END DESCRIPTION:
XS GIS Cut Line= 3
      3883310.14     10043097.45      3882392.87     10043752.87
      3882919.54     10044503.71
#Sta/Elev= 30
  3864.5   99.38  3882.5   98.41  3891.1  102.51  3947.7  105.49  4140.2  108.42
  4478.5  109.38  4721.8  101.28  4757.5  102.59    4787   98.08  4793.1   89.31
  4807.8      96    4814   85.96  4822.6   86.63  4828.7   76.22  4837.3   75.18
  4843.5   69.82  4914.8   65.75  4936.6   66.29  4944.2   70.17  4965.1   66.52
  4979.9   70.42  4991.9   68.24  4992.6   64.93  5011.1   64.93  5029.5   71.96
  5044.3   82.29  5050.7   90.88  5353.8   96.28  5603.9  110.45    5909  110.36
#Mann= 4 ,-1 , 0
  3864.5     .11       0  4140.2     .17       0    4787     .03       0
  5050.7     .17       0
Bank Sta=4787,5050.7
XS Rating Curve= 0 ,0
Exp/Cntr=0.3,0.1

Type RM Length L Ch R = 1 ,3500    ,500,500,500
BEGIN DESCRIPTION:
Crystal Creek 054 7.0
END DESCRIPTION:
XS GIS Cut Line= 3
      3883570.58     10042745.87      3881952.34     10043673.87
      3882880.47     10044803.16
#Sta/Elev= 30
    3122  100.26  3346.7   98.62  3421.5   92.53  3500.9   99.26  3808.4  108.04
  4121.8  108.58  4672.9   98.73  4731.9   91.12  4762.1   91.71  4769.3   87.51
  4785.1   90.69  4806.7   82.58    4834   65.49  4942.7   62.85  4961.3   62.85
  4967.8    66.7  5003.6   63.77  5038.8   70.38  5046.7   76.65  5053.1   75.14
    5061   83.24  5102.6   83.35  5124.9   79.03  5180.9   83.15  5302.1   79.65
  5728.3    83.9  5884.7   88.08  6088.1  101.18  6302.1  107.28  6449.2  110.04
#Mann= 7 ,-1 , 0
    3122     .17       0  3500.9     .11       0  4121.8     .17       0
  4806.7     .03       0    5061     .15       0  6088.1     .17       0
  6302.1     .15       0
Bank Sta=4806.7,5061
XS Rating Curve= 0 ,0
Exp/Cntr=0.3,0.1

Type RM Length L Ch R = 1 ,3000    ,500,500,500
BEGIN DESCRIPTION:
Crystal Creek 054 6.0
END DESCRIPTION:
XS GIS Cut Line= 3
      3883747.76     10042017.49      3881464.51     10043656.12
      3882669.02     10045010.75
#Sta/Elev= 30
  2189.6   98.93  2443.1    95.6  2579.4   84.49  2621.2    84.6  2650.7   79.22
  2694.1   84.38  3270.5    78.2  3409.5   82.84  3418.1   79.94  3609.9   83.12
  3839.3   89.36  3930.4   87.74  4074.7   84.83  4199.5   80.64  4250.9   81.41
  4324.3   80.27  4707.5   75.65  4944.5    77.5  4965.4   73.52  4986.2   63.12
  5003.6   62.37  5022.2   62.37  5027.2   71.07  5055.6   76.98  5445.3    75.4
  5643.4    83.4  6217.1   80.65  6527.1   91.25  6637.3      97  6812.7  104.66
#Mann= 12 ,-1 , 0
  2189.6     .17       0  3270.5     .11       0  3609.9     .17       0
  3930.4     .11       0  4074.7     .17       0  4199.5     .15       0
  4250.9     .17       0  4324.3     .15       0  4944.5     .03       0
  5055.6     .15       0  6527.1     .11       0  6637.3     .15       0
Bank Sta=4944.5,5055.6
XS Rating Curve= 0 ,0
Exp/Cntr=0.3,0.1

Type RM Length L Ch R = 1 ,2500    ,500,500,500
BEGIN DESCRIPTION:
Crystal Creek 054 5.0
END DESCRIPTION:
XS GIS Cut Line= 3
      3883718.09     10041910.83      3880964.89     10043636.84
      3882417.87     10045561.09
#Sta/Elev= 30
  1750.5  102.64  1904.2  101.14  2099.1   84.75  2214.6   79.57  2251.1   82.11
  2794.5   76.63  3153.3   76.88  3382.5   77.79  3586.7   72.48  4754.2   74.76
    4885    70.4  4936.8    74.2  4975.6   60.64  5005.8   62.27  5012.4   67.82
    5027   67.72  5033.2    62.2  5068.6   67.08  5076.9   63.19  5097.7   63.12
  5112.3   68.02  5297.5   75.19  6175.9   76.52  6342.8    84.9  6530.8   84.64
  6733.7   81.25  6889.8   84.49  7220.9  102.98  7310.9  109.29  7411.2  108.35
#Mann= 9 ,-1 , 0
  1750.5     .17       0  2794.5     .11       0  3153.3     .17       0
  3586.7     .15       0  4754.2     .03       0  5297.5     .15       0
  6342.8     .17       0  6530.8     .15       0  7220.9     .11       0
Bank Sta=4754.2,5297.5
XS Rating Curve= 0 ,0
Exp/Cntr=0.3,0.1

Type RM Length L Ch R = 1 ,2000    ,500,500,500
BEGIN DESCRIPTION:
Crystal Creek 054 4.0
END DESCRIPTION:
XS GIS Cut Line= 3
      3883714.49     10041802.24      3880493.88     10043586.84
      3881826.46     10045936.24
#Sta/Elev= 30
    1318  108.22    1735    80.6  2119.6   77.96  2655.1   76.73    2664   76.71
  3834.2   70.28  4304.5   72.91  4381.6   69.39  4869.3   76.13    4891   80.15
  4934.5   77.36  4956.3   74.83    4978   60.58  4984.5   59.78  5003.6   59.78
  5085.3   77.12  5116.8   73.37  5246.6   76.97  5321.6   71.48  5430.2    75.7
  5806.3      71  5951.9   76.79    6281   76.16  6462.5   82.93  6739.4   84.03
  7078.1   82.78  7315.7   87.07  7387.1   95.66  7557.3  109.52    7701  111.76
#Mann= 12 ,-1 , 0
    1318     .17       0  2119.6     .15       0  2655.1     .11       0
    2664     .15       0  3834.2     .17       0  4304.5     .15       0
  4934.5     .03       0  5085.3     .15       0  6462.5     .17       0
  6739.4     .11       0  7078.1     .15       0  7387.1     .17       0
Bank Sta=4934.5,5085.3
XS Rating Curve= 0 ,0
Exp/Cntr=0.3,0.1

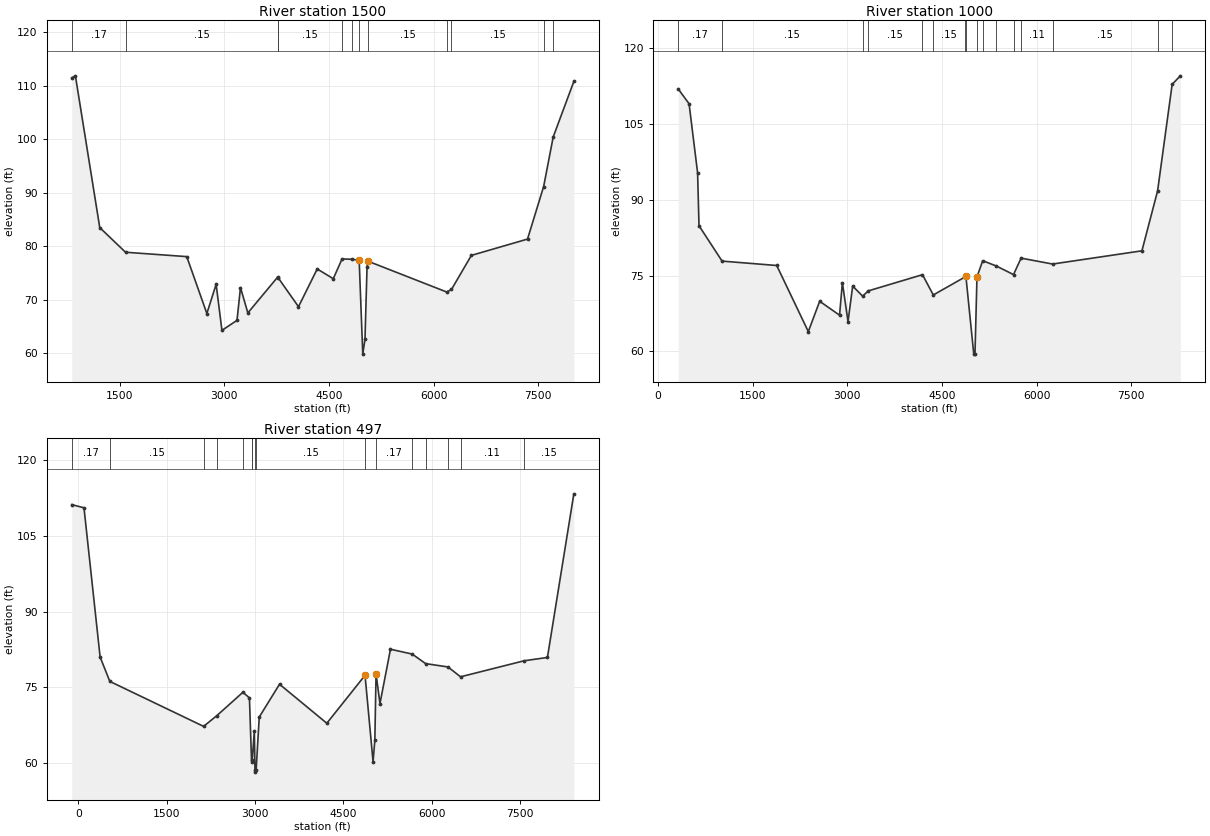
Type RM Length L Ch R = 1 ,1500    ,500,500,500
BEGIN DESCRIPTION:
Crystal Creek 054 3.0
END DESCRIPTION:
XS GIS Cut Line= 3
      3883747.06     10041661.17      3880022.88     10043576.84
      3881294.81     10046305.23
#Sta/Elev= 30
     812  111.49   864.1  111.88  1213.3   83.49  1582.8   78.88  2460.5   78.06
  2748.7   67.42  2881.8   72.88  2964.9   64.26    3181   66.14    3231   72.27
  3336.3   67.53  3766.8   74.27  3772.3   74.08  4062.5   68.69  4330.9   75.75
  4561.3   73.93  4687.2   77.63  4833.5   77.56  4932.6   77.37    4984   59.82
  5015.7   62.58  5045.3   76.04  5059.8    77.2  6187.4   71.44  6255.8   71.91
  6541.1   78.29  7346.1   81.34  7577.3   91.17  7714.3  100.44  8010.3  110.83
#Mann= 12 ,-1 , 0
     812     .17       0  1582.8     .15       0  3766.8     .17       0
  3772.3     .15       0  4687.2     .17       0  4833.5     .15       0
  4932.6     .03       0  5059.8     .15       0  6187.4     .11       0
  6255.8     .15       0  7577.3     .11       0  7714.3     .17       0
Bank Sta=4932.6,5059.8
XS Rating Curve= 0 ,0
Exp/Cntr=0.3,0.1

Type RM Length L Ch R = 1 ,1000    ,503,503,503
BEGIN DESCRIPTION:
Crystal Creek 054 2.0
END DESCRIPTION:
XS GIS Cut Line= 3
      3883736.22     10041520.11      3879531.16     10043576.84
      3880317.86      10046761.1
#Sta/Elev= 30
   318.9  111.96   490.7  109.04   625.8   95.36   648.3   84.87  1014.1   77.86
  1880.6   76.99  2381.5   63.89  2561.6    69.9  2876.7   67.15  2921.8   73.59
    3011   65.87  3084.9   72.91  3243.2   70.92  3332.1   71.96  4191.7   75.17
  4363.2   71.15  4872.2   74.76  4880.1   74.86  5005.1   59.43  5024.2   59.43
  5055.9   74.72  5146.5   77.94  5362.1   76.89  5635.3   75.19  5755.3   78.45
  6254.4   77.28  7671.2    79.9  7919.6   91.76  8150.7  112.88    8280  114.57
#Mann= 16 ,-1 , 0
   318.9     .17       0  1014.1     .15       0  3243.2     .17       0
  3332.1     .15       0  4191.7     .17       0  4363.2     .15       0
  4872.2     .17       0  4880.1     .03       0  5055.9     .15       0
  5146.5     .17       0  5362.1     .15       0  5635.3     .17       0
  5755.3     .11       0  6254.4     .15       0  7919.6     .11       0
  8150.7     .15       0
Bank Sta=4880.1,5055.9
XS Rating Curve= 0 ,0
Exp/Cntr=0.3,0.1

Type RM Length L Ch R = 1 ,497     ,0,0,0
BEGIN DESCRIPTION:
Crystal Creek 054 1.0
END DESCRIPTION:
XS GIS Cut Line= 3
      3883725.42     10041411.58      3879078.23     10043536.84
      3879764.88     10046880.36
#Sta/Elev= 30
  -110.1  111.19    97.4  110.56   371.1   81.01   535.7   76.18  2128.1   67.27
  2354.8   69.42  2795.8   74.03    2906   72.91  2941.1   60.62  2950.7   60.17
  2988.1   66.26  3000.1   58.71  3000.6   58.21  3020.2   58.71  3072.6   69.12
    3417   75.62  4219.7   67.89  4868.5   77.39  5004.7   60.28  5034.9   64.48
  5055.4   77.67  5122.1    71.8  5300.4   82.55  5669.6   81.59    5897    79.7
  6276.9   79.04  6489.9   77.09  7571.5   80.27  7964.8   80.92  8413.3  113.33
#Mann= 16 ,-1 , 0
  -110.1     .17       0   535.7     .15       0  2128.1     .17       0
  2354.8     .15       0  2795.8     .17       0  2941.1     .11       0
  2950.7     .15       0  3000.1     .12       0  3020.2     .15       0
  4868.5     .03       0  5055.4     .17       0  5669.6     .11       0
    5897     .17       0  6276.9     .15       0  6489.9     .11       0
  7571.5     .15       0
Bank Sta=4868.5,5055.4
XS Rating Curve= 0 ,0
Exp/Cntr=0.3,0.1

Chan Stop Cuts=-1
Use User Specified Reach Order=0
Composite Channel Slope=5

--- Crystal Creek 054.g10 (geometry) ---

Geom Title=Existing Conditions
Program Version=4.10

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
River Reach=Crystal Creek 05,Reach-1

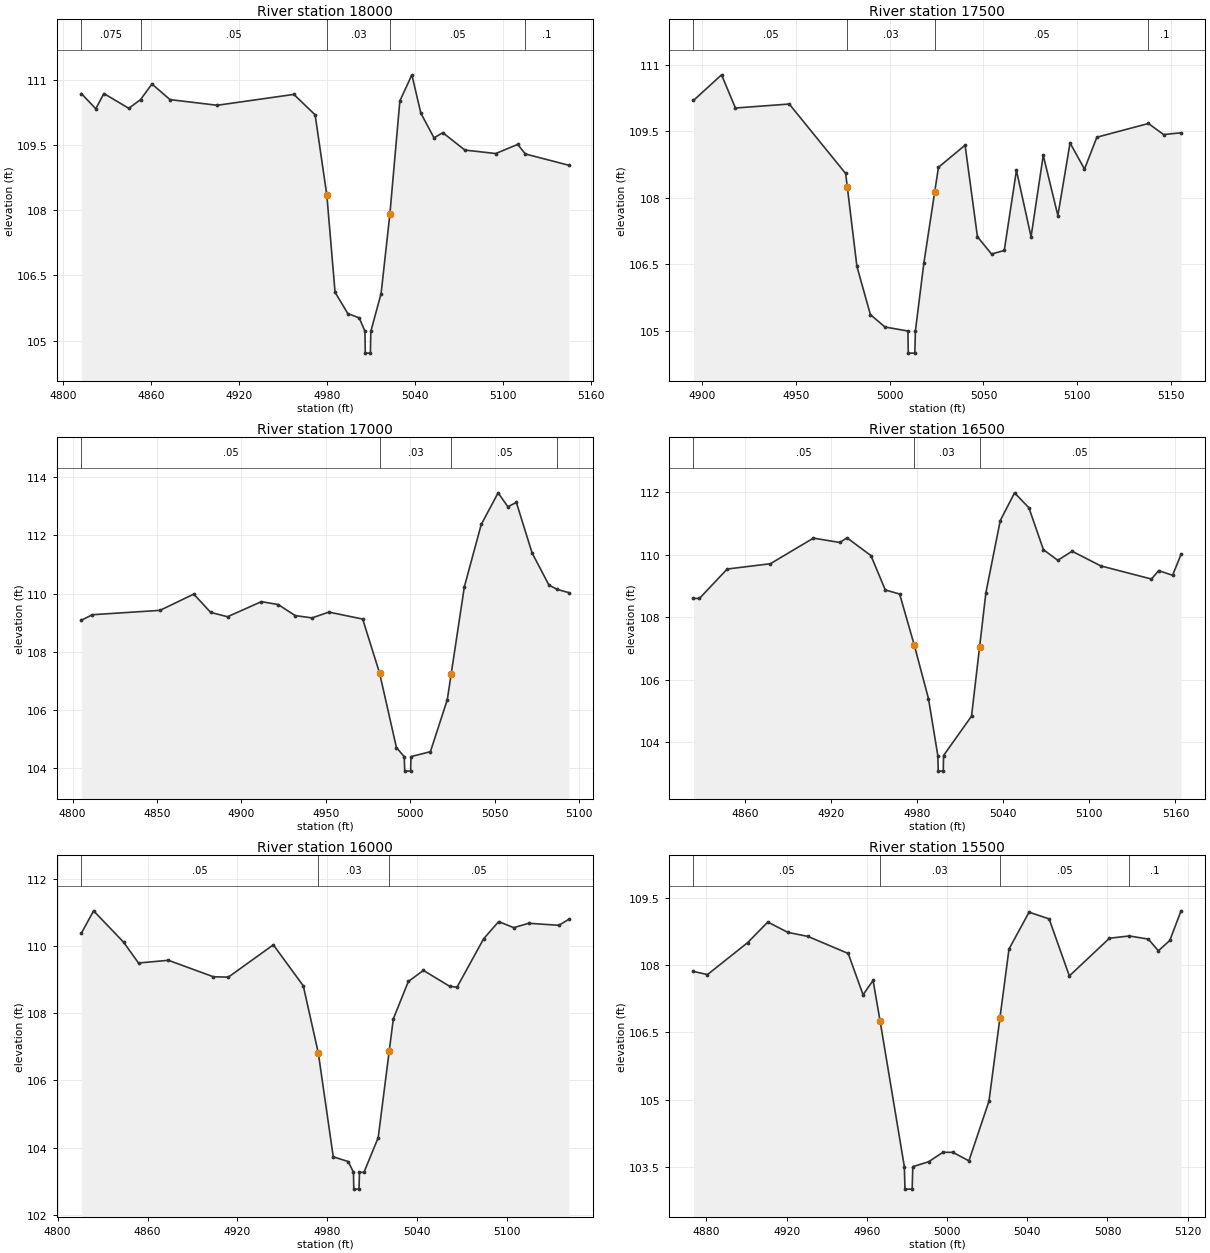
Type RM Length L Ch R = 1 ,18000   ,500,500,500
BEGIN DESCRIPTION:
Crystal Creek 054 36.0
END DESCRIPTION:
XS GIS Cut Line= 3
      3890024.53     10048561.47      3890193.08     10048643.85
      3890313.84     10048724.11
#Sta/Elev= 30
  4812.4  110.68  4822.3  110.33  4827.8  110.68  4844.8  110.34  4852.8  110.54
  4860.6   110.9  4872.9  110.54  4905.1  110.41  4957.4  110.66  4971.9  110.19
  4979.9  108.34  4985.5  106.11  4994.2  105.62    5002  105.52  5005.9  105.21
  5006.1  104.71  5009.6  104.71  5009.9  105.21  5016.9  106.08  5022.9  107.91
  5029.7  110.51  5037.9  111.11    5044  110.23    5053  109.66    5059  109.78
    5074  109.38  5095.1   109.3  5110.1  109.51  5115.3  109.29    5145  109.03
#Mann= 5 ,-1 , 0
  4812.4    .075       0  4852.8     .05       0  4979.9     .03       0
  5022.9     .05       0  5115.3      .1       0
Bank Sta=4979.9,5022.9
XS Rating Curve= 0 ,0
Exp/Cntr=0.3,0.1

Type RM Length L Ch R = 1 ,17500   ,500,500,500
BEGIN DESCRIPTION:
Crystal Creek 054 35.0
END DESCRIPTION:
XS GIS Cut Line= 3
      3889805.36     10048932.37      3889863.24     10049019.62
       3889963.7     10049138.18
#Sta/Elev= 30
  4895.3   110.2  4910.3  110.78  4917.7  110.03  4946.4  110.12  4976.5  108.55
 4977.35 108.253  4982.5  106.45  4989.7  105.36  4997.5  105.08  5009.7  104.99
  5009.9  104.49  5013.4  104.49  5013.7  104.99  5018.2  106.52    5024 108.134
    5026  108.69  5040.2  109.19  5046.8  107.12  5054.3  106.73  5061.1  106.81
  5067.6  108.62  5075.4  107.12  5081.9  108.96  5089.7   107.6  5096.2  109.24
  5103.9  108.65  5110.5  109.37    5138  109.68  5146.1  109.43  5155.4  109.47
#Mann= 4 ,-1 , 0
  4895.3     .05       0 4977.35     .03       0    5024     .05       0
    5138      .1       0
Bank Sta=4977.35,5024
XS Rating Curve= 0 ,0
Exp/Cntr=0.3,0.1

Type RM Length L Ch R = 1 ,17000   ,500,500,500
BEGIN DESCRIPTION:
Crystal Creek 054 34.0
END DESCRIPTION:
XS GIS Cut Line= 3
      3889422.02     10048964.52      3889427.79     10049159.23
      3889435.91     10049252.78
#Sta/Elev= 30
  4805.2  109.08  4811.8  109.27  4851.8  109.42  4871.8  109.98  4881.8  109.35
  4891.8   109.2  4911.8  109.72  4921.8  109.62  4931.8  109.24  4941.8  109.16
  4951.8  109.36  4971.8  109.12  4981.8  107.26  4991.8  104.69  4996.4  104.38
  4996.7  103.88  5000.2  103.88  5000.4  104.38  5011.9  104.55  5021.9  106.34
 5024.24 107.241    5032  110.23    5042  112.38    5052  113.47  5057.8  112.99
  5062.8  113.14  5072.1   111.4  5082.1  110.29  5087.1  110.14  5093.9  110.03
#Mann= 4 ,-1 , 0
  4805.2     .05       0  4981.8     .03       0 5024.24     .05       0
  5087.1      .1       0
Bank Sta=4981.8,5024.24
XS Rating Curve= 0 ,0
Exp/Cntr=0.3,0.1

Type RM Length L Ch R = 1 ,16500   ,500,500,500
BEGIN DESCRIPTION:
Crystal Creek 054 33.0
END DESCRIPTION:
XS GIS Cut Line= 3
      3888939.38     10048957.61      3888928.47     10049133.17
      3888922.05     10049296.95
#Sta/Elev= 30
  4824.1   108.6  4828.3   108.6  4847.6  109.54  4877.7  109.71  4907.7  110.53
  4926.1  110.39  4931.1  110.54  4947.8  109.97  4957.8  108.87  4967.8  108.74
  4977.9  107.12  4987.9  105.39  4994.4  103.57  4994.7  103.07  4998.2  103.07
  4998.4  103.57  5017.9  104.83 5023.47  107.03  5027.9  108.78  5037.9  111.09
  5047.9  111.98  5057.9   111.5    5068  110.16    5078  109.82    5088  110.11
    5108  109.64  5143.3  109.22  5148.3  109.49    5158  109.34  5163.9  110.01
#Mann= 3 , 0 , 0
  4824.1     .05       0  4977.9     .03       0 5023.47     .05       0
Bank Sta=4977.9,5023.47
XS Rating Curve= 0 ,0
Exp/Cntr=0.3,0.1

Type RM Length L Ch R = 1 ,16000   ,500,500,500
BEGIN DESCRIPTION:
Crystal Creek 054 32.0
END DESCRIPTION:
XS GIS Cut Line= 3
      3888428.96     10048922.91      3888429.15     10049107.11
      3888415.23     10049247.72
#Sta/Elev= 30
  4815.8  110.37    4824  111.04    4844  110.11    4854  109.49    4874  109.57
    4904  109.08    4914  109.07    4944  110.03    4964  108.81    4974  106.82
    4984  103.73    4994  103.59  4997.5  103.27  4997.7  102.77  5001.2  102.77
  5001.5  103.27  5004.5  103.27    5014   104.3 5021.37 106.876  5024.1  107.83
  5034.1  108.94  5044.2  109.27  5061.6   108.8  5066.6  108.77  5084.4  110.21
  5094.4  110.72  5104.5  110.54  5114.5  110.67  5134.6  110.61  5141.3  110.79
#Mann= 3 , 0 , 0
  4815.8     .05       0    4974     .03       0 5021.37     .05       0
Bank Sta=4974,5021.37
XS Rating Curve= 0 ,0
Exp/Cntr=0.3,0.1

Type RM Length L Ch R = 1 ,15500   ,500,500,500
BEGIN DESCRIPTION:
Crystal Creek 054 31.0
END DESCRIPTION:
XS GIS Cut Line= 3
      3887939.38      10048954.1      3887929.88     10049080.24
      3887922.05     10049196.68
#Sta/Elev= 30
  4873.5  107.86  4880.5  107.79  4900.5   108.5  4910.6  108.96  4920.6  108.73
  4930.6  108.64  4950.7  108.26  4958.1  107.34  4963.1  107.66 4966.62 106.748
  4978.7  103.51    4979  103.01  4982.6  103.01  4982.9  103.51  4990.8  103.62
  4997.9  103.83  5002.9  103.83  5010.9  103.64  5020.9  104.97 5026.34 106.814
  5030.9  108.36  5040.9  109.18  5050.9  109.03    5061  107.76    5081   108.6
  5090.9  108.65  5100.4  108.58  5105.4  108.32  5111.1  108.55  5116.7  109.21
#Mann= 4 ,-1 , 0
  4873.5     .05       0 4966.62     .03       0 5026.34     .05       0
  5090.9      .1       0
Bank Sta=4966.62,5026.34
XS Rating Curve= 0 ,0
Exp/Cntr=0.3,0.1

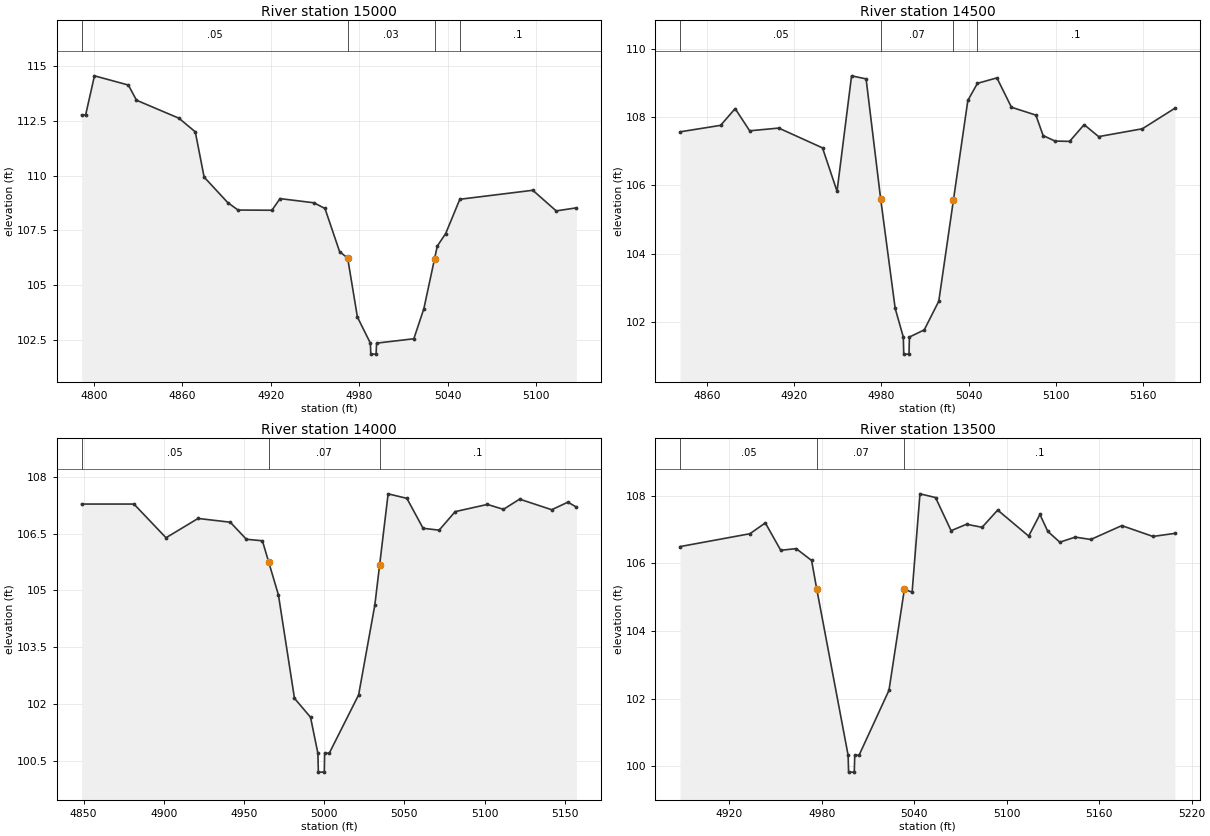
Type RM Length L Ch R = 1 ,15000   ,500,500,500
BEGIN DESCRIPTION:
Crystal Creek 054 30.0
END DESCRIPTION:
XS GIS Cut Line= 3
      3887517.85     10048861.08      3887430.78      10049050.3
      3887367.85     10049161.08
#Sta/Elev= 30
  4791.7  112.76  4794.4  112.76  4800.4  114.54  4823.4  114.12  4828.9  113.43
  4857.7  112.61  4868.8  111.99  4874.8  109.93  4890.8  108.77  4897.8  108.43
  4920.8  108.42  4926.3  108.95  4949.3  108.76  4956.8   108.5  4966.7  106.54
  4972.2  106.24  4978.8  103.56  4987.6  102.37  4987.9  101.87  4991.5  101.87
  4991.8  102.37  5017.1  102.57  5023.9  103.94 5031.12 106.201    5033  106.79
  5038.7  107.36  5048.3  108.92  5097.8  109.33  5113.7  108.39  5127.4  108.53
#Mann= 4 ,-1 , 0
  4791.7     .05       0  4972.2     .03       0 5031.12     .05       0
  5048.3      .1       0
Bank Sta=4972.2,5031.12
XS Rating Curve= 0 ,0
Exp/Cntr=0.3,0.1

Type RM Length L Ch R = 1 ,14500   ,500,500,500
BEGIN DESCRIPTION:
Crystal Creek 054 29.0
END DESCRIPTION:
XS GIS Cut Line= 3
      3887515.76     10048613.86      3887357.35     10048608.54
      3887175.52     10048603.44
#Sta/Elev= 30
  4841.5  107.57  4869.4  107.76  4879.4  108.25  4889.4   107.6  4909.4  107.68
  4939.5   107.1  4949.5  105.83  4959.5  109.21  4969.5  109.12  4979.5  105.61
  4989.5   102.4  4995.1  101.56  4995.4  101.06    4999  101.06  4999.3  101.56
  5009.5  101.77  5019.5  102.61 5029.59 105.576  5039.5  108.49  5046.1  108.99
  5059.5  109.15  5069.5  108.29  5086.3  108.06  5091.3  107.46  5099.5   107.3
  5109.5  107.29  5119.5  107.78  5129.5  107.43  5159.6  107.66  5181.9  108.26
#Mann= 4 ,-1 , 0
  4841.5     .05       0  4979.5     .07       0 5029.59     .05       0
  5046.1      .1       0
Bank Sta=4979.5,5029.59
XS Rating Curve= 0 ,0
Exp/Cntr=0.3,0.1

Type RM Length L Ch R = 1 ,14000   ,500,500,500
BEGIN DESCRIPTION:
Crystal Creek 054 28.0
END DESCRIPTION:
XS GIS Cut Line= 3
      3887540.49     10048112.07      3887389.31     10048109.56
      3887232.52     10048096.87
#Sta/Elev= 30
  4848.8  107.28  4881.4  107.28  4901.4  106.39  4921.4   106.9  4941.5   106.8
  4951.5  106.35  4961.5  106.31 4965.44 105.747  4971.5  104.88  4981.5  102.15
  4991.5  101.65  4996.1   100.7  4996.4   100.2  5000.1   100.2  5000.3   100.7
  5003.2   100.7  5021.5  102.24  5031.6  104.61 5034.59 105.669  5039.9  107.55
  5051.6  107.43  5061.7  106.64  5071.7  106.59  5081.7  107.08  5101.8  107.27
  5111.8  107.14  5121.9  107.41  5141.9  107.13    5152  107.33  5157.3   107.2
#Mann= 3 , 0 , 0
  4848.8     .05       0 4965.44     .07       0 5034.59      .1       0
Bank Sta=4965.44,5034.59
XS Rating Curve= 0 ,0
Exp/Cntr=0.3,0.1

Type RM Length L Ch R = 1 ,13500   ,737,737,737
BEGIN DESCRIPTION:
Crystal Creek 054 27.0
END DESCRIPTION:
XS GIS Cut Line= 3
      3887533.12     10047606.92      3887421.28     10047610.59
      3887213.72     10047586.09
#Sta/Elev= 30
  4888.1   106.5  4933.4  106.88  4943.4   107.2  4953.4  106.39  4963.4  106.44
  4973.4  106.09 4976.78 105.238  4997.1  100.33  4997.4   99.83  5001.1   99.83
  5001.4  100.33  5004.2  100.33  5023.6  102.25  5033.6  105.24  5038.6  105.15
  5043.7  108.06  5053.8  107.95  5063.9  106.97  5073.9  107.16    5084  107.07
  5094.1  107.58  5114.2  106.81  5121.5  107.45  5126.6  106.95  5134.4  106.63
  5144.4  106.78  5154.5  106.71  5174.6  107.12  5194.8   106.8    5209  106.89
#Mann= 3 , 0 , 0
  4888.1     .05       0 4976.78     .07       0  5033.6      .1       0
Bank Sta=4976.78,5033.6
XS Rating Curve= 0 ,0
Exp/Cntr=0.3,0.1