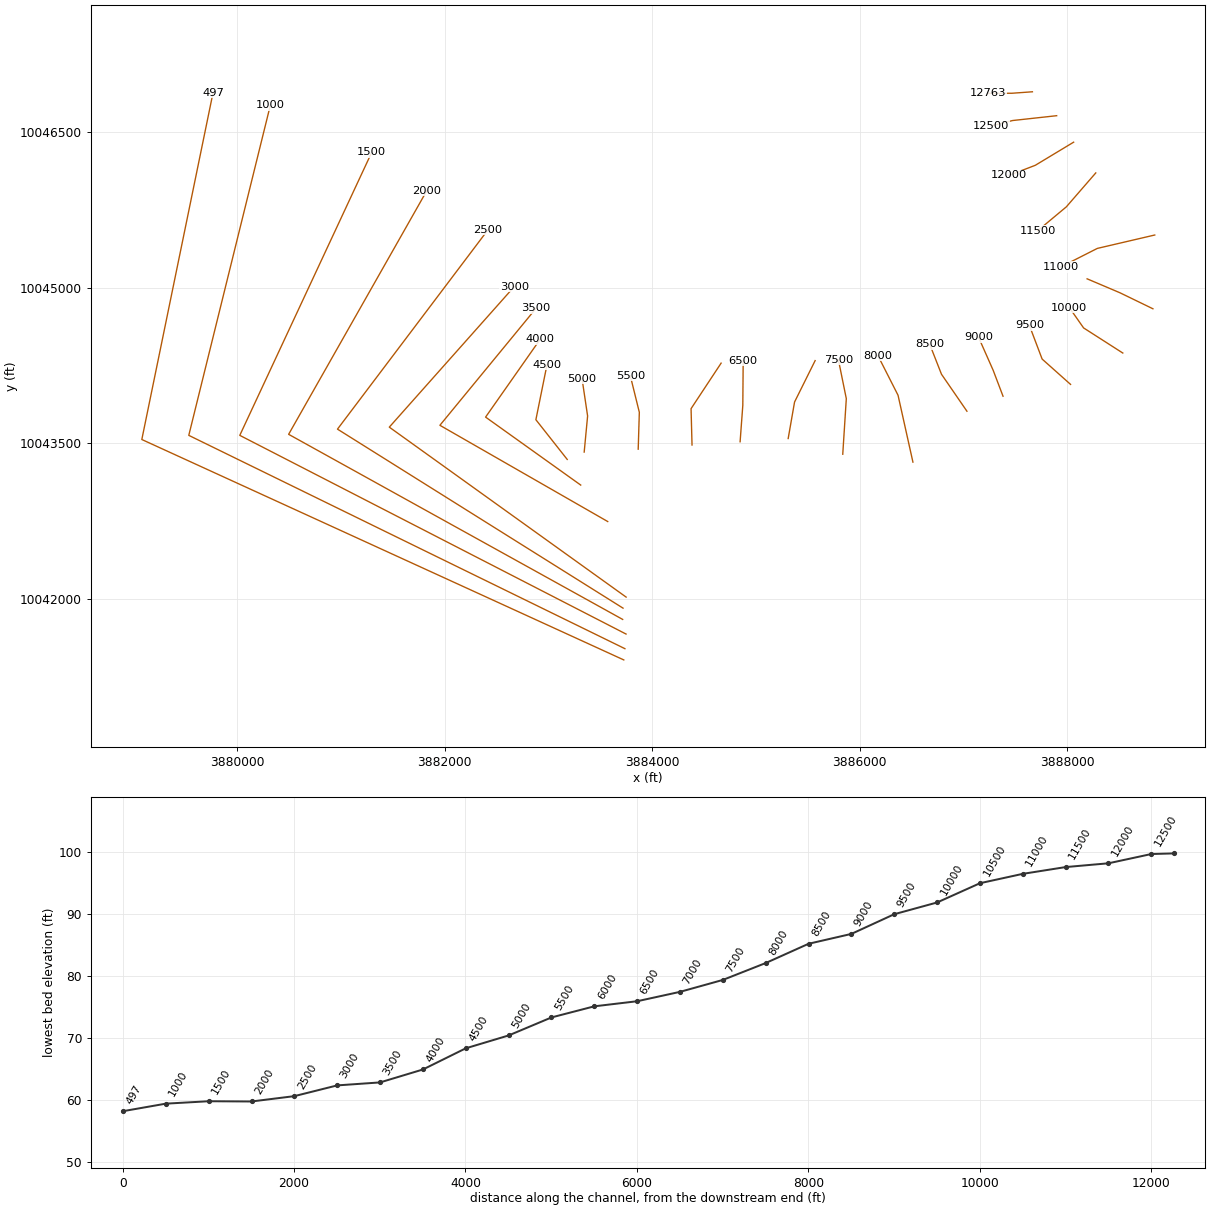
HEC-RAS study Crystal Creek 054.prj: Crystal Creek 054 Base Level Engineering

--- Crystal Creek 054.g10 (geometry) --- (continued)

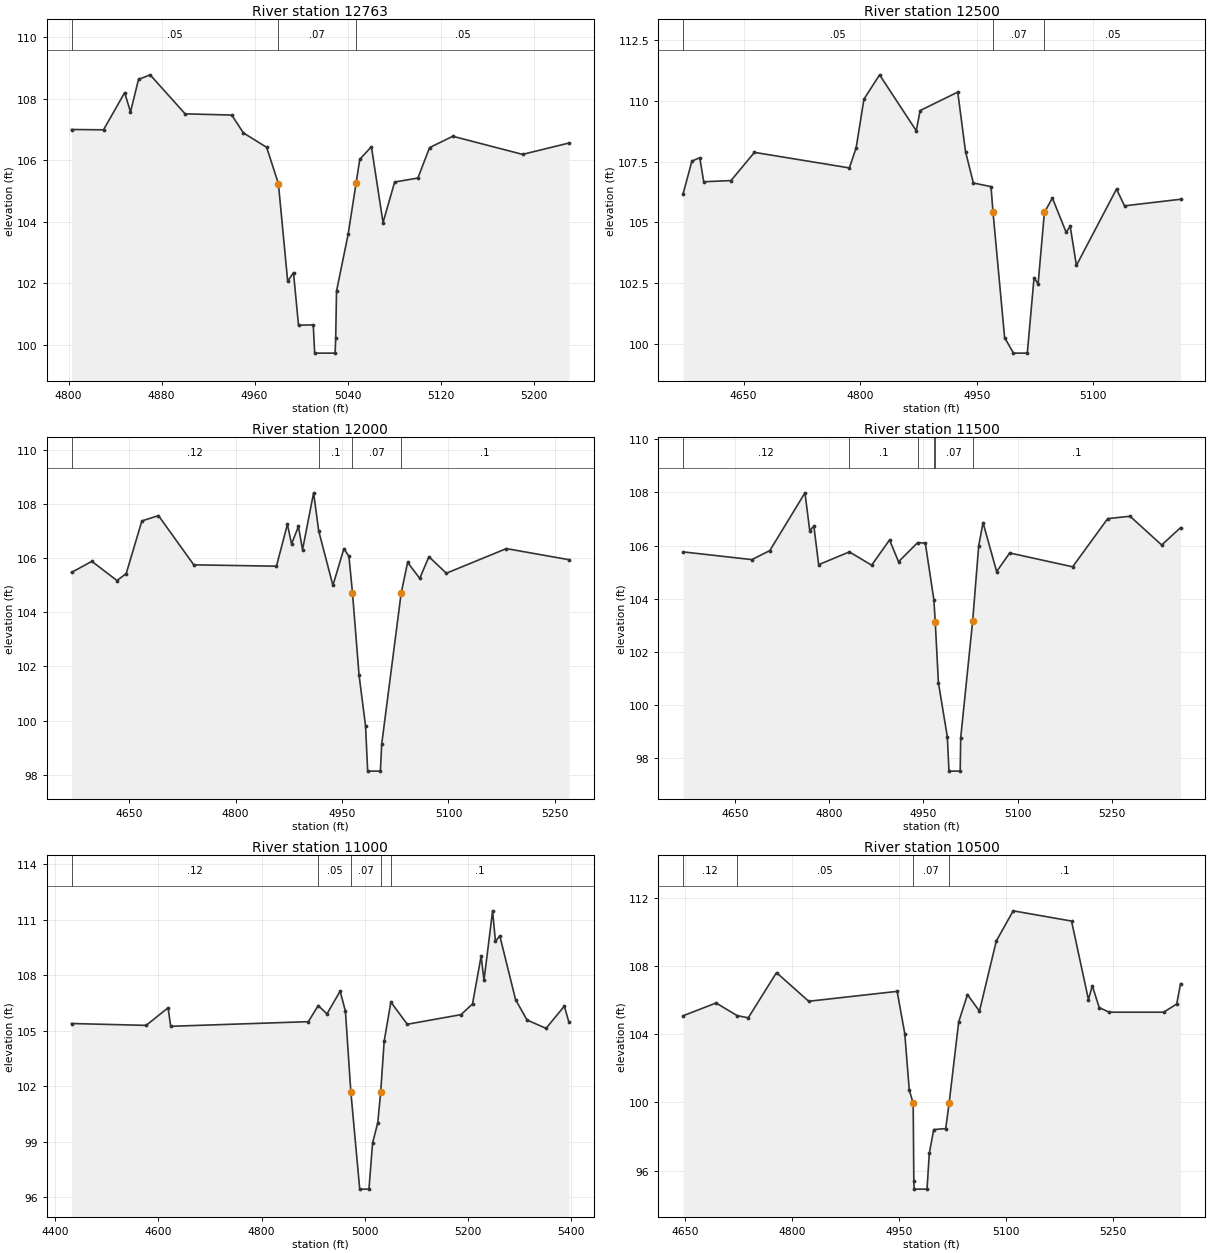
Type RM Length L Ch R = 1 ,12763   ,263,263,263
BEGIN DESCRIPTION:
Crystal Creek 054 26.0
END DESCRIPTION:
XS GIS Cut Line= 3
      3887665.27     10046889.56      3887468.37     10046875.47
      3887237.97     10046874.28
#Sta/Elev= 30
  4802.6     107  4830.1  106.99  4848.3   108.2  4853.3  107.57  4860.2  108.63
  4870.2  108.78  4900.3  107.51  4940.4  107.47  4950.4  106.89  4970.4  106.42
  4980.5  105.24  4988.5  102.06  4993.5  102.34  4997.8  100.63  5010.5  100.64
  5011.7   99.72  5029.3   99.72  5029.8  100.22  5030.5  101.74  5040.5  103.59
 5047.39 105.271  5050.5  106.03  5060.5  106.44  5070.5  103.97  5080.5  105.29
  5100.5  105.42  5110.5  106.41  5130.5  106.78  5190.5  106.19  5230.4  106.56
#Mann= 3 , 0 , 0
  4802.6     .05       0  4980.5     .07       0 5047.39     .05       0
Bank Sta=4980.5,5047.39
XS Rating Curve= 0 ,0
Exp/Cntr=0.3,0.1

Type RM Length L Ch R = 1 ,12500   ,500,500,500
BEGIN DESCRIPTION:
Crystal Creek 054 25.0
END DESCRIPTION:
XS GIS Cut Line= 3
      3887899.12     10046658.97      3887473.96     10046612.37
      3887267.85     10046561.07
#Sta/Elev= 30
  4572.3  106.18  4583.6  107.52  4593.7  107.66  4598.8  106.67  4633.9  106.72
  4664.1  107.88  4786.2  107.24  4794.9  108.06    4805  110.07  4825.1  111.07
  4872.3  108.77  4877.3   109.6  4925.7  110.36  4935.7  107.91  4945.8  106.62
  4968.5  106.47 4971.08 105.414    4986  100.26  4997.4   99.62  5015.2   99.62
  5023.9  102.73  5029.1  102.46  5037.2  105.41  5047.5     106  5065.2  104.59
  5070.4  104.84  5078.4  103.23    5130  106.37  5140.3  105.68  5212.4  105.95
#Mann= 3 , 0 , 0
  4572.3     .05       0 4971.08     .07       0  5037.2     .05       0
Bank Sta=4971.08,5037.2
XS Rating Curve= 0 ,0
Exp/Cntr=0.3,0.1

Type RM Length L Ch R = 1 ,12000   ,500,500,500
BEGIN DESCRIPTION:
Crystal Creek 054 24.0
END DESCRIPTION:
XS GIS Cut Line= 3
      3888062.72     10046403.61      3887693.36     10046180.92
      3887441.57       10046084.
#Sta/Elev= 30
  4568.7  105.47  4597.3  105.88  4632.8  105.17  4645.8  105.43  4667.8  107.37
  4691.2  107.57    4741  105.75  4857.5   105.7    4873  107.25  4878.8  106.52
  4888.5  107.17  4894.3  106.31  4909.9  108.41  4917.1     107  4937.1  104.99
  4952.6  106.35  4959.7  106.06 4964.68  104.72  4973.9  101.69  4983.1    99.8
  4986.1   98.13    5004   98.13  5005.9   99.13 5033.26 104.697  5042.4  105.84
  5059.5  105.25  5072.4  106.05    5097  105.44  5181.6  106.35  5269.8  105.94
#Mann= 4 ,-1 , 0
  4568.7     .12       0  4917.1      .1       0 4964.68     .07       0
 5033.26      .1       0
Bank Sta=4964.68,5033.26
XS Rating Curve= 0 ,0
Exp/Cntr=0.3,0.1

Type RM Length L Ch R = 1 ,11500   ,500,500,500
BEGIN DESCRIPTION:
Crystal Creek 054 23.0
END DESCRIPTION:
XS GIS Cut Line= 3
      3888276.14     10046107.29       3887992.4      10045780.2
      3887716.03     10045549.82
#Sta/Elev= 30
    4567  105.76  4676.7  105.47  4705.2  105.81  4761.2  107.98  4768.8  106.56
  4775.4  106.73    4783  105.28    4832  105.76  4867.5  105.26    4896  106.21
  4910.3  105.39  4940.8  106.11    4953  106.09  4966.6  103.97  4968.8 103.143
  4973.9  100.84  4988.1   98.81  4990.7   97.52  5008.6   97.52  5009.4   98.77
 5028.42  103.15  5038.1  105.99    5045  106.86  5066.7  105.02  5087.5  105.72
  5187.8   105.2  5243.7  107.01  5279.3   107.1  5329.7  106.02  5359.8  106.67
#Mann= 6 ,-1 , 0
    4567     .12       0    4832      .1       0  4940.8     .05       0
  4966.6      .1       0  4968.8     .07       0 5028.42      .1       0
Bank Sta=4968.8,5028.42
XS Rating Curve= 0 ,0
Exp/Cntr=0.3,0.1

Type RM Length L Ch R = 1 ,11000   ,500,500,500
BEGIN DESCRIPTION:
Crystal Creek 054 22.0
END DESCRIPTION:
XS GIS Cut Line= 3
      3888845.09      10045508.6      3888291.44     10045379.49
      3887938.26     10045200.39
#Sta/Elev= 30
  4431.5  105.38  4576.1  105.28  4618.7  106.23  4623.8  105.23  4890.7  105.48
  4909.8  106.35  4926.8   105.9  4952.3  107.13  4962.6  106.04 4973.06 101.688
  4990.3   96.43  5008.2   96.43  5015.2   98.92  5025.3  100.02  5030.9  101.66
  5037.7  104.42  5050.7  106.54  5082.5  105.34  5186.7  105.86    5209  106.44
  5225.7  109.02  5231.3  107.71  5247.9  111.47  5253.5  109.82  5261.9  110.12
  5292.5  106.67  5314.7  105.57  5351.6  105.12  5387.1  106.32    5396  105.44
#Mann= 5 ,-1 , 0
  4431.5     .12       0  4909.8     .05       0 4973.06     .07       0
  5030.9     .05       0  5050.7      .1       0
Bank Sta=4973.06,5030.9
XS Rating Curve= 0 ,0
Exp/Cntr=0.3,0.1

Type RM Length L Ch R = 1 ,10500   ,500,500,500
BEGIN DESCRIPTION:
Crystal Creek 054 21.0
END DESCRIPTION:
XS GIS Cut Line= 3
      3888827.36     10044797.33      3888509.88     10044951.43
      3888192.91     10045086.11
#Sta/Elev= 30
  4647.1  105.08  4693.3  105.83  4722.8  105.09  4738.4  104.96    4778  107.61
  4823.1  105.93  4947.1  106.51  4957.8  104.04  4964.1  100.73  4969.6   99.95
  4970.5   95.42    4971   94.92    4989   94.92  4992.2   97.02  4998.4   98.41
  5015.2   98.47 5019.95  99.944  5033.4  104.72  5045.7  106.32  5062.5  105.35
  5086.1  109.46  5109.8  111.23  5191.6  110.63  5215.3  106.03  5220.7  106.84
  5230.4  105.56  5244.3  105.29  5320.7  105.29    5339  105.77  5344.4  106.96
#Mann= 4 ,-1 , 0
  4647.1     .12       0  4722.8     .05       0  4969.6     .07       0
 5019.95      .1       0
Bank Sta=4969.6,5019.95
XS Rating Curve= 0 ,0
Exp/Cntr=0.3,0.1

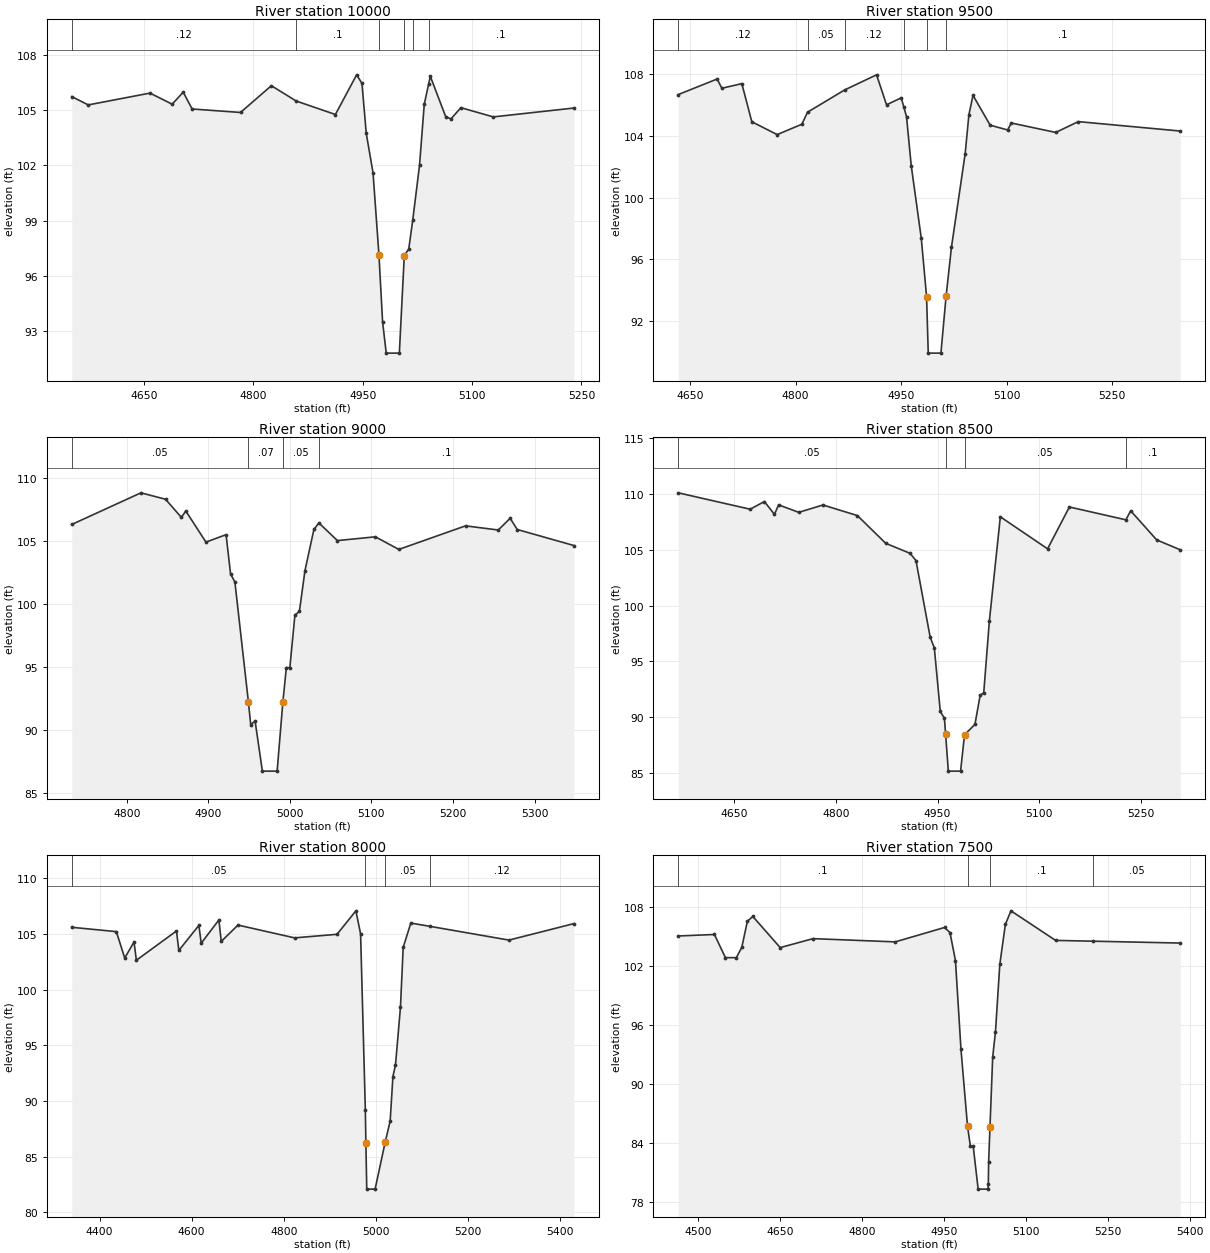
Type RM Length L Ch R = 1 ,10000   ,500,500,500
BEGIN DESCRIPTION:
Crystal Creek 054 20.0
END DESCRIPTION:
XS GIS Cut Line= 3
       3888536.9     10044370.59      3888158.67     10044612.92
      3888021.24     10044809.19
#Sta/Elev= 30
  4550.8  105.72  4573.4  105.27  4658.1  105.91  4688.5  105.31  4703.7  105.96
  4715.9  105.05  4782.3  104.86  4824.6  106.31  4858.7  105.48  4912.5  104.75
  4941.6   106.9  4948.9  106.44  4954.8  103.73  4964.1  101.59 4972.24   97.13
  4977.2   93.52  4982.2   91.82  5000.2   91.82    5007   97.11  5013.1   97.46
  5018.6   99.03  5027.9     102  5034.4  105.31  5040.4   106.4  5042.7  106.82
  5063.7  104.64    5071  104.51  5084.6  105.12  5129.1  104.62  5239.6   105.1
#Mann= 6 ,-1 , 0
  4550.8     .12       0  4858.7      .1       0 4972.24     .07       0
    5007      .1       0  5018.6     .12       0  5040.4      .1       0
Bank Sta=4972.24,5007
XS Rating Curve= 0 ,0
Exp/Cntr=0.3,0.1

Type RM Length L Ch R = 1 ,9500    ,500,500,500
BEGIN DESCRIPTION:
Crystal Creek 054 19.0
END DESCRIPTION:
XS GIS Cut Line= 3
      3888033.07     10044068.32      3887759.09     10044312.35
      3887636.22     10044636.65
#Sta/Elev= 30
  4633.1  106.67  4688.4  107.68  4695.1  107.08  4723.5  107.38  4737.7  104.91
  4773.7  104.08  4808.8  104.75  4816.9  105.53  4869.6  106.97    4915  107.95
  4929.2  106.01  4950.1  106.46  4953.6  105.89  4957.6  105.24  4964.3  102.07
  4978.6   97.36  4986.1   93.59  4988.5   89.93  5006.5   89.93 5013.85  93.609
  5021.5   96.79    5041  102.85  5046.3  105.37  5052.1  106.62  5076.5  104.69
  5101.3  104.38  5106.6  104.83  5169.7  104.22  5201.8  104.92  5346.8  104.31
#Mann= 6 ,-1 , 0
  4633.1     .12       0  4816.9     .05       0  4869.6     .12       0
  4953.6     .05       0  4986.1     .07       0 5013.85      .1       0
Bank Sta=4986.1,5013.85
XS Rating Curve= 0 ,0
Exp/Cntr=0.3,0.1

Type RM Length L Ch R = 1 ,9000    ,500,500,500
BEGIN DESCRIPTION:
Crystal Creek 054 18.0
END DESCRIPTION:
XS GIS Cut Line= 3
      3887381.99     10043954.16      3887287.04     10044204.13
      3887146.06     10044522.52
#Sta/Elev= 30
  4732.6  106.33  4817.4  108.84  4847.6  108.33    4867  106.89  4872.4   107.4
  4897.1  104.93  4921.8  105.52  4927.3   102.4  4932.6  101.77 4949.23  92.219
    4952   90.45  4957.4   90.73  4966.3   86.76  4984.4   86.76 4991.44  92.253
  4995.7   94.97    5000   94.97  5006.2   99.14  5011.7   99.43  5018.5  102.66
  5029.5  105.94  5035.6  106.45  5058.3  105.05  5104.8  105.35  5133.6  104.35
  5215.4  106.22  5255.5  105.89  5270.1  106.82  5278.8  105.93  5348.2  104.66
#Mann= 4 ,-1 , 0
  4732.6     .05       0 4949.23     .07       0 4991.44     .05       0
  5035.6      .1       0
Bank Sta=4949.23,4991.44
XS Rating Curve= 0 ,0
Exp/Cntr=0.3,0.1

Type RM Length L Ch R = 1 ,8500    ,500,500,500
BEGIN DESCRIPTION:
Crystal Creek 054 17.0
END DESCRIPTION:
XS GIS Cut Line= 3
      3887033.93      10043809.7      3886788.48     10044166.29
      3886675.77     10044453.57
#Sta/Elev= 30
  4567.1  110.12  4673.4  108.65  4694.3  109.34  4709.2  108.19  4715.3  109.04
  4745.1  108.37  4780.9  109.03  4831.7  108.08  4873.6  105.59  4909.4   104.7
  4918.2  104.05  4939.2   97.17  4945.3   96.22  4954.1   90.52  4960.2   89.91
 4962.02  88.454    4966   85.17  4984.1   85.17  4989.9   88.43  5005.3   89.36
    5013   91.97  5018.3    92.2  5026.6   98.63  5042.8  107.97  5112.6   105.1
  5144.8  108.85  5228.2   107.7  5235.3  108.51  5273.7   105.9  5308.6  105.01
#Mann= 4 ,-1 , 0
  4567.1     .05       0 4962.02     .07       0  4989.9     .05       0
  5228.2      .1       0
Bank Sta=4962.02,4989.9
XS Rating Curve= 0 ,0
Exp/Cntr=0.3,0.1

Type RM Length L Ch R = 1 ,8000    ,500,500,500
BEGIN DESCRIPTION:
Crystal Creek 054 16.0
END DESCRIPTION:
XS GIS Cut Line= 3
      3886513.28     10043318.81      3886369.82     10043963.44
      3886175.11     10044346.72
#Sta/Elev= 30
  4339.6   105.6  4436.4  105.21  4454.6  102.84  4474.8  104.28  4479.9  102.64
    4567  105.27  4572.1  103.52  4615.6  105.77  4620.7  104.17  4659.1  106.26
  4664.2  104.33  4700.5   105.8  4823.4  104.65  4915.6  104.97  4956.6  107.08
  4966.8  105.01  4977.1   89.21 4978.27  86.222  4980.2   82.07  4998.3   82.07
  5020.4   86.33    5031   88.17    5037   92.19  5042.6   93.23  5053.4   98.43
  5059.3  103.79  5075.9  105.98  5118.2  105.68    5289  104.45  5429.9  105.93
#Mann= 4 ,-1 , 0
  4339.6     .05       0  4977.1     .07       0  5020.4     .05       0
  5118.2     .12       0
Bank Sta=4978.27,5020.4
XS Rating Curve= 0 ,0
Exp/Cntr=0.3,0.1

Type RM Length L Ch R = 1 ,7500    ,500,500,500
BEGIN DESCRIPTION:
Crystal Creek 054 15.0
END DESCRIPTION:
XS GIS Cut Line= 3
      3885836.66     10043394.96      3885870.94     10043930.67
        3885795.     10044304.64
#Sta/Elev= 30
  4463.2  105.03  4529.4  105.18  4549.5  102.83  4569.5  102.83  4579.5  103.88
  4589.6  106.51  4599.6  107.01  4649.7  103.85  4709.8  104.76  4860.1  104.43
  4950.3  105.89  4960.3  105.37  4970.3  102.53  4980.4   93.52 4992.37   85.71
  4997.7   83.68  5002.8   83.68  5011.8   79.35  5029.9   79.35  5030.4   79.85
    5031   82.13 5033.47  85.675  5038.4   92.75  5043.5   95.31  5051.4  102.14
  5061.6   106.2  5071.8  107.58  5153.5  104.58  5222.4   104.5  5381.6  104.31
#Mann= 4 ,-1 , 0
  4463.2      .1       0 4992.37     .07       0 5033.47      .1       0
  5222.4     .05       0
Bank Sta=4992.37,5033.47
XS Rating Curve= 0 ,0
Exp/Cntr=0.3,0.1

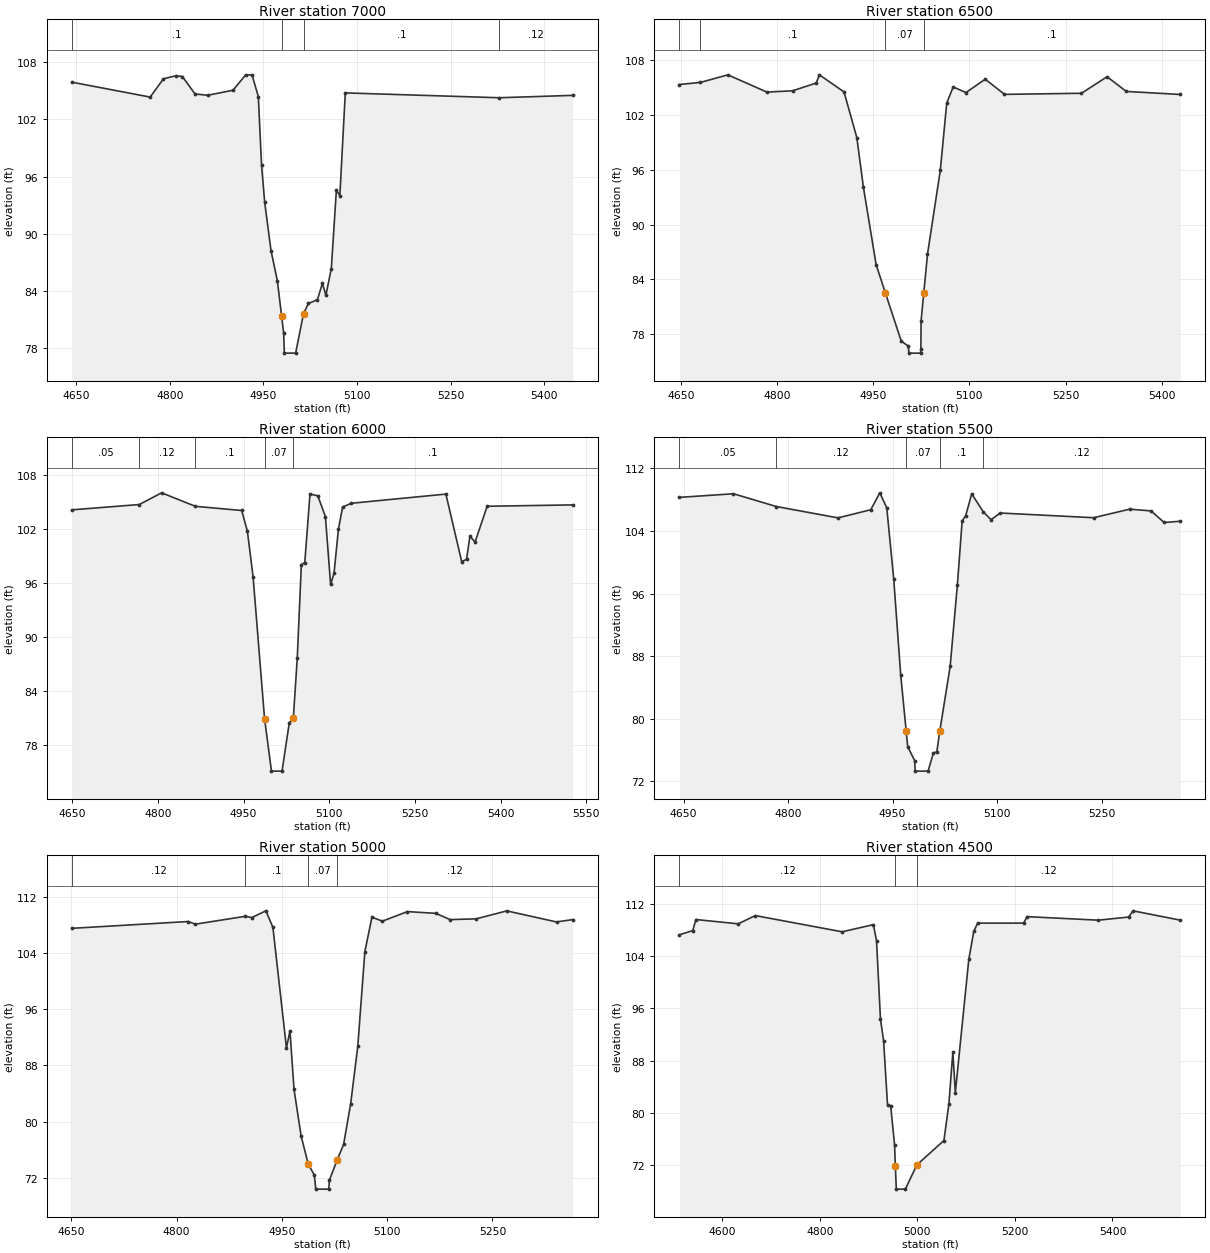
Type RM Length L Ch R = 1 ,7000    ,500,500,500
BEGIN DESCRIPTION:
Crystal Creek 054 14.0
END DESCRIPTION:
XS GIS Cut Line= 3
      3885310.48     10043546.31      3885371.98     10043898.38
      3885570.33     10044297.51
#Sta/Elev= 30
  4642.6  105.92  4768.4  104.35  4789.6  106.27  4809.9   106.6    4820  106.51
  4840.3  104.68  4860.6  104.54  4901.2  105.07  4921.5  106.69  4931.7  106.68
  4941.8   104.4  4946.9   97.24    4952   93.28  4962.1   88.21  4972.3   85.03
 4979.08  81.345  4982.4   79.54  4983.5   77.43  5001.6   77.43  5014.2   81.58
  5022.1   82.65  5036.5   83.05  5044.5   84.77  5050.1   83.51  5058.8   86.32
  5066.9   94.55  5072.5      94  5081.2  104.79    5328  104.28  5445.7  104.53
#Mann= 4 ,-1 , 0
  4642.6      .1       0 4979.08     .07       0  5014.2      .1       0
    5328     .12       0
Bank Sta=4979.08,5014.2
XS Rating Curve= 0 ,0
Exp/Cntr=0.3,0.1

Type RM Length L Ch R = 1 ,6500    ,500,500,500
BEGIN DESCRIPTION:
Crystal Creek 054 13.0
END DESCRIPTION:
XS GIS Cut Line= 3
      3884846.94     10043515.09      3884873.01     10043866.33
      3884876.59     10044295.41
#Sta/Elev= 30
  4647.8  105.33  4680.6  105.56  4723.3  106.39  4784.2   104.5  4824.3  104.64
  4861.1  105.49  4866.1  106.39  4904.5  104.52  4924.5   99.51  4934.6   94.15
  4954.6    85.6 4968.97  82.521  4993.8   77.23  5004.9   76.69  5005.6   75.92
  5023.9   75.92  5024.4   76.42  5024.7   79.45 5028.81   82.45  5034.7   86.75
  5054.7   95.94  5064.7  103.29  5074.7  105.06  5094.7  104.45  5124.8  105.91
  5154.8  104.25  5274.8  104.37  5314.8  106.18  5344.8  104.57  5429.1  104.24
#Mann= 4 ,-1 , 0
  4647.8     .05       0  4680.6      .1       0 4968.97     .07       0
 5028.81      .1       0
Bank Sta=4968.97,5028.81
XS Rating Curve= 0 ,0
Exp/Cntr=0.3,0.1

Type RM Length L Ch R = 1 ,6000    ,500,500,500
BEGIN DESCRIPTION:
Crystal Creek 054 12.0
END DESCRIPTION:
XS GIS Cut Line= 3
       3884383.4     10043483.81      3884374.04     10043834.28
      3884663.81     10044273.15
#Sta/Elev= 30
  4649.4   104.1  4767.6  104.69  4806.7  105.99  4865.9  104.49  4946.8  104.03
  4956.8  101.72  4966.8   96.64  4986.8   80.94  4998.9    75.1  5017.4    75.1
  5030.1   80.47 5037.15  80.973  5044.1   87.68  5051.2   98.02  5057.2   98.25
  5066.3  105.86    5080  105.66  5093.3  103.35  5102.4   95.82  5108.4   97.06
    5116  101.92  5123.4  104.41  5138.5  104.83  5304.1  105.85  5331.7   98.36
  5340.2    98.6  5346.2  101.18  5355.2  100.53  5376.3   104.5  5525.9  104.65
#Mann= 5 ,-1 , 0
  4649.4     .05       0  4767.6     .12       0  4865.9      .1       0
  4986.8     .07       0 5037.15      .1       0
Bank Sta=4986.8,5037.15
XS Rating Curve= 0 ,0
Exp/Cntr=0.3,0.1

Type RM Length L Ch R = 1 ,5500    ,500,500,500
BEGIN DESCRIPTION:
Crystal Creek 054 11.0
END DESCRIPTION:
XS GIS Cut Line= 3
      3883864.44     10043443.49      3883875.26     10043799.33
      3883788.04      10044151.9
#Sta/Elev= 30
    4644  108.29  4721.6  108.75  4783.1  107.12  4871.7  105.67  4918.7  106.71
  4931.7  108.87  4941.7  106.94  4951.7   97.81  4961.7   85.58 4969.49  78.468
  4971.7   76.45  4981.7   74.66  4982.5   73.31    5001   73.31  5008.5    75.6
  5013.6    75.8 5017.78  78.417  5032.7    86.7    5043   97.04  5049.9  105.28
  5055.1  105.97  5063.6  108.74  5080.2  106.45  5091.3  105.44  5104.8  106.29
  5238.7  105.69  5290.2  106.78  5321.1  106.56  5339.9  105.08  5363.2  105.24
#Mann= 5 ,-1 , 0
    4644     .05       0  4783.1     .12       0 4969.49     .07       0
 5017.78      .1       0  5080.2     .12       0
Bank Sta=4969.49,5017.78
XS Rating Curve= 0 ,0
Exp/Cntr=0.3,0.1

Type RM Length L Ch R = 1 ,5000    ,500,500,500
BEGIN DESCRIPTION:
Crystal Creek 054 10.0
END DESCRIPTION:
XS GIS Cut Line= 3
       3883343.6     10043415.75      3883376.55     10043763.49
      3883322.82     10044123.81
#Sta/Elev= 30
  4650.7   107.5  4816.8  108.47  4826.8  108.09  4897.9  109.21  4907.2  109.03
  4927.3  109.99  4937.3  107.63  4956.6   90.48  4961.6   92.92  4967.4   84.58
  4977.5   77.97  4987.5   74.01  4996.3   72.39  4998.4   70.41  5016.9   70.41
  5017.8   71.69    5029    74.6    5038   76.76  5048.1   82.57  5058.2   90.71
  5068.3  104.18  5078.4  109.09  5093.2  108.52    5129  109.88  5169.4  109.63
  5189.7  108.74  5226.8  108.85  5270.5  109.98  5341.3  108.41  5364.3  108.74
#Mann= 4 ,-1 , 0
  4650.7     .12       0  4897.9      .1       0  4987.5     .07       0
    5029     .12       0
Bank Sta=4987.5,5029
XS Rating Curve= 0 ,0
Exp/Cntr=0.3,0.1

Type RM Length L Ch R = 1 ,4500    ,500,500,500
BEGIN DESCRIPTION:
Crystal Creek 054 9.0
END DESCRIPTION:
XS GIS Cut Line= 3
      3883179.96     10043344.81      3882877.83     10043727.65
      3882984.61     10044256.18
#Sta/Elev= 30
  4512.3  107.27  4539.7   107.9    4546   109.6  4632.7  108.94  4667.9   110.2
  4845.9  107.72    4910  108.82  4916.4  106.29  4924.4   94.37  4930.8   91.04
  4938.9   81.22  4945.3    81.1  4953.3   75.14 4954.92  71.848  4956.9   68.34
  4975.4   68.34    4999   72.05  5054.5   75.78  5064.7   81.39  5072.8   89.29
  5077.9   83.11  5105.5  103.51  5115.7  107.78  5123.6  109.05  5217.7  109.05
  5225.1  110.04  5370.8   109.5  5433.2  109.98  5442.2  110.93  5539.2   109.5
#Mann= 3 , 0 , 0
  4512.3     .12       0 4954.92     .03       0    4999     .12       0
Bank Sta=4954.92,4999
XS Rating Curve= 0 ,0
Exp/Cntr=0.3,0.1

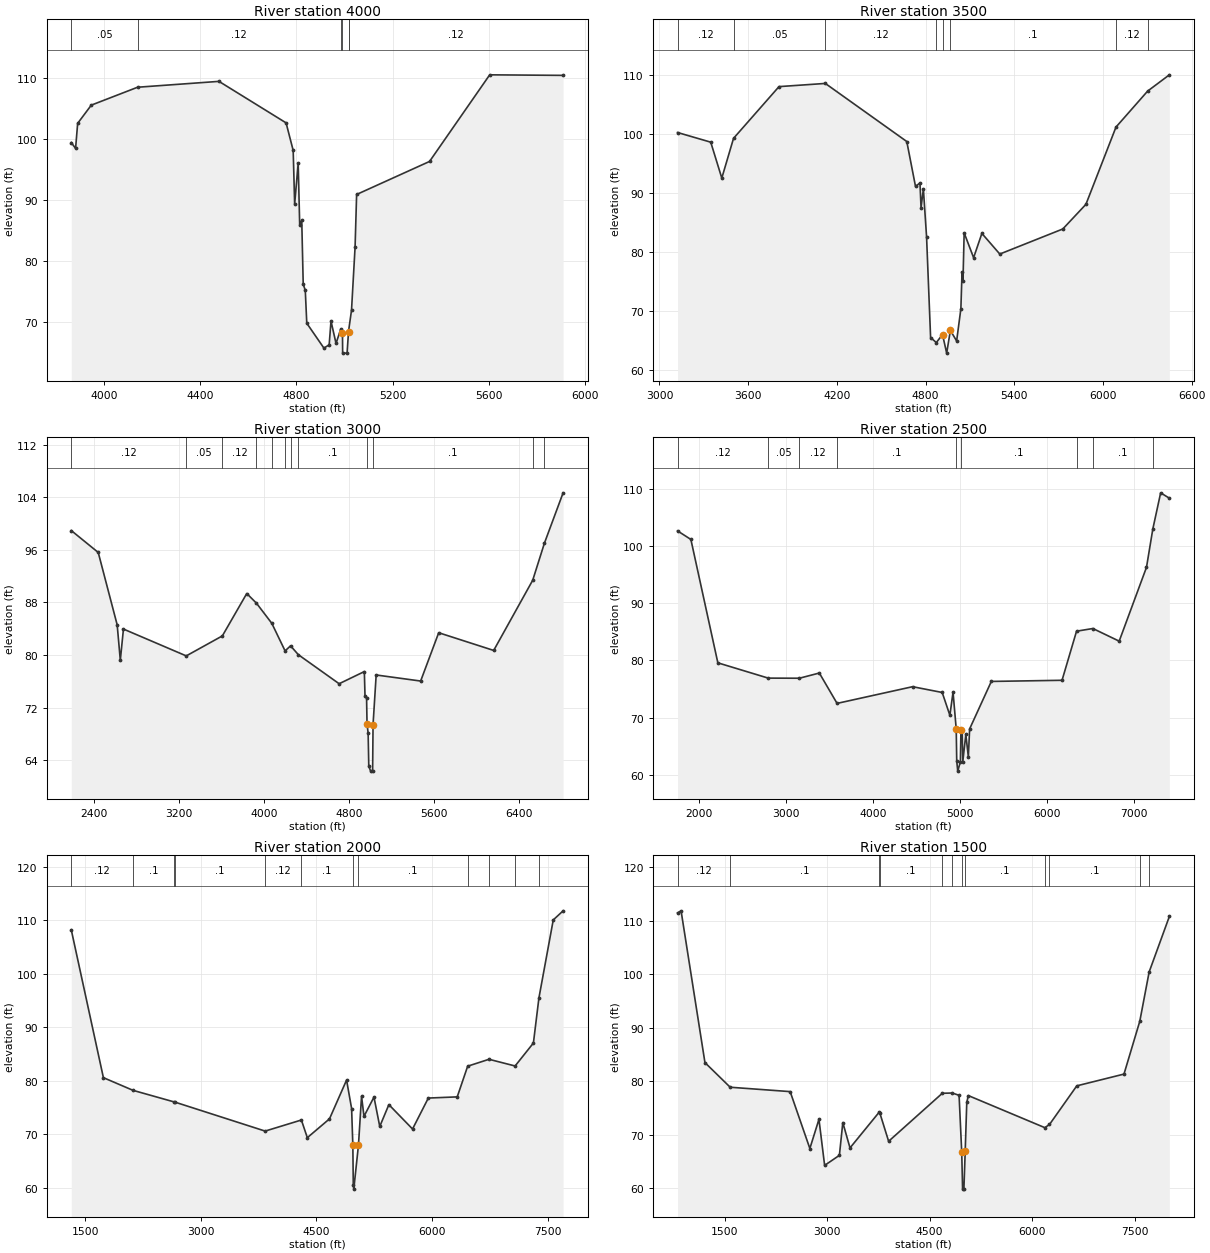
Type RM Length L Ch R = 1 ,4000    ,500,500,500
BEGIN DESCRIPTION:
Crystal Creek 054 8.0
END DESCRIPTION:
XS GIS Cut Line= 3
      3883310.14     10043097.45      3882392.87     10043752.87
      3882919.54     10044503.71
#Sta/Elev= 30
  3864.5   99.38  3882.5   98.41  3891.1  102.51  3947.7  105.49  4140.2  108.42
  4478.5  109.38  4757.5  102.59    4787   98.08  4793.1   89.31  4807.8      96
    4814   85.96  4822.6   86.63  4828.7   76.22  4837.3   75.18  4843.5   69.82
  4914.8   65.75  4936.6   66.29  4944.2   70.17  4965.1   66.52  4984.4   68.81
  4991.9   68.24  4992.6   64.93  5011.1   64.93    5017   68.46  5029.5   71.96
  5044.3   82.29  5050.7   90.88  5353.8   96.28  5603.9  110.45    5909  110.36
#Mann= 6 ,-1 , 0
  3864.5     .05       0  4140.2     .12       0  4984.4      .1       0
  4991.9     .07       0    5017      .1       0    5017     .12       0
Bank Sta=4991.9,5017
XS Rating Curve= 0 ,0
Exp/Cntr=0.3,0.1

Type RM Length L Ch R = 1 ,3500    ,500,500,500
BEGIN DESCRIPTION:
Crystal Creek 054 7.0
END DESCRIPTION:
XS GIS Cut Line= 3
      3883570.58     10042745.87      3881952.34     10043673.87
      3882880.47     10044803.16
#Sta/Elev= 30
    3122  100.26  3346.7   98.62  3421.5   92.53  3500.9   99.27  3808.4  108.04
  4121.8  108.58  4672.9   98.73  4731.9   91.12  4762.1   91.71  4769.3   87.51
  4785.1   90.69  4806.7   82.58    4834   65.49  4872.7   64.64  4914.6      66
  4942.7   62.85  4967.8    66.7  5010.1   64.91  5038.8   70.38  5046.7   76.65
  5053.1   75.14    5061   83.24  5124.9   79.03  5180.9   83.15  5302.1   79.65
  5728.3    83.9  5884.7   88.08  6088.1  101.18  6302.1  107.28  6449.2  110.04
#Mann= 8 ,-1 , 0
    3122     .12       0  3500.9     .05       0  4121.8     .12       0
  4872.7      .1       0  4914.6     .03       0  4967.8      .1       0
  6088.1     .12       0  6302.1      .1       0
Bank Sta=4914.6,4967.8
XS Rating Curve= 0 ,0
Exp/Cntr=0.3,0.1

Type RM Length L Ch R = 1 ,3000    ,500,500,500
BEGIN DESCRIPTION:
Crystal Creek 054 6.0
END DESCRIPTION:
XS GIS Cut Line= 3
      3883747.76     10042017.49      3881464.51     10043656.12
      3882669.02     10045010.75
#Sta/Elev= 30
  2189.6   98.93  2443.1    95.6  2621.2    84.6  2650.7   79.22  2680.1   83.96
  3270.5   79.88  3609.9   82.92  3839.3   89.36  3930.4   87.89  4074.7   84.83
  4199.5   80.64  4250.9   81.41  4324.3   80.06  4707.5   75.65  4944.5    77.5
  4950.6    73.8  4965.4   73.52  4969.7  69.551  4980.1   68.14  4986.2   63.12
  5003.6   62.37  5022.2   62.37 5026.31  69.448  5055.6   76.98  5473.7   76.06
  5643.4    83.4  6160.2   80.71  6527.1   91.38  6637.3   97.02  6812.7  104.66
#Mann= 12 ,-1 , 0
  2189.6     .12       0  3270.5     .05       0  3609.9     .12       0
  3930.4     .05       0  4074.7     .12       0  4199.5      .1       0
  4250.9     .12       0  4324.3      .1       0  4969.7     .07       0
 5026.31      .1       0  6527.1     .05       0  6637.3      .1       0
Bank Sta=4969.7,5026.31
XS Rating Curve= 0 ,0
Exp/Cntr=0.3,0.1

Type RM Length L Ch R = 1 ,2500    ,500,500,500
BEGIN DESCRIPTION:
Crystal Creek 054 5.0
END DESCRIPTION:
XS GIS Cut Line= 3
      3883718.09     10041910.83      3880964.89     10043636.84
      3882417.87     10045561.09
#Sta/Elev= 30
  1750.5  102.64  1904.2  101.14  2214.6   79.57  2794.5    76.9  3153.3   76.88
  3382.5   77.79  3586.7   72.48    4456    75.4  4796.6   74.39    4885    70.4
  4921.5   74.45    4958   68.02  4963.9   62.41  4975.6   60.64  5005.8   62.27
  5012.4   67.82    5027   67.72  5033.2    62.2  5068.6   67.08  5097.7   63.12
  5112.3   68.02  5362.1   76.32  6175.9   76.52  6342.8    85.1  6530.8   85.57
  6833.6   83.36  7147.9   96.27  7220.9  102.98  7310.9  109.29  7411.2  108.35
#Mann= 9 ,-1 , 0
  1750.5     .12       0  2794.5     .05       0  3153.3     .12       0
  3586.7      .1       0    4958     .07       0  5012.4      .1       0
  6342.8     .12       0  6530.8      .1       0  7220.9     .05       0
Bank Sta=4958,5012.4
XS Rating Curve= 0 ,0
Exp/Cntr=0.3,0.1

Type RM Length L Ch R = 1 ,2000    ,500,500,500
BEGIN DESCRIPTION:
Crystal Creek 054 4.0
END DESCRIPTION:
XS GIS Cut Line= 3
      3883714.49     10041802.24      3880493.88     10043586.84
      3881826.46     10045936.24
#Sta/Elev= 30
    1318  108.22    1735    80.6  2119.6   78.23  2655.1   76.06    2664   76.03
  3834.2   70.62  4304.5   72.69  4381.6   69.39    4669    72.9    4891   80.15
  4956.3   74.83  4972.3   67.95    4978   60.58  4984.5   59.78 5045.22   67.99
  5085.3   77.12  5116.8   73.37  5246.6   76.97  5321.6   71.48  5439.9   75.56
  5747.1   71.01  5951.9   76.79    6327   77.01  6462.5   82.74  6739.4   84.03
  7078.1   82.78  7315.7   87.07  7387.1   95.48  7573.2  110.06    7701  111.76
#Mann= 12 ,-1 , 0
    1318     .12       0  2119.6      .1       0  2655.1     .05       0
    2664      .1       0  3834.2     .12       0  4304.5      .1       0
  4972.3     .07       0 5045.22      .1       0  6462.5     .12       0
  6739.4     .05       0  7078.1      .1       0  7387.1     .12       0
Bank Sta=4972.3,5045.22
XS Rating Curve= 0 ,0
Exp/Cntr=0.3,0.1

Type RM Length L Ch R = 1 ,1500    ,500,500,500
BEGIN DESCRIPTION:
Crystal Creek 054 3.0
END DESCRIPTION:
XS GIS Cut Line= 3
      3883747.06     10041661.17      3880022.88     10043576.84
      3881294.81     10046305.23
#Sta/Elev= 30
     812  111.49   864.1  111.88  1213.3   83.49  1582.8   78.88  2460.5   78.06
  2748.7   67.42  2881.8   72.88  2964.9   64.26    3181   66.14    3231   72.27
  3336.3   67.53  3766.8   74.27  3772.3   74.08  3901.6   68.77  4687.2   77.75
  4833.5    77.8  4932.6   77.37  4971.4    66.7    4984   59.82  5003.1   59.82
  5022.4   66.95  5045.3   76.04  5068.1   77.32  6187.4   71.32  6255.8   71.91
  6655.4   79.14  7346.1   81.34  7577.3   91.22  7714.3  100.44  8010.3  110.83
#Mann= 12 ,-1 , 0
     812     .12       0  1582.8      .1       0  3766.8     .12       0
  3772.3      .1       0  4687.2     .12       0  4833.5      .1       0
  4971.4     .07       0  5022.4      .1       0  6187.4     .05       0
  6255.8      .1       0  7577.3     .05       0  7714.3     .12       0
Bank Sta=4971.4,5022.4
XS Rating Curve= 0 ,0
Exp/Cntr=0.3,0.1

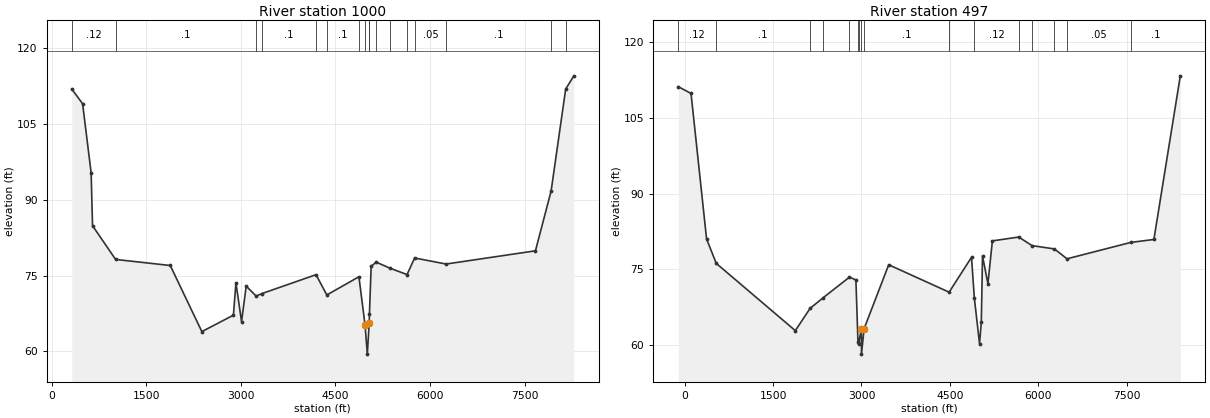
Type RM Length L Ch R = 1 ,1000    ,503,503,503
BEGIN DESCRIPTION:
Crystal Creek 054 2.0
END DESCRIPTION:
XS GIS Cut Line= 3
      3883736.22     10041520.11      3879531.16     10043576.84
      3880317.86      10046761.1
#Sta/Elev= 30
   318.9  111.96   490.7  109.04   625.8   95.36   648.3   84.87  1014.1   78.19
  1880.6   76.99  2381.5   63.89  2882.3   67.15  2921.8   73.59    3011   65.87
  3084.9   72.91  3243.2   70.92  3332.1   71.42  4191.7   75.17  4363.2   71.15
  4872.2   74.76  4970.1   65.11  5005.1   59.43  5035.3   65.57  5038.9   67.37
  5066.2   76.84  5146.5   77.65  5362.1   76.47  5635.3   75.19  5755.3   78.48
  6254.4   77.28  7671.2    79.9  7919.6   91.75  8150.7  111.95    8280  114.57
#Mann= 17 ,-1 , 0
   318.9     .12       0  1014.1      .1       0  3243.2     .12       0
  3332.1      .1       0  4191.7     .12       0  4363.2      .1       0
  4872.2     .12       0  4970.1     .07       0  5035.3     .12       0
  5038.9      .1       0  5146.5     .12       0  5362.1      .1       0
  5635.3     .12       0  5755.3     .05       0  6254.4      .1       0
  7919.6     .05       0  8150.7      .1       0
Bank Sta=4970.1,5035.3
XS Rating Curve= 0 ,0
Exp/Cntr=0.3,0.1

Type RM Length L Ch R = 1 ,497     ,0,0,0
BEGIN DESCRIPTION:
Crystal Creek 054 1.0
END DESCRIPTION:
XS GIS Cut Line= 3
      3883725.42     10041411.58      3879078.23     10043536.84
      3879764.88     10046880.36
#Sta/Elev= 30
  -110.1  111.19   107.1  109.84   371.1   81.01   535.7   76.18  1877.7   62.86
  2128.1   67.27  2354.8   69.42  2795.8   73.45    2906   72.91  2941.1   60.62
  2950.7   60.17 2998.75  63.229  3000.6   58.21 3045.27  63.249  3462.9   75.91
  4488.5   70.48  4868.5   77.39  4916.3   69.36  5004.7   60.28  5034.9   64.48
  5055.4   77.67  5147.2   72.15  5222.8   80.64  5669.6    81.4    5897    79.7
  6276.9   79.04  6489.9   77.09  7571.5   80.33  7964.8   80.92  8413.3  113.33
#Mann= 16 ,-1 , 0
  -110.1     .12       0   535.7      .1       0  2128.1     .12       0
  2354.8      .1       0  2795.8     .12       0  2941.1     .05       0
  2950.7      .1       0 2998.75     .07       0 3045.27      .1       0
  4488.5     .05       0  4916.3     .12       0  5669.6     .05       0
    5897     .12       0  6276.9      .1       0  6489.9     .05       0
  7571.5      .1       0
Bank Sta=2998.75,3045.27
XS Rating Curve= 0 ,0
Exp/Cntr=0.3,0.1