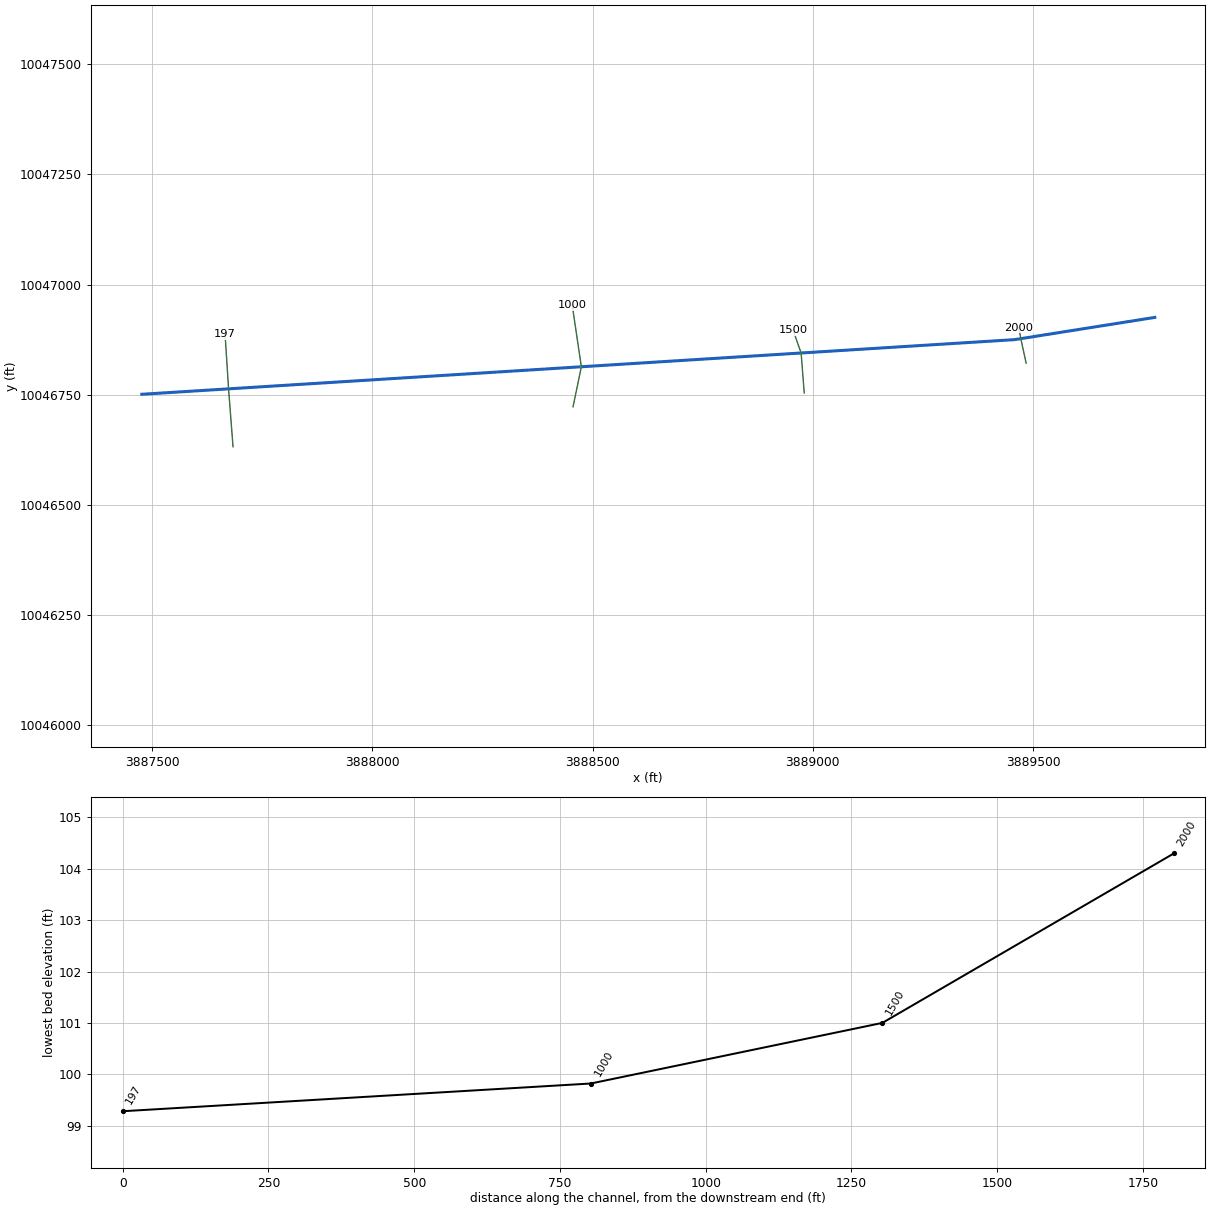
--- Crystal Creek 055.prj (project) ---

Proj Title=Crystal Creek 055 Base Level Engineering
Current Plan=p01
Default Exp/Contr=0.3,0.1
English Units
Geom File=g01
Flow File=f01
Plan File=p01
Y Axis Title=Elevation
X Axis Title(PF)=Main Channel Distance
X Axis Title(XS)=Station
BEGIN DESCRIPTION:
Crystal Creek 055
END DESCRIPTION:
DSS Export Rating Curves= 0
DSS Export Rating Curve Sorted= 0
DSS Export Volume Flow Curves= 0
DXF OffsetX= 0
DXF OffsetY= 0
DXF ScaleX= 1
DXF ScaleY= 10

--- Crystal Creek 055.p01 (plan) ---

Plan Title=Multiple Run
Short Identifier=Multiple
Geom File=g01
Flow File=f01
Subcritical Flow
K Sum by GR= 0
Std Step Tol= 0.01
Critical Tol= 0.01
Num of Std Step Trials= 20
Max Error Tol= 0.3
Flow Tol Ratio= 0.001
Split Flow NTrial= 30
Split Flow Tol= 0.02
Split Flow Ratio= 0.02
Log Output Level= 0
Friction Slope Method= 1
Unsteady Friction Slope Method= 2
Unsteady Bridges Friction Slope Method= 1
Parabolic Critical Depth
Global Vel Dist=  1 , 1 , 1
Global Log Level= 0
CheckData=True
Encroach Param= -1, 0, 0, 0
BEGIN DESCRIPTION:
Multiple Run
END DESCRIPTION:

--- Crystal Creek 055.f01 (steady flow) ---

Flow Title=Multiple
Program Version=4.10
Number of Profiles= 7
Profile Names=10-year,25-year,50-year,1pct_min,100-year,1pct_plu,500-year
River Rch & RM=Crystal Creek 05,Reach-1         ,2000
     120     140     170      69     207     625     315
Boundary for River Rch & Prof#=Crystal Creek 05,Reach-1         , 1
Up Type= 0
Dn Type= 3
Dn Slope=0.005
Boundary for River Rch & Prof#=Crystal Creek 05,Reach-1         , 2
Up Type= 0
Dn Type= 3
Dn Slope=0.005
Boundary for River Rch & Prof#=Crystal Creek 05,Reach-1         , 3
Up Type= 0
Dn Type= 3
Dn Slope=0.005
Boundary for River Rch & Prof#=Crystal Creek 05,Reach-1         , 4
Up Type= 0
Dn Type= 3
Dn Slope=0.005
Boundary for River Rch & Prof#=Crystal Creek 05,Reach-1         , 5
Up Type= 0
Dn Type= 3
Dn Slope=0.005
Boundary for River Rch & Prof#=Crystal Creek 05,Reach-1         , 6
Up Type= 0
Dn Type= 3
Dn Slope=0.005
Boundary for River Rch & Prof#=Crystal Creek 05,Reach-1         , 7
Up Type= 0
Dn Type= 3
Dn Slope=0.005
DSS Import GetInterval= 0
DSS Import GetPeak= 0
DSS Import FillOption= 0

--- Crystal Creek 055.g01 (geometry) ---

Geom Title=Existing Conditions
Program Version=4.10

River Reach=Crystal Creek 05,Reach-1
Reach XY= 3
      3889776.41     10046925.38      3889458.36     10046874.96
      3887476.35     10046750.84

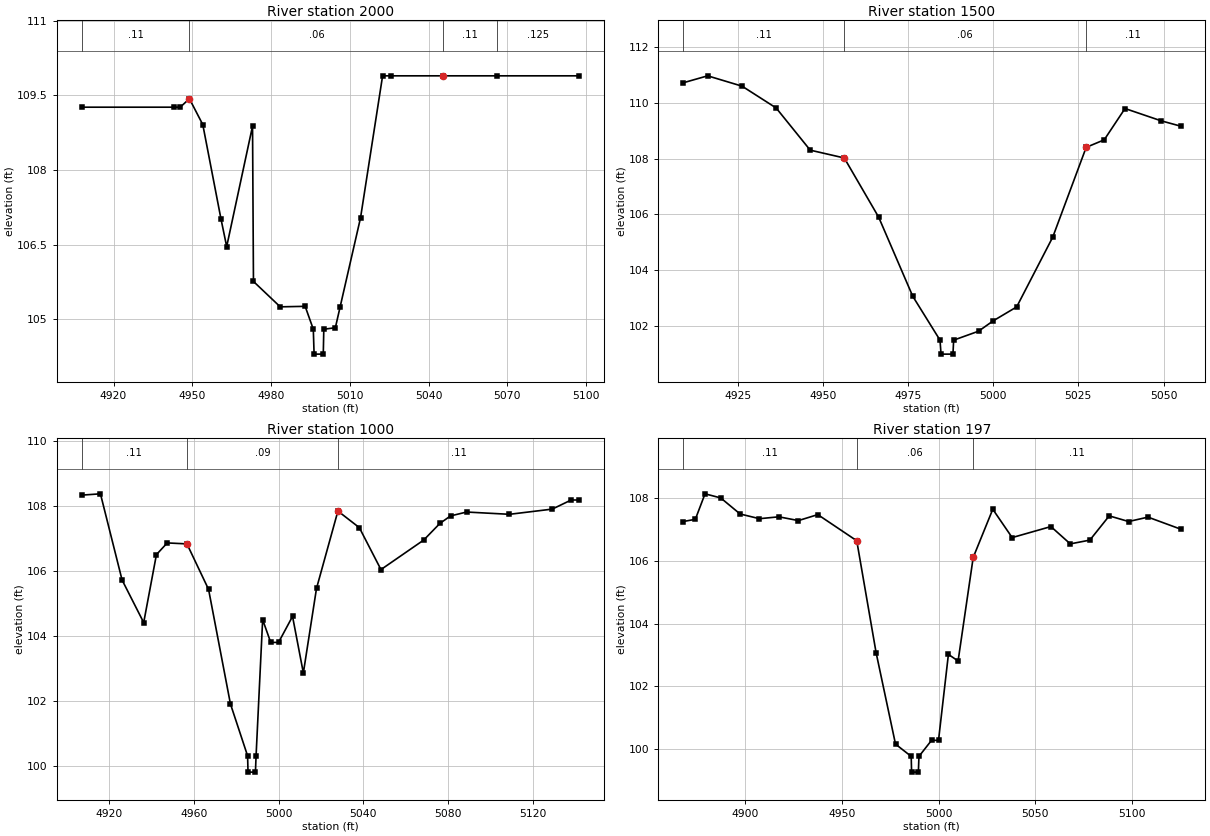
Type RM Length L Ch R = 1 ,2000    ,500,500,500
BEGIN DESCRIPTION:
Crystal Creek 055 4.0
END DESCRIPTION:
XS GIS Cut Line= 3
      3889484.33     10046821.46       3889472.3     10046877.17
       3889467.5     10046902.42
#Sta/Elev= 23
  4907.9  109.26    4943  109.26  4945.4  109.26  4948.9  109.43    4954  108.91
 4960.91  107.02  4963.1  106.46 4972.95  108.88  4973.3  105.76  4983.5  105.25
    4993  105.26  4996.1   104.8  4996.4   104.3  4999.9   104.3  5000.1   104.8
  5004.5  104.83 5006.34105.2535  5014.1  107.04  5022.5  109.89  5025.7  109.89
 5045.68  109.89  5066.2  109.89  5097.4  109.89
#Mann= 4 ,-1 , 0
  4907.9     .11       0  4948.9     .06       0 5045.68     .11       0
  5066.2    .125       0
Bank Sta=4948.9,5045.68
XS Rating Curve= 0 ,0
Exp/Cntr=0.3,0.1

Type RM Length L Ch R = 1 ,1500    ,500,500,500
BEGIN DESCRIPTION:
Crystal Creek 055 3.0
END DESCRIPTION:
XS GIS Cut Line= 3
      3888980.49     10046753.87      3888973.42     10046844.59
      3888955.16     10046896.47
#Sta/Elev= 21
    4909  110.71  4916.2  110.96  4926.3  110.59  4936.3  109.81  4946.3   108.3
  4956.3  108.02  4966.4   105.9  4976.4  103.07  4984.4   101.5  4984.7     101
  4988.2     101  4988.4   101.5  4995.7  101.82    5000  102.19  5006.9  102.69
  5017.5  105.19  5027.3   108.4  5032.6  108.67  5038.7  109.79  5049.3  109.35
    5055  109.16
#Mann= 3 , 0 , 0
    4909     .11       0  4956.3     .06       0  5027.3     .11       0
Bank Sta=4956.3,5027.3
XS Rating Curve= 0 ,0
Exp/Cntr=0.3,0.1

Type RM Length L Ch R = 1 ,1000    ,803,803,803
BEGIN DESCRIPTION:
Crystal Creek 055 2.0
END DESCRIPTION:
XS GIS Cut Line= 3
      3888455.53     10046722.48       3888474.4     10046813.34
      3888453.58     10046953.61
#Sta/Elev= 30
  4907.2  108.34    4916  108.38  4926.2  105.73  4936.4  104.42  4942.4  106.51
  4947.5  106.87  4956.8  106.84    4967  105.44  4977.3  101.92  4985.4  100.32
  4985.6   99.82  4989.1   99.82  4989.4  100.32  4992.5  104.51  4996.3  103.81
    5000  103.81  5006.6  104.61  5011.7  102.87  5017.9  105.47    5028  107.85
  5038.1  107.34  5048.3  106.05  5068.5  106.96  5076.1  107.47  5081.1   107.7
  5088.7  107.82  5108.9  107.75  5129.1  107.91    5138  108.19  5141.8  108.19
#Mann= 3 , 0 , 0
  4907.2     .11       0  4956.8     .09       0    5028     .11       0
Bank Sta=4956.8,5028
XS Rating Curve= 0 ,0
Exp/Cntr=0.3,0.1

Type RM Length L Ch R = 1 ,197     ,0,0,0
BEGIN DESCRIPTION:
Crystal Creek 055 1.0
END DESCRIPTION:
XS GIS Cut Line= 3
      3887683.48     10046631.77      3887673.32     10046763.18
      3887665.37     10046887.82
#Sta/Elev= 30
  4868.2  107.24  4874.5  107.31  4879.5  108.12  4887.6  107.99  4897.6  107.48
  4907.6  107.33  4917.6  107.39  4927.7  107.27  4937.7  107.46  4957.8  106.63
  4967.8  103.07  4977.8  100.17  4985.9   99.78  4986.1   99.28  4989.6   99.28
  4989.9   99.78  4996.4  100.29    5000  100.29  5005.1  103.02  5010.1  102.81
  5017.9   106.1    5028  107.63    5038  106.73    5058  107.08    5068  106.53
  5078.1  106.65  5088.1  107.42  5098.1  107.24  5108.1  107.38  5124.9     107
#Mann= 3 , 0 , 0
  4868.2     .11       0  4957.8     .06       0  5017.9     .11       0
Bank Sta=4957.8,5017.9
XS Rating Curve= 0 ,0
Exp/Cntr=0.3,0.1

Chan Stop Cuts=-1
Use User Specified Reach Order=0
Composite Channel Slope=5

--- Crystal Creek 055.g10 (geometry) ---

Geom Title=Existing Conditions
Program Version=4.10

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
River Reach=Crystal Creek 05,Reach-1

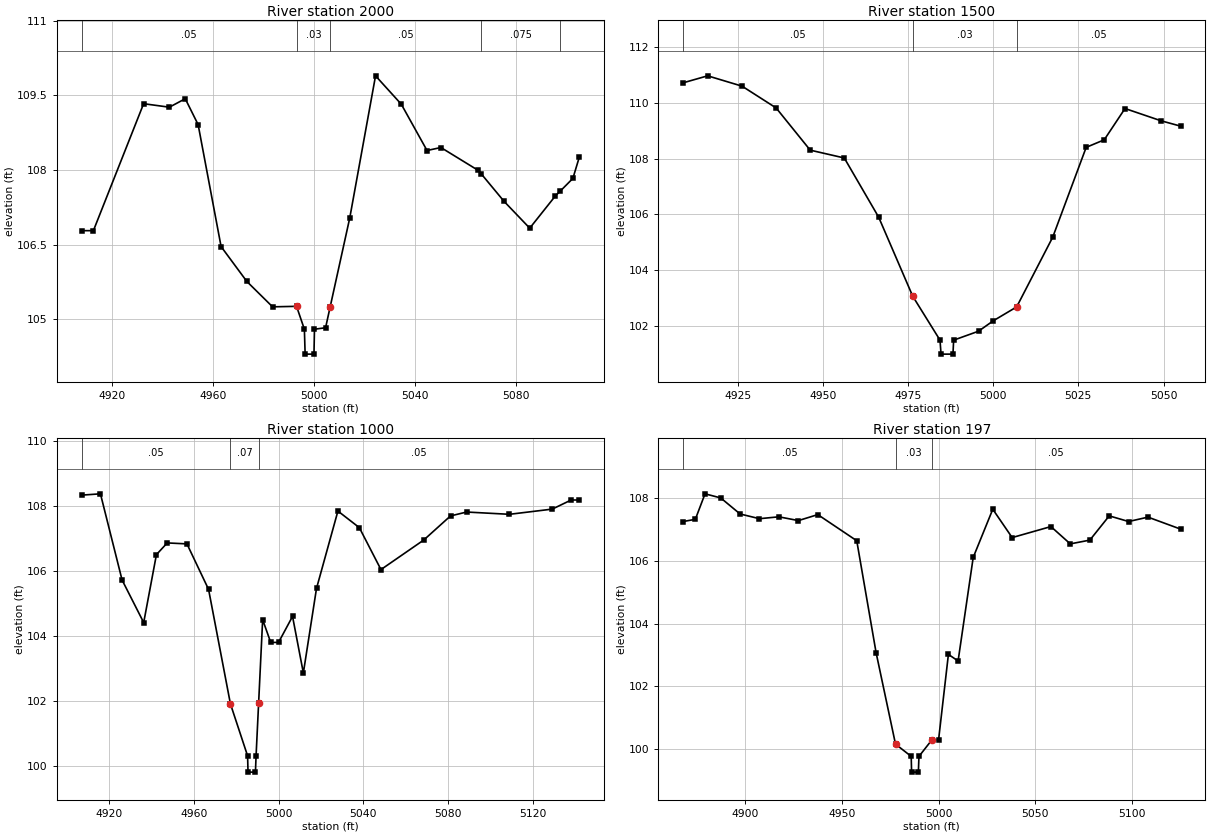
Type RM Length L Ch R = 1 ,2000    ,500,500,500
BEGIN DESCRIPTION:
Crystal Creek 055 4.0
END DESCRIPTION:
XS GIS Cut Line= 3
      3889491.74     10046787.15       3889472.3     10046877.17
      3889452.71     10046980.33
#Sta/Elev= 29
  4907.9  106.78  4912.5  106.78  4932.4  109.33  4942.6  109.26  4948.9  109.43
    4954  108.91  4963.1  106.46  4973.3  105.76  4983.5  105.25    4993  105.26
  4996.1   104.8  4996.4   104.3  4999.9   104.3  5000.1   104.8  5004.5  104.83
 5006.34 105.254  5014.1  107.04  5024.3  109.89  5034.5  109.32  5044.7  108.39
  5050.2  108.45    5065  107.99  5066.2  107.92  5075.2  107.37  5085.4  106.83
  5095.6  107.48  5097.4  107.57  5102.5  107.83    5105  108.25
#Mann= 5 ,-1 , 0
  4907.9     .05       0    4993     .03       0 5006.34     .05       0
  5066.2    .075       0  5097.4     .05       0
Bank Sta=4993,5006.34
XS Rating Curve= 0 ,0
Exp/Cntr=0.3,0.1

Type RM Length L Ch R = 1 ,1500    ,500,500,500
BEGIN DESCRIPTION:
Crystal Creek 055 3.0
END DESCRIPTION:
XS GIS Cut Line= 3
      3888980.49     10046753.87      3888973.42     10046844.59
      3888955.16     10046896.47
#Sta/Elev= 21
    4909  110.71  4916.2  110.96  4926.3  110.59  4936.3  109.81  4946.3   108.3
  4956.3  108.02  4966.4   105.9  4976.4  103.07  4984.4   101.5  4984.7     101
  4988.2     101  4988.4   101.5  4995.7  101.82    5000  102.19  5006.9  102.69
  5017.5  105.19  5027.3   108.4  5032.6  108.67  5038.7  109.79  5049.3  109.35
    5055  109.16
#Mann= 3 , 0 , 0
    4909     .05       0  4976.4     .03       0  5006.9     .05       0
Bank Sta=4976.4,5006.9
XS Rating Curve= 0 ,0
Exp/Cntr=0.3,0.1

Type RM Length L Ch R = 1 ,1000    ,803,803,803
BEGIN DESCRIPTION:
Crystal Creek 055 2.0
END DESCRIPTION:
XS GIS Cut Line= 3
      3888455.53     10046722.48       3888474.4     10046813.34
      3888453.58     10046953.61
#Sta/Elev= 30
  4907.2  108.34    4916  108.38  4926.2  105.73  4936.4  104.42  4942.4  106.51
  4947.5  106.87  4956.8  106.84    4967  105.44  4977.3  101.92  4985.4  100.32
  4985.6   99.82  4989.1   99.82  4989.4  100.32  4990.6 101.942  4992.5  104.51
  4996.3  103.81    5000  103.81  5006.6  104.61  5011.7  102.87  5017.9  105.47
    5028  107.85  5038.1  107.34  5048.3  106.05  5068.5  106.96  5081.1   107.7
  5088.7  107.82  5108.9  107.75  5129.1  107.91    5138  108.19  5141.8  108.19
#Mann= 3 , 0 , 0
  4907.2     .05       0  4977.3     .07       0  4990.6     .05       0
Bank Sta=4977.3,4990.6
XS Rating Curve= 0 ,0
Exp/Cntr=0.3,0.1

Type RM Length L Ch R = 1 ,197     ,0,0,0
BEGIN DESCRIPTION:
Crystal Creek 055 1.0
END DESCRIPTION:
XS GIS Cut Line= 3
      3887683.48     10046631.77      3887673.32     10046763.18
      3887665.37     10046887.82
#Sta/Elev= 30
  4868.2  107.24  4874.5  107.31  4879.5  108.12  4887.6  107.99  4897.6  107.48
  4907.6  107.33  4917.6  107.39  4927.7  107.27  4937.7  107.46  4957.8  106.63
  4967.8  103.07  4977.8  100.17  4985.9   99.78  4986.1   99.28  4989.6   99.28
  4989.9   99.78  4996.4  100.29    5000  100.29  5005.1  103.02  5010.1  102.81
  5017.9   106.1    5028  107.63    5038  106.73    5058  107.08    5068  106.53
  5078.1  106.65  5088.1  107.42  5098.1  107.24  5108.1  107.38  5124.9     107
#Mann= 3 , 0 , 0
  4868.2     .05       0  4977.8     .03       0  4996.4     .05       0
Bank Sta=4977.8,4996.4
XS Rating Curve= 0 ,0
Exp/Cntr=0.3,0.1