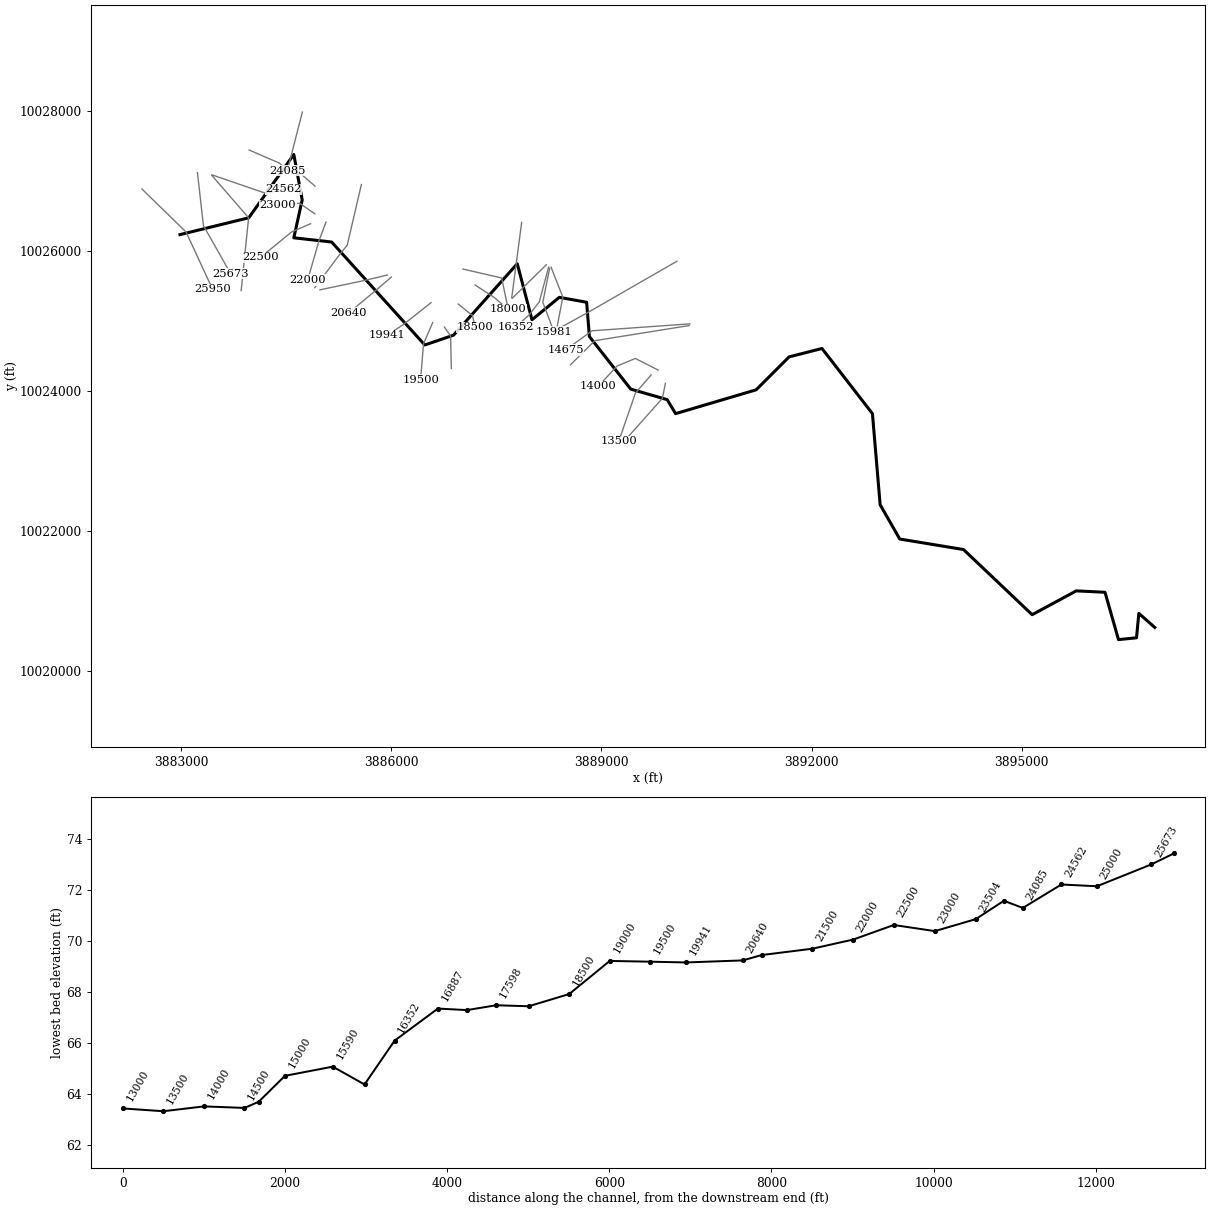
--- Crystal Creek 056.prj (project) ---

Proj Title=Crystal Creek 056 Base Level Engineering
Current Plan=p01
Default Exp/Contr=0.3,0.1
English Units
Geom File=g01
Flow File=f01
Plan File=p01
Y Axis Title=Elevation
X Axis Title(PF)=Main Channel Distance
X Axis Title(XS)=Station
BEGIN DESCRIPTION:
Crystal Creek 056
END DESCRIPTION:
DSS Export Rating Curves= 0
DSS Export Rating Curve Sorted= 0
DSS Export Volume Flow Curves= 0
DXF OffsetX= 0
DXF OffsetY= 0
DXF ScaleX= 1
DXF ScaleY= 10

--- Crystal Creek 056.p01 (plan) ---

Plan Title=Multiple Run
Short Identifier=Multiple
Geom File=g01
Flow File=f01
Subcritical Flow
K Sum by GR= 0
Std Step Tol= 0.01
Critical Tol= 0.01
Num of Std Step Trials= 20
Max Error Tol= 0.3
Flow Tol Ratio= 0.001
Split Flow NTrial= 30
Split Flow Tol= 0.02
Split Flow Ratio= 0.02
Log Output Level= 0
Friction Slope Method= 1
Unsteady Friction Slope Method= 2
Unsteady Bridges Friction Slope Method= 1
Parabolic Critical Depth
Global Vel Dist=  1 , 1 , 1
Global Log Level= 0
CheckData=True
Encroach Param= -1, 0, 0, 0
BEGIN DESCRIPTION:
Multiple Run
END DESCRIPTION:

--- Crystal Creek 056.f01 (steady flow) ---

Flow Title=Multiple
Program Version=4.10
Number of Profiles= 7
Profile Names=10-year,25-year,50-year,1pct_min,100-year,1pct_plu,500-year
River Rch & RM=Crystal Creek 05,Reach-1         ,25950
     635     827    1088     470    1418    4282    2491
River Rch & RM=Crystal Creek 05,Reach-1         ,25000
     815    1067    1409     609    1840    5557    3242
River Rch & RM=Crystal Creek 05,Reach-1         ,11500
     963    1272    1688     733    2214    6686    3941
Boundary for River Rch & Prof#=Crystal Creek 05,Reach-1         , 1
Up Type= 0
Dn Type= 3
Dn Slope=0.003
Boundary for River Rch & Prof#=Crystal Creek 05,Reach-1         , 2
Up Type= 0
Dn Type= 3
Dn Slope=0.003
Boundary for River Rch & Prof#=Crystal Creek 05,Reach-1         , 3
Up Type= 0
Dn Type= 3
Dn Slope=0.003
Boundary for River Rch & Prof#=Crystal Creek 05,Reach-1         , 4
Up Type= 0
Dn Type= 3
Dn Slope=0.003
Boundary for River Rch & Prof#=Crystal Creek 05,Reach-1         , 5
Up Type= 0
Dn Type= 3
Dn Slope=0.003
Boundary for River Rch & Prof#=Crystal Creek 05,Reach-1         , 6
Up Type= 0
Dn Type= 3
Dn Slope=0.003
Boundary for River Rch & Prof#=Crystal Creek 05,Reach-1         , 7
Up Type= 0
Dn Type= 3
Dn Slope=0.003
DSS Import GetInterval= 0
DSS Import GetPeak= 0
DSS Import FillOption= 0

--- Crystal Creek 056.g01 (geometry) ---

Geom Title=Existing Conditions
Program Version=4.10

River Reach=Crystal Creek 05,Reach-1
Reach XY= 30
       3882983.3     10026232.26      3883965.94     10026472.89
      3884608.24     10027376.86      3884728.24     10026726.86
      3884608.24     10026186.86      3885148.24     10026126.86
      3886478.24     10024656.86      3886888.24     10024796.86
      3887798.24     10025816.86      3888008.24     10025016.86
      3888398.24     10025336.86      3888788.24     10025266.86
      3888828.24     10024776.86      3889418.24     10024026.86
      3889938.24     10023876.86      3890058.24     10023676.86
      3891208.24     10024016.86      3891678.24     10024486.86
      3892148.24     10024606.86      3892868.24     10023676.86
      3892978.24     10022376.86      3893258.24     10021886.86
      3894168.24     10021736.86      3895148.24     10020806.86
      3895778.24     10021146.86      3896188.24     10021126.86
      3896380.69     10020451.09      3896638.06     10020476.98
      3896671.04     10020825.49      3896898.68     10020624.92

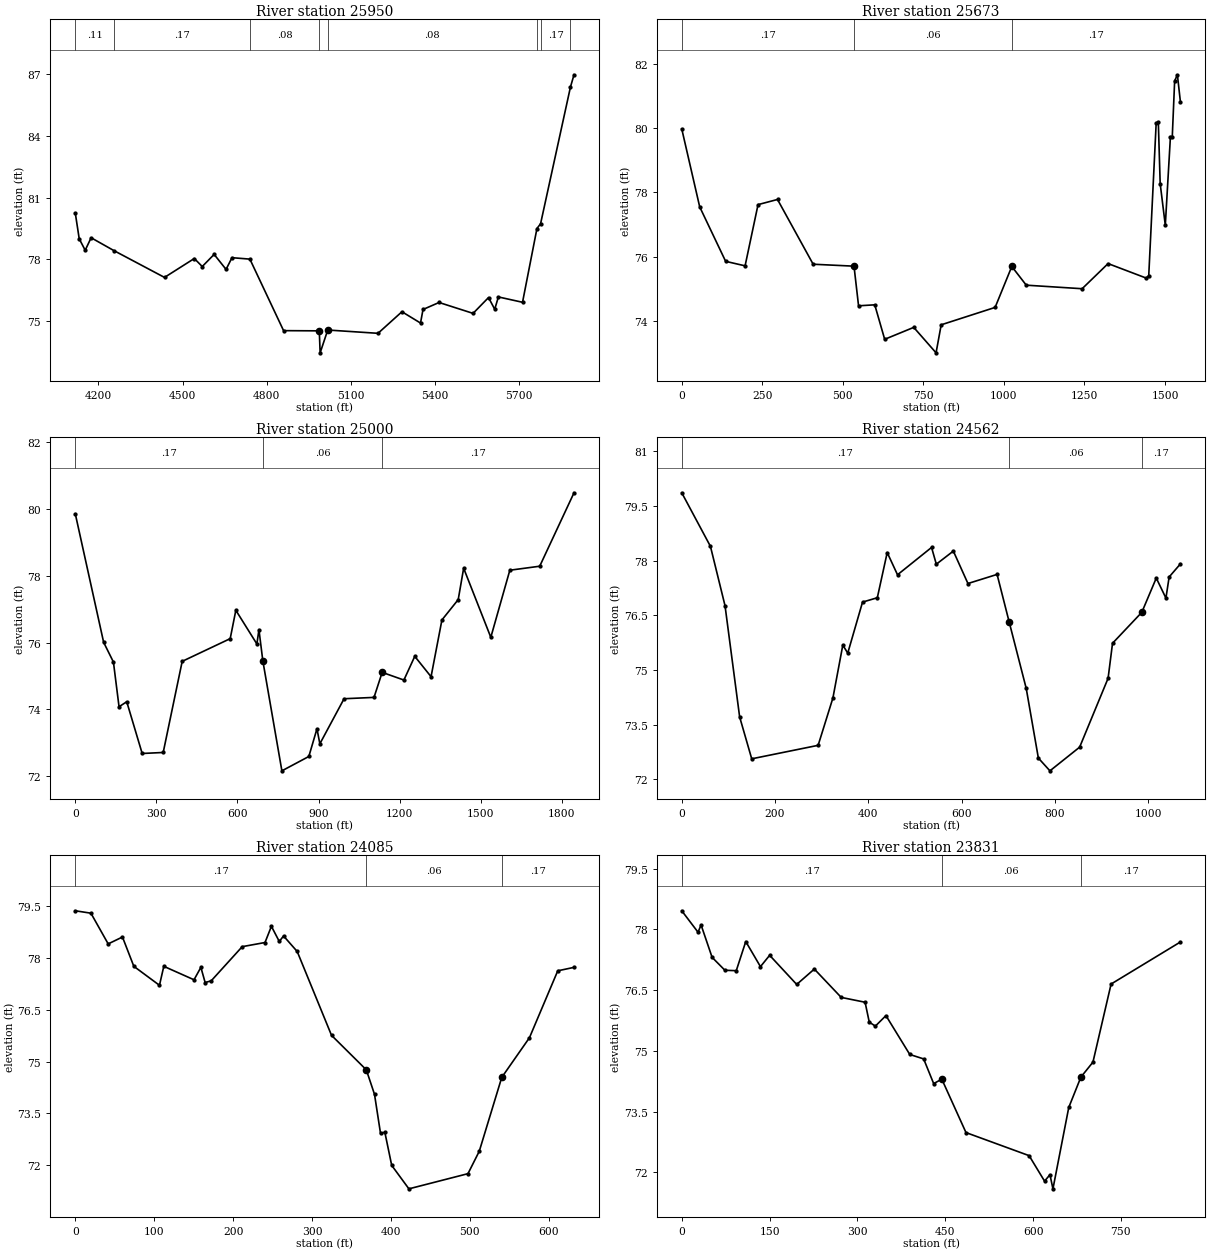
Type RM Length L Ch R = 1 ,25950   ,277,277,277
BEGIN DESCRIPTION:
Crystal Creek 056 52.0
END DESCRIPTION:
XS GIS Cut Line= 3
      3882440.32     10026883.38      3883069.67     10026270.31
      3883447.71     10025454.66
#Sta/Elev= 30
  4117.6   80.25  4131.6      79  4152.9   78.44    4174   79.05  4255.9   78.42
  4435.6   77.12  4541.8   78.04  4570.1   77.65  4612.5   78.24    4655   77.51
  4676.1   78.08  4739.9   78.01    4860   74.53  4987.3   74.52  4990.3   73.45
  5017.4   74.56  5196.6    74.4  5281.9   75.45  5348.1    74.9    5357   75.56
  5414.2    75.9  5535.4   75.37  5590.5   76.14  5612.6   75.57  5625.6   76.17
  5711.7   75.91  5763.1    79.5    5776   79.73  5882.6   86.39  5895.2   86.98
#Mann= 8 ,-1 , 0
  4117.6     .11       0  4255.9     .17       0  4739.9     .08       0
  4987.3     .06       0  5017.4     .08       0  5763.1     .15       0
    5776     .17       0  5882.6     .11       0
Bank Sta=4987.3,5017.4
XS Rating Curve= 0 ,0
Exp/Cntr=0.3,0.1

Type RM Length L Ch R = 1 ,25673   ,672,672,672
XS GIS Cut Line= 3
      3883233.16     10027116.44      3883317.72      10026362.1
      3883706.61      10025674.6
#Sta/Elev= 30
       0   79.97    55.7   77.55   136.2   75.86   196.6   75.72   236.8   77.62
   297.2   77.78   407.9   75.77   534.7   75.71   548.8   74.48   599.1   74.51
   629.9   73.44   720.1   73.81   789.4   73.02   805.3   73.89   972.7   74.43
  1024.5    75.7  1069.4   75.12  1242.8   75.01  1323.4   75.79  1441.8   75.34
  1449.6   75.42  1472.6   80.14  1479.3   80.19  1485.1   78.27    1501   76.98
  1516.9   79.73  1522.6   79.72    1530   81.46  1538.5   81.65  1548.1   80.79
#Mann= 3 , 0 , 0
       0     .17       0   534.7     .06       0  1024.5     .17       0
Bank Sta=534.7,1024.5
XS Rating Curve= 0 ,0
Exp/Cntr=0.3,0.1

Type RM Length L Ch R = 1 ,25000   ,438,438,438
XS GIS Cut Line= 3
       3883437.4     10027079.13      3883962.77     10026472.19
      3883857.02      10025433.5
#Sta/Elev= 30
       0   79.86   104.9   76.01   141.1   75.42   161.9   74.08   190.4   74.23
   247.5   72.68   325.3   72.71   395.6   75.44   573.2   76.12   594.1   76.97
     672   75.96   679.6   76.39   693.9   75.46   764.5   72.16   864.2   72.59
   894.3   73.42     905   72.97   994.6   74.32  1105.4   74.36  1135.6   75.11
    1216   74.88  1256.2   75.59  1316.5   74.98  1356.7   76.68    1417   77.29
  1437.1   78.23  1537.6   76.16    1608   78.17  1718.6   78.29  1845.5   80.49
#Mann= 3 , 0 , 0
       0     .17       0   693.9     .06       0  1135.6     .17       0
Bank Sta=693.9,1135.6
XS Rating Curve= 0 ,0
Exp/Cntr=0.3,0.1

Type RM Length L Ch R = 1 ,24562   ,476,476,476
XS GIS Cut Line= 3
      3883441.27      10027084.9      3884216.59      10026818.7
      3884458.03     10026881.76
#Sta/Elev= 30
       0   79.86    61.5   78.39    92.8   76.76   124.1   73.71     150   72.56
   292.4   72.93   324.1   74.23   345.3   75.68   355.9   75.46   387.6   76.86
   419.3   76.98   440.5   78.22   462.6   77.61   535.6   78.36   545.8    77.9
   582.3   78.26   613.6   77.37   676.1   77.62   702.1   76.31   738.6   74.49
   764.6   72.58   789.4   72.23   853.1   72.88   914.1   74.77   923.6   75.73
   986.4   76.58  1017.4   77.52  1038.1   76.97    1045   77.55  1069.3   77.91
#Mann= 3 , 0 , 0
       0     .17       0   702.1     .06       0   986.4     .17       0
Bank Sta=702.1,986.4
XS Rating Curve= 0 ,0
Exp/Cntr=0.3,0.1

Type RM Length L Ch R = 1 ,24085   ,234,234,234
XS GIS Cut Line= 3
      3883969.71     10027440.54      3884398.88      10027254.9
      3884523.88     10027146.82
#Sta/Elev= 30
       0   79.37    19.8    79.3    41.7   78.41    59.8   78.61    74.2   77.76
   106.7   77.21   112.2   77.76   150.5   77.37   159.2   77.73   164.6   77.29
   172.3   77.34   211.6   78.33   240.5   78.45   248.6   78.92   258.6   78.48
     264   78.64   281.3   78.19   324.8   75.76   368.9   74.76   379.3   74.05
   386.9   72.92   392.4   72.95   401.1   71.99   422.9   71.31   497.8   71.75
   512.1    72.4   540.6   74.54   575.7   75.69   611.6   77.63   632.2   77.73
#Mann= 3 , 0 , 0
       0     .17       0   368.9     .06       0   540.6     .17       0
Bank Sta=368.9,540.6
XS Rating Curve= 0 ,0
Exp/Cntr=0.3,0.1

Type RM Length L Ch R = 1 ,23831   ,347,347,347
XS GIS Cut Line= 2
      3884730.22     10027981.24       3884518.4     10027156.34
#Sta/Elev= 30
       0   78.46    27.8   77.93      33   78.11    51.8   77.31    73.7   76.99
    93.1   76.98   109.3    77.7   134.4   77.08   150.1   77.36   196.3   76.64
   226.4   77.02   272.3   76.32   313.1    76.2   320.2   75.71   330.6   75.61
   348.7   75.87   389.4   74.91   413.1    74.8   430.2   74.19   444.1    74.3
   485.4   72.98   593.2   72.41   619.6   71.78   628.8   71.94   633.9   71.59
   660.9    73.6   681.6   74.35   702.2   74.72   733.2   76.65   851.7   77.69
#Mann= 3 , 0 , 0
       0     .17       0   444.1     .06       0   681.6     .17       0
Bank Sta=444.1,681.6
XS Rating Curve= 0 ,0
Exp/Cntr=0.3,0.1

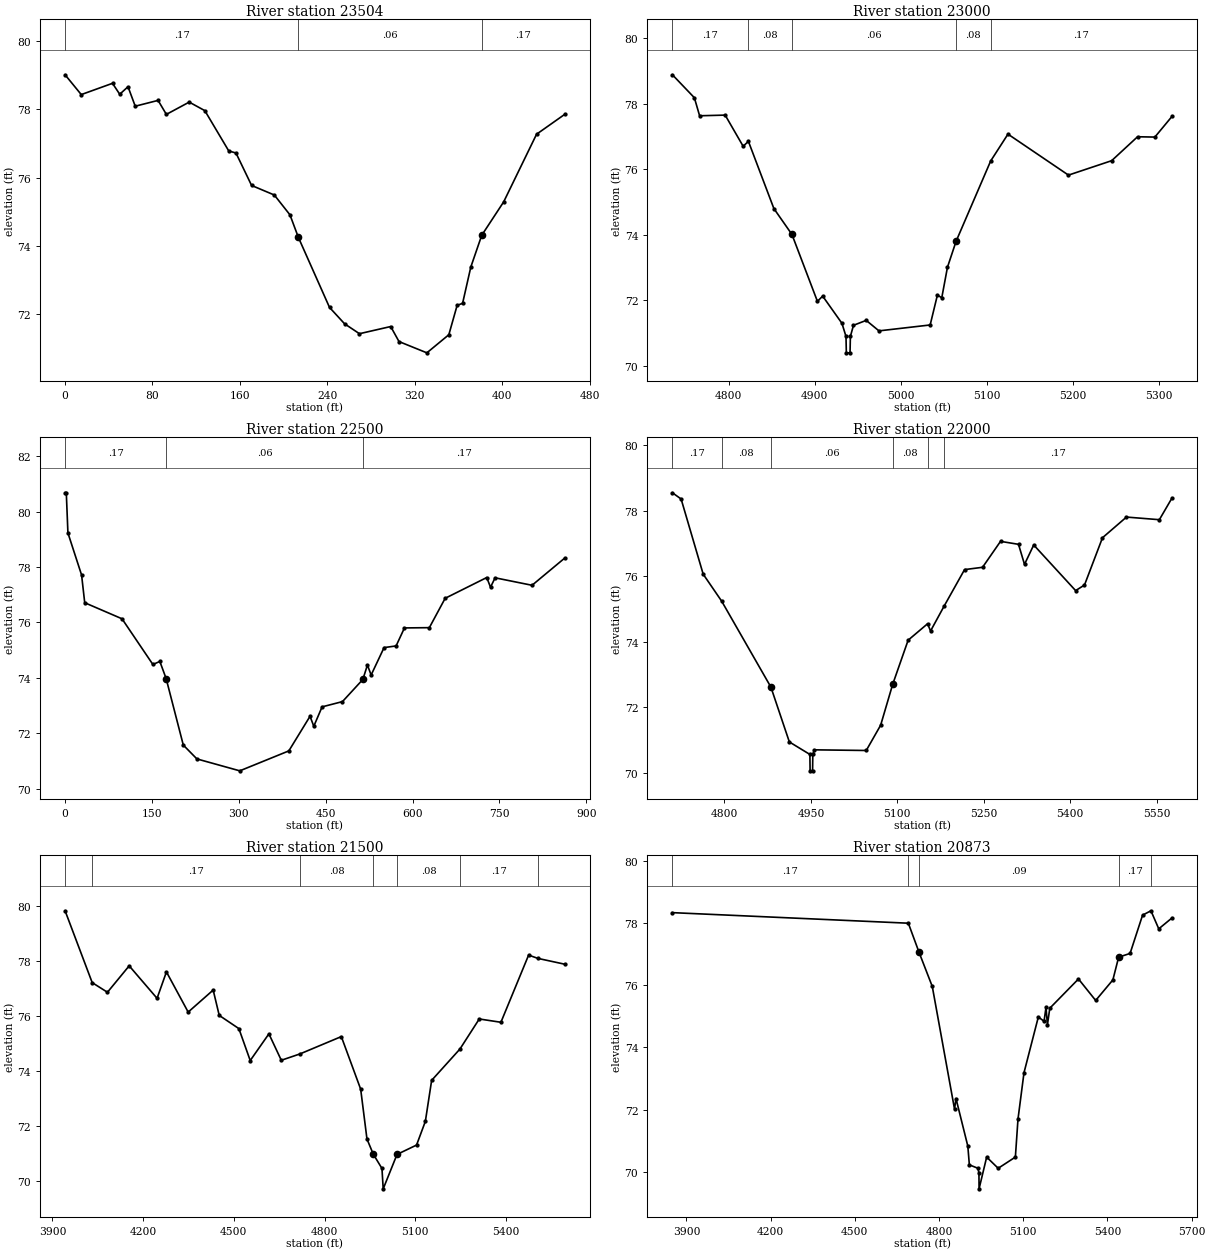
Type RM Length L Ch R = 1 ,23504   ,504,504,504
XS GIS Cut Line= 3
      3884911.83     10026924.45      3884669.72      10027132.5
       3884531.7     10027144.22
#Sta/Elev= 30
       0   79.01    14.8   78.43    43.4   78.76      50   78.44    57.6   78.66
    64.2   78.09    85.1   78.26    92.7   77.85   113.6   78.21   127.9   77.96
   149.8   76.78   156.4   76.72   170.7   75.77   191.5   75.49   205.8   74.91
   213.5   74.25     242    72.2   255.8   71.72   269.4   71.43     298   71.64
   305.6    71.2   331.1   70.87   351.2    71.4   358.8   72.26   363.8   72.32
   371.3   73.38   381.3   74.31   401.4   75.29   431.5   77.27   457.2   77.85
#Mann= 3 , 0 , 0
       0     .17       0   213.5     .06       0   381.3     .17       0
Bank Sta=213.5,381.3
XS Rating Curve= 0 ,0
Exp/Cntr=0.3,0.1

Type RM Length L Ch R = 1 ,23000   ,507,507,507
BEGIN DESCRIPTION:
Crystal Creek 056 46.0
END DESCRIPTION:
XS GIS Cut Line= 3
      3884909.29     10026528.34      3884691.77      10026680.4
      3884378.07     10026650.73
#Sta/Elev= 30
  4734.6   78.88  4760.1   78.18  4766.2   77.63  4795.9   77.65  4816.8    76.7
  4822.9   76.85  4852.5    74.8  4873.5   74.01  4903.1   71.97  4909.2   72.13
  4931.6    71.3  4936.3    70.9  4936.7    70.4    4941    70.4  4941.4    70.9
    4945   71.24  4959.8   71.39  4974.6   71.07  5034.1   71.25  5042.5   72.16
  5047.6   72.08  5054.2   73.01  5064.2    73.8  5104.4   76.25  5124.5   77.07
  5194.8   75.82    5245   76.26  5275.1   76.99  5295.2   76.98  5315.1   77.61
#Mann= 5 ,-1 , 0
  4734.6     .17       0  4822.9     .08       0  4873.5     .06       0
  5064.2     .08       0  5104.4     .17       0
Bank Sta=4873.5,5064.2
XS Rating Curve= 0 ,0
Exp/Cntr=0.3,0.1

Type RM Length L Ch R = 1 ,22500   ,499,499,499
XS GIS Cut Line= 3
       3884848.1     10026387.71      3884578.24     10026271.52
      3884138.05     10025911.52
#Sta/Elev= 30
       0   80.68     2.1   80.68     4.9   79.23    28.5   77.71    33.9   76.71
    98.3   76.13   151.6   74.48   163.6   74.59   174.5   73.97   204.1   71.57
   227.6   71.07   301.6   70.64   386.3   71.36   422.9   72.61   429.4   72.25
   443.7   72.95   478.9   73.14   514.1   73.94     522   74.46   528.4    74.1
   550.7   75.09   571.5   75.15   585.9    75.8   628.9   75.81   656.2   76.87
     728   77.62   734.5   77.27   742.4   77.61   806.2   77.34   862.5   78.32
#Mann= 3 , 0 , 0
       0     .17       0   174.5     .06       0   514.1     .17       0
Bank Sta=174.5,514.1
XS Rating Curve= 0 ,0
Exp/Cntr=0.3,0.1

Type RM Length L Ch R = 1 ,22000   ,504,504,504
BEGIN DESCRIPTION:
Crystal Creek 056 44.0
END DESCRIPTION:
XS GIS Cut Line= 3
      3885067.85     10026411.06      3884965.83     10026139.27
      3884806.79     10025585.14
#Sta/Elev= 30
  4709.7   78.54  4724.8   78.35  4763.1   76.06  4795.1   75.24  4880.6   72.62
  4912.6   70.95  4948.2   70.57  4948.6   70.07  4952.9   70.07  4953.3   70.57
  4956.1   70.71    5046   70.69    5071   71.46  5091.8    72.7  5118.7   74.05
  5152.4   74.55  5157.6   74.33  5181.2   75.09  5216.6    76.2  5247.8   76.27
    5279   77.06  5310.2   76.97  5320.6   76.36  5336.6   76.95  5409.3   75.56
  5424.7   75.73  5455.9   77.17  5497.5    77.8  5554.6   77.72  5576.5   78.38
#Mann= 6 ,-1 , 0
  4709.7     .17       0  4795.1     .08       0  4880.6     .06       0
  5091.8     .08       0  5152.4     .15       0  5181.2     .17       0
Bank Sta=4880.6,5091.8
XS Rating Curve= 0 ,0
Exp/Cntr=0.3,0.1

Type RM Length L Ch R = 1 ,21500   ,627,627,627
BEGIN DESCRIPTION:
Crystal Creek 056 43.0
END DESCRIPTION:
XS GIS Cut Line= 4
      3885573.06     10026947.51      3885371.09     10026081.69
      3885265.03     10025950.07      3884907.69     10025475.45
#Sta/Elev= 30
  3941.9   79.81  4031.6    77.2    4082   76.85  4153.9   77.81  4246.1   76.63
  4277.1   77.59    4349   76.13  4431.7   76.93  4451.7   76.01  4516.7   75.53
  4554.2   74.37    4616   75.34    4657   74.38  4718.6   74.61  4855.5   75.24
  4919.5   73.33  4940.3   71.52  4961.1   70.97  4989.9   70.45    4994   69.71
  5039.7   70.96  5104.3    71.3  5133.4   72.16  5154.2   73.65  5247.9   74.79
  5311.7   75.88  5383.3   75.76  5474.9    78.2  5505.8   78.08  5594.1   77.87
#Mann= 7 ,-1 , 0
  3941.9     .11       0  4031.6     .17       0  4718.6     .08       0
  4961.1     .06       0  5039.7     .08       0  5247.9     .17       0
  5505.8     .11       0
Bank Sta=4961.1,5039.7
XS Rating Curve= 0 ,0
Exp/Cntr=0.3,0.1

Type RM Length L Ch R = 1 ,20873   ,233,233,233
BEGIN DESCRIPTION:
Crystal Creek 056 42.0
END DESCRIPTION:
XS GIS Cut Line= 3
       3885942.5     10025655.17      3885601.23     10025574.21
      3884981.76     10025444.25
#Sta/Elev= 30
  3849.9   78.33  4690.577.99104  4728.5   77.06  4775.8   75.96  4855.1   72.02
  4860.3   72.36  4902.5   70.83  4907.9   70.23  4938.7   70.12  4942.1   69.96
  4942.5   69.46  4969.6   70.48  5010.6   70.12  5071.9   70.48  5081.2    71.7
  5102.6   73.19  5153.7   74.98  5174.1   74.84    5181   75.29  5186.1   74.73
  5194.5   75.26  5296.7    76.2    5358   75.51  5419.3   76.17  5439.8    76.9
  5480.6   77.02  5525.1   78.25  5554.9   78.39  5582.8   77.81  5629.9   78.16
#Mann= 5 ,-1 , 0
  3849.9     .17       0  4690.5     .15       0  4728.5     .09       0
  5439.8     .17       0  5554.9     .11       0
Bank Sta=4728.5,5439.8
XS Rating Curve= 0 ,0
Exp/Cntr=0.3,0.1

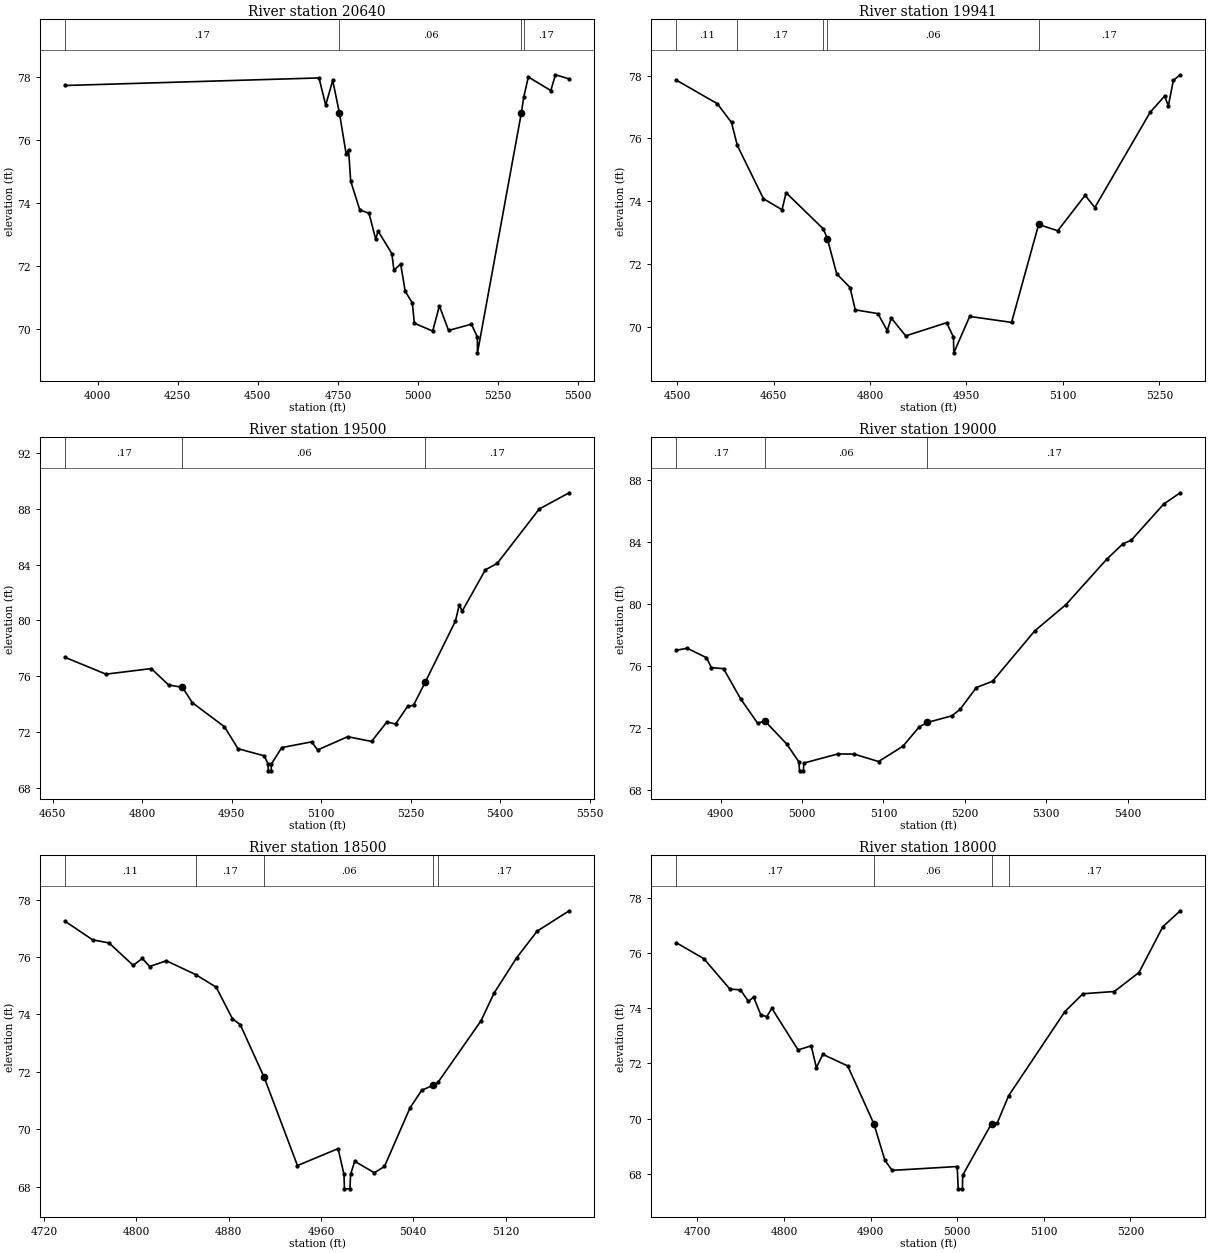
Type RM Length L Ch R = 1 ,20640   ,699,699,699
BEGIN DESCRIPTION:
Crystal Creek 056 41.0
END DESCRIPTION:
XS GIS Cut Line= 3
      3886000.71     10025625.92      3885753.79     10025415.14
      3885392.93     10025115.97
#Sta/Elev= 30
  3899.2   77.73  4690.8   77.97  4711.6   77.11  4733.6   77.89  4754.4   76.86
  4775.3   75.57    4783   75.69  4789.6    74.7  4818.1   73.78  4846.7   73.68
  4867.5   72.86  4875.2   73.11    4918    72.4  4924.6   71.87  4945.5   72.07
  4959.7    71.2  4981.7   70.84  4988.3   70.19  5045.5   69.94  5066.3   70.74
    5095   69.96  5166.2   70.16  5184.8   69.75  5185.2   69.25  5322.1   76.86
  5329.4   77.35  5343.7      78  5414.1   77.57  5428.4   78.07  5471.4   77.94
#Mann= 4 ,-1 , 0
  3899.2     .17       0  4754.4     .06       0  5322.1     .08       0
  5329.4     .17       0
Bank Sta=4754.4,5322.1
XS Rating Curve= 0 ,0
Exp/Cntr=0.3,0.1

Type RM Length L Ch R = 1 ,19941   ,441,441,441
BEGIN DESCRIPTION:
Crystal Creek 056 40.0
END DESCRIPTION:
XS GIS Cut Line= 3
      3886567.83     10025261.05      3886171.76     10024948.56
      3885938.91     10024795.05
#Sta/Elev= 30
  4498.9   77.86  4562.6   77.11  4584.7   76.51  4593.7   75.78  4634.4   74.08
  4663.2   73.73  4669.6   74.27  4727.4   73.12  4733.7   72.81  4748.2   71.69
    4769   71.25  4777.1   70.54  4812.3   70.42  4826.8   69.88  4833.1   70.28
  4855.5   69.71  4919.2   70.13  4929.8   69.67  4930.3   69.17    4955   70.33
  5020.1   70.14  5062.2   73.26  5091.9   73.06  5134.5   74.19  5149.5    73.8
  5235.7   76.84    5258   77.35  5263.9   77.04  5271.6   77.85  5282.3   78.03
#Mann= 5 ,-1 , 0
  4498.9     .11       0  4593.7     .17       0  4727.4     .08       0
  4733.7     .06       0  5062.2     .17       0
Bank Sta=4733.7,5062.2
XS Rating Curve= 0 ,0
Exp/Cntr=0.3,0.1

Type RM Length L Ch R = 1 ,19500   ,500,500,500
BEGIN DESCRIPTION:
Crystal Creek 056 39.0
END DESCRIPTION:
XS GIS Cut Line= 3
      3886590.88     10024976.44      3886460.13     10024674.97
      3886417.85     10024161.11
#Sta/Elev= 30
  4671.4   77.34  4739.5   76.14  4815.4   76.54  4844.3   75.37  4867.7   75.19
  4884.3   74.09  4938.1   72.36  4960.7   70.79  5004.5   70.28  5011.1    69.7
  5011.6    69.2  5016.3    69.2  5016.8    69.7    5034   70.87    5084   71.28
  5094.2    70.7  5144.4   71.65  5184.5   71.31  5210.2   72.71  5224.7   72.56
  5244.7   73.82  5254.8   73.91  5274.8    75.6    5325   79.95  5331.3   81.09
  5336.4   80.67  5375.2   83.63  5395.2    84.1  5465.5      88  5515.6   89.16
#Mann= 3 , 0 , 0
  4671.4     .17       0  4867.7     .06       0  5274.8     .17       0
Bank Sta=4867.7,5274.8
XS Rating Curve= 0 ,0
Exp/Cntr=0.3,0.1

Type RM Length L Ch R = 1 ,19000   ,500,500,500
BEGIN DESCRIPTION:
Crystal Creek 056 38.0
END DESCRIPTION:
XS GIS Cut Line= 3
      3886758.58      10024911.9       3886846.4     10024785.03
      3886857.02     10024320.75
#Sta/Elev= 30
  4845.7   77.01  4859.1   77.14  4882.7   76.53  4888.8   75.89  4903.7   75.82
  4924.6   73.88  4945.6    72.3  4954.4   72.45  4981.4   70.95  4996.2   69.81
    4997   69.23  5001.8   69.23  5002.2   69.73    5044   70.32    5064   70.31
    5094   69.83    5124   70.82    5144   72.07    5154   72.35    5184   72.78
    5194   73.19    5214    74.6    5234   75.01  5285.6   78.25    5324   79.95
  5374.1   82.88  5394.1   83.88  5404.1    84.1  5444.1   86.44  5464.4   87.17
#Mann= 3 , 0 , 0
  4845.7     .17       0  4954.4     .06       0    5154     .17       0
Bank Sta=4954.4,5154
XS Rating Curve= 0 ,0
Exp/Cntr=0.3,0.1

Type RM Length L Ch R = 1 ,18500   ,500,500,500
BEGIN DESCRIPTION:
Crystal Creek 056 37.0
END DESCRIPTION:
XS GIS Cut Line= 3
      3886955.15     10025241.38      3887158.53     10025077.16
      3887198.67     10024906.72
#Sta/Elev= 30
  4738.6   77.24  4762.2    76.6  4776.5   76.49  4797.4   75.71  4805.3   75.95
  4811.7   75.67  4826.1   75.87  4851.5   75.39  4869.3   74.95  4883.4   73.85
  4890.1   73.65  4910.9   71.81  4939.7   68.74  4974.9   69.33    4980   68.43
  4980.4   67.93  4985.2   67.93  4985.7   68.43  4989.3   68.89  5006.3   68.49
  5015.1   68.71  5037.1   70.74  5047.3   71.36  5057.5   71.54  5061.5   71.64
  5098.7   73.78  5110.1   74.75  5129.5   75.97  5147.3    76.9  5175.1   77.61
#Mann= 5 ,-1 , 0
  4738.6     .11       0  4851.5     .17       0  4910.9     .06       0
  5057.5     .15       0  5061.5     .17       0
Bank Sta=4910.9,5057.5
XS Rating Curve= 0 ,0
Exp/Cntr=0.3,0.1

Type RM Length L Ch R = 1 ,18000   ,401,401,401
BEGIN DESCRIPTION:
Crystal Creek 056 36.0
END DESCRIPTION:
XS GIS Cut Line= 3
      3887196.08     10025513.48      3887467.74     10025336.36
      3887663.19     10025168.72
#Sta/Elev= 30
  4675.7   76.38  4707.6    75.8  4737.5    74.7  4749.8   74.67    4759   74.25
  4764.9   74.41  4773.3   73.76  4780.1    73.7    4786      74  4816.3   72.49
  4831.4   72.64  4837.4   71.85  4844.9   72.33  4873.6   71.91  4903.8   69.81
  4916.6   68.48  4924.9   68.12    5000   68.26  5001.2   67.45    5006   67.45
  5006.4   67.95  5039.7   69.82  5046.4   69.85  5059.4   70.83  5124.3   73.88
  5145.2   74.53  5181.4   74.61  5209.9    75.3  5237.4   76.96  5257.5   77.54
#Mann= 4 ,-1 , 0
  4675.7     .17       0  4903.8     .06       0  5039.7     .15       0
  5059.4     .17       0
Bank Sta=4903.8,5039.7
XS Rating Curve= 0 ,0
Exp/Cntr=0.3,0.1

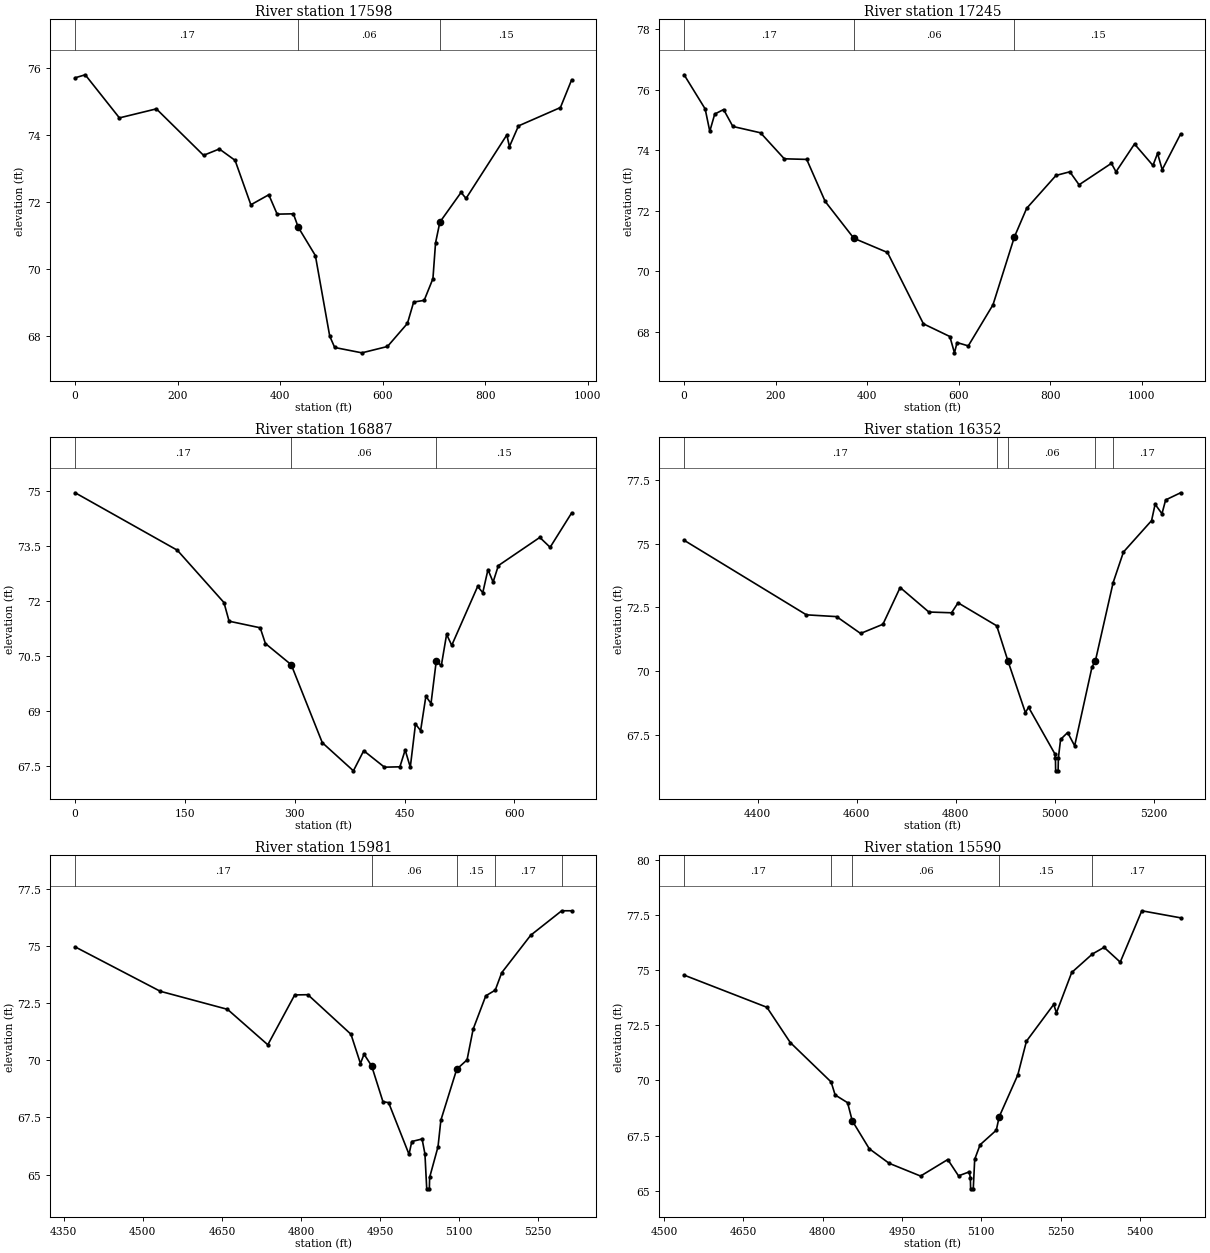
Type RM Length L Ch R = 1 ,17598   ,360,360,360
XS GIS Cut Line= 3
      3887023.73     10025740.46      3887575.15     10025613.78
      3887658.39     10025219.47
#Sta/Elev= 30
       0   75.72    19.6   75.81    86.3   74.52   158.4   74.79   250.5    73.4
   281.3   73.59     312   73.25   342.8   71.92   377.8   72.22   394.1   71.64
   425.8   71.65   435.2   71.25   468.7    70.4   496.7   67.99   506.4   67.65
   559.5   67.49   609.4   67.68   648.3   68.37   660.5   69.01     681   69.06
   698.1   69.71   703.2   70.78   711.6    71.4     753   72.29   762.7   72.11
   842.3   74.01   847.4   73.66     865   74.28   946.9   74.83   968.8   75.66
#Mann= 3 , 0 , 0
       0     .17       0   435.2     .06       0   711.6     .15       0
Bank Sta=435.2,711.6
XS Rating Curve= 0 ,0
Exp/Cntr=0.3,0.1

Type RM Length L Ch R = 1 ,17245   ,359,359,359
XS GIS Cut Line= 2
      3887861.04     10026406.66      3887718.98     10025331.17
#Sta/Elev= 30
       0    76.5      46   75.37    56.1   74.63    66.9    75.2    86.3   75.35
   106.5   74.79     167   74.58   218.9   73.72   267.9    73.7   308.2   72.31
   370.9   71.09   444.4   70.62   522.9   68.26   580.6   67.84   590.7    67.3
   596.4   67.64   620.9   67.53   674.9   68.89   721.8   71.14   748.4   72.08
   812.6   73.17   842.8   73.29     863   72.86   933.6   73.57   943.7   73.29
   984.1   74.21  1024.4    73.5  1034.5    73.9  1044.6   73.36  1084.8   74.54
#Mann= 3 , 0 , 0
       0     .17       0   370.9     .06       0   721.8     .15       0
Bank Sta=370.9,721.8
XS Rating Curve= 0 ,0
Exp/Cntr=0.3,0.1

Type RM Length L Ch R = 1 ,16887   ,534,534,534
XS GIS Cut Line= 2
      3888213.75     10025802.48      3887729.61     10025327.69
#Sta/Elev= 30
       0   74.96   139.5   73.39   203.2   71.96   210.2   71.45   252.7   71.27
   259.8   70.84   295.1   70.26   337.5   68.13     380   67.36   394.1   67.91
   422.4   67.46   443.5   67.47   450.7   67.93   457.7   67.46   464.8   68.64
   471.8   68.46     479    69.4     486    69.2   493.1   70.35   500.1   70.24
   507.3   71.09   514.3   70.79   549.7    72.4   556.7   72.23   563.8   72.86
   570.8   72.52     578   72.97   634.6   73.74   648.7   73.47   678.1   74.41
#Mann= 3 , 0 , 0
       0     .17       0   295.1     .06       0   493.1     .15       0
Bank Sta=295.1,493.1
XS Rating Curve= 0 ,0
Exp/Cntr=0.3,0.1

Type RM Length L Ch R = 1 ,16352   ,371,371,371
BEGIN DESCRIPTION:
Crystal Creek 056 33.0
END DESCRIPTION:
XS GIS Cut Line= 4
      3888246.03     10025768.49      3888112.34     10025271.92
      3887968.24     10025086.86      3887779.66     10024916.56
#Sta/Elev= 30
  4251.2   75.13  4498.2   72.21  4559.2   72.14  4607.7   71.48  4652.8   71.84
  4687.6   73.28  4745.6   72.32  4791.4   72.29  4804.6   72.68  4882.7   71.78
  4905.4    70.4  4940.6   68.38    4947   68.59    5000   66.77  5001.3    66.6
  5001.7    66.1  5006.7    66.1  5007.2    66.6  5011.7   67.33  5025.9    67.6
  5040.1   67.08  5075.2   70.17  5081.9    70.4  5117.8   73.47  5138.7   74.67
  5195.5    75.9  5202.6   76.54  5216.5   76.17  5223.9   76.71  5254.1   76.99
#Mann= 5 ,-1 , 0
  4251.2     .17       0  4882.7     .08       0  4905.4     .06       0
  5081.9     .08       0  5117.8     .17       0
Bank Sta=4905.4,5081.9
XS Rating Curve= 0 ,0
Exp/Cntr=0.3,0.1

Type RM Length L Ch R = 1 ,15981   ,391,391,391
BEGIN DESCRIPTION:
Crystal Creek 056 32.0
END DESCRIPTION:
XS GIS Cut Line= 3
       3888259.9      10025749.3      3888162.69     10025266.71
      3888321.33     10024846.23
#Sta/Elev= 30
  4371.6   74.96    4533   73.02  4660.5   72.23    4737   70.68    4788   72.86
    4813   72.87  4894.7   71.14  4912.7   69.86  4919.5   70.27    4934   69.75
  4955.4   68.19  4966.1   68.15  5004.8   65.89  5010.1   66.45  5029.6   66.56
    5035   65.91  5038.4   64.38  5043.4   64.38  5043.9   64.88  5059.8   66.22
  5065.2   67.38  5095.3   69.61  5114.9   70.02  5126.4   71.36  5150.4   72.82
  5168.4   73.07  5180.6   73.83  5235.6   75.47  5294.4   76.54  5313.3   76.54
#Mann= 5 ,-1 , 0
  4371.6     .17       0    4934     .06       0  5095.3     .15       0
  5168.4     .17       0  5294.4     .11       0
Bank Sta=4934,5095.3
XS Rating Curve= 0 ,0
Exp/Cntr=0.3,0.1

Type RM Length L Ch R = 1 ,15590   ,590,590,590
BEGIN DESCRIPTION:
Crystal Creek 056 31.0
END DESCRIPTION:
XS GIS Cut Line= 3
      3888280.74     10025766.71      3888449.14     10025339.63
      3888357.13     10024869.12
#Sta/Elev= 30
  4538.1   74.78  4694.6   73.32  4738.8   71.72    4816   69.93  4823.6   69.34
  4847.1   68.99  4855.9   68.17  4888.1    66.9  4925.6   66.24  4985.1   65.66
  5036.5   66.41  5056.8   65.67  5077.1   65.85  5079.2   65.58  5079.7   65.08
  5084.7   65.08  5087.4   66.42  5097.6   67.08  5128.2   67.74  5133.7   68.35
  5168.9   70.25  5185.2   71.78  5236.8   73.45  5241.9   73.07  5270.8    74.9
    5310   75.74    5332   76.04  5362.5   75.37  5403.3    77.7  5476.6   77.38
#Mann= 5 ,-1 , 0
  4538.1     .17       0    4816     .15       0  4855.9     .06       0
  5133.7     .15       0    5310     .17       0
Bank Sta=4855.9,5133.7
XS Rating Curve= 0 ,0
Exp/Cntr=0.3,0.1

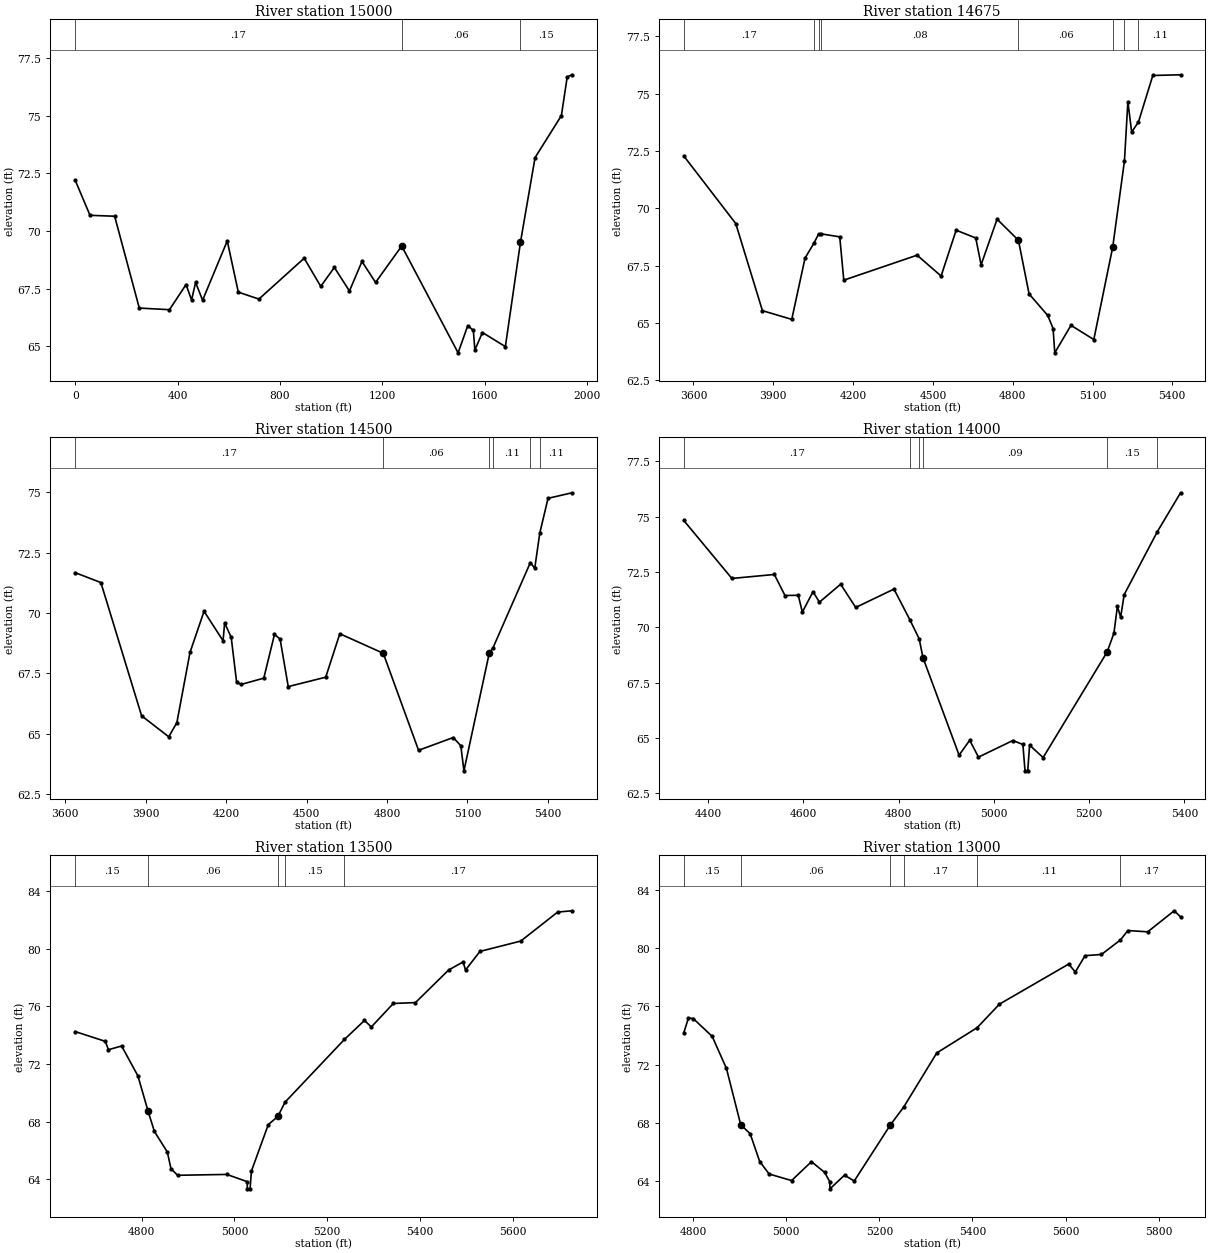
Type RM Length L Ch R = 1 ,15000   ,325,325,325
XS GIS Cut Line= 3
      3890077.46     10025852.28      3888804.97     10025120.13
      3888390.12     10024891.71
#Sta/Elev= 30
       0    72.2    57.8   70.68   154.1   70.64   250.3   66.66   368.2   66.59
   432.9   67.68   454.4   67.01   470.2   67.77   497.5      67   593.8   69.57
     637   67.35   717.4   67.05   894.2   68.82   958.9    67.6    1012   68.42
    1071    67.4  1119.9   68.68    1173   67.77  1275.1   69.35  1495.3   64.72
  1533.1    65.9  1554.9   65.69  1560.6   64.84  1590.4    65.6  1679.9   64.99
  1738.8   69.51  1795.8   73.18  1898.6      75  1921.4   76.68  1940.1   76.77
#Mann= 3 , 0 , 0
       0     .17       0  1275.1     .06       0  1738.8     .15       0
Bank Sta=1275.1,1738.8
XS Rating Curve= 0 ,0
Exp/Cntr=0.3,0.1

Type RM Length L Ch R = 1 ,14675   ,175,175,175
BEGIN DESCRIPTION:
Mapping XS e11ed770
END DESCRIPTION:
XS GIS Cut Line= 3
      3890262.81     10024958.67      3888865.31     10024859.48
      3888487.44     10024585.61
#Sta/Elev= 30
  3563.4   72.29  3758.9   69.34  3859.1   65.54  3969.4   65.16  4019.2   67.83
  4052.4  68.478  4070.6   68.89  4079.7   68.89  4149.8   68.76    4165   66.87
  4440.6   67.96  4530.8   67.05  4587.4   69.05  4661.1   68.71  4681.2   67.54
  4741.3   69.53  4821.5   68.61  4861.6   66.27  4931.8   65.33  4951.8   64.76
  4958.1    63.7  5019.1    64.9  5104.9   64.28  5176.1   68.32  5220.1   72.07
    5233   74.66  5247.2   73.33  5272.7   73.77  5326.8    75.8  5431.1   75.83
#Mann= 8 ,-1 , 0
  3563.4     .17       0  4052.4     .15       0  4070.6     .17       0
  4079.7     .08       0  4821.5     .06       0  5176.1     .08       0
  5220.1     .17       0  5272.7     .11       0
Bank Sta=4821.5,5176.1
XS Rating Curve= 0 ,0
Exp/Cntr=0.3,0.1

Type RM Length L Ch R = 1 ,14500   ,500,500,500
BEGIN DESCRIPTION:
Crystal Creek 056 29.0
END DESCRIPTION:
XS GIS Cut Line= 3
      3890252.42     10024934.37      3888906.39     10024718.71
      3888557.68     10024374.75
#Sta/Elev= 30
  3636.8   71.67  3732.6   71.26  3884.5   65.74  3985.8   64.87  4016.1   65.46
  4065.1   68.37  4117.4   70.07  4188.3   68.85  4194.2   69.59  4218.7   68.99
    4239   67.12  4256.1   67.04  4340.2    67.3  4380.1   69.11    4401   68.92
  4431.4   66.95  4571.2   67.34  4623.8   69.14  4785.8   68.33  4917.5   64.31
  5046.8   64.84  5075.1    64.5  5086.7   63.46  5181.1   68.33  5195.2   68.56
  5334.5   72.09  5350.8   71.85  5369.6   73.31  5400.4   74.75  5489.8   74.98
#Mann= 6 ,-1 , 0
  3636.8     .17       0  4785.8     .06       0  5181.1     .08       0
  5195.2     .11       0  5334.5     .17       0  5369.6     .11       0
Bank Sta=4785.8,5181.1
XS Rating Curve= 0 ,0
Exp/Cntr=0.3,0.1

Type RM Length L Ch R = 1 ,14000   ,500,500,500
BEGIN DESCRIPTION:
Crystal Creek 056 28.0
END DESCRIPTION:
XS GIS Cut Line= 4
      3889809.85     10024298.81      3889483.11     10024464.43
      3889220.44     10024354.66      3888954.81     10024066.65
#Sta/Elev= 30
    4349   74.83    4450   72.21  4539.1   72.39  4561.4   71.44  4589.3   71.45
  4597.9   70.69  4620.3   71.61  4633.8   71.14  4678.3   71.95  4709.9    70.9
  4790.2   71.73  4823.9   70.33  4843.2   69.48  4851.1   68.63  4926.9   64.23
  4949.2    64.9  4967.6   64.14  5039.8   64.89  5060.8   64.71  5065.3   63.52
    5071   63.52  5074.9   64.68  5103.3   64.12  5237.7   68.89  5251.9   69.74
  5259.2   70.95    5266   70.46  5273.4   71.48  5343.2   74.33  5391.8   76.08
#Mann= 6 ,-1 , 0
    4349     .17       0  4823.9     .15       0  4843.2     .12       0
  4851.1     .09       0  5237.7     .15       0  5343.2     .17       0
Bank Sta=4851.1,5237.7
XS Rating Curve= 0 ,0
Exp/Cntr=0.3,0.1

Type RM Length L Ch R = 1 ,13500   ,500,500,500
BEGIN DESCRIPTION:
Crystal Creek 056 27.0
END DESCRIPTION:
XS GIS Cut Line= 3
       3889709.6     10024230.39        3889485.      10023970.1
      3889246.65      10023281.8
#Sta/Elev= 30
  4656.2   74.24  4721.3   73.56  4727.9   72.98  4756.4   73.24  4791.5   71.17
  4813.4   68.73    4827   67.32  4855.1   65.88  4862.8   64.74    4877   64.27
  4983.4   64.33  5027.3   63.83  5027.8   63.33  5033.6   63.33  5036.6   64.57
    5073   67.79  5093.6   68.35    5109   69.34  5237.4    73.7  5280.5   75.01
  5295.3   74.56  5342.8   76.19  5390.5   76.25  5462.1   78.51  5493.3   79.07
  5498.6   78.51  5529.7    79.8  5617.9   80.52  5697.4   82.53  5728.4   82.62
#Mann= 5 ,-1 , 0
  4656.2     .15       0  4813.4     .06       0  5093.6     .17       0
    5109     .15       0  5237.4     .17       0
Bank Sta=4813.4,5093.6
XS Rating Curve= 0 ,0
Exp/Cntr=0.3,0.1

Type RM Length L Ch R = 1 ,13000   ,550,550,550
BEGIN DESCRIPTION:
Crystal Creek 056 26.0
END DESCRIPTION:
XS GIS Cut Line= 3
      3889913.16     10024110.98      3889870.06     10023895.04
      3889306.47     10023262.76
#Sta/Elev= 30
  4779.8   74.19  4789.9    75.2  4800.1   75.17  4840.9   73.94  4871.5   71.73
  4902.1   67.86  4922.5   67.23  4942.9   65.32  4963.3   64.46  5011.4   64.01
  5054.1   65.31  5082.5   64.57  5093.3   63.94  5093.8   63.44  5125.1   64.38
    5146   63.98  5223.8   67.85  5252.2   69.07  5323.3    72.8  5410.1   74.54
  5457.9   76.16  5606.7   78.92  5620.9   78.37  5641.8    79.5    5677   79.58
  5717.8   80.58  5733.8   81.23  5776.4   81.14  5833.3   82.59    5847   82.17
#Mann= 6 ,-1 , 0
  4779.8     .15       0  4902.1     .06       0  5223.8     .08       0
  5252.2     .17       0  5410.1     .11       0  5717.8     .17       0
Bank Sta=4902.1,5223.8
XS Rating Curve= 0 ,0
Exp/Cntr=0.3,0.1