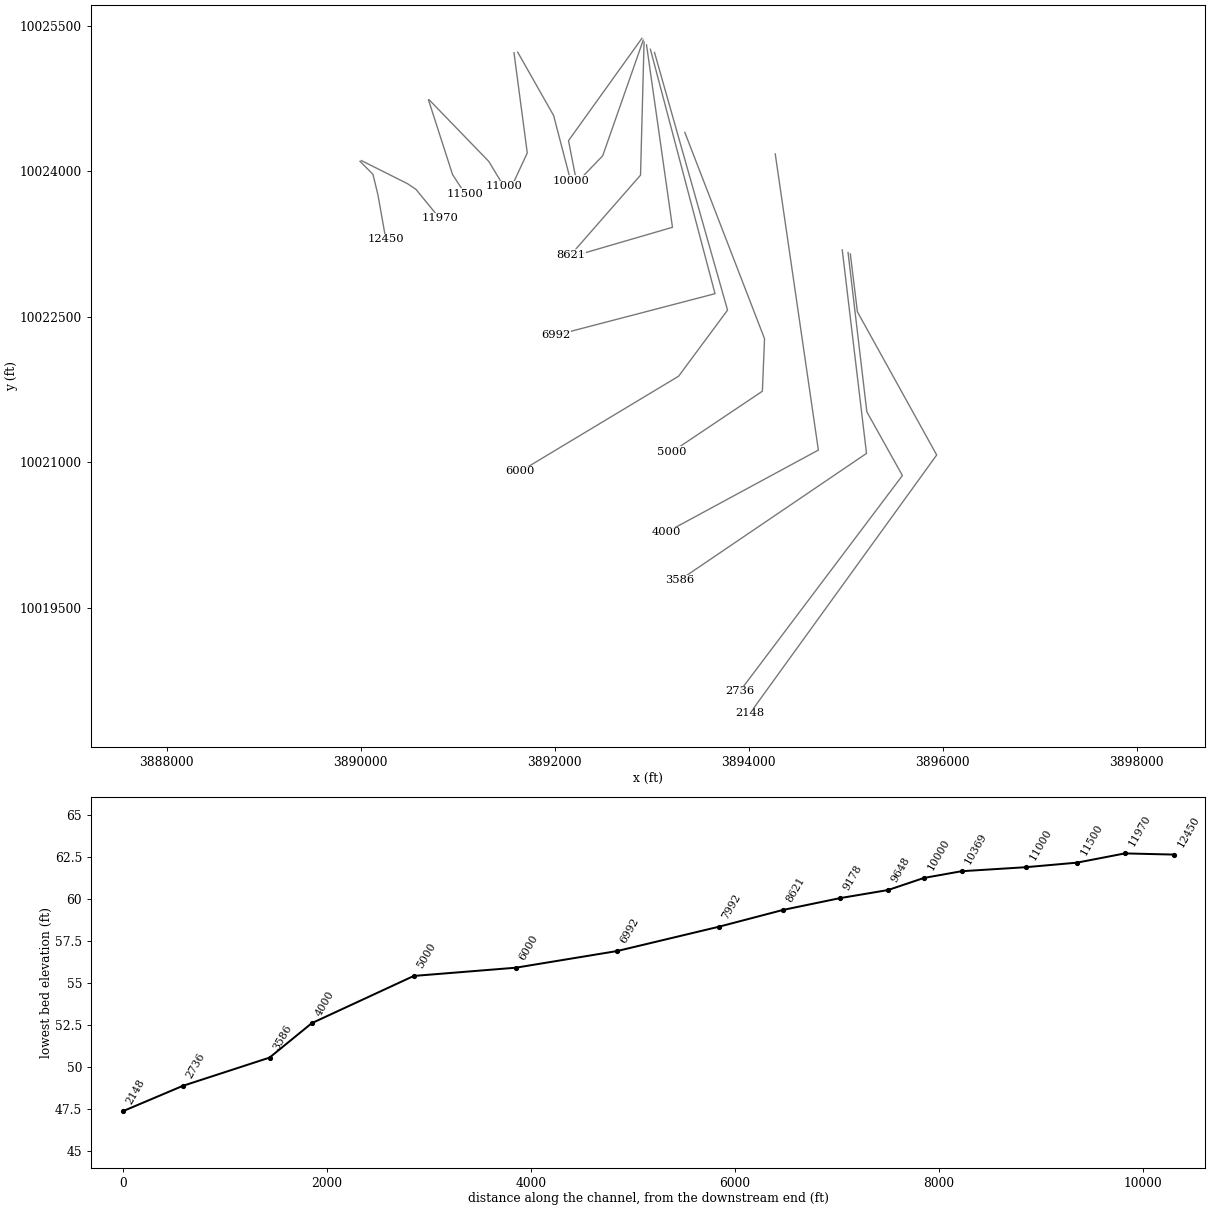
HEC-RAS study Crystal Creek 056.prj: Crystal Creek 056 Base Level Engineering

--- Crystal Creek 056.g01 (geometry) --- (continued)

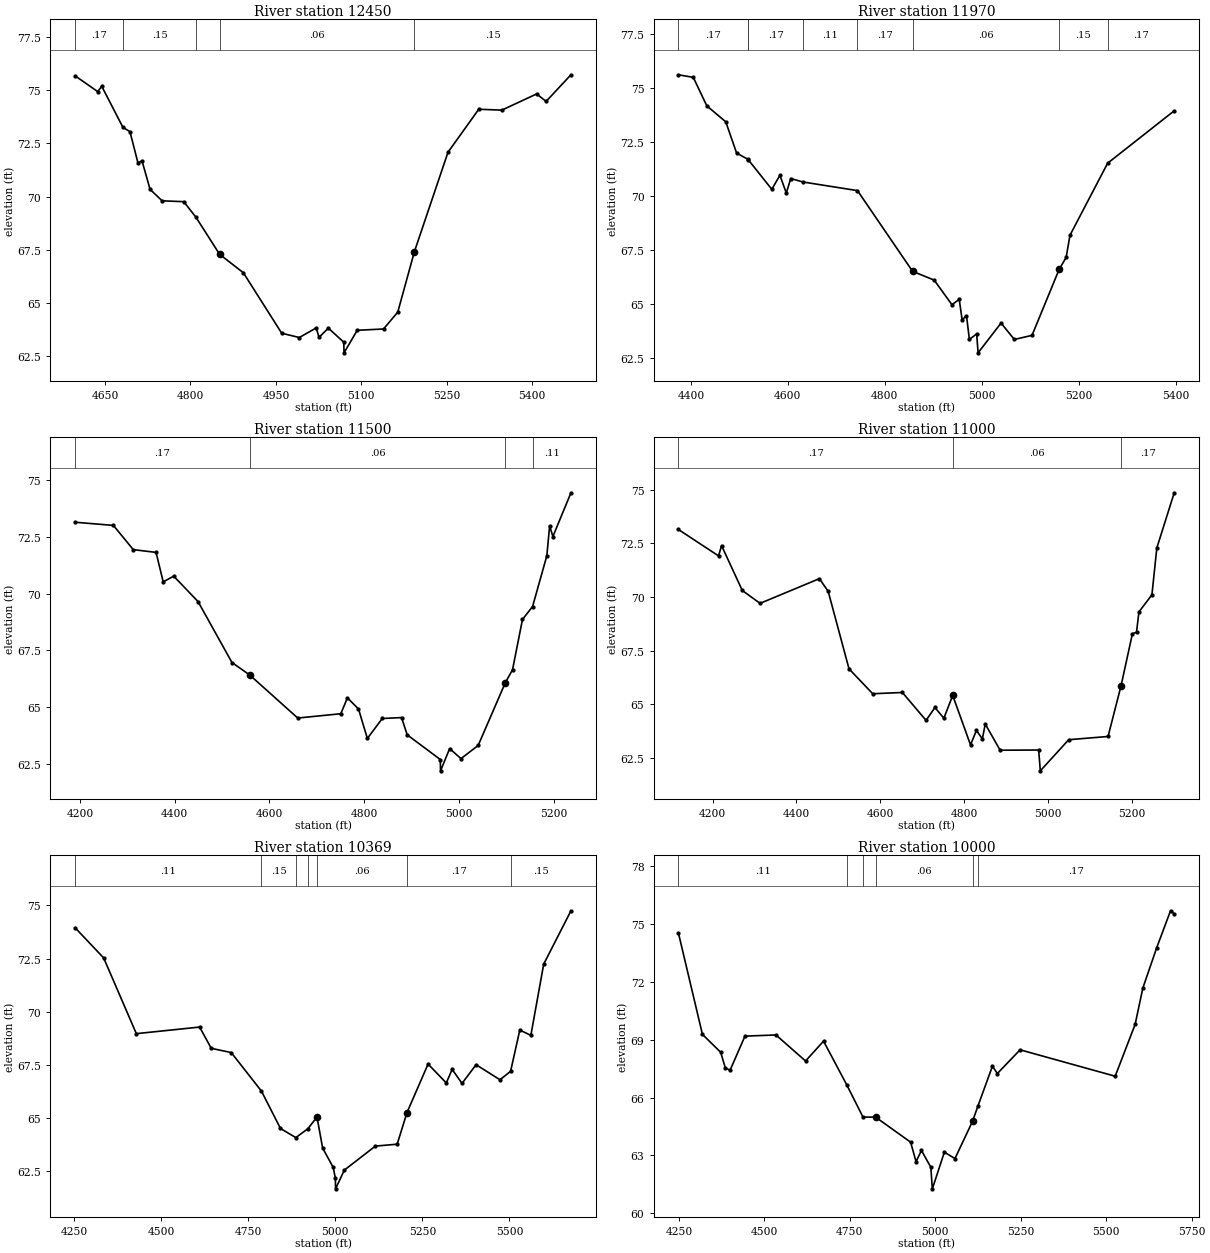
Type RM Length L Ch R = 1 ,12450   ,480,480,480
BEGIN DESCRIPTION:
Crystal Creek 056 25.0
END DESCRIPTION:
XS GIS Cut Line= 4
      3889994.53     10024103.76      3890127.73     10023970.38
      3890179.46     10023757.38      3890260.19     10023301.67
#Sta/Elev= 30
  4597.5   75.67  4637.1   74.93  4644.2   75.18  4681.4   73.25  4693.7   73.05
  4707.8   71.58  4714.9   71.68    4729   70.34  4750.2    69.8  4788.2   69.76
  4809.8   69.02  4851.1   67.29  4892.9   66.42  4960.2   63.58  4991.1   63.38
  5020.7   63.83  5025.7   63.39  5042.1   63.82  5069.1   63.16  5069.6   62.66
  5092.8   63.72  5138.9   63.78  5163.9   64.57    5193    67.4  5252.1   72.08
  5306.1    74.1  5346.7   74.06  5407.7   74.82  5424.4   74.47    5468   75.72
#Mann= 5 ,-1 , 0
  4597.5     .17       0  4681.4     .15       0  4809.8     .17       0
  4851.1     .06       0    5193     .15       0
Bank Sta=4851.1,5193
XS Rating Curve= 0 ,0
Exp/Cntr=0.3,0.1

Type RM Length L Ch R = 1 ,11970   ,470,470,470
BEGIN DESCRIPTION:
Crystal Creek 056 24.0
END DESCRIPTION:
XS GIS Cut Line= 4
      3890008.87     10024111.55      3890484.15     10023873.26
      3890571.39     10023814.67      3890815.83     10023515.62
#Sta/Elev= 30
  4374.3   75.62    4405    75.5  4432.9   74.18    4472   73.44  4494.4   71.99
  4517.1   71.71  4518.9   71.67    4567   70.31  4583.7   70.96  4596.9   70.14
  4606.1   70.81  4631.3   70.65  4743.8   70.25  4857.4   66.51  4902.1    66.1
  4938.7   64.96  4953.7   65.21  4959.7   64.26  4968.7   64.45  4974.7   63.35
  4989.7   63.61  4992.6   62.73    5040   64.11  5067.4   63.35  5103.9   63.54
  5159.9    66.6  5174.3   67.15  5182.2   68.18  5259.9   71.52  5397.3   73.95
#Mann= 8 ,-1 , 0
  4374.3     .17       0  4517.1     .15       0  4518.9     .17       0
  4631.3     .11       0  4743.8     .17       0  4857.4     .06       0
  5159.9     .15       0  5259.9     .17       0
Bank Sta=4857.4,5159.9
XS Rating Curve= 0 ,0
Exp/Cntr=0.3,0.1

Type RM Length L Ch R = 1 ,11500   ,500,500,500
BEGIN DESCRIPTION:
Crystal Creek 056 23.0
END DESCRIPTION:
XS GIS Cut Line= 3
      3890700.28     10024737.88      3890948.86     10023966.86
      3891077.88     10023769.13
#Sta/Elev= 30
  4189.9   73.15  4270.6   73.01  4312.6   71.94  4360.6   71.82  4375.7   70.52
  4397.9   70.77  4449.2   69.65  4520.8   66.96  4558.2   66.41  4659.6   64.51
  4750.5    64.7  4764.4    65.4  4787.8   64.91  4806.5   63.61    4838   64.49
  4878.7   64.53  4890.5   63.77  4960.4   62.68  4960.9   62.18  4980.1   63.16
  5004.1   62.72  5040.3    63.3  5097.6   66.07  5112.8   66.64  5133.8   68.86
  5155.1   69.43  5185.2   71.67  5191.1   72.99    5198   72.52  5236.1   74.45
#Mann= 4 ,-1 , 0
  4189.9     .17       0  4558.2     .06       0  5097.6     .15       0
  5155.1     .11       0
Bank Sta=4558.2,5097.6
XS Rating Curve= 0 ,0
Exp/Cntr=0.3,0.1

Type RM Length L Ch R = 1 ,11000   ,631,631,631
BEGIN DESCRIPTION:
Crystal Creek 056 22.0
END DESCRIPTION:
XS GIS Cut Line= 3
      3890708.54     10024737.33      3891321.31     10024103.79
      3891477.29     10023845.54
#Sta/Elev= 30
  4118.6   73.15  4214.4   71.92  4221.6    72.4    4271   70.31  4313.5   69.71
  4454.9   70.86    4476   70.27  4525.7   66.66  4582.3    65.5    4653   65.56
  4709.6   64.26  4730.7   64.86    4752   64.36  4773.2   65.42  4815.6   63.12
  4829.7   63.79  4843.9    63.4  4850.8   64.09  4886.3   62.87  4978.2   62.88
  4982.2   61.91  5049.9   63.36  5143.8   63.51  5174.8   65.87    5202    68.3
  5211.7   68.36  5217.5   69.31  5248.5   70.11  5260.2   72.29  5301.7   74.86
#Mann= 3 , 0 , 0
  4118.6     .17       0  4773.2     .06       0  5174.8     .17       0
Bank Sta=4773.2,5174.8
XS Rating Curve= 0 ,0
Exp/Cntr=0.3,0.1

Type RM Length L Ch R = 1 ,10369   ,369,369,369
BEGIN DESCRIPTION:
Crystal Creek 056 21.0
END DESCRIPTION:
XS GIS Cut Line= 3
      3891581.81     10025225.14      3891718.96     10024190.45
      3891559.23     10023846.69
#Sta/Elev= 30
  4253.6   73.95  4335.5   72.53  4429.2   68.97  4610.8   69.28  4644.1   68.28
  4701.6   68.08  4788.1   66.27  4842.8   64.51  4886.8   64.08  4921.7    64.5
  4947.6   65.05  4963.8   63.59  4994.1   62.68  5000.4   62.17  5000.9   61.67
    5026   62.55  5115.1   63.68  5177.7   63.77  5205.9   65.26  5266.4   67.54
  5318.7   66.65  5335.4   67.29  5363.8   66.63  5404.1   67.51  5472.8    66.8
  5503.2    67.2  5529.6   69.14  5561.3   68.89  5598.2   72.24  5676.4   74.75
#Mann= 7 ,-1 , 0
  4253.6     .11       0  4788.1     .15       0  4886.8     .17       0
  4921.7     .15       0  4947.6     .06       0  5205.9     .17       0
  5503.2     .15       0
Bank Sta=4947.6,5205.9
XS Rating Curve= 0 ,0
Exp/Cntr=0.3,0.1

Type RM Length L Ch R = 1 ,10000   ,352,352,352
BEGIN DESCRIPTION:
Crystal Creek 056 20.0
END DESCRIPTION:
XS GIS Cut Line= 3
      3891619.98     10025230.42      3891990.33     10024576.86
      3892166.87     10023900.53
#Sta/Elev= 30
  4248.8   74.54  4319.1   69.28  4372.5   68.35    4386   67.54  4399.9   67.42
  4443.5   69.19  4534.1   69.25  4620.7    67.9  4673.3   68.93  4741.6   66.65
  4788.7   64.99  4825.5   64.99    4928   63.69  4943.9   62.68  4959.7   63.26
  4987.1   62.39  4991.5   61.27  5026.7   63.17  5057.7   62.84  5109.3   64.78
  5125.2   65.58  5167.3   67.63  5181.7   67.25  5248.2   68.48  5526.3   67.11
  5584.7    69.8  5607.2   71.68  5647.7   73.77  5688.2   75.69    5699   75.53
#Mann= 6 ,-1 , 0
  4248.8     .11       0  4741.6     .17       0  4788.7     .11       0
  4825.5     .06       0  5109.3     .15       0  5125.2     .17       0
Bank Sta=4825.5,5109.3
XS Rating Curve= 0 ,0
Exp/Cntr=0.3,0.1

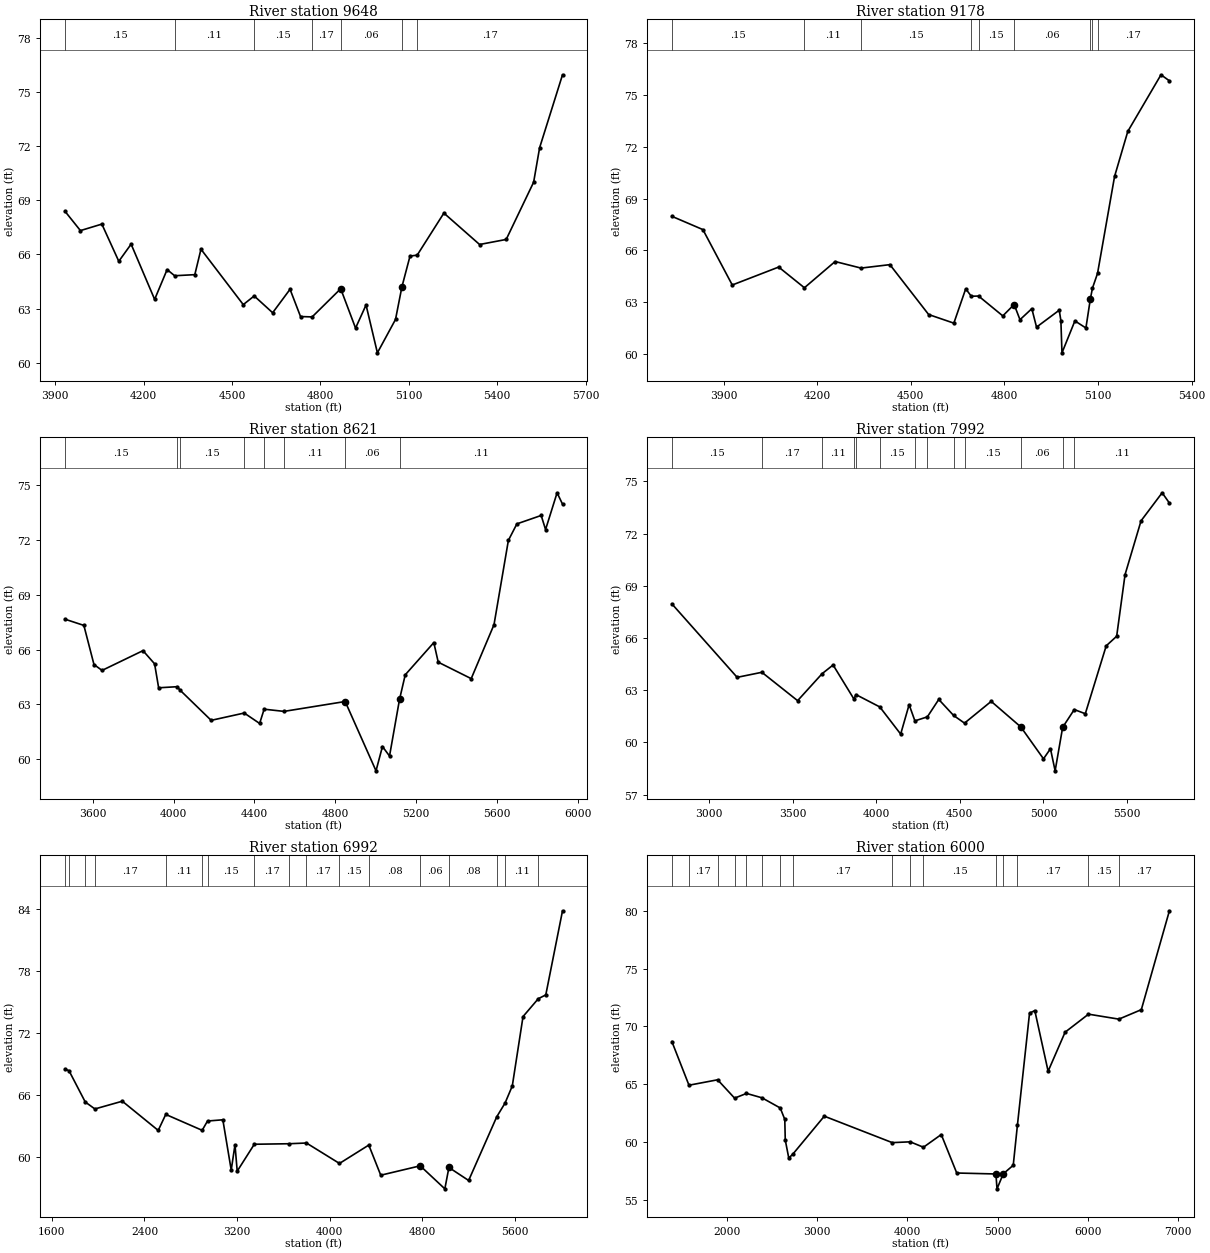
Type RM Length L Ch R = 1 ,9648    ,470,470,470
BEGIN DESCRIPTION:
Crystal Creek 056 19.0
END DESCRIPTION:
XS GIS Cut Line= 3
      3892900.46     10025372.74      3892144.13     10024317.19
       3892218.7     10023934.84
#Sta/Elev= 30
  3933.5   68.39  3985.9   67.32  4058.6   67.68  4116.1   65.62  4157.9   66.57
  4237.7   63.51    4280   65.16  4305.6   64.82    4374   64.88  4394.9   66.29
  4538.4   63.22  4575.5    63.7  4638.1   62.77  4697.1   64.07  4732.7   62.56
  4772.1   62.54    4869    64.1  4919.4   61.92    4955    63.2  4993.5   60.55
    5055    62.4  5076.6    64.2  5104.2   65.91  5128.5   65.96  5219.1   68.29
  5340.2   66.55  5430.5   66.83  5523.6      70  5543.9   71.91  5621.6   75.95
#Mann= 7 ,-1 , 0
  3933.5     .15       0  4305.6     .11       0  4575.5     .15       0
  4772.1     .17       0    4869     .06       0  5076.6     .15       0
  5128.5     .17       0
Bank Sta=4869,5076.6
XS Rating Curve= 0 ,0
Exp/Cntr=0.3,0.1

Type RM Length L Ch R = 1 ,9178    ,557,557,557
BEGIN DESCRIPTION:
Crystal Creek 056 18.0
END DESCRIPTION:
XS GIS Cut Line= 3
      3892914.37     10025353.68      3892496.56     10024160.94
      3892267.55     10023923.07
#Sta/Elev= 30
  3734.5   67.98  3833.9   67.21    3928      64  4076.7   65.04  4159.1   63.84
  4257.5   65.36  4340.5   64.98    4433   65.18  4557.1   62.29  4637.9   61.79
  4675.9   63.78  4693.7   63.35  4717.2   63.36  4794.7   62.21    4831   62.87
  4849.8   61.99  4887.7   62.63  4902.8   61.56  4975.5   62.54  4980.8   61.94
  4984.3   60.07  5025.7   61.92    5061   61.51  5075.1   63.18    5082   63.82
  5098.2   64.67  5152.8   70.29  5195.2    72.9  5301.5   76.18  5328.5   75.83
#Mann= 9 ,-1 , 0
  3734.5     .15       0  4159.1     .11       0  4340.5     .15       0
  4693.7     .17       0  4717.2     .15       0    4831     .06       0
  5075.1     .08       0    5082     .15       0  5098.2     .17       0
Bank Sta=4831,5075.1
XS Rating Curve= 0 ,0
Exp/Cntr=0.3,0.1

Type RM Length L Ch R = 1 ,8621    ,629,629,629
BEGIN DESCRIPTION:
Crystal Creek 056 17.0
END DESCRIPTION:
XS GIS Cut Line= 4
      3892923.04     10025334.57      3892886.58     10023961.29
       3892777.2     10023836.29      3892169.34     10023141.01
#Sta/Elev= 30
  3461.7   67.66  3555.2   67.32  3605.3   65.18  3645.3   64.86  3847.9   65.94
  3905.4   65.22  3925.4   63.91  4018.1   63.97  4029.7    63.8  4185.5   62.13
  4349.2   62.53  4425.5   61.96  4447.7   62.74  4546.2   62.62    4849   63.16
  5001.7   59.37  5033.5    60.7  5068.6   60.18    5118   63.27  5146.4   64.62
  5287.9   66.38  5309.7   65.31    5473   64.41  5585.9   67.36  5657.1   71.97
  5699.2   72.87  5819.4   73.33  5841.2   72.56  5898.2   74.57  5925.1   73.95
#Mann= 8 ,-1 , 0
  3461.7     .15       0  4018.1     .11       0  4029.7     .15       0
  4349.2     .11       0  4447.7     .15       0  4546.2     .11       0
    4849     .06       0    5118     .11       0
Bank Sta=4849,5118
XS Rating Curve= 0 ,0
Exp/Cntr=0.3,0.1

Type RM Length L Ch R = 1 ,7992    ,1000,1000,1000
BEGIN DESCRIPTION:
Crystal Creek 056 16.0
END DESCRIPTION:
XS GIS Cut Line= 3
      3892948.38      10025305.3      3893215.75     10023423.32
      3892185.16     10023122.74
#Sta/Elev= 30
  2778.8   67.96    3169   63.74  3316.8   64.03  3530.5    62.4    3677   63.95
  3742.6   64.45  3867.5   62.49    3879   62.75  4021.8   62.04  4146.6   60.48
  4197.1   62.17  4231.7   61.24  4306.1   61.47  4374.3   62.47  4463.1   61.55
  4528.3   61.11  4687.9   62.36    4865   60.89  5000.4   59.06  5042.1   59.64
    5070   58.37    5115   60.87  5184.5   61.89  5250.4   61.65  5375.4   65.55
  5437.9    66.1    5488   69.64  5583.7   72.73  5709.8   74.34  5753.2   73.75
#Mann= 13 ,-1 , 0
  2778.8     .15       0  3316.8     .17       0    3677     .11       0
  3867.5     .15       0    3879     .11       0  4021.8     .15       0
  4231.7     .11       0  4306.1     .15       0  4463.1     .17       0
  4528.3     .15       0    4865     .06       0    5115     .15       0
  5184.5     .11       0
Bank Sta=4865,5115
XS Rating Curve= 0 ,0
Exp/Cntr=0.3,0.1

Type RM Length L Ch R = 1 ,6992    ,992,992,992
BEGIN DESCRIPTION:
Crystal Creek 056 14.0
END DESCRIPTION:
XS GIS Cut Line= 3
      3892988.46     10025260.14      3893654.69     10022738.43
       3892017.9     10022311.08
#Sta/Elev= 30
  1713.3   68.51  1747.8   68.37  1888.7   65.33    1972   64.66  2208.8   65.41
  2519.1   62.58  2584.2   64.13  2898.8   62.59  2945.1   63.49  3077.6   63.61
    3150   58.74  3182.6   61.19  3201.7   58.63  3349.5   61.24  3650.3   61.29
  3800.1   61.36  4085.6   59.38  4338.9   61.16  4442.3   58.24  4783.4   59.15
  4996.2   56.92  5031.4   58.99  5201.8   57.73  5444.8    63.9  5516.6   65.23
  5579.2   66.89  5671.9   73.61  5803.7   75.34  5868.6   75.71  6013.2   83.86
#Mann= 17 ,-1 , 0
  1713.3     .15       0  1747.8     .11       0  1888.7     .15       0
    1972     .17       0  2584.2     .11       0  2898.8     .17       0
  2945.1     .15       0  3349.5     .17       0  3650.3     .15       0
  3800.1     .17       0  4085.6     .15       0  4338.9     .08       0
  4783.4     .06       0  5031.4     .08       0  5444.8     .17       0
  5516.6     .11       0  5803.7     .17       0
Bank Sta=4783.4,5031.4
XS Rating Curve= 0 ,0
Exp/Cntr=0.3,0.1

Type RM Length L Ch R = 1 ,6000    ,1000,1000,1000
BEGIN DESCRIPTION:
Crystal Creek 056 12.0
END DESCRIPTION:
XS GIS Cut Line= 4
      3893030.76     10025227.06      3893783.65     10022568.67
      3893279.01     10021886.86      3891646.94      10020905.1
#Sta/Elev= 30
  1388.8   68.68  1578.4    64.9  1896.1   65.37  2084.2   63.78  2216.1   64.19
  2387.7   63.81    2590   62.93  2640.6   61.94  2645.8   60.16  2684.9   58.59
  2731.6   58.95  3078.7   62.22    3832   59.93  4031.1      60  4177.7   59.53
  4375.3   60.63  4546.9    57.3 4981.2657.21681  4993.3   55.93  5062.6   57.23
  5173.3   57.97    5220   61.47    5354   71.14  5412.3   71.36  5559.9   66.11
  5748.2   69.49  6007.6   71.05  6344.3   70.62  6593.3   71.44  6904.6      80
#Mann= 16 ,-1 , 0
  1388.8     .11       0  1578.4     .17       0  1896.1     .11       0
  2084.2     .17       0  2216.1     .11       0  2387.7     .17       0
    2590     .15       0  2731.6     .17       0    3832     .15       0
  4031.1     .17       0  4177.7     .15       0 4981.26     .06       0
  5062.6     .15       0    5220     .17       0  6007.6     .15       0
  6344.3     .17       0
Bank Sta=4981.26,5062.6
XS Rating Curve= 0 ,0
Exp/Cntr=0.3,0.1

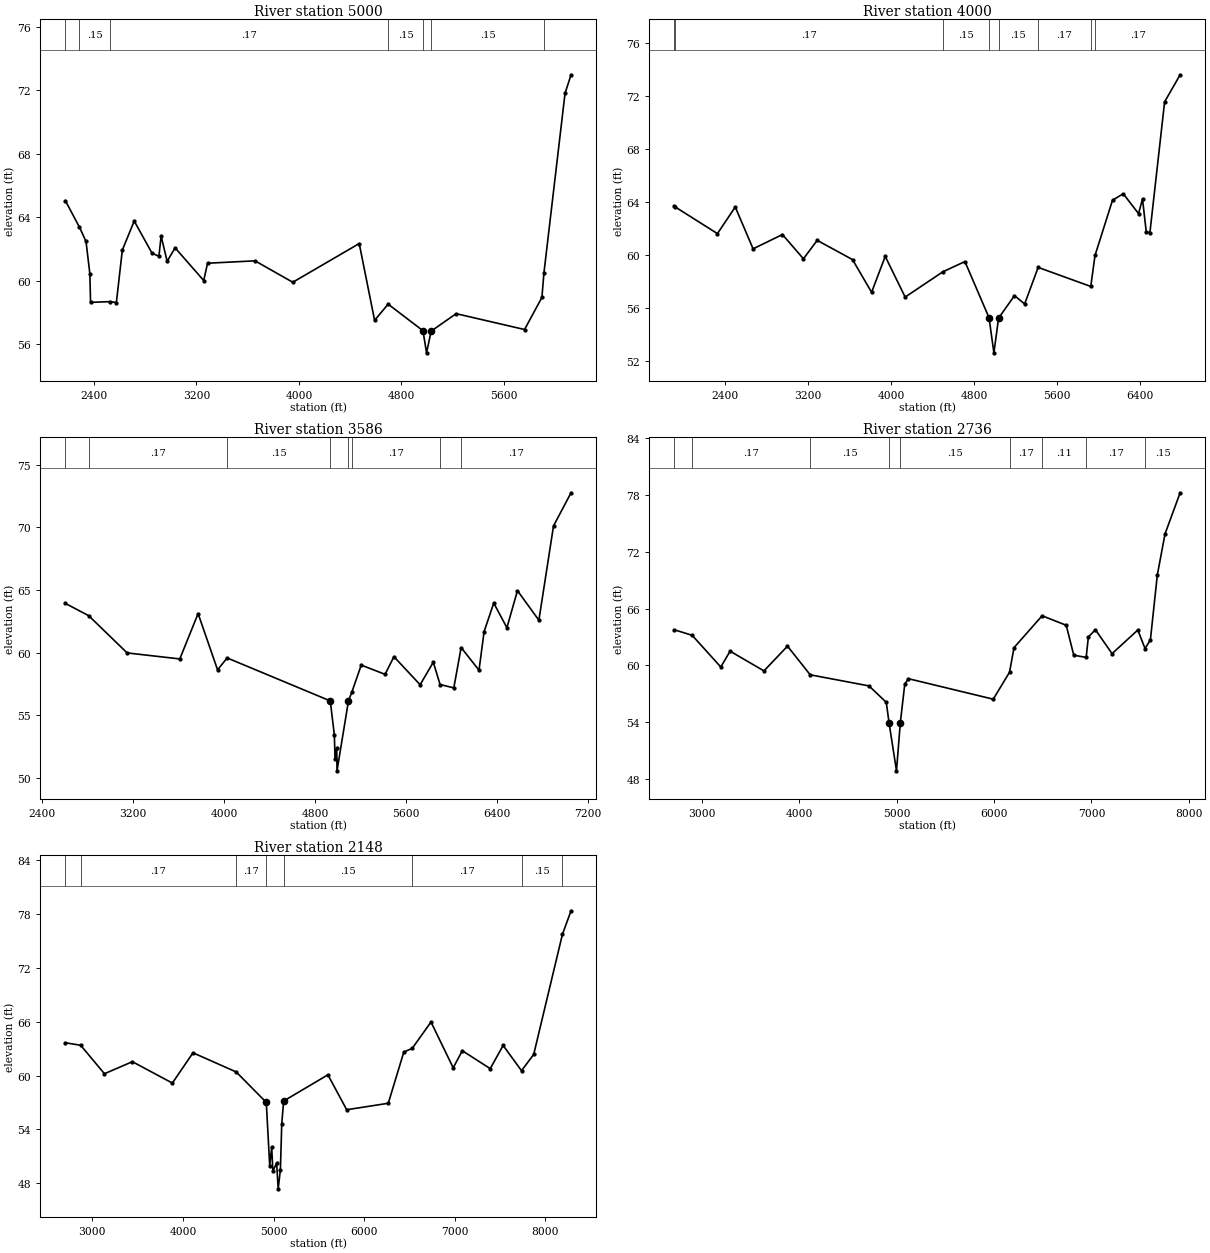
Type RM Length L Ch R = 1 ,5000    ,1000,1000,1000
BEGIN DESCRIPTION:
Crystal Creek 056 10.0
END DESCRIPTION:
XS GIS Cut Line= 4
      3893343.26     10024402.48      3894165.03     10022273.98
      3894142.84     10021732.26      3893208.92     10021105.38
#Sta/Elev= 30
  2176.2   65.03  2286.1   63.36  2337.4   62.46  2367.4   60.42  2372.7   58.62
  2526.7   58.67  2574.3   58.61  2620.9   61.92  2713.7   63.75    2853   61.72
  2906.6   61.53  2923.7    62.8  2970.9   61.21  3032.8   62.06  3256.4      60
  3286.4   61.09    3657   61.24  3951.9   59.89  4470.7   62.33  4590.8   57.49
  4696.5   58.51 4968.6156.83325  4996.4   55.44  5032.6   56.81  5227.6   57.91
  5761.7   56.91  5897.3   58.93    5913   60.47  6077.9    71.8  6124.8   72.97
#Mann= 7 ,-1 , 0
  2176.2     .11       0  2286.1     .15       0  2526.7     .17       0
  4696.5     .15       0 4968.61     .06       0  5032.6     .15       0
    5913     .17       0
Bank Sta=4968.61,5032.6
XS Rating Curve= 0 ,0
Exp/Cntr=0.3,0.1

Type RM Length L Ch R = 1 ,4000    ,414,414,414
BEGIN DESCRIPTION:
Crystal Creek 056 8.0
END DESCRIPTION:
XS GIS Cut Line= 3
       3894275.3     10024180.67      3894720.03     10021125.07
      3893150.46     10020275.39
#Sta/Elev= 30
  1912.2   63.71  1915.8   63.66  2326.1   61.63  2497.9   63.64  2669.7   60.48
  2952.6   61.56  3154.8   59.73  3287.5   61.12  3627.8   59.67  3811.6    57.2
    3943   59.91    4135   56.84  4498.9   58.75    4711   59.52  4943.4   55.28
  4990.2   52.63  5035.4   55.25  5188.5   56.95  5286.5   56.32  5416.6   59.08
  5923.7   57.64  5964.5   59.98  6133.1   64.15  6236.7   64.64  6384.2   63.14
  6422.2   64.25    6458   61.78  6493.5    61.7  6635.3   71.58  6784.8   73.62
#Mann= 8 ,-1 , 0
  1912.2     .11       0  1915.8     .17       0  4498.9     .15       0
  4943.4     .09       0  5035.4     .15       0  5416.6     .17       0
  5923.7     .15       0  5964.5     .17       0
Bank Sta=4943.4,5035.4
XS Rating Curve= 0 ,0
Exp/Cntr=0.3,0.1

Type RM Length L Ch R = 1 ,3586    ,850,850,850
BEGIN DESCRIPTION:
Crystal Creek 056 6.0
END DESCRIPTION:
XS GIS Cut Line= 3
      3894966.19     10023190.61      3895216.43     10021090.72
      3893285.17     10019779.63
#Sta/Elev= 30
    2603   63.94  2808.2   62.96  3146.4   59.99  3609.6   59.51  3770.7   63.13
  3941.9   58.64  4026.1   59.59  4933.6   56.16  4969.5   53.43  4975.6   51.54
  4990.5   52.42  4992.8   50.58 5093.67 56.1605  5125.3   56.91  5206.1   59.02
  5415.7   58.28  5493.6   59.69  5724.2   57.45  5840.1   59.25  5899.5   57.47
  6020.5    57.2    6085   60.42  6242.2   58.61    6287   61.69  6371.9   63.97
  6487.7      62  6580.5   64.96  6769.1    62.6  6897.9   70.13    7052   72.77
#Mann= 8 ,-1 , 0
    2603     .11       0  2808.2     .17       0  4026.1     .15       0
  4933.6     .09       0 5093.67     .15       0  5125.3     .17       0
  5899.5     .15       0    6085     .17       0
Bank Sta=4933.6,5093.67
XS Rating Curve= 0 ,0
Exp/Cntr=0.3,0.1

Type RM Length L Ch R = 1 ,2736    ,588,588,588
BEGIN DESCRIPTION:
Crystal Creek 056 4.0
END DESCRIPTION:
XS GIS Cut Line= 4
      3895026.03     10023163.39       3895219.7     10021520.21
      3895586.36     10020862.23      3893911.85     10018638.62
#Sta/Elev= 30
  2719.2   63.76    2901   63.18  3194.8   59.84  3290.3   61.51  3637.8   59.43
  3879.5   62.04  4112.6   59.02  4716.2   57.85  4893.7   56.12  4922.3   53.95
  4998.6    48.9 5037.8853.98218  5083.5   58.03  5121.2   58.61  5991.6   56.45
  6159.1   59.29    6205   61.88  6493.7   65.24  6741.2   64.24  6818.4   61.09
  6945.9   60.85  6968.6   63.01    7041   63.77  7211.8   61.25  7476.2   63.74
  7550.1   61.79  7605.3    62.7  7676.1   69.51  7755.2   73.86  7910.6    78.2
#Mann= 9 ,-1 , 0
  2719.2     .11       0    2901     .17       0  4112.6     .15       0
  4922.3     .09       0 5037.88     .15       0  6159.1     .17       0
  6493.7     .11       0  6945.9     .17       0  7550.1     .15       0
Bank Sta=4922.3,5037.88
XS Rating Curve= 0 ,0
Exp/Cntr=0.3,0.1

Type RM Length L Ch R = 1 ,2148    ,0,0,0
BEGIN DESCRIPTION:
Crystal Creek 056 2.0
END DESCRIPTION:
XS GIS Cut Line= 4
      3895049.56      10023148.7      3895122.48     10022551.46
      3895939.96      10021074.4      3894014.16     10018408.74
#Sta/Elev= 30
  2703.5   63.66  2872.2   63.38  3134.3   60.21  3442.8   61.55  3883.5   59.17
  4111.4   62.54  4587.7   60.41  4919.8   57.02  4957.6   49.98  4979.4   52.01
  4992.4   49.39    5034   50.24    5051   47.39  5075.7   49.54  5090.4   54.63
  5111.3   57.17  5599.5   60.09  5806.8    56.2  6265.6   56.92  6437.3   62.63
  6529.4   63.03  6736.9   65.97  6981.9   60.87  7082.4   62.77  7390.4   60.78
  7532.7   63.36  7735.5   60.55    7870   62.36  8186.7   75.73  8281.9   78.36
#Mann= 8 ,-1 , 0
  2703.5     .11       0  2872.2     .17       0  4587.7     .17       0
  4919.8     .09       0  5111.3     .15       0  6529.4     .17       0
  7735.5     .15       0  8186.7     .17       0
Bank Sta=4919.8,5111.3
XS Rating Curve= 0 ,0
Exp/Cntr=0.3,0.1

Chan Stop Cuts=-1
Use User Specified Reach Order=0
Composite Channel Slope=5

--- Crystal Creek 056.g10 (geometry) ---

Geom Title=Existing Conditions
Program Version=4.10

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
River Reach=Crystal Creek 05,Reach-1

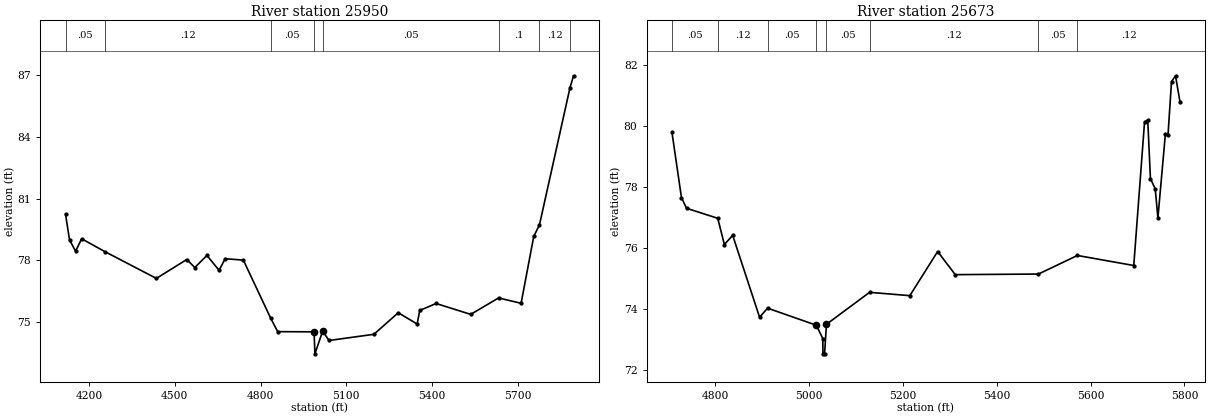
Type RM Length L Ch R = 1 ,25950   ,277,277,277
BEGIN DESCRIPTION:
Crystal Creek 056 52.0
END DESCRIPTION:
XS GIS Cut Line= 3
      3882440.32     10026883.38      3883069.67     10026270.31
      3883447.71     10025454.66
#Sta/Elev= 30
  4117.6   80.25  4131.6      79  4152.9   78.44    4174   79.05  4255.9   78.42
  4435.6   77.12  4541.8   78.04  4570.1   77.65  4612.5   78.24    4655   77.51
  4676.1   78.08  4739.9   78.01  4835.3   75.19    4860   74.53  4987.3   74.52
  4990.3   73.45  5017.4   74.56  5039.5    74.1  5196.6    74.4  5281.9   75.45
  5348.1    74.9    5357   75.56  5414.2    75.9  5535.4   75.37  5632.9   76.17
  5711.7   75.91  5755.9   79.16    5776   79.73  5882.6   86.39  5895.2   86.98
#Mann= 8 ,-1 , 0
  4117.6     .05       0  4255.9     .12       0  4835.3     .05       0
  4987.3     .03       0  5017.4     .05       0  5632.9      .1       0
    5776     .12       0  5882.6     .05       0
Bank Sta=4987.3,5017.4
XS Rating Curve= 0 ,0
Exp/Cntr=0.3,0.1

Type RM Length L Ch R = 1 ,25673   ,673,673,673
BEGIN DESCRIPTION:
Crystal Creek 056 51.0
END DESCRIPTION:
XS GIS Cut Line= 3
      3883197.93     10026629.47      3883317.72      10026362.1
      3883706.19     10025675.34
#Sta/Elev= 30
  4708.6   79.79  4728.8   77.65  4739.7    77.3  4806.1   76.97  4820.2   76.11
  4837.9   76.41  4895.2   73.72  4912.1   74.02    5016   73.46  5029.9   73.02
  5030.1   72.52  5033.6   72.52  5037.6   73.49  5129.5   74.54  5215.2   74.43
  5274.4   75.88  5311.9   75.12  5489.1   75.14  5572.1   75.75  5692.1   75.42
  5715.1   80.14  5721.9   80.19  5727.6   78.27  5737.8   77.94  5743.5   76.98
  5759.4   79.73  5765.1   79.72  5772.5   81.46    5781   81.65  5790.6   80.79
#Mann= 8 ,-1 , 0
  4708.6     .05       0  4806.1     .12       0  4912.1     .05       0
    5016     .03       0  5037.6     .05       0  5129.5     .12       0
  5489.1     .05       0  5572.1     .12       0
Bank Sta=5016,5037.6
XS Rating Curve= 0 ,0
Exp/Cntr=0.3,0.1