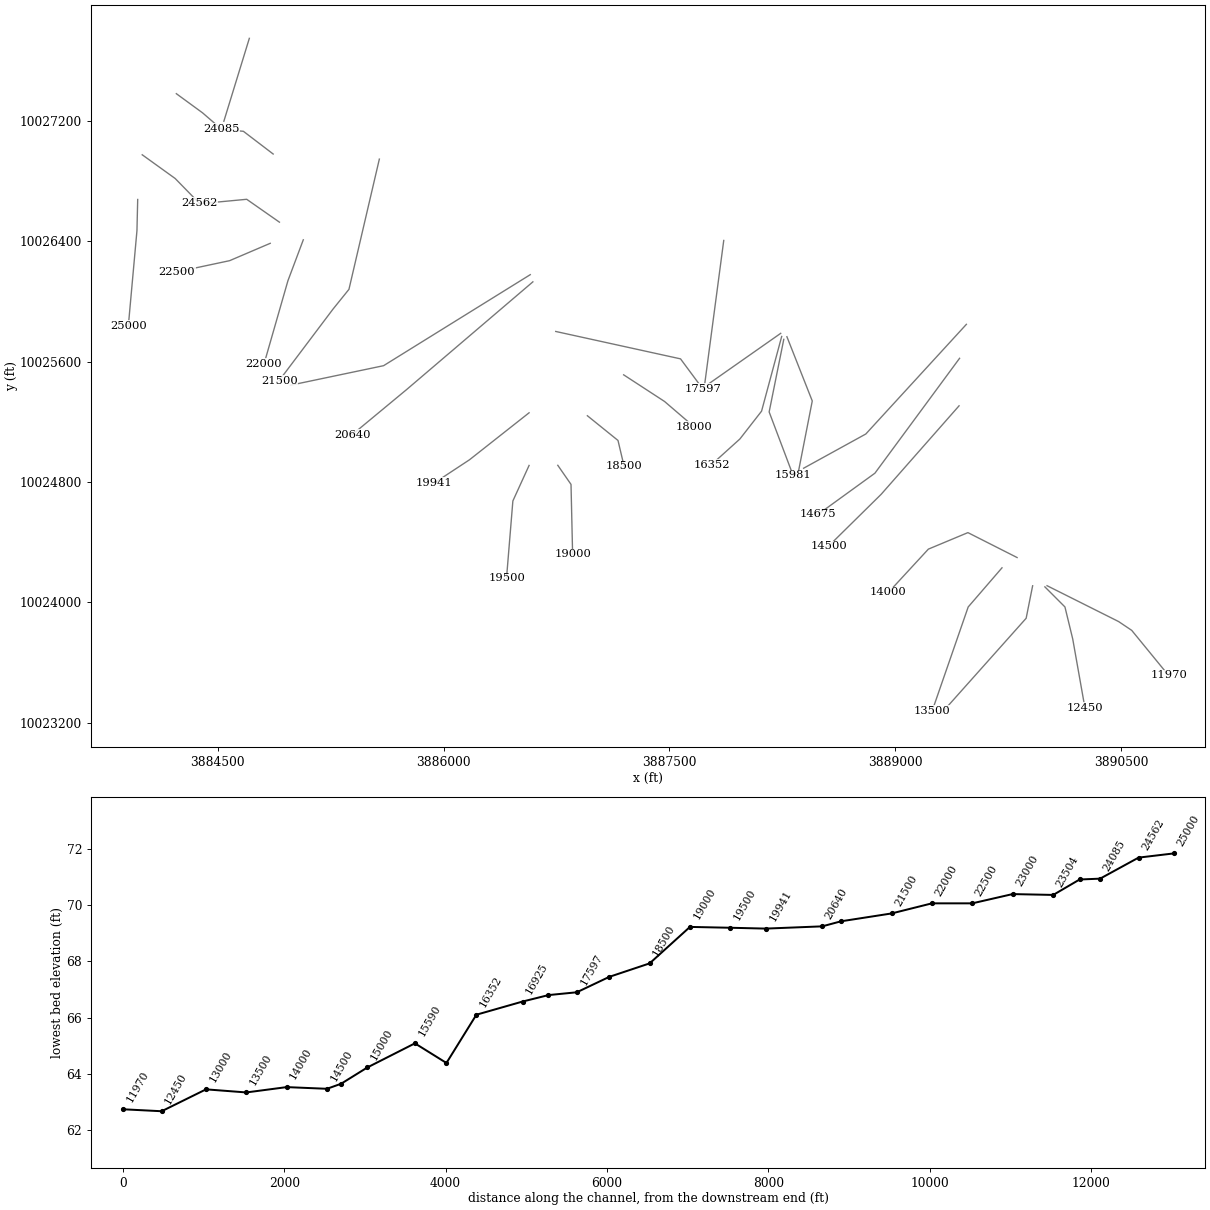
HEC-RAS study Crystal Creek 056.prj: Crystal Creek 056 Base Level Engineering

--- Crystal Creek 056.g10 (geometry) --- (continued)

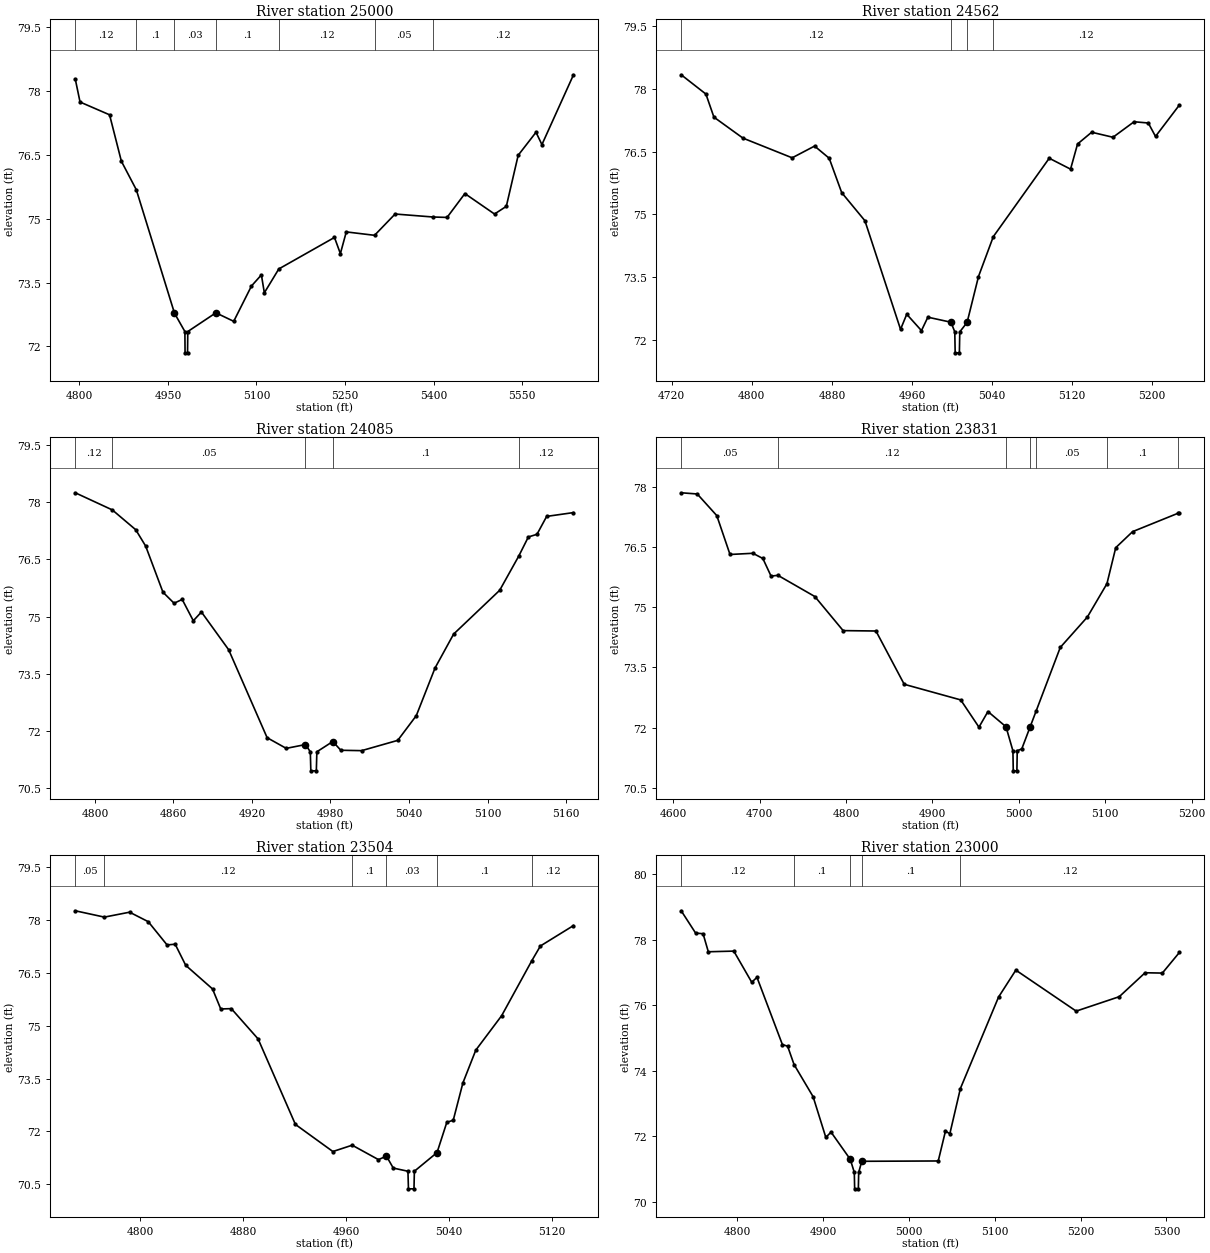
Type RM Length L Ch R = 1 ,25000   ,438,438,438
BEGIN DESCRIPTION:
Crystal Creek 056 50.0
END DESCRIPTION:
XS GIS Cut Line= 3
      3883967.68     10026679.14      3883962.77     10026472.19
      3883905.39     10025837.78
#Sta/Elev= 30
    4793   78.28  4801.1   77.74  4851.1   77.44  4871.1   76.35  4896.4   75.68
  4961.1   72.78  4978.7   72.35    4979   71.85  4983.2   71.85  4983.6   72.35
  5031.2   72.79  5061.4   72.59  5091.5   73.42  5108.3   73.68  5113.3   73.26
  5137.8   73.82  5232.1   74.56  5242.1   74.18  5252.1   74.69    5300   74.61
  5334.8   75.11  5399.1   75.04  5422.8   75.03    5453   75.59  5503.2   75.11
  5523.2   75.29  5543.3   76.49  5573.5   77.03  5583.5   76.74    5637   78.38
#Mann= 7 ,-1 , 0
    4793     .12       0  4896.4      .1       0  4961.1     .03       0
  5031.2      .1       0  5137.8     .12       0    5300     .05       0
  5399.1     .12       0
Bank Sta=4961.1,5031.2
XS Rating Curve= 0 ,0
Exp/Cntr=0.3,0.1

Type RM Length L Ch R = 1 ,24562   ,477,477,477
BEGIN DESCRIPTION:
Crystal Creek 056 49.0
END DESCRIPTION:
XS GIS Cut Line= 3
      3883997.82     10026976.26      3884216.59      10026818.7
      3884376.07     10026655.34
#Sta/Elev= 30
  4729.4   78.33  4754.1   77.87  4762.1   77.32  4791.1   76.82  4840.3   76.35
  4862.7   76.63  4877.3   76.34  4889.8   75.52    4913   74.85  4948.6   72.26
  4954.8   72.62  4969.5   72.23  4975.9   72.55    4999   72.43  5002.8    72.2
  5003.2    71.7  5007.4    71.7  5007.8    72.2 5015.11  72.425  5026.5   73.52
  5041.3   74.47  5097.2   76.34  5118.5   76.08  5125.5   76.68  5139.6   76.96
  5160.9   76.84    5182   77.21  5196.2   77.18  5203.4   76.86  5227.3   77.61
#Mann= 4 ,-1 , 0
  4729.4     .12       0    4999     .03       0 5015.11     .12       0
  5041.3     .12       0
Bank Sta=4999,5015.11
XS Rating Curve= 0 ,0
Exp/Cntr=0.3,0.1

Type RM Length L Ch R = 1 ,24085   ,254,254,254
BEGIN DESCRIPTION:
Crystal Creek 056 48.0
END DESCRIPTION:
XS GIS Cut Line= 3
      3884224.41     10027382.49      3884398.88      10027254.9
      3884523.36     10027147.28
#Sta/Elev= 30
    4785   78.25  4813.3    77.8  4831.2   77.28  4838.8   76.85    4852   75.64
  4860.5   75.35  4866.7   75.45  4875.2   74.89  4881.4   75.12  4902.2   74.13
  4931.6   71.82  4946.2   71.54  4960.9   71.64  4964.6   71.45    4965   70.95
  4969.2   70.95  4969.6   71.45  4981.8   71.72  4987.9   71.49  5003.8   71.48
  5031.4   71.75  5045.6    72.4  5059.9   73.65  5074.1   74.54  5109.3   75.69
  5123.9   76.59  5131.2   77.09  5137.8   77.16  5145.2   77.63  5165.7   77.73
#Mann= 5 ,-1 , 0
    4785     .12       0  4813.3     .05       0  4960.9     .03       0
  4981.8      .1       0  5123.9     .12       0
Bank Sta=4960.9,4981.8
XS Rating Curve= 0 ,0
Exp/Cntr=0.3,0.1

Type RM Length L Ch R = 1 ,23831   ,327,327,327
BEGIN DESCRIPTION:
Mapping XS f3d0749d
END DESCRIPTION:
XS GIS Cut Line= 2
      3884709.34     10027750.45      3884540.08     10027199.25
#Sta/Elev= 30
  4609.2   77.86  4627.8   77.83  4650.4   77.29  4665.7   76.32  4692.2   76.35
  4703.7   76.22  4713.2   75.78  4721.1    75.8  4763.9   75.27  4796.6   74.42
  4834.6   74.41  4867.3   73.08  4932.7   72.69  4953.8   72.01  4964.2    72.4
  4985.1   72.02  4993.1   71.42  4993.5   70.92  4997.7   70.92  4998.1   71.42
  5003.4   71.47 5013.12  72.023  5020.1   72.42  5047.9      74  5079.3   74.76
  5101.9   75.59  5112.1   76.49  5131.6   76.89  5184.3   77.35  5185.8   77.35
#Mann= 7 ,-1 , 0
  4609.2     .05       0  4721.1     .12       0  4985.1     .03       0
 5013.12     .12       0  5020.1     .05       0  5101.9      .1       0
  5184.3     .12       0
Bank Sta=4985.1,5013.12
XS Rating Curve= 0 ,0
Exp/Cntr=0.3,0.1

Type RM Length L Ch R = 1 ,23504   ,504,504,504
BEGIN DESCRIPTION:
Crystal Creek 056 47.0
END DESCRIPTION:
XS GIS Cut Line= 3
      3884867.67     10026981.43      3884669.72      10027132.5
      3884532.23     10027144.18
#Sta/Elev= 30
  4749.5   78.27  4772.1   78.09  4791.7   78.23  4806.2   77.96  4820.8    77.3
  4827.1   77.32  4835.3   76.72  4856.1   76.05  4862.5   75.48  4870.7   75.49
  4891.5   74.63  4920.5    72.2  4949.6   71.43  4964.6   71.61    4985    71.2
  4991.2    71.3  4996.5   70.96  5007.9   70.87  5008.3   70.37  5012.6   70.37
  5012.9   70.87  5030.5    71.4  5038.1   72.26  5043.1   72.32  5050.6   73.38
  5060.6   74.31  5080.7   75.29  5104.1   76.85  5110.8   77.27  5136.5   77.85
#Mann= 6 ,-1 , 0
  4749.5     .05       0  4772.1     .12       0  4964.6      .1       0
  4991.2     .03       0  5030.5      .1       0  5104.1     .12       0
Bank Sta=4991.2,5030.5
XS Rating Curve= 0 ,0
Exp/Cntr=0.3,0.1

Type RM Length L Ch R = 1 ,23000   ,500,500,500
BEGIN DESCRIPTION:
Crystal Creek 056 46.0
END DESCRIPTION:
XS GIS Cut Line= 3
      3884909.29     10026528.34      3884691.77      10026680.4
      3884378.07     10026650.73
#Sta/Elev= 30
  4734.6   78.88  4751.4    78.2  4760.1   78.18  4766.2   77.63  4795.9   77.65
  4816.8    76.7  4822.9   76.85  4852.5    74.8  4858.6   74.75  4866.1   74.19
  4888.3   73.21  4903.1   71.97  4909.2   72.13  4931.6    71.3  4936.3    70.9
  4936.7    70.4    4941    70.4  4941.4    70.9    4945   71.24  5034.1   71.25
  5042.5   72.16  5047.6   72.08  5059.9   73.46  5104.4   76.25  5124.5   77.07
  5194.8   75.82    5245   76.26  5275.1   76.99  5295.2   76.98  5315.1   77.61
#Mann= 5 ,-1 , 0
  4734.6     .12       0  4866.1      .1       0  4931.6     .03       0
    4945      .1       0  5059.9     .12       0
Bank Sta=4931.6,4945
XS Rating Curve= 0 ,0
Exp/Cntr=0.3,0.1

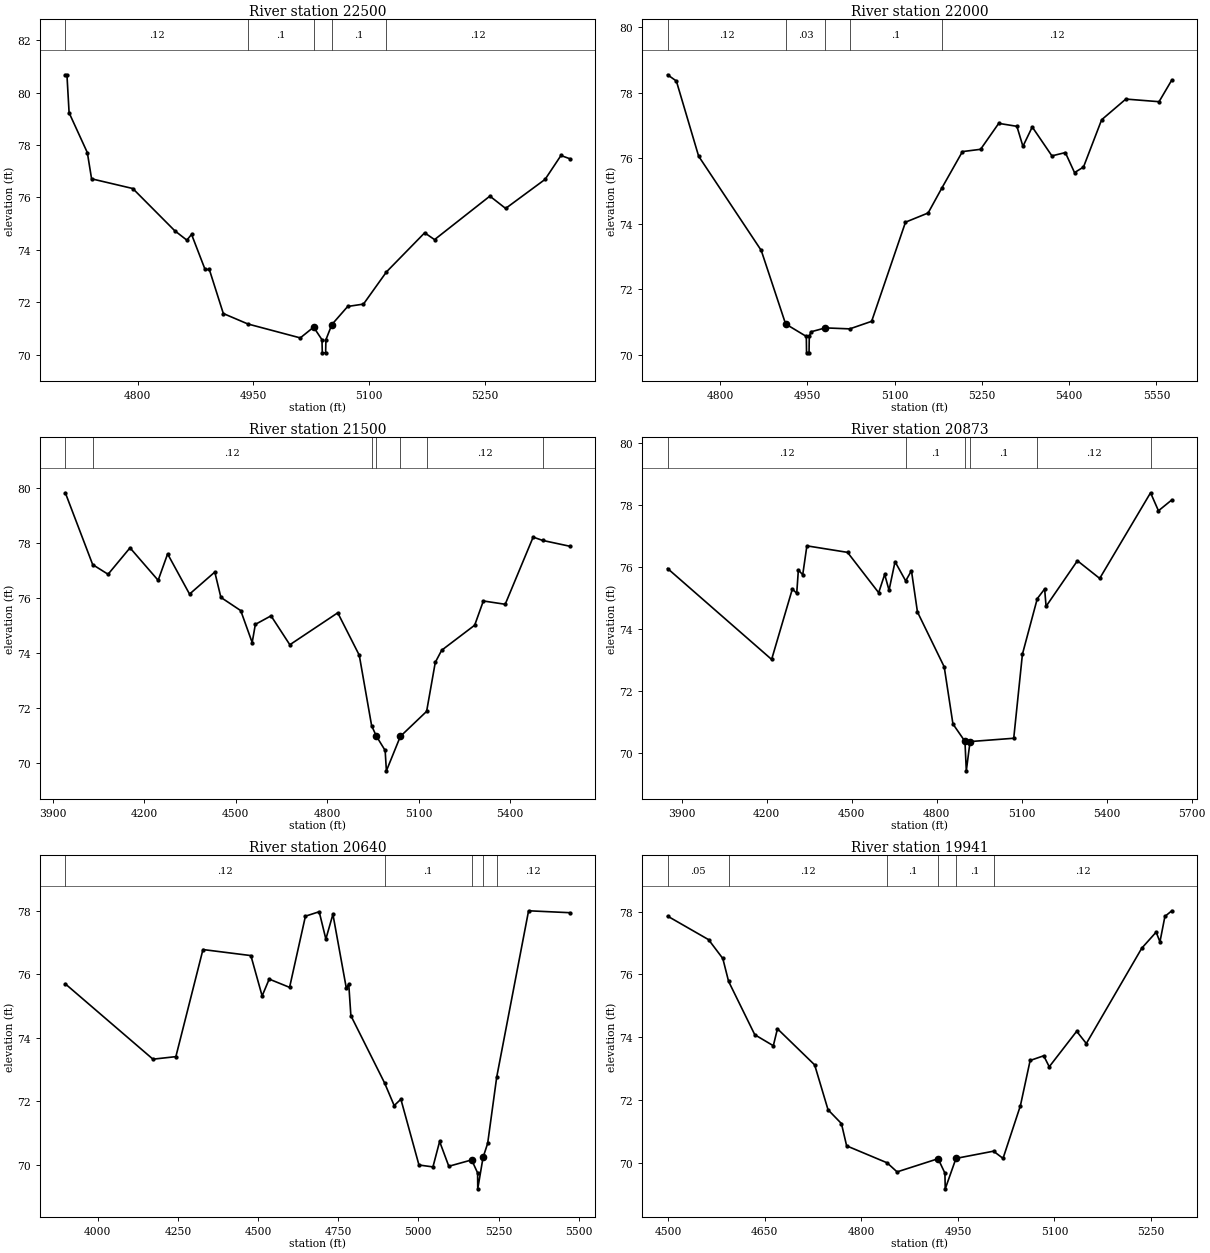
Type RM Length L Ch R = 1 ,22500   ,500,500,500
BEGIN DESCRIPTION:
Crystal Creek 056 45.0
END DESCRIPTION:
XS GIS Cut Line= 3
      3884848.09      10026387.7      3884578.24     10026272.28
      3884226.99      10026197.6
#Sta/Elev= 30
  4706.5   80.68  4708.6   80.68  4711.4   79.23    4735   77.71  4740.5   76.71
  4793.8   76.34  4848.1   74.73  4863.8   74.37  4869.9   74.59  4887.4   73.25
  4892.9   73.25    4911   71.57  4942.9   71.17  5010.6   70.64  5027.9   71.05
  5038.7   70.57  5039.1   70.07  5043.4   70.07  5043.8   70.57  5051.5   71.15
    5072   71.84  5092.4   71.93  5122.2   73.16  5171.6   74.65  5184.4   74.39
    5256   76.05  5276.4   75.58  5327.5   76.69    5348    77.6  5359.1   77.48
#Mann= 5 ,-1 , 0
  4706.5     .12       0  4942.9      .1       0  5027.9     .03       0
  5051.5      .1       0  5122.2     .12       0
Bank Sta=5027.9,5051.5
XS Rating Curve= 0 ,0
Exp/Cntr=0.3,0.1

Type RM Length L Ch R = 1 ,22000   ,500,500,500
BEGIN DESCRIPTION:
Crystal Creek 056 44.0
END DESCRIPTION:
XS GIS Cut Line= 3
      3885067.85     10026411.06      3884965.83     10026139.27
      3884806.79     10025585.14
#Sta/Elev= 30
  4709.7   78.54  4724.8   78.35  4763.1   76.06  4870.7   73.19  4912.6   70.95
  4948.2   70.57  4948.6   70.07  4952.9   70.07  4953.3   70.57  4956.1   70.71
    4981   70.83  5022.9    70.8  5060.5   71.03  5118.7   74.05  5157.6   74.33
  5181.2   75.09  5216.6    76.2  5247.8   76.27    5279   77.06  5310.2   76.97
  5320.6   76.36  5336.6   76.95  5370.4   76.07  5393.5   76.17  5409.3   75.56
  5424.7   75.73  5455.9   77.17  5497.5    77.8  5554.6   77.72  5576.5   78.38
#Mann= 5 ,-1 , 0
  4709.7     .12       0  4912.6     .03       0    4981     .12       0
  5022.9      .1       0  5181.2     .12       0
Bank Sta=4912.6,4981
XS Rating Curve= 0 ,0
Exp/Cntr=0.3,0.1

Type RM Length L Ch R = 1 ,21500   ,627,627,627
BEGIN DESCRIPTION:
Crystal Creek 056 43.0
END DESCRIPTION:
XS GIS Cut Line= 4
      3885573.06     10026947.51      3885371.09     10026081.69
      3885265.03     10025950.07      3884907.69     10025475.45
#Sta/Elev= 30
  3941.9   79.81  4031.6    77.2    4082   76.85  4153.9   77.81  4246.1   76.63
  4277.1   77.59    4349   76.13  4431.7   76.93  4451.7   76.01  4516.7   75.53
  4554.2   74.37  4564.6   75.03    4616   75.34  4677.6   74.29  4834.6   75.45
  4905.1   73.91  4945.6   71.35  4961.1   70.97  4989.9   70.45    4994   69.71
  5039.7   70.96  5125.8   71.87  5154.2   73.65  5175.1   74.09  5283.3      75
  5311.7   75.88  5383.3   75.76  5474.9    78.2  5505.8   78.08  5594.1   77.87
#Mann= 7 ,-1 , 0
  3941.9     .05       0  4031.6     .12       0  4945.6      .1       0
  4961.1     .03       0  5039.7      .1       0  5125.8     .12       0
  5505.8     .05       0
Bank Sta=4961.1,5039.7
XS Rating Curve= 0 ,0
Exp/Cntr=0.3,0.1

Type RM Length L Ch R = 1 ,20873   ,233,233,233
BEGIN DESCRIPTION:
Crystal Creek 056 42.0
END DESCRIPTION:
XS GIS Cut Line= 3
      3886575.69     10026179.31      3885601.23     10025574.21
      3884981.76     10025444.25
#Sta/Elev= 30
  3849.9   75.95  4217.2   73.02  4290.4   75.29  4305.8   75.15  4311.6    75.9
    4327   75.75  4341.7   76.68  4485.2   76.47  4595.1   75.17  4616.3   75.76
  4631.7   75.25  4652.9   76.17  4690.5   75.55  4710.8   75.88    4732   74.55
  4826.5   72.78  4857.3   70.94  4899.7   70.38  4904.5   69.43  4917.7  70.373
  5071.9   70.48  5102.6   73.19  5155.1   74.98    5181   75.29  5186.1   74.73
  5296.7    76.2  5375.4   75.63  5554.9   78.39  5582.8   77.81  5629.9   78.16
#Mann= 6 ,-1 , 0
  3849.9     .12       0  4690.5      .1       0  4899.7     .07       0
  4917.7      .1       0  5155.1     .12       0  5554.9     .05       0
Bank Sta=4899.7,4917.7
XS Rating Curve= 0 ,0
Exp/Cntr=0.3,0.1

Type RM Length L Ch R = 1 ,20640   ,699,699,699
BEGIN DESCRIPTION:
Crystal Creek 056 41.0
END DESCRIPTION:
XS GIS Cut Line= 3
      3886593.04     10026131.56      3885753.79     10025415.14
      3885392.93     10025115.97
#Sta/Elev= 30
  3899.2    75.7  4172.5   73.33  4243.9   73.41  4328.4   76.78  4477.8   76.59
  4512.9   75.32  4534.9   75.85  4598.5   75.59  4647.9   77.83  4690.8   77.97
  4711.6   77.11  4733.6   77.89  4775.3   75.57    4783   75.69  4789.6    74.7
  4894.8   72.58  4924.6   71.87  4945.5   72.07  5001.9      70  5045.5   69.94
  5066.3   70.74    5095   69.96  5166.2   70.16  5184.8   69.75  5185.2   69.25
  5201.8   70.24  5216.1   70.68  5244.4   72.77  5343.7      78  5471.4   77.94
#Mann= 5 ,-1 , 0
  3899.2     .12       0  4894.8      .1       0  5166.2     .03       0
  5201.8      .1       0  5244.4     .12       0
Bank Sta=5166.2,5201.8
XS Rating Curve= 0 ,0
Exp/Cntr=0.3,0.1

Type RM Length L Ch R = 1 ,19941   ,441,441,441
BEGIN DESCRIPTION:
Crystal Creek 056 40.0
END DESCRIPTION:
XS GIS Cut Line= 3
      3886567.83     10025261.05      3886171.76     10024948.56
      3885938.91     10024795.05
#Sta/Elev= 30
  4498.9   77.86  4562.6   77.11  4584.7   76.51  4593.7   75.78  4634.4   74.08
  4663.2   73.73  4669.6   74.27  4727.4   73.12  4748.2   71.69    4769   71.25
  4777.1   70.54  4839.9      70  4855.5   69.71  4919.2   70.13  4929.8   69.67
  4930.3   69.17    4947   70.14  5005.3   70.37  5020.1   70.14  5047.1   71.82
  5062.2   73.26  5083.3   73.41  5091.9   73.06  5134.5   74.19  5149.5    73.8
  5235.7   76.84    5258   77.35  5263.9   77.04  5271.6   77.85  5282.3   78.03
#Mann= 6 ,-1 , 0
  4498.9     .05       0  4593.7     .12       0  4839.9      .1       0
  4919.2     .03       0    4947      .1       0  5005.3     .12       0
Bank Sta=4919.2,4947
XS Rating Curve= 0 ,0
Exp/Cntr=0.3,0.1

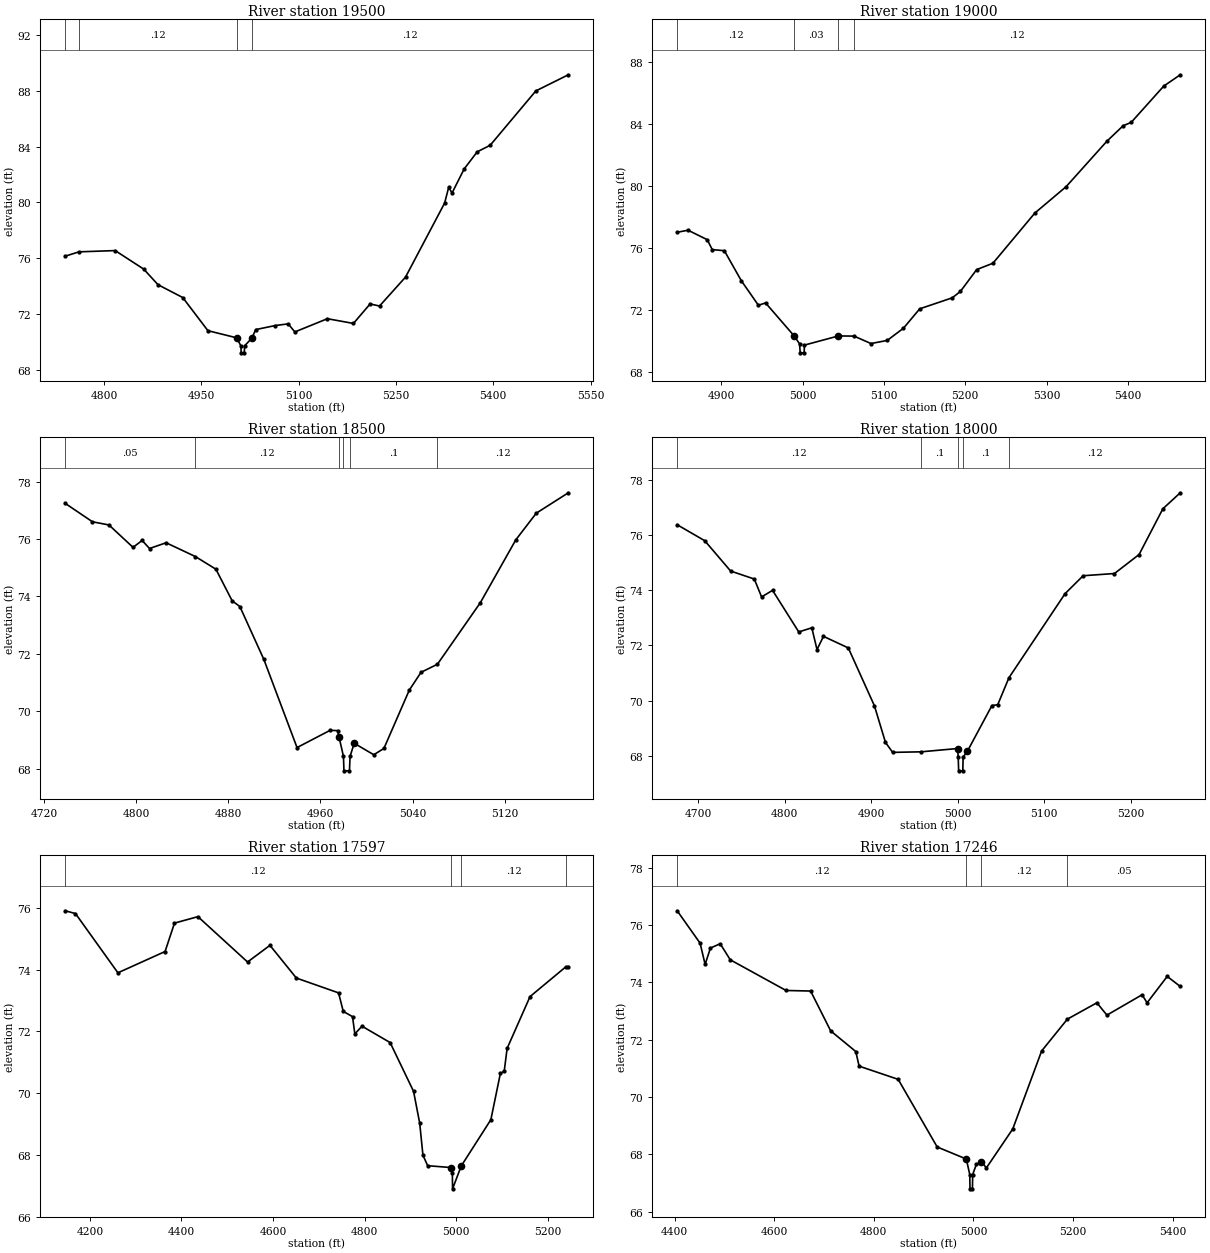
Type RM Length L Ch R = 1 ,19500   ,500,500,500
BEGIN DESCRIPTION:
Crystal Creek 056 39.0
END DESCRIPTION:
XS GIS Cut Line= 3
      3886567.85     10024911.06      3886460.13     10024674.97
      3886417.85     10024161.11
#Sta/Elev= 30
  4740.5   76.14  4761.6   76.45  4817.4   76.54  4861.4   75.21  4883.4   74.09
  4921.5   73.17  4960.3   70.79  5004.5   70.28  5011.1    69.7  5011.6    69.2
  5016.3    69.2  5016.8    69.7 5027.95  70.253    5034   70.87  5064.1   71.16
    5084   71.28  5094.2    70.7  5144.4   71.65  5184.5   71.31  5210.2   72.71
  5224.7   72.56  5264.8   74.64    5325   79.95  5331.3   81.09  5336.4   80.67
  5355.1    82.4  5375.2   83.63  5395.2    84.1  5465.5      88  5515.6   89.16
#Mann= 4 ,-1 , 0
  4740.5     .05       0  4761.6     .12       0  5004.5     .03       0
 5027.95     .12       0
Bank Sta=5004.5,5027.95
XS Rating Curve= 0 ,0
Exp/Cntr=0.3,0.1

Type RM Length L Ch R = 1 ,19000   ,500,500,500
BEGIN DESCRIPTION:
Crystal Creek 056 38.0
END DESCRIPTION:
XS GIS Cut Line= 3
      3886758.58      10024911.9       3886846.4     10024785.03
      3886857.02     10024320.75
#Sta/Elev= 30
  4845.7   77.01  4859.1   77.14  4882.7   76.53  4888.8   75.89  4903.7   75.82
  4924.6   73.88  4945.6    72.3  4954.4   72.45 4989.56  70.321  4996.2   69.81
    4997   69.23  5001.8   69.23  5002.2   69.73    5044   70.32  5063.2   70.31
    5084   69.83    5104   70.03    5124   70.82    5144   72.07    5184   72.78
    5194   73.19    5214    74.6    5234   75.01  5285.6   78.25    5324   79.95
  5374.1   82.88  5394.1   83.88  5404.1    84.1  5444.1   86.44  5464.4   87.17
#Mann= 4 ,-1 , 0
  4845.7     .12       0 4989.56     .03       0    5044      .1       0
  5063.2     .12       0
Bank Sta=4989.56,5044
XS Rating Curve= 0 ,0
Exp/Cntr=0.3,0.1

Type RM Length L Ch R = 1 ,18500   ,500,500,500
BEGIN DESCRIPTION:
Crystal Creek 056 37.0
END DESCRIPTION:
XS GIS Cut Line= 3
      3886955.15     10025241.38      3887158.53     10025077.16
      3887198.67     10024906.72
#Sta/Elev= 30
  4738.6   77.24  4762.2    76.6  4776.5   76.49  4797.4   75.71  4805.3   75.95
  4811.7   75.67  4826.1   75.87  4851.5   75.39  4869.3   74.95  4883.4   73.85
  4890.1   73.65  4910.9   71.81  4939.7   68.74  4968.4   69.34  4974.9   69.33
  4976.2    69.1    4980   68.43  4980.4   67.93  4985.2   67.93  4985.7   68.43
  4989.3   68.89  5006.3   68.49  5015.1   68.71  5037.1   70.74  5047.3   71.36
  5061.5   71.64  5098.7   73.78  5129.5   75.97  5147.3    76.9  5175.1   77.61
#Mann= 6 ,-1 , 0
  4738.6     .05       0  4851.5     .12       0  4976.2      .1       0
    4980     .03       0  4985.7      .1       0  5061.5     .12       0
Bank Sta=4976.2,4989.3
XS Rating Curve= 0 ,0
Exp/Cntr=0.3,0.1

Type RM Length L Ch R = 1 ,18000   ,403,403,403
BEGIN DESCRIPTION:
Crystal Creek 056 36.0
END DESCRIPTION:
XS GIS Cut Line= 3
      3887196.08     10025513.48      3887467.74     10025336.36
      3887663.19     10025168.72
#Sta/Elev= 30
  4675.7   76.38  4707.6    75.8  4737.5    74.7  4764.9   74.41  4773.3   73.76
    4786      74  4816.3   72.49  4831.4   72.64  4837.4   71.85  4844.9   72.33
  4873.6   71.91  4903.8   69.81  4916.6   68.48  4924.9   68.12  4957.7   68.14
    5000   68.26  5000.7   67.95  5001.2   67.45    5006   67.45  5006.4   67.95
  5011.3   68.16  5039.7   69.82  5046.4   69.85  5059.4   70.83  5124.3   73.88
  5145.2   74.53  5181.4   74.61  5209.9    75.3  5237.4   76.96  5257.5   77.54
#Mann= 5 ,-1 , 0
  4675.7     .12       0  4957.7      .1       0  5000.7     .03       0
  5006.4      .1       0  5059.4     .12       0
Bank Sta=5000,5011.3
XS Rating Curve= 0 ,0
Exp/Cntr=0.3,0.1

Type RM Length L Ch R = 1 ,17597   ,351,351,351
BEGIN DESCRIPTION:
Crystal Creek 056 35.0
END DESCRIPTION:
XS GIS Cut Line= 3
      3886744.93      10025801.7      3887573.93      10025619.6
      3887722.61     10025418.82
#Sta/Elev= 30
  4146.2   75.91  4168.5   75.82  4261.2    73.9  4364.2   74.59  4384.7   75.51
  4435.9   75.72  4544.3   74.25  4593.2   74.79  4650.9   73.73    4743   73.25
  4753.3   72.65  4773.5   72.48  4778.6   71.92  4794.2   72.17  4855.6   71.64
  4906.8   70.06  4920.2   69.03  4927.3   67.99  4937.6   67.65  4988.7   67.59
  4991.5    67.4    4992    66.9  5010.9   67.64  5075.6   69.14  5096.4   70.64
  5104.8   70.71  5111.1   71.45  5161.2   73.13    5239   74.09  5244.8    74.1
#Mann= 4 ,-1 , 0
  4146.2     .12       0  4988.7     .03       0  5010.9     .12       0
    5239     .05       0
Bank Sta=4988.7,5010.9
XS Rating Curve= 0 ,0
Exp/Cntr=0.3,0.1

Type RM Length L Ch R = 1 ,17246   ,321,321,321
BEGIN DESCRIPTION:
Mapping XS c2b715d3
END DESCRIPTION:
XS GIS Cut Line= 2
      3887861.04     10026406.71      3887728.36     10025405.06
#Sta/Elev= 30
    4405    76.5    4451   75.37  4461.1   74.63  4471.8    75.2  4491.4   75.35
  4511.6   74.79  4623.6   73.72    4673    73.7  4713.3   72.31  4763.7   71.59
  4770.4   71.08  4848.8   70.62  4927.2   68.26  4985.7   67.84  4992.6    67.3
  4993.1    66.8    4998    66.8  4998.5    67.3  5005.8   67.65  5015.9   67.75
    5026   67.53    5079   68.89    5137   71.61  5188.7   72.72  5247.9   73.29
  5268.1   72.86  5338.7   73.57  5348.8   73.29  5389.2   74.21  5415.4   73.86
#Mann= 4 ,-1 , 0
    4405     .12       0  4985.7     .03       0  5015.9     .12       0
  5188.7     .05       0
Bank Sta=4985.7,5015.9
XS Rating Curve= 0 ,0
Exp/Cntr=0.3,0.1

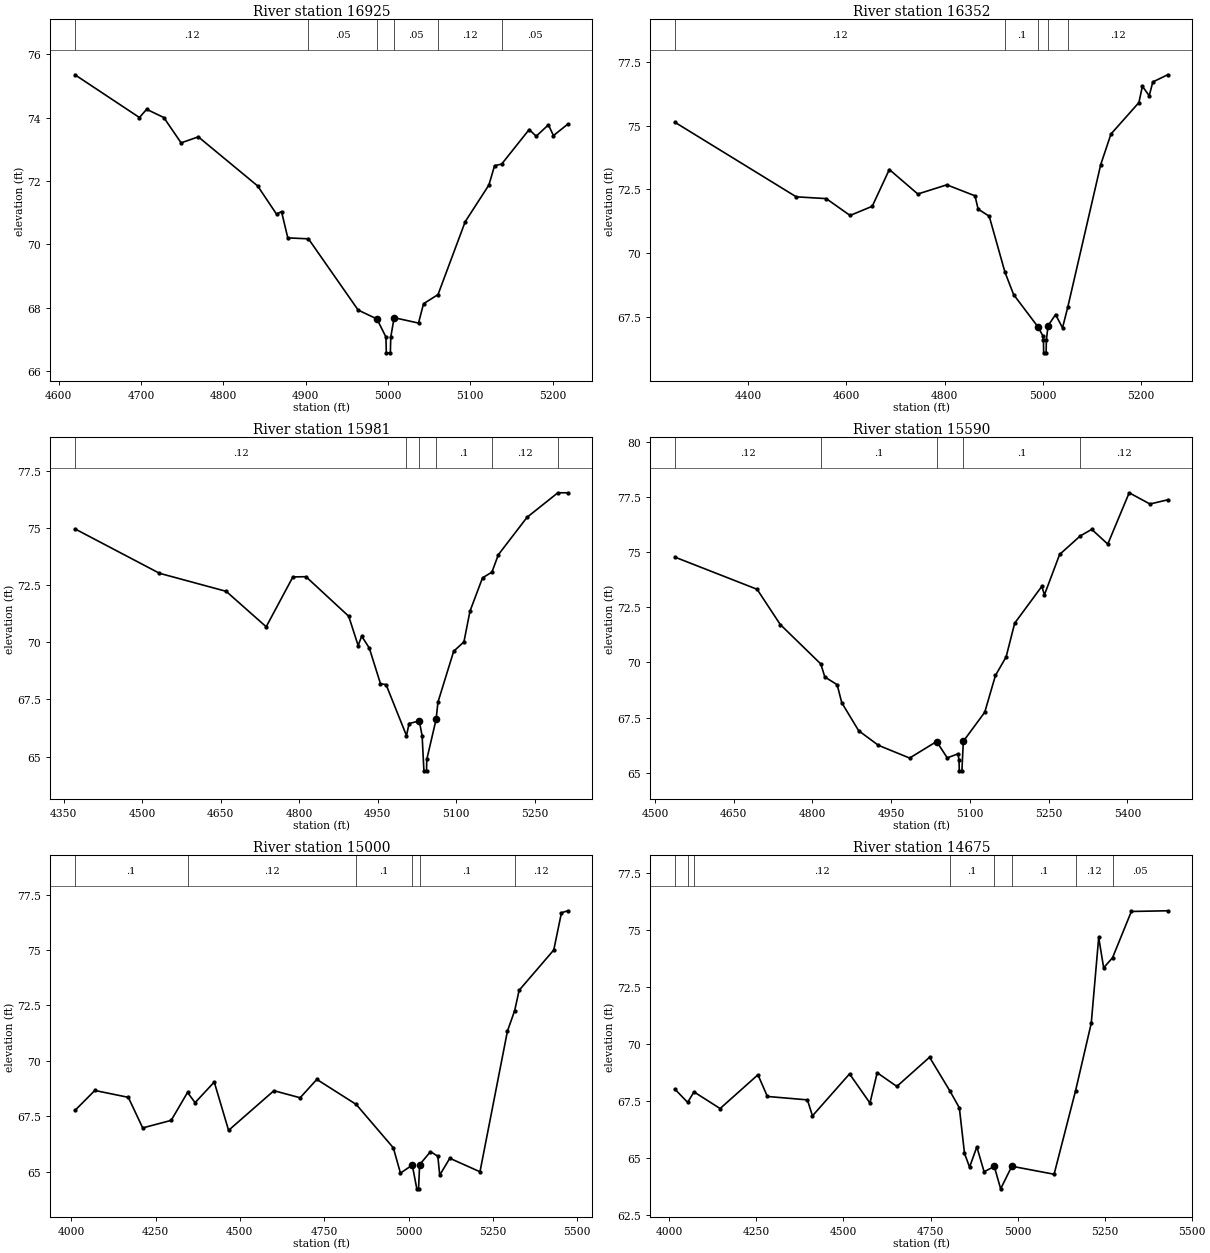
Type RM Length L Ch R = 1 ,16925   ,573,573,573
BEGIN DESCRIPTION:
Crystal Creek 056 34.0
END DESCRIPTION:
XS GIS Cut Line= 2
      3888239.47     10025789.28      3887749.45     10025445.48
#Sta/Elev= 30
  4619.8   75.35  4698.1      74  4706.8   74.26  4727.7      74  4748.7    73.2
  4769.6   73.39  4841.7   71.84  4864.6   70.95  4870.7   71.03  4878.3    70.2
  4903.4   70.17  4963.8   67.92  4986.6   67.64  4997.5   67.07    4998   66.57
  5002.9   66.57  5003.4   67.07  5007.5   67.68  5037.1   67.51  5043.2   68.12
  5060.8   68.41  5093.8   70.71  5122.6   71.87  5129.5   72.48  5138.1   72.53
  5171.5   73.62  5180.1   73.41  5194.9   73.77    5201   73.43  5218.4   73.79
#Mann= 6 ,-1 , 0
  4619.8     .12       0  4903.4     .05       0  4986.6     .03       0
  5007.5     .05       0  5060.8     .12       0  5138.1     .05       0
Bank Sta=4986.6,5007.5
XS Rating Curve= 0 ,0
Exp/Cntr=0.3,0.1

Type RM Length L Ch R = 1 ,16352   ,371,371,371
BEGIN DESCRIPTION:
Crystal Creek 056 33.0
END DESCRIPTION:
XS GIS Cut Line= 4
      3888246.03     10025768.49      3888112.34     10025271.92
      3887968.24     10025086.86      3887779.66     10024916.56
#Sta/Elev= 30
  4251.2   75.13  4498.2   72.21  4559.2   72.14  4607.7   71.48  4652.8   71.84
  4687.6   73.28  4745.6   72.32  4804.6   72.68  4861.9   72.25  4868.3   71.73
  4890.9   71.45  4922.9   69.26  4940.6   68.38  4990.4   67.11    5000   66.77
  5001.3    66.6  5001.7    66.1  5006.7    66.1  5007.2    66.6 5010.66  67.161
  5025.9    67.6  5040.1   67.08  5050.9    67.9  5117.8   73.47  5138.7   74.67
  5195.5    75.9  5202.6   76.54  5216.5   76.17  5223.9   76.71  5254.1   76.99
#Mann= 5 ,-1 , 0
  4251.2     .12       0  4922.9      .1       0  4990.4     .03       0
 5010.66      .1       0  5050.9     .12       0
Bank Sta=4990.4,5010.66
XS Rating Curve= 0 ,0
Exp/Cntr=0.3,0.1

Type RM Length L Ch R = 1 ,15981   ,391,391,391
BEGIN DESCRIPTION:
Crystal Creek 056 32.0
END DESCRIPTION:
XS GIS Cut Line= 3
       3888259.9      10025749.3      3888162.69     10025266.71
      3888321.33     10024846.23
#Sta/Elev= 30
  4371.6   74.96    4533   73.02  4660.5   72.23    4737   70.68    4788   72.86
    4813   72.87  4894.7   71.14  4912.7   69.86  4919.5   70.27    4934   69.75
  4955.4   68.19  4966.1   68.15  5005.1   65.92  5010.1   66.45  5029.6   66.56
    5035   65.91  5038.4   64.38  5043.4   64.38  5043.9   64.88 5061.73  66.635
  5065.2   67.38  5095.3   69.61  5114.9   70.02  5126.4   71.36  5150.4   72.82
  5168.4   73.07  5180.6   73.83  5235.6   75.47  5294.4   76.54  5313.3   76.54
#Mann= 6 ,-1 , 0
  4371.6     .12       0  5005.1      .1       0  5029.6     .03       0
 5061.73      .1       0  5168.4     .12       0  5294.4     .05       0
Bank Sta=5029.6,5061.73
XS Rating Curve= 0 ,0
Exp/Cntr=0.3,0.1

Type RM Length L Ch R = 1 ,15590   ,590,590,590
BEGIN DESCRIPTION:
Crystal Creek 056 31.0
END DESCRIPTION:
XS GIS Cut Line= 3
      3888280.74     10025766.71      3888449.14     10025339.63
      3888357.13     10024869.12
#Sta/Elev= 30
  4538.1   74.78  4694.6   73.32  4738.8   71.72    4816   69.93  4823.6   69.34
  4847.1   68.99  4855.9   68.17  4888.1    66.9  4925.6   66.24  4985.1   65.66
  5036.5   66.41  5056.8   65.67  5077.1   65.85  5079.2   65.58  5079.7   65.08
  5084.7   65.08  5087.4   66.42  5128.2   67.74  5148.6   69.41  5168.9   70.25
  5185.2   71.78  5236.8   73.45  5241.9   73.07  5270.8    74.9    5310   75.74
    5332   76.04  5362.5   75.37  5403.3    77.7  5442.9   77.19  5476.6   77.38
#Mann= 5 ,-1 , 0
  4538.1     .12       0    4816      .1       0  5036.5     .03       0
  5087.4      .1       0    5310     .12       0
Bank Sta=5036.5,5087.4
XS Rating Curve= 0 ,0
Exp/Cntr=0.3,0.1

Type RM Length L Ch R = 1 ,15000   ,325,325,325
BEGIN DESCRIPTION:
Crystal Creek 056 30.0
END DESCRIPTION:
XS GIS Cut Line= 3
      3889472.95     10025849.06      3888804.97     10025120.13
       3888391.5     10024892.47
#Sta/Elev= 30
  4011.3   67.76  4070.1   68.66  4169.4   68.35    4212   66.97  4296.4   67.31
  4344.9   68.57  4367.3   68.11  4424.1   69.04  4466.6   66.86    4601   68.65
  4678.7   68.33  4728.1   69.16  4844.9   68.03    4955   66.07    4976   64.93
  5011.1   65.29  5024.6   64.22  5029.7   64.22  5032.9   65.31  5065.1    65.9
  5086.8   65.69  5092.5   64.84  5122.3    65.6  5211.8   64.99  5293.2   71.34
  5314.6   72.26  5327.8   73.18  5430.5      75  5453.3   76.68    5472   76.77
#Mann= 6 ,-1 , 0
  4011.3      .1       0  4344.9     .12       0  4844.9      .1       0
  5011.1     .03       0  5032.9      .1       0  5314.6     .12       0
Bank Sta=5011.1,5032.9
XS Rating Curve= 0 ,0
Exp/Cntr=0.3,0.1

Type RM Length L Ch R = 1 ,14675   ,175,175,175
BEGIN DESCRIPTION:
Mapping XS e11ed770
END DESCRIPTION:
XS GIS Cut Line= 3
      3889427.79     10025623.34      3888865.31     10024859.48
      3888487.44     10024585.61
#Sta/Elev= 30
  4015.8   68.01  4052.4   67.43  4070.6   67.89  4145.6   67.16  4254.3   68.64
  4281.4   67.69  4396.3   67.54  4410.9   66.84  4517.4   68.68    4576    67.4
  4596.8   68.73  4653.2   68.13  4747.2   69.41  4806.4   67.91  4832.8   67.19
  4847.5    65.2  4862.1   64.59    4883   65.48  4903.8   64.39  4933.1   64.62
  4951.4   63.64  4983.5   64.63  5104.9   64.28  5166.7   67.95  5211.6    70.9
    5233   74.66  5247.2   73.33  5272.7   73.77  5326.8    75.8  5431.1   75.83
#Mann= 8 ,-1 , 0
  4015.8     .12       0  4052.4      .1       0  4070.6     .12       0
  4806.4      .1       0  4933.1     .03       0  4983.5      .1       0
  5166.7     .12       0  5272.7     .05       0
Bank Sta=4933.1,4983.5
XS Rating Curve= 0 ,0
Exp/Cntr=0.3,0.1

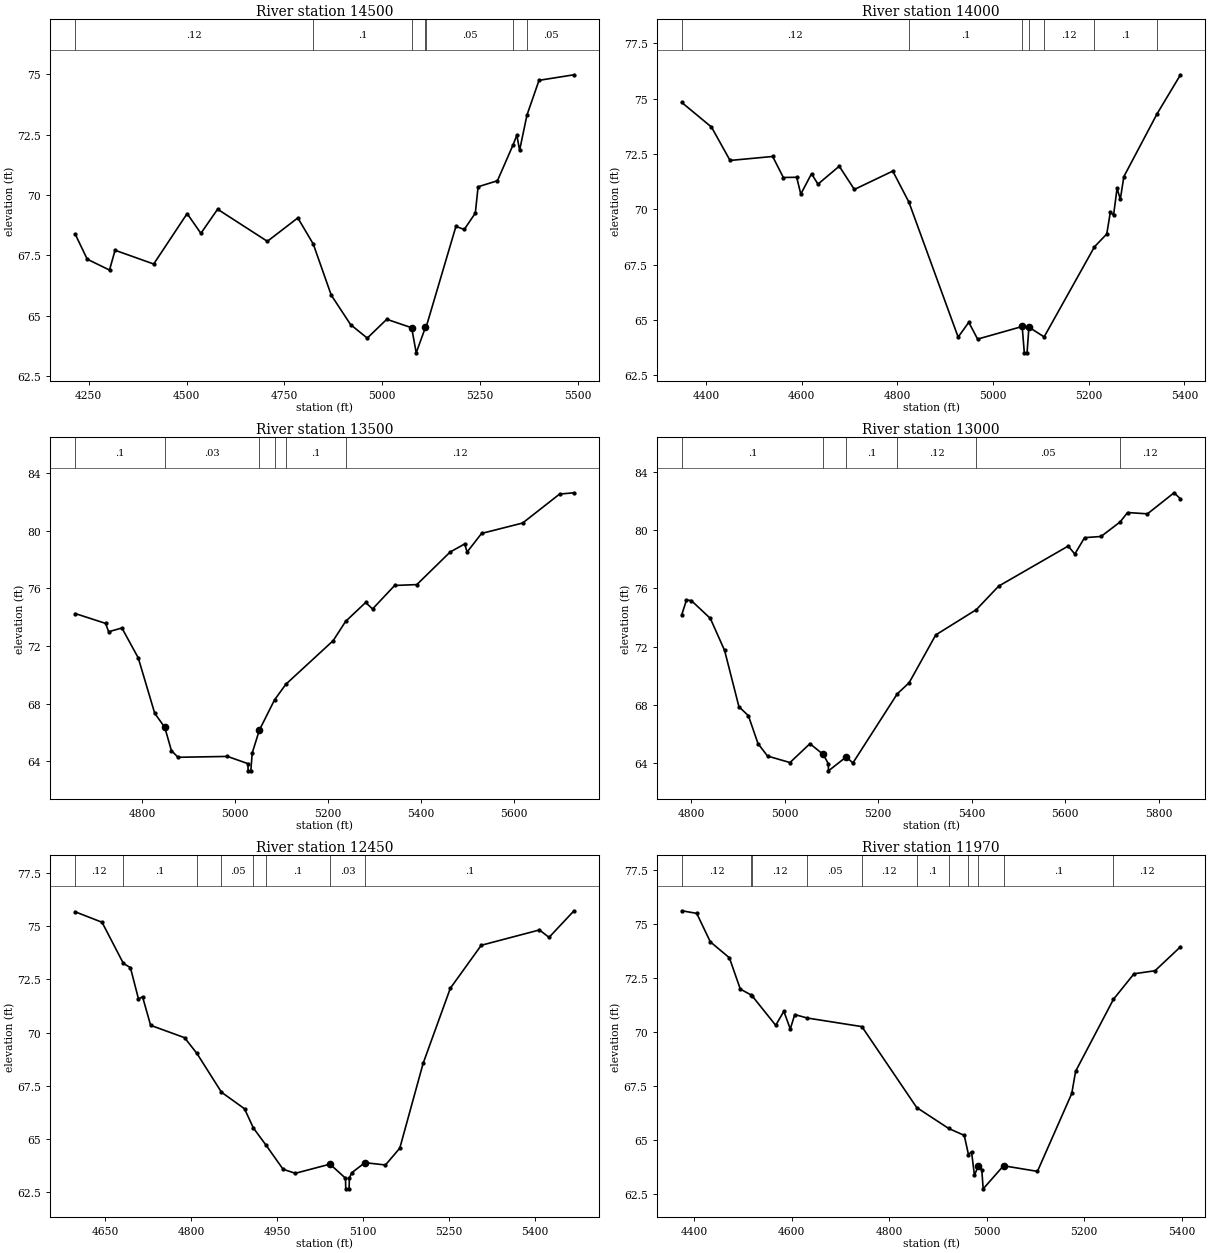
Type RM Length L Ch R = 1 ,14500   ,500,500,500
BEGIN DESCRIPTION:
Crystal Creek 056 29.0
END DESCRIPTION:
XS GIS Cut Line= 3
      3889424.33     10025307.39      3888906.39     10024718.71
      3888557.68     10024374.75
#Sta/Elev= 30
  4215.9   68.37  4246.4   67.34  4303.3   66.89  4317.5   67.71  4416.2   67.14
  4501.6   69.23  4536.7   68.41  4579.4   69.41  4706.5   68.08  4784.3   69.05
  4823.7   67.97  4869.7   65.85  4919.1   64.63  4961.7   64.07  5011.5   64.85
  5075.1    64.5  5086.7   63.46  5110.4   64.52  5111.8   64.51  5188.2    68.7
  5209.4   68.57  5237.7   69.25  5244.8   70.34  5294.2   70.59  5334.5   72.09
  5343.8   72.48  5350.8   71.85  5369.6   73.31  5400.4   74.75  5489.8   74.98
#Mann= 7 ,-1 , 0
  4215.9     .12       0  4823.7      .1       0  5075.1     .03       0
  5110.4      .1       0  5111.8     .05       0  5334.5     .12       0
  5369.6     .05       0
Bank Sta=5075.1,5110.4
XS Rating Curve= 0 ,0
Exp/Cntr=0.3,0.1

Type RM Length L Ch R = 1 ,14000   ,500,500,500
BEGIN DESCRIPTION:
Crystal Creek 056 28.0
END DESCRIPTION:
XS GIS Cut Line= 4
      3889809.85     10024298.81      3889483.11     10024464.43
      3889220.44     10024354.66      3888954.81     10024066.65
#Sta/Elev= 30
    4349   74.83  4411.1   73.72    4450   72.21  4539.1   72.39  4561.4   71.44
  4589.3   71.45  4597.9   70.69  4620.3   71.61  4633.8   71.14  4678.3   71.95
  4709.9    70.9  4790.2   71.73  4823.9   70.33  4926.9   64.23  4949.2    64.9
  4967.6   64.14  5060.8   64.71  5065.3   63.52    5071   63.52  5074.9   64.68
  5106.7   64.24    5212   68.31  5237.7   68.89  5245.1   69.87  5251.9   69.74
  5259.2   70.95    5266   70.46  5273.4   71.48  5343.2   74.33  5391.8   76.08
#Mann= 7 ,-1 , 0
    4349     .12       0  4823.9      .1       0  5060.8     .07       0
  5074.9      .1       0  5106.7     .12       0    5212      .1       0
  5343.2     .12       0
Bank Sta=5060.8,5074.9
XS Rating Curve= 0 ,0
Exp/Cntr=0.3,0.1

Type RM Length L Ch R = 1 ,13500   ,500,500,500
BEGIN DESCRIPTION:
Crystal Creek 056 27.0
END DESCRIPTION:
XS GIS Cut Line= 3
       3889709.6     10024230.39        3889485.      10023970.1
      3889246.65      10023281.8
#Sta/Elev= 30
  4656.2   74.24  4721.3   73.56  4727.9   72.98  4756.4   73.24  4791.5   71.17
    4827   67.32  4848.5   66.35  4862.8   64.74    4877   64.27  4983.4   64.33
  5027.3   63.83  5027.8   63.33  5033.6   63.33  5036.6   64.57  5051.9   66.15
  5084.5   68.25    5109   69.34  5210.6   72.36  5237.4    73.7  5280.5   75.01
  5295.3   74.56  5342.8   76.19  5390.5   76.25  5462.1   78.51  5493.3   79.07
  5498.6   78.51  5529.7    79.8  5617.9   80.52  5697.4   82.53  5728.4   82.62
#Mann= 6 ,-1 , 0
  4656.2      .1       0  4848.5     .03       0  5051.9      .1       0
  5084.5     .12       0    5109      .1       0  5237.4     .12       0
Bank Sta=4848.5,5051.9
XS Rating Curve= 0 ,0
Exp/Cntr=0.3,0.1

Type RM Length L Ch R = 1 ,13000   ,550,550,550
BEGIN DESCRIPTION:
Crystal Creek 056 26.0
END DESCRIPTION:
XS GIS Cut Line= 3
      3889913.16     10024110.98      3889870.06     10023895.04
      3889306.47     10023262.76
#Sta/Elev= 30
  4779.8   74.19  4789.9    75.2  4800.1   75.17  4840.9   73.94  4871.5   71.73
  4902.1   67.86  4922.5   67.23  4942.9   65.32  4963.3   64.46  5011.4   64.01
  5054.1   65.31  5082.5   64.57  5093.3   63.94  5093.8   63.44  5131.8    64.4
    5146   63.98  5240.9   68.74  5266.4   69.51  5323.3    72.8  5410.1   74.54
  5457.9   76.16  5606.7   78.92  5620.9   78.37  5641.8    79.5    5677   79.58
  5717.8   80.58  5733.8   81.23  5776.4   81.14  5833.3   82.59    5847   82.17
#Mann= 6 ,-1 , 0
  4779.8      .1       0  5082.5     .03       0  5131.8      .1       0
  5240.9     .12       0  5410.1     .05       0  5717.8     .12       0
Bank Sta=5082.5,5131.8
XS Rating Curve= 0 ,0
Exp/Cntr=0.3,0.1

Type RM Length L Ch R = 1 ,12450   ,480,480,480
BEGIN DESCRIPTION:
Crystal Creek 056 25.0
END DESCRIPTION:
XS GIS Cut Line= 4
      3889994.53     10024103.76      3890127.73     10023970.38
      3890179.46     10023757.38      3890260.19     10023301.67
#Sta/Elev= 30
  4597.5   75.67  4644.2   75.18  4681.4   73.25  4693.7   73.05  4707.8   71.58
  4714.9   71.68    4729   70.34  4788.2   69.76  4809.8   69.02  4852.6    67.2
  4892.9   66.42  4908.3   65.52  4930.2   64.72  4960.2   63.58  4981.6   63.39
  5042.1   63.82  5069.1   63.16  5069.6   62.66  5075.4   62.66  5075.9   63.16
  5079.8   63.41    5103   63.89  5138.9   63.78  5163.9   64.57  5204.6   68.55
  5252.1   72.08  5306.1    74.1  5407.7   74.82  5424.4   74.47    5468   75.72
#Mann= 8 ,-1 , 0
  4597.5     .12       0  4681.4      .1       0  4809.8     .12       0
  4852.6     .05       0  4908.3     .12       0  4930.2      .1       0
  5042.1     .03       0    5103      .1       0
Bank Sta=5042.1,5103
XS Rating Curve= 0 ,0
Exp/Cntr=0.3,0.1

Type RM Length L Ch R = 1 ,11970   ,470,470,470
BEGIN DESCRIPTION:
Crystal Creek 056 24.0
END DESCRIPTION:
XS GIS Cut Line= 4
      3890008.87     10024111.55      3890484.15     10023873.26
      3890571.39     10023814.67      3890815.83     10023515.62
#Sta/Elev= 30
  4374.3   75.62    4405    75.5  4432.9   74.18    4472   73.44  4494.4   71.99
  4517.1   71.71  4518.9   71.67    4567   70.31  4583.7   70.96  4596.9   70.14
  4606.1   70.81  4631.3   70.65  4743.8   70.25  4856.2    66.5  4921.7   65.53
  4953.7   65.21  4962.4   64.32  4968.7   64.45  4974.7   63.35  4982.7   63.81
  4989.7   63.61  4992.6   62.73  5034.3    63.8  5103.9   63.54  5174.3   67.15
  5182.2   68.18  5259.9   71.52    5302    72.7  5345.1   72.84  5397.3   73.95
#Mann= 11 ,-1 , 0
  4374.3     .12       0  4517.1      .1       0  4518.9     .12       0
  4631.3     .05       0  4743.8     .12       0  4856.2      .1       0
  4921.7     .12       0  4962.4      .1       0  4982.7     .03       0
  5034.3      .1       0  5259.9     .12       0
Bank Sta=4982.7,5034.3
XS Rating Curve= 0 ,0
Exp/Cntr=0.3,0.1