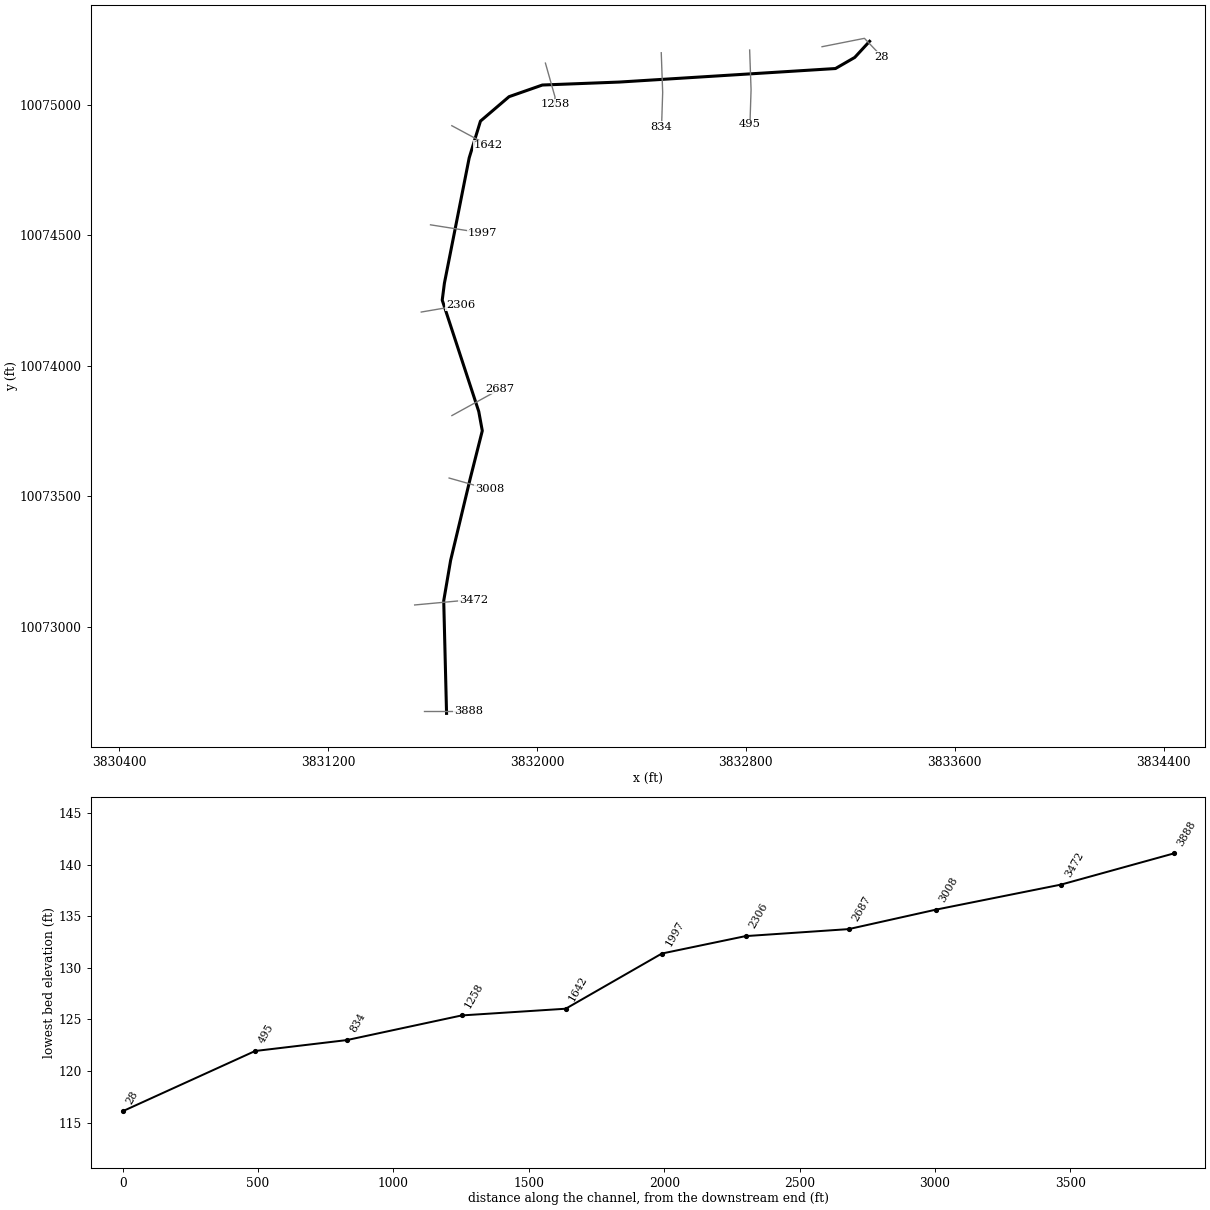
--- Crystal Creek 060.prj (project) ---

Proj Title=Crystal Creek 060 Base Level Engineering
Current Plan=p01
Default Exp/Contr=0.3,0.1
English Units
Geom File=g01
Flow File=f01
Plan File=p01
Y Axis Title=Elevation
X Axis Title(PF)=Main Channel Distance
X Axis Title(XS)=Station
BEGIN DESCRIPTION:
Crystal Creek 060
END DESCRIPTION:
DSS Export Rating Curves= 0
DSS Export Rating Curve Sorted= 0
DSS Export Volume Flow Curves= 0
DXF OffsetX= 0
DXF OffsetY= 0
DXF ScaleX= 1
DXF ScaleY= 10

--- Crystal Creek 060.p01 (plan) ---

Plan Title=Multiple Run
Short Identifier=Multiple
Geom File=g01
Flow File=f01
Subcritical Flow
K Sum by GR= 0
Std Step Tol= 0.01
Critical Tol= 0.01
Num of Std Step Trials= 20
Max Error Tol= 0.3
Flow Tol Ratio= 0.001
Split Flow NTrial= 30
Split Flow Tol= 0.02
Split Flow Ratio= 0.02
Log Output Level= 0
Friction Slope Method= 1
Unsteady Friction Slope Method= 2
Unsteady Bridges Friction Slope Method= 1
Parabolic Critical Depth
Global Vel Dist=  1 , 1 , 1
Global Log Level= 0
CheckData=True
Encroach Param= -1, 0, 0, 0
BEGIN DESCRIPTION:
Multiple Run
END DESCRIPTION:

--- Crystal Creek 060.f01 (steady flow) ---

Flow Title=Multiple
Program Version=4.10
Number of Profiles= 7
Profile Names=10-year,25-year,50-year,1pct_min,100-year,1pct_plu,500-year
River Rch & RM=Crystal Creek 06,Reach-1         ,3888
     168     205     259     108     326     985     531
River Rch & RM=Crystal Creek 06,Reach-1         ,28
     398     518     682     296     893    2697    1581
Boundary for River Rch & Prof#=Crystal Creek 06,Reach-1         , 1
Up Type= 0
Dn Type= 3
Dn Slope=0.013
Boundary for River Rch & Prof#=Crystal Creek 06,Reach-1         , 2
Up Type= 0
Dn Type= 3
Dn Slope=0.013
Boundary for River Rch & Prof#=Crystal Creek 06,Reach-1         , 3
Up Type= 0
Dn Type= 3
Dn Slope=0.013
Boundary for River Rch & Prof#=Crystal Creek 06,Reach-1         , 4
Up Type= 0
Dn Type= 3
Dn Slope=0.013
Boundary for River Rch & Prof#=Crystal Creek 06,Reach-1         , 5
Up Type= 0
Dn Type= 3
Dn Slope=0.013
Boundary for River Rch & Prof#=Crystal Creek 06,Reach-1         , 6
Up Type= 0
Dn Type= 3
Dn Slope=0.013
Boundary for River Rch & Prof#=Crystal Creek 06,Reach-1         , 7
Up Type= 0
Dn Type= 3
Dn Slope=0.013
DSS Import GetInterval= 0
DSS Import GetPeak= 0
DSS Import FillOption= 0

--- Crystal Creek 060.g01 (geometry) ---

Geom Title=Existing Conditions
Program Version=4.10

River Reach=Crystal Creek 06,Reach-1
Reach XY= 16
      3831654.04     10072668.49      3831643.17     10073099.89
      3831669.63     10073254.78      3831744.06     10073565.39
       3831790.9     10073750.84      3831777.35     10073824.77
      3831637.47     10074251.19       3831645.8     10074316.04
      3831740.75     10074796.19       3831783.9     10074936.83
      3831893.42      10075030.4      3832020.93     10075075.02
      3832316.57     10075086.43      3833143.61     10075138.19
      3833217.37     10075180.75      3833274.26      10075242.5

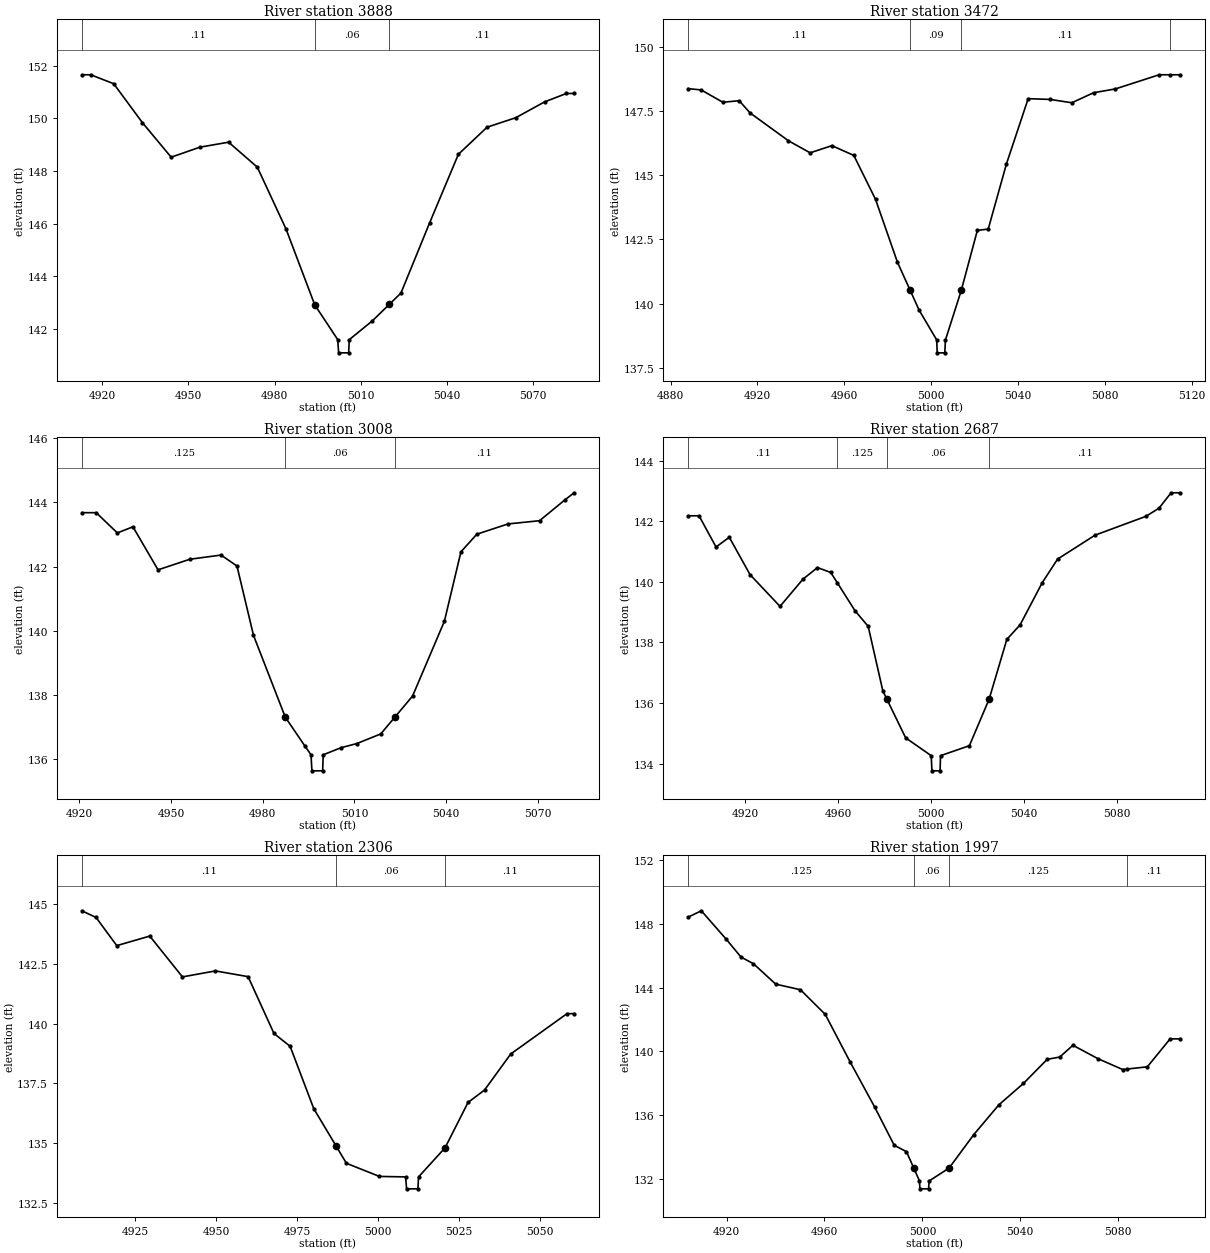
Type RM Length L Ch R = 1 ,3888    ,416,416,416
BEGIN DESCRIPTION:
Crystal Creek 060 11.0
END DESCRIPTION:
XS GIS Cut Line= 2
       3831566.7     10072678.02       3831738.1     10072678.02
#Sta/Elev= 24
  4912.9  151.66    4916  151.66    4924  151.32    4934  149.84    4944  148.53
    4954  148.91    4964   149.1    4974  148.15    4984   145.8    4994  142.92
    5002   141.6  5002.3   141.1  5005.8   141.1    5006   141.6    5014  142.31
 5019.91142.9365    5024  143.37    5034  146.04    5044  148.64    5054  149.67
    5064  150.03    5074  150.63  5081.6  150.95  5084.3  150.95
#Mann= 3 , 0 , 0
  4912.9     .11       0    4994     .06       0 5019.91     .11       0
Bank Sta=4994,5019.91
XS Rating Curve= 0 ,0
Exp/Cntr=0.3,0.1

Type RM Length L Ch R = 1 ,3472    ,464,464,464
BEGIN DESCRIPTION:
Crystal Creek 060 10.0
END DESCRIPTION:
XS GIS Cut Line= 2
      3831531.89     10073083.68      3831757.63     10073104.52
#Sta/Elev= 29
  4888.1  148.37  4894.1  148.32  4904.1  147.84  4911.6   147.9  4916.7  147.42
  4934.3  146.34  4944.3  145.87  4954.3  146.15  4964.4  145.77  4974.4  144.06
  4984.5  141.61 4990.38140.5105  4994.5  139.74  5002.6  138.58  5002.8  138.08
  5006.3  138.08  5006.6  138.58 5013.88140.5091  5021.3  142.85  5026.3   142.9
  5034.7  145.44  5044.7  147.98  5054.8  147.95  5064.8  147.82  5074.8  148.21
  5084.9  148.36    5105  148.91  5109.8  148.91  5114.8  148.91
#Mann= 4 ,-1 , 0
  4888.1     .11       0 4990.38     .09       0 5013.88     .11       0
  5109.8     .11       0
Bank Sta=4990.38,5013.88
XS Rating Curve= 0 ,0
Exp/Cntr=0.3,0.1

Type RM Length L Ch R = 1 ,3008    ,321,321,321
BEGIN DESCRIPTION:
Crystal Creek 060 9.0
END DESCRIPTION:
XS GIS Cut Line= 2
      3831663.84     10073569.81      3831818.68     10073526.06
#Sta/Elev= 27
  4920.9  143.68  4925.6  143.68  4932.5  143.05  4937.6  143.24  4945.8   141.9
  4956.2  142.23  4966.4  142.36  4971.6  142.02    4977  139.86  4987.4  137.31
  4993.9   136.4  4995.8  136.14  4996.1  135.64  4999.6  135.64  4999.8  136.14
  5005.6  136.36  5010.8  136.49  5018.6  136.79 5023.14137.3051    5029  137.97
  5039.4   140.3  5044.8  142.46    5050  143.01  5060.2  143.33  5070.5  143.43
  5078.8  144.08  5081.8   144.3
#Mann= 3 , 0 , 0
  4920.9    .125       0  4987.4     .06       0 5023.14     .11       0
Bank Sta=4987.4,5023.14
XS Rating Curve= 0 ,0
Exp/Cntr=0.3,0.1

Type RM Length L Ch R = 1 ,2687    ,381,381,381
BEGIN DESCRIPTION:
Crystal Creek 060 8.0
END DESCRIPTION:
XS GIS Cut Line= 2
      3831674.54     10073809.04       3831859.9      10073911.1
#Sta/Elev= 30
  4895.6  142.18  4900.3  142.18  4907.6  141.15  4913.3  141.47  4922.2  140.24
  4935.1  139.19    4945  140.09  4951.2  140.47  4956.9  140.31  4959.8  139.96
  4967.3  139.05    4973  138.53  4979.3   136.4 4981.01136.1296  4989.1  134.85
  5000.1  134.26  5000.4  133.76  5003.9  133.76  5004.1  134.26  5016.5  134.59
    5025  136.13  5032.6   138.1  5038.3  138.58  5047.8  139.97  5054.4  140.75
  5070.5  141.54  5092.3  142.16    5098  142.43  5103.2  142.94  5107.2  142.94
#Mann= 4 ,-1 , 0
  4895.6     .11       0  4959.8    .125       0 4981.01     .06       0
    5025     .11       0
Bank Sta=4981.01,5025
XS Rating Curve= 0 ,0
Exp/Cntr=0.3,0.1

Type RM Length L Ch R = 1 ,2306    ,309,309,309
BEGIN DESCRIPTION:
Crystal Creek 060 7.0
END DESCRIPTION:
XS GIS Cut Line= 2
      3831557.19     10074205.56       3831707.2     10074231.26
#Sta/Elev= 23
  4908.5  144.73  4912.9  144.45  4919.3  143.27  4929.5  143.67  4939.6  141.96
  4949.8  142.21  4959.9  141.97  4967.9  139.59  4972.9  139.05  4980.2  136.44
 4987.14134.8664  4990.3  134.15  5000.5   133.6  5008.6  133.58  5008.9  133.08
  5012.4  133.08  5012.6  133.58  5020.8   134.8  5027.9   136.7    5033  137.22
  5041.1  138.73  5058.5  140.42  5060.7  140.42
#Mann= 3 , 0 , 0
  4908.5     .11       0 4987.14     .06       0  5020.8     .11       0
Bank Sta=4987.14,5020.8
XS Rating Curve= 0 ,0
Exp/Cntr=0.3,0.1

Type RM Length L Ch R = 1 ,1997    ,355,355,355
BEGIN DESCRIPTION:
Crystal Creek 060 6.0
END DESCRIPTION:
XS GIS Cut Line= 2
      3831592.53      10074539.6      3831791.18     10074508.34
#Sta/Elev= 30
  4904.3  148.42  4909.7  148.82  4919.8  147.05  4925.9  145.92    4931   145.5
  4940.1  144.22  4950.2  143.87  4960.3  142.33  4970.4  139.37  4980.6  136.49
  4988.5  134.12  4993.5  133.72  4996.5132.6841  4998.8  131.89    4999  131.39
  5002.5  131.39  5002.8  131.89  5010.9  132.69    5021  134.79  5031.2  136.65
  5041.3     138    5051  139.51  5056.1  139.65  5061.5  140.39  5071.7  139.55
  5081.8  138.87  5083.7   138.9  5091.9  139.04  5101.2  140.79  5105.4  140.79
#Mann= 4 ,-1 , 0
  4904.3    .125       0  4996.5     .06       0  5010.9    .125       0
  5083.7     .11       0
Bank Sta=4996.5,5010.9
XS Rating Curve= 0 ,0
Exp/Cntr=0.3,0.1

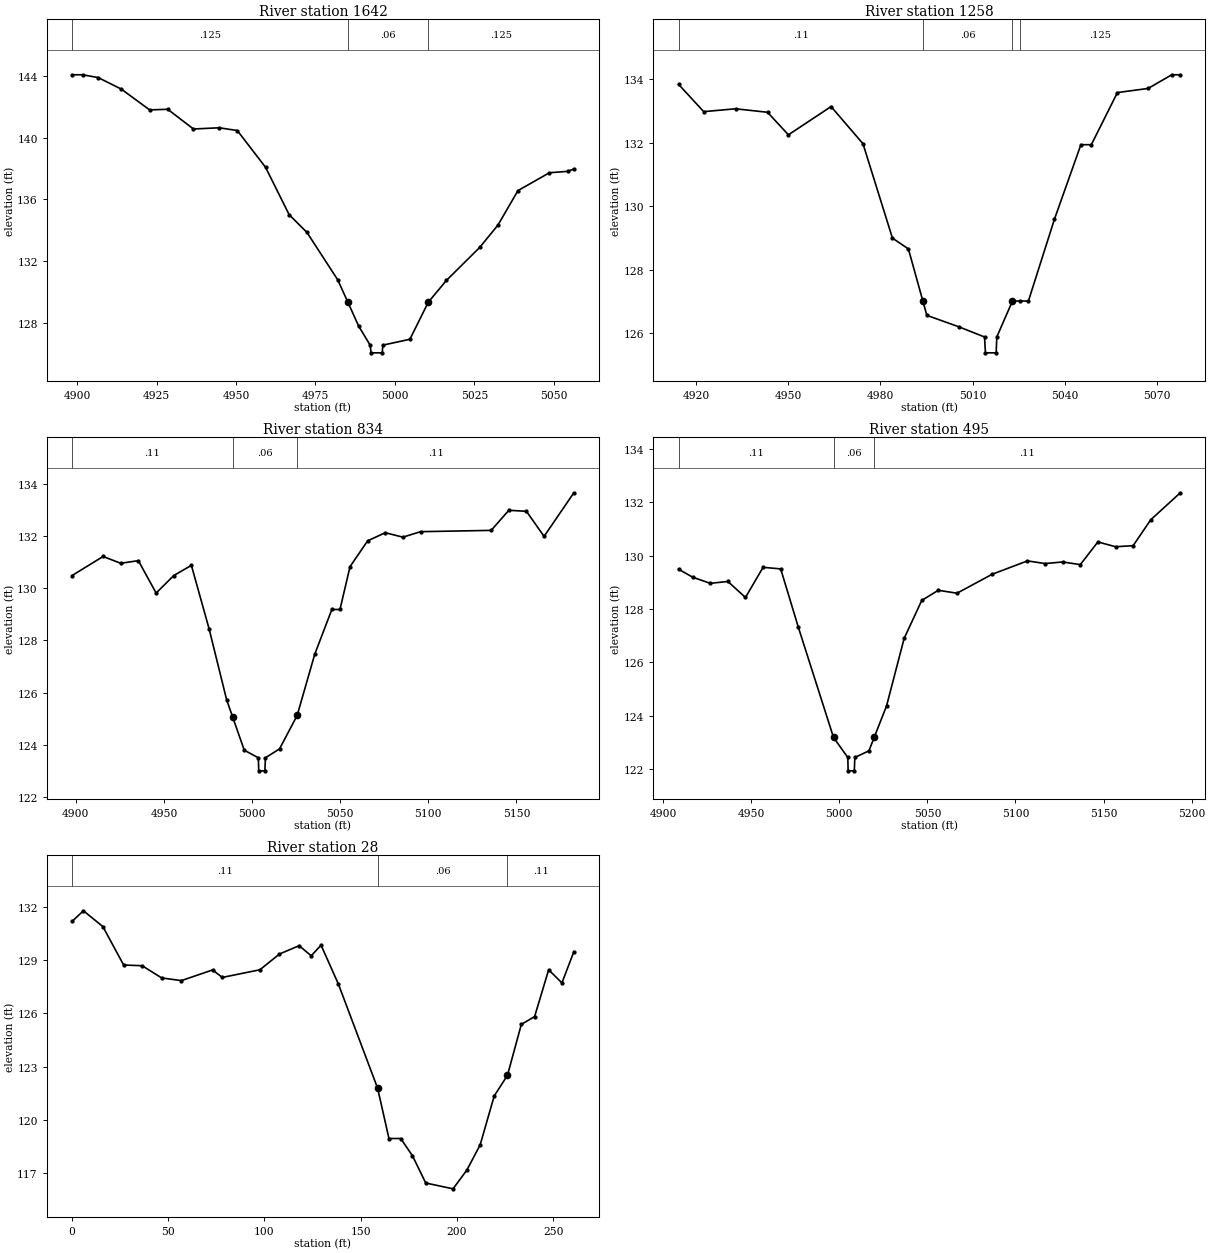
Type RM Length L Ch R = 1 ,1642    ,384,384,384
BEGIN DESCRIPTION:
Crystal Creek 060 5.0
END DESCRIPTION:
XS GIS Cut Line= 2
      3831674.23     10074919.18      3831813.32     10074844.45
#Sta/Elev= 28
  4898.4  144.09  4901.7  144.09  4906.6  143.91  4913.9  143.16  4922.8  141.81
  4928.5  141.85  4936.6  140.57  4944.7  140.65  4950.4  140.47  4959.3  138.08
  4966.7  135.01  4972.3  133.86    4982  130.78 4985.16129.3388  4988.6  127.77
  4992.2  126.54  4992.5  126.04    4996  126.04  4996.2  126.54  5004.7  126.92
  5010.5  129.33  5016.2  130.74  5026.7  132.89  5032.4  134.33  5038.7  136.57
  5048.6  137.73  5054.3  137.82  5056.3  137.97
#Mann= 3 , 0 , 0
  4898.4    .125       0 4985.16     .06       0  5010.5    .125       0
Bank Sta=4985.16,5010.5
XS Rating Curve= 0 ,0
Exp/Cntr=0.3,0.1

Type RM Length L Ch R = 1 ,1258    ,424,424,424
BEGIN DESCRIPTION:
Crystal Creek 060 4.0
END DESCRIPTION:
XS GIS Cut Line= 3
      3832032.66     10075158.93      3832069.33     10075029.57
      3832068.39     10075000.54
#Sta/Elev= 26
  4914.2  133.84  4922.4  132.98  4932.8  133.07  4943.2  132.96    4950  132.25
  4963.9  133.14  4974.3  131.97  4983.9     129  4989.1  128.66 4993.78127.0299
  4995.1  126.57  5005.5  126.21  5013.9  125.89  5014.2  125.39  5017.7  125.39
  5017.9  125.89    5023  127.02  5025.6  127.02  5028.2  127.02  5036.7   129.6
  5045.3  131.94  5048.7  131.94  5057.2  133.58  5067.2  133.71  5074.9  134.14
  5077.7  134.14
#Mann= 4 ,-1 , 0
  4914.2     .11       0 4993.78     .06       0    5023     .11       0
  5025.6    .125       0
Bank Sta=4993.78,5023
XS Rating Curve= 0 ,0
Exp/Cntr=0.3,0.1

Type RM Length L Ch R = 1 ,834     ,339,339,339
BEGIN DESCRIPTION:
Crystal Creek 060 3.0
END DESCRIPTION:
XS GIS Cut Line= 3
      3832476.31     10075198.69      3832481.74     10075046.76
      3832477.46     10074914.16
#Sta/Elev= 30
  4897.9  130.48  4915.5  131.21  4925.5  130.95  4935.5  131.05  4945.6  129.81
  4955.6  130.48  4965.6  130.87  4975.6  128.45  4985.6  125.72 4989.01125.0619
  4995.6  123.79  5003.6   123.5  5003.8     123  5007.3     123  5007.6   123.5
  5015.6  123.84  5025.6  125.12  5035.6  127.47  5045.3  129.18  5049.9  129.18
  5055.6  130.82  5065.6  131.81  5075.6  132.12  5085.6  131.95  5095.6  132.16
  5135.7  132.21  5145.7  132.98  5155.7  132.94  5165.7  131.98  5182.6  133.65
#Mann= 3 , 0 , 0
  4897.9     .11       0 4989.01     .06       0  5025.6     .11       0
Bank Sta=4989.01,5025.6
XS Rating Curve= 0 ,0
Exp/Cntr=0.3,0.1

Type RM Length L Ch R = 1 ,495     ,489,489,489
BEGIN DESCRIPTION:
Crystal Creek 060 2.0
END DESCRIPTION:
XS GIS Cut Line= 3
      3832814.86     10075209.06      3832820.28     10075057.18
      3832815.99     10074924.33
#Sta/Elev= 30
  4908.7  129.49  4916.7  129.19  4926.7  128.96  4936.7  129.03  4946.7  128.43
  4956.7  129.56  4966.7   129.5  4976.7  127.32  4996.7  123.19  5004.8  122.44
    5005  121.94  5008.5  121.94  5008.8  122.44  5016.8  122.69 5019.77 123.189
  5026.8  124.37  5036.8   126.9  5046.8  128.32  5056.2   128.7  5066.8  128.59
  5086.8   129.3  5106.8   129.8  5116.8   129.7  5126.8  129.76  5136.8  129.66
  5146.8  130.51  5156.8  130.33  5166.8  130.37  5176.8  131.34  5193.6  132.35
#Mann= 3 , 0 , 0
  4908.7     .11       0  4996.7     .06       0 5019.77     .11       0
Bank Sta=4996.7,5019.77
XS Rating Curve= 0 ,0
Exp/Cntr=0.3,0.1

Type RM Length L Ch R = 1 ,28      ,0,0,0
XS GIS Cut Line= 3
      3833092.11     10075221.75      3833254.44     10075253.83
      3833321.42     10075183.64
#Sta/Elev= 30
       0  131.19     5.9  131.79      16   130.9    26.8  128.73    36.4  128.69
    46.6     128    56.8  127.85      73  128.45    78.1  128.03    97.6  128.46
   107.8  129.35     118  129.82   124.3  129.25   129.4  129.85   138.4  127.66
   158.8  121.78   164.7  118.94   170.8  118.94   176.9  117.97   183.8  116.43
     198   116.1   205.2  117.16   212.1  118.58   219.4  121.34   226.3  122.51
   233.5  125.38   240.4  125.82   247.7  128.46   254.6  127.72   260.8  129.48
#Mann= 3 , 0 , 0
       0     .11       0   158.8     .06       0   226.3     .11       0
Bank Sta=158.8,226.3
XS Rating Curve= 0 ,0
Exp/Cntr=0.3,0.1

Chan Stop Cuts=-1
Use User Specified Reach Order=0
Composite Channel Slope=5

--- Crystal Creek 060.g10 (geometry) ---

Geom Title=Existing Conditions
Program Version=4.10

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
River Reach=Crystal Creek 06,Reach-1

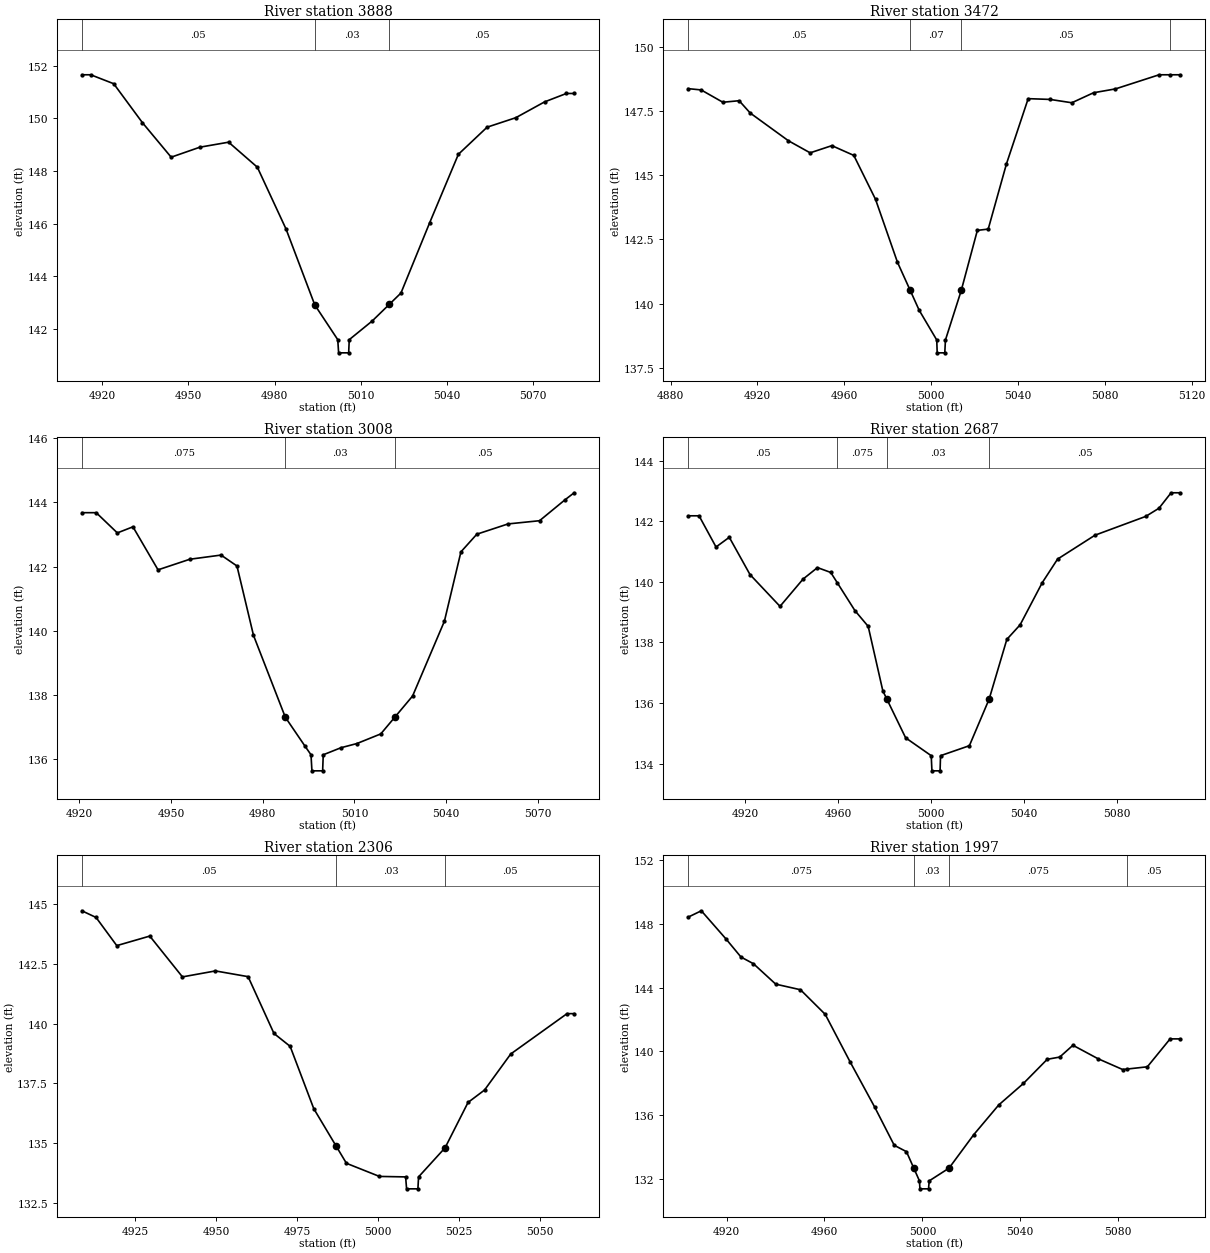
Type RM Length L Ch R = 1 ,3888    ,416,416,416
BEGIN DESCRIPTION:
Crystal Creek 060 11.0
END DESCRIPTION:
XS GIS Cut Line= 2
       3831566.7     10072678.02       3831738.1     10072678.02
#Sta/Elev= 24
  4912.9  151.66    4916  151.66    4924  151.32    4934  149.84    4944  148.53
    4954  148.91    4964   149.1    4974  148.15    4984   145.8    4994  142.92
    5002   141.6  5002.3   141.1  5005.8   141.1    5006   141.6    5014  142.31
 5019.91 142.937    5024  143.37    5034  146.04    5044  148.64    5054  149.67
    5064  150.03    5074  150.63  5081.6  150.95  5084.3  150.95
#Mann= 3 , 0 , 0
  4912.9     .05       0    4994     .03       0 5019.91     .05       0
Bank Sta=4994,5019.91
XS Rating Curve= 0 ,0
Exp/Cntr=0.3,0.1

Type RM Length L Ch R = 1 ,3472    ,464,464,464
BEGIN DESCRIPTION:
Crystal Creek 060 10.0
END DESCRIPTION:
XS GIS Cut Line= 2
      3831531.89     10073083.68      3831757.63     10073104.52
#Sta/Elev= 29
  4888.1  148.37  4894.1  148.32  4904.1  147.84  4911.6   147.9  4916.7  147.42
  4934.3  146.34  4944.3  145.87  4954.3  146.15  4964.4  145.77  4974.4  144.06
  4984.5  141.61 4990.38 140.511  4994.5  139.74  5002.6  138.58  5002.8  138.08
  5006.3  138.08  5006.6  138.58 5013.88 140.509  5021.3  142.85  5026.3   142.9
  5034.7  145.44  5044.7  147.98  5054.8  147.95  5064.8  147.82  5074.8  148.21
  5084.9  148.36    5105  148.91  5109.8  148.91  5114.8  148.91
#Mann= 4 ,-1 , 0
  4888.1     .05       0 4990.38     .07       0 5013.88     .05       0
  5109.8     .05       0
Bank Sta=4990.38,5013.88
XS Rating Curve= 0 ,0
Exp/Cntr=0.3,0.1

Type RM Length L Ch R = 1 ,3008    ,321,321,321
BEGIN DESCRIPTION:
Crystal Creek 060 9.0
END DESCRIPTION:
XS GIS Cut Line= 2
      3831663.84     10073569.81      3831818.68     10073526.06
#Sta/Elev= 27
  4920.9  143.68  4925.6  143.68  4932.5  143.05  4937.6  143.24  4945.8   141.9
  4956.2  142.23  4966.4  142.36  4971.6  142.02    4977  139.86  4987.4  137.31
  4993.9   136.4  4995.8  136.14  4996.1  135.64  4999.6  135.64  4999.8  136.14
  5005.6  136.36  5010.8  136.49  5018.6  136.79 5023.14 137.305    5029  137.97
  5039.4   140.3  5044.8  142.46    5050  143.01  5060.2  143.33  5070.5  143.43
  5078.8  144.08  5081.8   144.3
#Mann= 3 , 0 , 0
  4920.9    .075       0  4987.4     .03       0 5023.14     .05       0
Bank Sta=4987.4,5023.14
XS Rating Curve= 0 ,0
Exp/Cntr=0.3,0.1

Type RM Length L Ch R = 1 ,2687    ,381,381,381
BEGIN DESCRIPTION:
Crystal Creek 060 8.0
END DESCRIPTION:
XS GIS Cut Line= 2
      3831674.54     10073809.04       3831859.9      10073911.1
#Sta/Elev= 30
  4895.6  142.18  4900.3  142.18  4907.6  141.15  4913.3  141.47  4922.2  140.24
  4935.1  139.19    4945  140.09  4951.2  140.47  4956.9  140.31  4959.8  139.96
  4967.3  139.05    4973  138.53  4979.3   136.4 4981.01  136.13  4989.1  134.85
  5000.1  134.26  5000.4  133.76  5003.9  133.76  5004.1  134.26  5016.5  134.59
    5025  136.13  5032.6   138.1  5038.3  138.58  5047.8  139.97  5054.4  140.75
  5070.5  141.54  5092.3  142.16    5098  142.43  5103.2  142.94  5107.2  142.94
#Mann= 4 ,-1 , 0
  4895.6     .05       0  4959.8    .075       0 4981.01     .03       0
    5025     .05       0
Bank Sta=4981.01,5025
XS Rating Curve= 0 ,0
Exp/Cntr=0.3,0.1

Type RM Length L Ch R = 1 ,2306    ,309,309,309
BEGIN DESCRIPTION:
Crystal Creek 060 7.0
END DESCRIPTION:
XS GIS Cut Line= 2
      3831557.19     10074205.56       3831707.2     10074231.26
#Sta/Elev= 23
  4908.5  144.73  4912.9  144.45  4919.3  143.27  4929.5  143.67  4939.6  141.96
  4949.8  142.21  4959.9  141.97  4967.9  139.59  4972.9  139.05  4980.2  136.44
 4987.14 134.866  4990.3  134.15  5000.5   133.6  5008.6  133.58  5008.9  133.08
  5012.4  133.08  5012.6  133.58  5020.8   134.8  5027.9   136.7    5033  137.22
  5041.1  138.73  5058.5  140.42  5060.7  140.42
#Mann= 3 , 0 , 0
  4908.5     .05       0 4987.14     .03       0  5020.8     .05       0
Bank Sta=4987.14,5020.8
XS Rating Curve= 0 ,0
Exp/Cntr=0.3,0.1

Type RM Length L Ch R = 1 ,1997    ,355,355,355
BEGIN DESCRIPTION:
Crystal Creek 060 6.0
END DESCRIPTION:
XS GIS Cut Line= 2
      3831592.53      10074539.6      3831791.18     10074508.34
#Sta/Elev= 30
  4904.3  148.42  4909.7  148.82  4919.8  147.05  4925.9  145.92    4931   145.5
  4940.1  144.22  4950.2  143.87  4960.3  142.33  4970.4  139.37  4980.6  136.49
  4988.5  134.12  4993.5  133.72  4996.5 132.684  4998.8  131.89    4999  131.39
  5002.5  131.39  5002.8  131.89  5010.9  132.69    5021  134.79  5031.2  136.65
  5041.3     138    5051  139.51  5056.1  139.65  5061.5  140.39  5071.7  139.55
  5081.8  138.87  5083.7   138.9  5091.9  139.04  5101.2  140.79  5105.4  140.79
#Mann= 4 ,-1 , 0
  4904.3    .075       0  4996.5     .03       0  5010.9    .075       0
  5083.7     .05       0
Bank Sta=4996.5,5010.9
XS Rating Curve= 0 ,0
Exp/Cntr=0.3,0.1

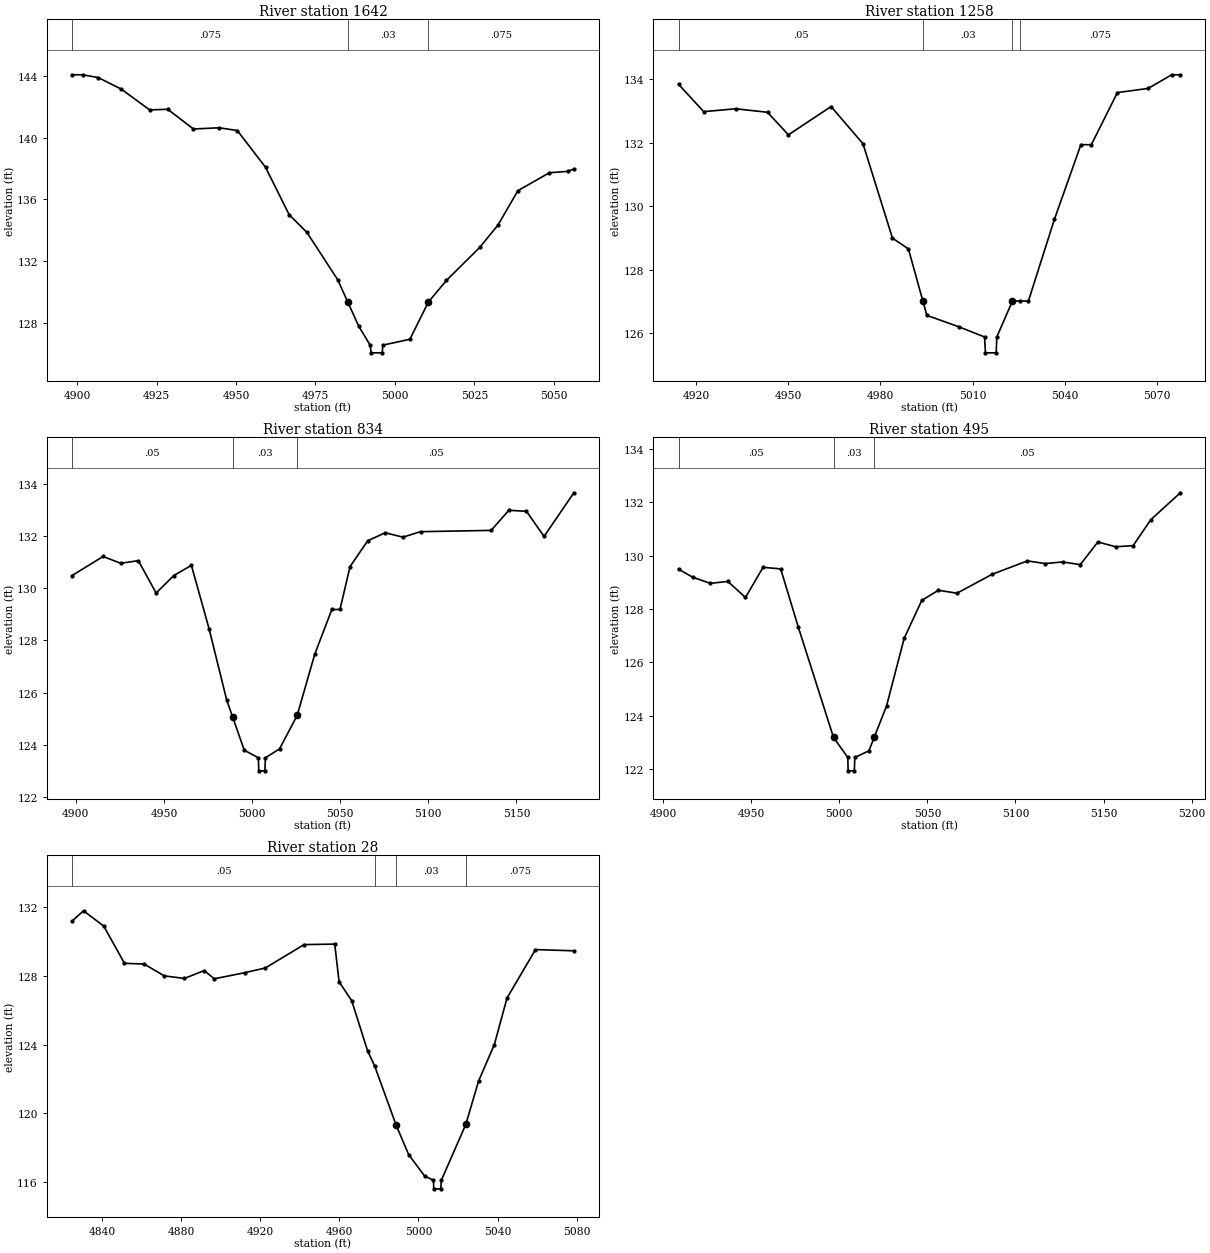
Type RM Length L Ch R = 1 ,1642    ,384,384,384
BEGIN DESCRIPTION:
Crystal Creek 060 5.0
END DESCRIPTION:
XS GIS Cut Line= 2
      3831674.23     10074919.18      3831813.32     10074844.45
#Sta/Elev= 28
  4898.4  144.09  4901.7  144.09  4906.6  143.91  4913.9  143.16  4922.8  141.81
  4928.5  141.85  4936.6  140.57  4944.7  140.65  4950.4  140.47  4959.3  138.08
  4966.7  135.01  4972.3  133.86    4982  130.78 4985.16 129.339  4988.6  127.77
  4992.2  126.54  4992.5  126.04    4996  126.04  4996.2  126.54  5004.7  126.92
  5010.5  129.33  5016.2  130.74  5026.7  132.89  5032.4  134.33  5038.7  136.57
  5048.6  137.73  5054.3  137.82  5056.3  137.97
#Mann= 3 , 0 , 0
  4898.4    .075       0 4985.16     .03       0  5010.5    .075       0
Bank Sta=4985.16,5010.5
XS Rating Curve= 0 ,0
Exp/Cntr=0.3,0.1

Type RM Length L Ch R = 1 ,1258    ,424,424,424
BEGIN DESCRIPTION:
Crystal Creek 060 4.0
END DESCRIPTION:
XS GIS Cut Line= 3
      3832032.66     10075158.93      3832069.33     10075029.57
      3832068.39     10075000.54
#Sta/Elev= 26
  4914.2  133.84  4922.4  132.98  4932.8  133.07  4943.2  132.96    4950  132.25
  4963.9  133.14  4974.3  131.97  4983.9     129  4989.1  128.66 4993.78  127.03
  4995.1  126.57  5005.5  126.21  5013.9  125.89  5014.2  125.39  5017.7  125.39
  5017.9  125.89    5023  127.02  5025.6  127.02  5028.2  127.02  5036.7   129.6
  5045.3  131.94  5048.7  131.94  5057.2  133.58  5067.2  133.71  5074.9  134.14
  5077.7  134.14
#Mann= 4 ,-1 , 0
  4914.2     .05       0 4993.78     .03       0    5023     .05       0
  5025.6    .075       0
Bank Sta=4993.78,5023
XS Rating Curve= 0 ,0
Exp/Cntr=0.3,0.1

Type RM Length L Ch R = 1 ,834     ,339,339,339
BEGIN DESCRIPTION:
Crystal Creek 060 3.0
END DESCRIPTION:
XS GIS Cut Line= 3
      3832476.31     10075198.69      3832481.74     10075046.76
      3832477.46     10074914.16
#Sta/Elev= 30
  4897.9  130.48  4915.5  131.21  4925.5  130.95  4935.5  131.05  4945.6  129.81
  4955.6  130.48  4965.6  130.87  4975.6  128.45  4985.6  125.72 4989.01 125.062
  4995.6  123.79  5003.6   123.5  5003.8     123  5007.3     123  5007.6   123.5
  5015.6  123.84  5025.6  125.12  5035.6  127.47  5045.3  129.18  5049.9  129.18
  5055.6  130.82  5065.6  131.81  5075.6  132.12  5085.6  131.95  5095.6  132.16
  5135.7  132.21  5145.7  132.98  5155.7  132.94  5165.7  131.98  5182.6  133.65
#Mann= 3 , 0 , 0
  4897.9     .05       0 4989.01     .03       0  5025.6     .05       0
Bank Sta=4989.01,5025.6
XS Rating Curve= 0 ,0
Exp/Cntr=0.3,0.1

Type RM Length L Ch R = 1 ,495     ,467,467,467
BEGIN DESCRIPTION:
Crystal Creek 060 2.0
END DESCRIPTION:
XS GIS Cut Line= 3
      3832814.86     10075209.06      3832820.28     10075057.18
      3832815.99     10074924.33
#Sta/Elev= 30
  4908.7  129.49  4916.7  129.19  4926.7  128.96  4936.7  129.03  4946.7  128.43
  4956.7  129.56  4966.7   129.5  4976.7  127.32  4996.7  123.19  5004.8  122.44
    5005  121.94  5008.5  121.94  5008.8  122.44  5016.8  122.69 5019.77 123.189
  5026.8  124.37  5036.8   126.9  5046.8  128.32  5056.2   128.7  5066.8  128.59
  5086.8   129.3  5106.8   129.8  5116.8   129.7  5126.8  129.76  5136.8  129.66
  5146.8  130.51  5156.8  130.33  5166.8  130.37  5176.8  131.34  5193.6  132.35
#Mann= 3 , 0 , 0
  4908.7     .05       0  4996.7     .03       0 5019.77     .05       0
Bank Sta=4996.7,5019.77
XS Rating Curve= 0 ,0
Exp/Cntr=0.3,0.1

Type RM Length L Ch R = 1 ,28      ,0,0,0
BEGIN DESCRIPTION:
Crystal Creek 060 1.0
END DESCRIPTION:
XS GIS Cut Line= 3
      3833092.16     10075221.76      3833222.32     10075248.31
       3833317.1     10075173.32
#Sta/Elev= 30
  4824.9  131.19  4830.7  131.79  4840.9   130.9  4851.4  128.73  4861.3  128.69
  4871.5     128  4881.7  127.85  4891.7  128.31  4896.8  127.83  4912.4  128.19
  4922.6  128.46  4942.2  129.82  4957.7  129.85  4959.9  127.66  4966.3  126.55
  4974.3  123.64  4977.9  122.75  4988.8  119.29  4995.1  117.59  5003.1  116.35
  5007.6   116.1  5007.8   115.6  5011.3   115.6  5011.6   116.1    5024  119.36
  5030.4  121.87  5038.4     124  5044.8  126.71  5059.2  129.53  5078.6  129.46
#Mann= 4 ,-1 , 0
  4824.9     .05       0  4977.9    .075       0  4988.8     .03       0
    5024    .075       0
Bank Sta=4988.8,5024
XS Rating Curve= 0 ,0
Exp/Cntr=0.3,0.1