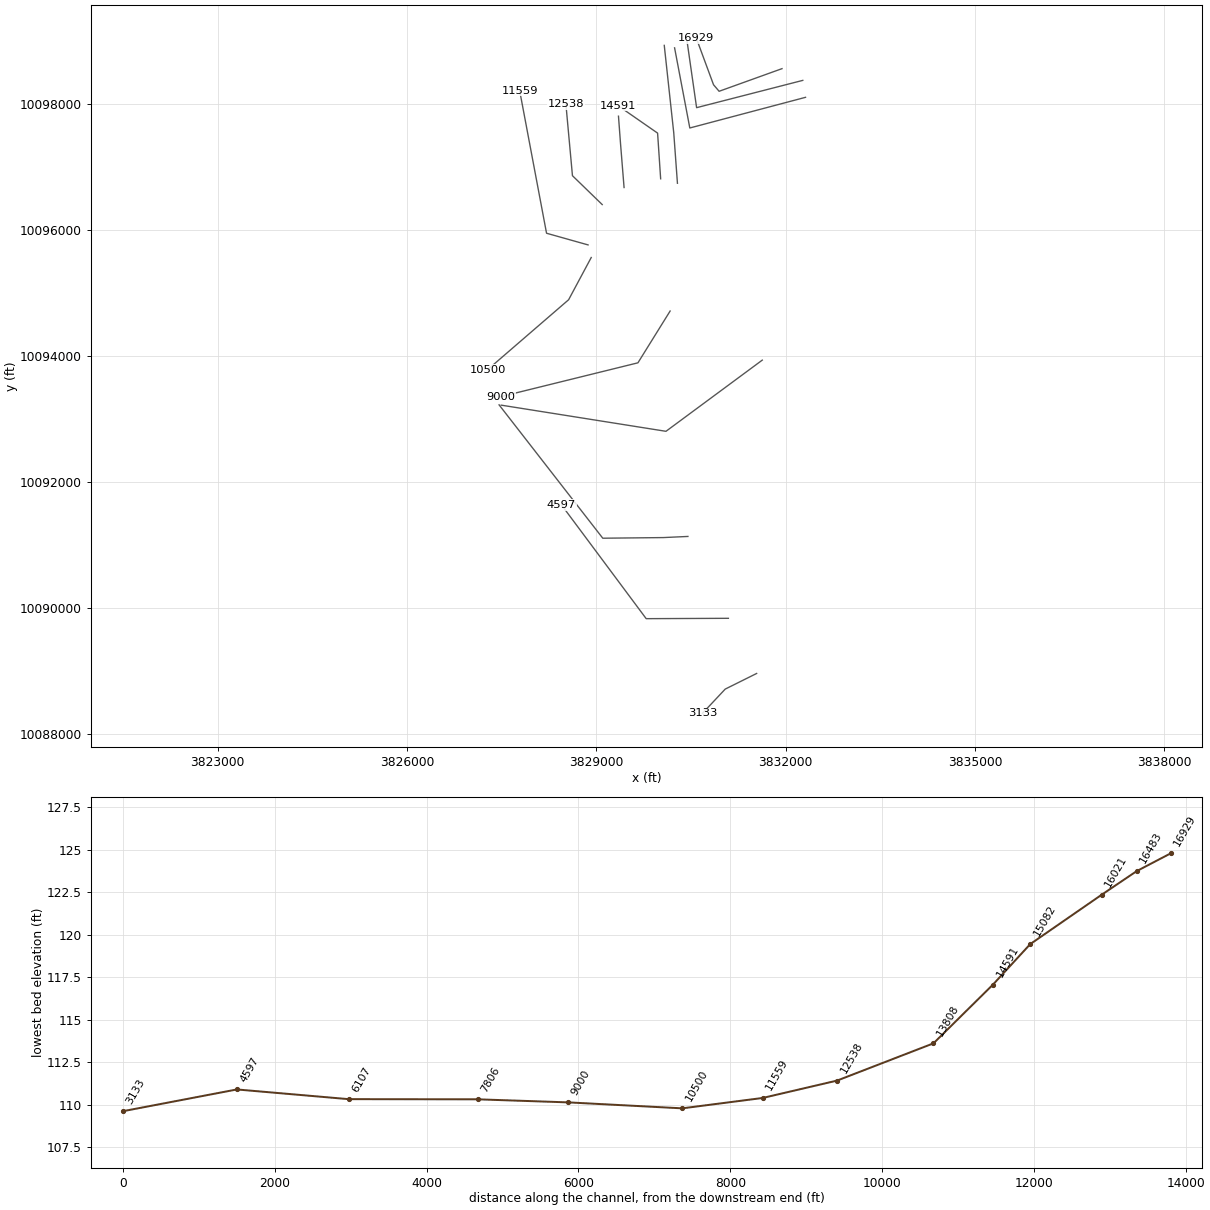
HEC-RAS study GRAND LAKE CREEK.prj: GRAND LAKE CREEK Base Level Engineering

--- GRAND LAKE CREEK.g01 (geometry) --- (continued)

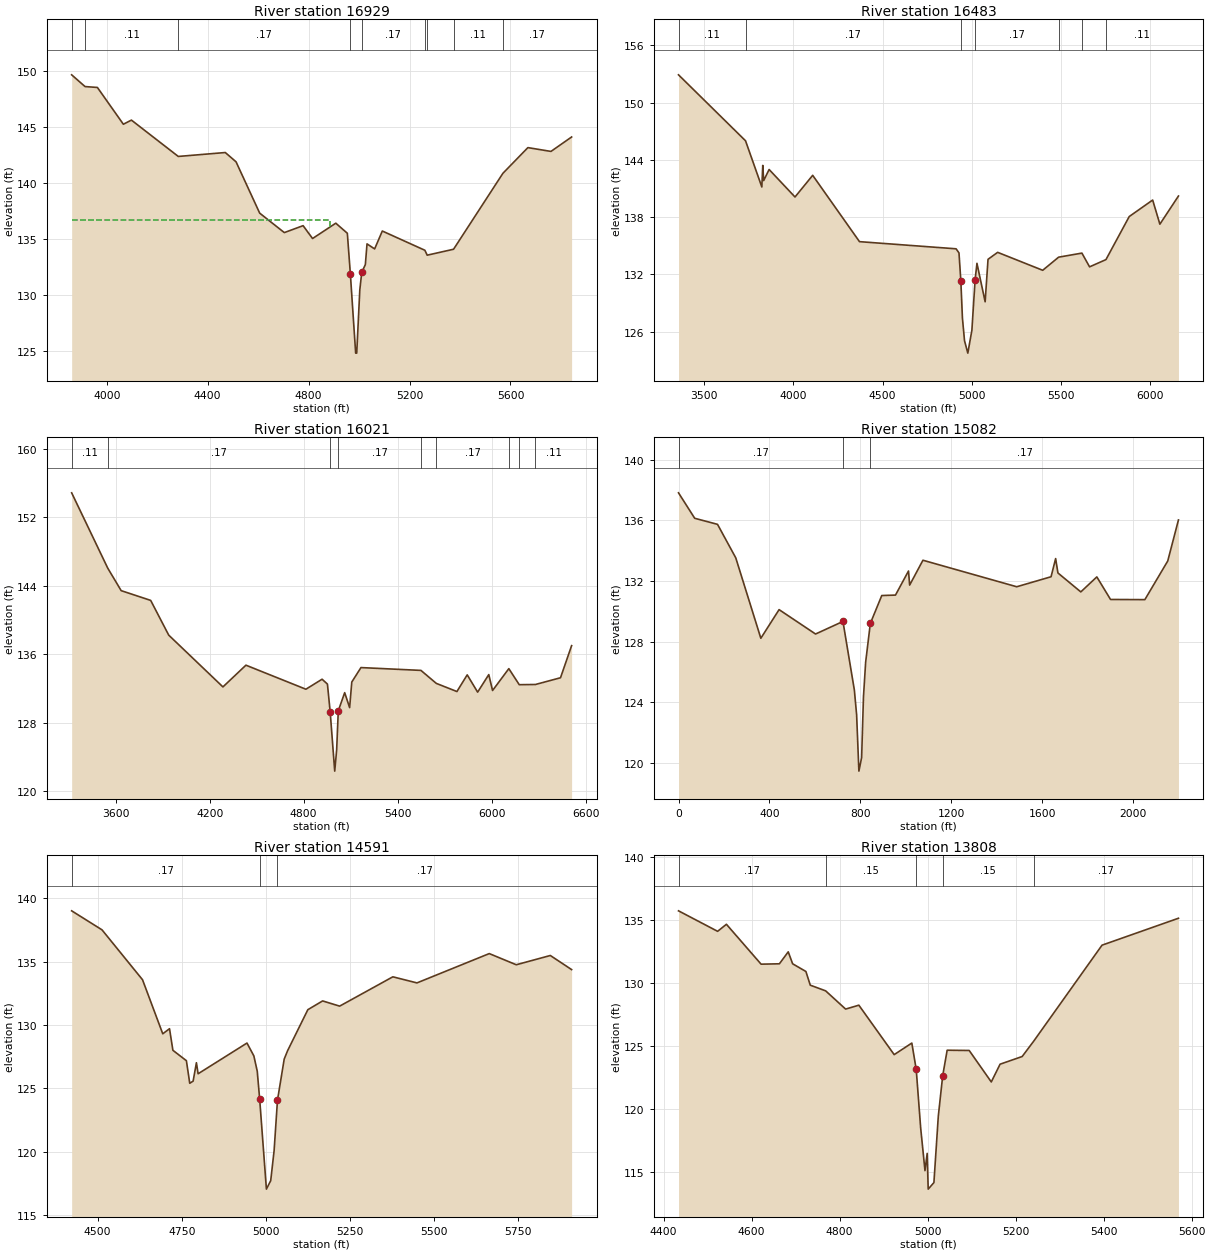
Type RM Length L Ch R = 1 ,16929   ,446,446,446
BEGIN DESCRIPTION:
GRAND LAKE CREEK 33.0
END DESCRIPTION:
XS GIS Cut Line= 4
      3831940.58     10098560.02       3830944.1     10098200.66
      3830855.55     10098304.83      3830584.04     10099041.47
#Sta/Elev= 30
  3861.2  149.67  3914.2  148.62  3963.2  148.54  4066.1  145.25    4098  145.62
  4283.7  142.37    4470  142.72  4512.6  141.89  4606.3   137.3  4703.9  135.56
  4778.3  136.18  4815.8  135.03  4907.9   136.4  4953.6   135.5 4965.67131.8385
  4986.6  124.78  4990.8  124.78    5003  130.43  5010.7     132    5025   132.7
  5031.6  134.55  5061.8   134.1  5092.2   135.7  5260.8  133.98  5270.1  133.54
  5374.5  134.07    5570  140.86  5669.1  143.16  5760.5  142.82  5842.3  144.11
#Mann= 9 ,-1 , 0
  3861.2     .17       0  3914.2     .11       0  4283.7     .17       0
 4965.67     .06       0  5010.7     .17       0  5260.8     .15       0
  5270.1     .17       0  5374.5     .11       0    5570     .17       0
#XS Ineff= 2 , 0
         4884.26  136.65
Permanent Ineff=
       F       F
Bank Sta=4965.67,5010.7
XS Rating Curve= 0 ,0
Exp/Cntr=0.3,0.1

Type RM Length L Ch R = 1 ,16483   ,462,462,462
BEGIN DESCRIPTION:
GRAND LAKE CREEK 32.0
END DESCRIPTION:
XS GIS Cut Line= 3
      3832270.09     10098373.87      3830587.47     10097940.53
      3830436.52     10098994.15
#Sta/Elev= 30
  3356.2   152.9  3731.8  145.99  3823.2  141.15  3828.4  143.41  3833.6  141.82
    3864  142.98  4009.1   140.1  4108.2  142.37  4370.5  135.42  4911.9  134.67
  4928.1  134.24  4938.4  131.34  4947.4  127.42  4959.1  125.04  4977.6  123.74
  5000.4  126.14 5018.55 131.444  5028.8  133.15  5074.7  129.12  5090.9  133.57
  5144.8   134.3  5397.3  132.42  5486.5133.7938    5617  134.22    5660  132.78
  5751.8133.5395  5882.2  138.05  6013.6  139.78    6054  137.25  6158.1   140.2
#Mann= 7 ,-1 , 0
  3356.2     .11       0  3731.8     .17       0  4938.4     .06       0
 5018.55     .17       0  5486.5     .15       0    5617     .17       0
  5751.8     .11       0
Bank Sta=4938.4,5018.55
XS Rating Curve= 0 ,0
Exp/Cntr=0.3,0.1

Type RM Length L Ch R = 1 ,16021   ,940,940,940
BEGIN DESCRIPTION:
GRAND LAKE CREEK 31.0
END DESCRIPTION:
XS GIS Cut Line= 3
       3832313.5     10098104.78      3830479.87     10097617.84
       3830238.6      10098890.7
#Sta/Elev= 30
  3318.4  154.87  3549.1  146.06  3634.6  143.44    3823   142.3  3938.3  138.24
  4284.4  132.19  4431.3  134.73  4814.2  131.92  4917.6  133.09  4951.8  132.52
  4969.4  129.26  4998.3  122.35  5010.7  124.83  5021.1   129.4    5062  131.52
  5093.5  129.77  5107.3  132.76  5165.9  134.45  5548.9134.1202  5647.1132.6024
  5778.7  131.65  5844.4   133.6    5911  131.58  5982.2  133.63  6006.3  131.77
  6110.2134.3253  6176.7132.4506  6280.1132.4734  6440.2  133.26  6511.1  137.01
#Mann= 9 ,-1 , 0
  3318.4     .11       0  3549.1     .17       0  4969.4     .06       0
  5021.1     .17       0  5548.9     .11       0  5647.1     .17       0
  6110.2     .11       0  6176.7     .17       0  6280.1     .11       0
Bank Sta=4969.4,5021.1
XS Rating Curve= 0 ,0
Exp/Cntr=0.3,0.1

Type RM Length L Ch R = 1 ,15082   ,491,491,491
XS GIS Cut Line= 3
      3830283.85     10096740.03      3830225.26     10097542.98
      3830075.02     10098929.71
#Sta/Elev= 30
       0  137.82    71.2  136.14   171.5  135.74   251.7  133.53     362  128.22
   442.2  130.11   602.6   128.5     723  129.33   773.1  124.81   783.1  123.17
   793.1  119.45   805.1  120.34   813.2  124.35   822.8  126.64   843.4   129.2
   893.7  131.04     954  131.07  1011.2  132.66  1016.3  131.73  1074.7  133.37
  1487.1  131.62    1638  132.28  1658.1  133.48  1668.2  132.53  1768.8  131.28
  1839.2  132.27  1899.5  130.78  2050.4  130.77    2151  133.32  2198.1  136.03
#Mann= 3 , 0 , 0
       0     .17       0     723     .06       0   843.4     .17       0
Bank Sta=723,843.4
XS Rating Curve= 0 ,0
Exp/Cntr=0.3,0.1

Type RM Length L Ch R = 1 ,14591   ,783,783,783
BEGIN DESCRIPTION:
GRAND LAKE CREEK 29.0
END DESCRIPTION:
XS GIS Cut Line= 3
      3830017.85     10096811.04      3829969.44     10097536.25
      3829347.06     10097969.41
#Sta/Elev= 30
  4422.9     139  4513.1   137.5  4633.4  133.57  4693.5  129.31  4713.6  129.71
  4723.6  128.01  4763.7  127.19  4773.7  125.41  4783.7  125.58  4793.5  127.03
  4798.5  126.16  4943.7  128.58  4964.1  127.57  4974.2  126.36 4981.47124.1354
  5001.4  117.07  5014.2  117.74  5024.3  120.11  5034.3  124.08  5054.3  127.32
  5064.4  127.98  5124.5  131.21  5168.4   131.9    5219  131.49    5377   133.8
  5448.6  133.32  5663.4  135.63  5743.6  134.75  5844.8  135.48    5908  134.37
#Mann= 3 , 0 , 0
  4422.9     .17       0 4981.47     .06       0  5034.3     .17       0
Bank Sta=4981.47,5034.3
XS Rating Curve= 0 ,0
Exp/Cntr=0.3,0.1

Type RM Length L Ch R = 1 ,13808   ,1270,1270,1270
BEGIN DESCRIPTION:
GRAND LAKE CREEK 27.0
END DESCRIPTION:
XS GIS Cut Line= 3
       3829438.2     10096672.49      3829382.64     10097362.64
      3829349.65     10097805.33
#Sta/Elev= 30
  4433.8  135.74  4522.7  134.11  4542.7  134.67  4621.5   131.5  4663.1  131.53
  4683.2  132.48  4693.2  131.53  4723.3  130.92  4733.3  129.83  4768.2  129.38
  4813.6  127.93  4843.7  128.24    4924  124.31  4964.1  125.23  4974.1  123.13
  4984.2  118.48    4994  115.09    4999  116.46  5001.3  113.62  5014.3  114.14
  5024.3  119.43  5034.3  122.64  5044.4  124.66  5094.5  124.64  5144.7  122.14
  5164.7  123.55  5214.9  124.16  5241.1  125.38  5396.4  133.01  5570.1  135.15
#Mann= 5 ,-1 , 0
  4433.8     .17       0  4768.2     .15       0  4974.1     .06       0
  5034.3     .15       0  5241.1     .17       0
Bank Sta=4974.1,5034.3
XS Rating Curve= 0 ,0
Exp/Cntr=0.3,0.1

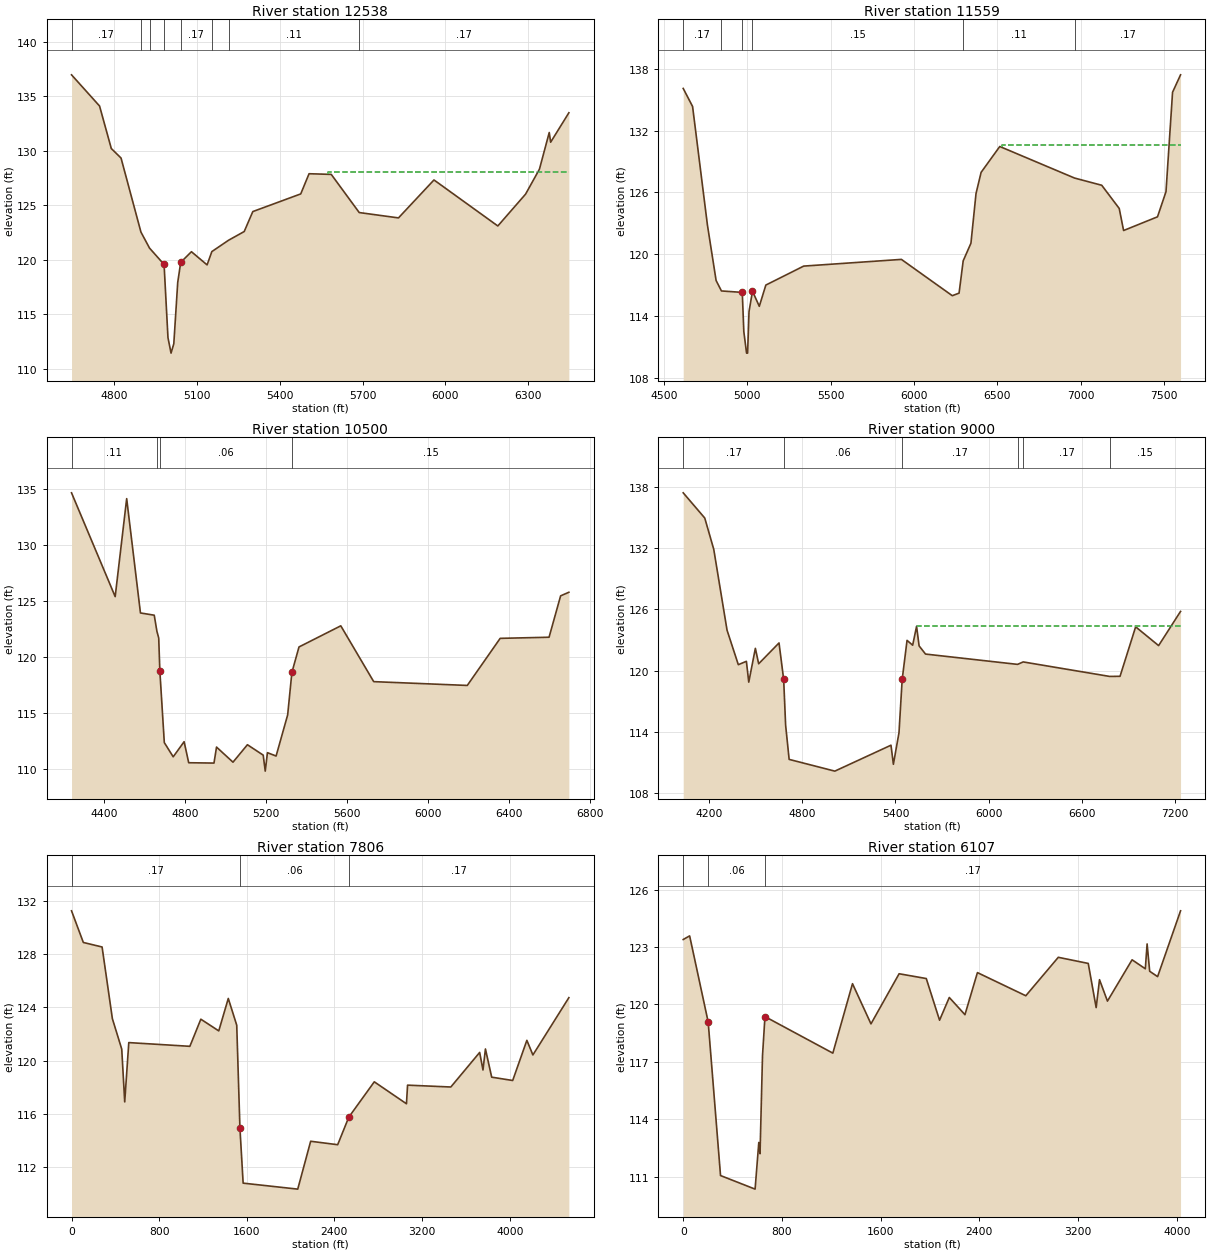
Type RM Length L Ch R = 1 ,12538   ,979,979,979
BEGIN DESCRIPTION:
GRAND LAKE CREEK 25.0
END DESCRIPTION:
XS GIS Cut Line= 3
      3829091.83     10096401.71      3828620.48     10096860.04
      3828516.41     10097997.04
#Sta/Elev= 30
  4647.3  136.95  4748.7  134.09  4791.2  130.19  4826.4  129.32  4898.4  122.53
  4929.5  121.06  4982.1  119.56  4996.2  112.85  5007.3  111.43  5017.3  112.29
  5031.5  117.92  5042.3119.7511  5081.1  120.73  5137.7  119.52  5154.9  120.74
  5215.3  121.78    5272  122.58  5303.1  124.41  5476.5  126.03  5506.6  127.88
  5586.9  127.82  5688.1  124.32  5830.1  123.83  5958.5  127.31  6189.5  123.09
  6289.9  126.01  6340.1   128.3  6375.5  131.66  6380.6  130.77  6446.5  133.47
#Mann= 8 ,-1 , 0
  4647.3     .17       0  4898.4     .15       0  4929.5     .17       0
  4982.1     .06       0  5042.3     .17       0  5154.9     .15       0
  5215.3     .11       0  5688.1     .17       0
#XS Ineff= 2 , 0
                         5576.75          128.07
Permanent Ineff=
       F       F
Bank Sta=4982.1,5042.3
XS Rating Curve= 0 ,0
Exp/Cntr=0.3,0.1

Type RM Length L Ch R = 1 ,11559   ,1059,1059,1059
BEGIN DESCRIPTION:
GRAND LAKE CREEK 23.0
END DESCRIPTION:
XS GIS Cut Line= 3
      3828867.85     10095761.07      3828209.89     10095946.41
       3827784.7      10098206.9
#Sta/Elev= 30
    4616  136.08  4672.2  134.33  4761.4  122.82  4813.4  117.45  4845.4  116.44
  4970.4   116.3  4979.6   112.5  4996.1  110.41  5002.3  110.41  5010.8  114.43
  5031.6  116.42  5072.5  114.95  5111.7  117.01  5338.8  118.85    5925   119.5
  6230.3  115.98    6271  116.23  6295.7  119.36  6342.2  121.07  6372.7  125.89
  6403.2  127.94  6515.2  130.45  6963.6  127.39  7126.8  126.69  7231.8  124.44
    7258   122.3  7461.5  123.63  7512.4  126.07  7551.8  135.71  7599.7   137.4
#Mann= 6 ,-1 , 0
    4616     .17       0  4845.4     .15       0  4970.4     .06       0
  5031.6     .15       0  6295.7     .11       0  6963.6     .17       0
#XS Ineff= 2 , 0
                         6525.58          130.57
Permanent Ineff=
       F       F
Bank Sta=4970.4,5031.6
XS Rating Curve= 0 ,0
Exp/Cntr=0.3,0.1

Type RM Length L Ch R = 1 ,10500   ,1500,1500,1500
BEGIN DESCRIPTION:
GRAND LAKE CREEK 21.0
END DESCRIPTION:
XS GIS Cut Line= 3
      3828917.86     10095561.08      3828559.73     10094890.41
      3827278.77     10093782.36
#Sta/Elev= 30
  4239.7  134.68  4455.1   125.4  4511.8  134.16  4579.8  123.94  4647.8  123.74
    4661   122.3  4669.9   121.7  4675.5  118.75  4697.5  112.35  4741.4  111.08
  4795.2  112.43  4817.9  110.55  4942.6  110.52  4955.2  111.95  5036.4   110.6
  5107.6  112.16  5185.5  111.23  5195.5   109.8  5206.4  111.45  5249.1  111.15
  5306.2  114.83    5327  118.62  5362.1   120.9  5568.3  122.79  5730.7   117.8
  6192.4  117.46  6354.8  121.67    6596  121.77    6653  125.47  6693.7  125.79
#Mann= 4 ,-1 , 0
  4239.7     .11       0    4661     .17       0  4675.5     .06       0
    5327     .15       0
Bank Sta=4675.5,5327
XS Rating Curve= 0 ,0
Exp/Cntr=0.3,0.1

Type RM Length L Ch R = 1 ,9000    ,1194,1194,1194
BEGIN DESCRIPTION:
GRAND LAKE CREEK 18.0
END DESCRIPTION:
XS GIS Cut Line= 3
      3830167.85     10094711.07      3829658.07     10093888.89
      3827487.12      10093351.8
#Sta/Elev= 30
  4032.6  137.42  4171.4  134.95  4229.3  131.89    4315  123.96  4387.6  120.58
  4439.6  120.91  4454.9  118.87  4497.4  122.18  4518.7  120.67  4649.8  122.71
  4679.7  119.14  4692.3  114.66    4715   111.3  5009.3  110.15  5371.1  112.69
  5386.5  110.82  5422.6  113.91  5443.2  119.13  5474.5  122.96  5510.8  122.49
  5535.9  124.34  5552.2  122.42  5593.6  121.62  6186.5  120.61  6222.7  120.85
  6779.4  119.43  6846.6  119.44  6947.2  124.29  7095.1  122.45  7236.4   125.8
#Mann= 6 ,-1 , 0
  4032.6     .17       0  4679.7     .06       0  5443.2     .17       0
  6186.5     .15       0  6222.7     .17       0  6779.4     .15       0
#XS Ineff= 2 , 0
                          5536.1          124.39
Permanent Ineff=
       F       F
Bank Sta=4679.7,5443.2
XS Rating Curve= 0 ,0
Exp/Cntr=0.3,0.1

Type RM Length L Ch R = 1 ,7806    ,1699,1699,1699
XS GIS Cut Line= 3
      3831627.86     10093931.44      3830102.21     10092801.17
      3827491.74     10093216.51
#Sta/Elev= 30
       0  131.26   107.8  128.88   278.9  128.54   372.9  123.15   458.4  120.86
   485.5  116.89   522.7  121.35  1080.3  121.07  1180.5  123.11  1344.1  122.23
    1431  124.67  1508.1  122.66  1537.4   114.9  1566.6  110.78  2065.1  110.33
    2183  113.93  2429.7  113.67  2530.9  115.74  2763.8   118.4  3057.5  116.75
  3067.6  118.15  3462.5  118.01  3725.8  120.61  3756.1  119.29  3778.5  120.87
  3835.6  118.75  4027.3   118.5  4156.7  121.52  4211.8  120.42  4540.1  124.73
#Mann= 3 , 0 , 0
       0     .17       0  1537.4     .06       0  2530.9     .17       0
Bank Sta=1537.4,2530.9
XS Rating Curve= 0 ,0
Exp/Cntr=0.3,0.1

Type RM Length L Ch R = 1 ,6107    ,1471,1471,1471
XS GIS Cut Line= 4
      3830449.94     10091131.63      3830061.02     10091113.68
      3829100.84      10091103.5      3827457.69     10093221.35
#Sta/Elev= 30
       0  123.39    52.1  123.58   202.3  119.08   302.4  111.05   582.5  110.34
   612.5  112.78   622.5  112.19   642.5  117.31   662.5  119.36  1212.5  117.45
  1371.8  121.08  1521.5  118.98  1749.6   121.6  1969.6  121.35  2077.3  119.17
  2156.1  120.36  2283.1  119.46  2384.2  121.66  2776.1  120.45  3039.5  122.46
  3282.1  122.14  3346.3  119.83  3373.5  121.29  3437.8  120.17  3637.4  122.33
  3744.7  121.86  3759.1  123.16    3780  121.73  3844.2  121.45  4030.1  124.89
#Mann= 3 , 0 , 0
       0     .17       0   202.3     .06       0   662.5     .17       0
Bank Sta=202.3,662.5
XS Rating Curve= 0 ,0
Exp/Cntr=0.3,0.1

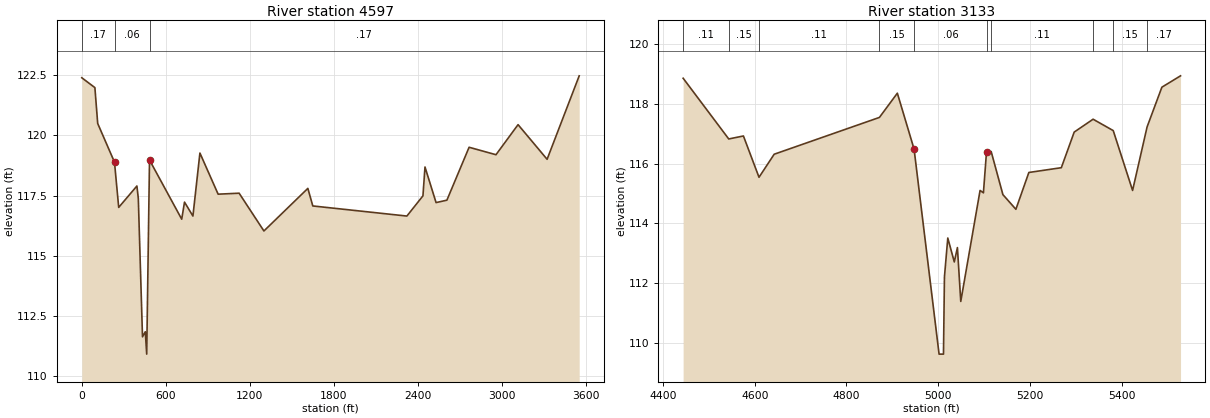
Type RM Length L Ch R = 1 ,4597    ,1503,1503,1503
XS GIS Cut Line= 3
       3831091.4     10089831.57      3829788.72     10089826.02
      3828447.26     10091631.52
#Sta/Elev= 30
       0   122.4    93.6  121.99   113.6   120.5   233.6  118.89   263.6  117.01
   393.6   117.9   403.6  117.39   433.6  111.63   453.6  111.84   463.6  110.91
   483.6  118.98   713.6  116.52   733.6  117.23   793.6  116.65   843.6  119.27
   973.6  117.56  1123.6   117.6  1300.6  116.03  1614.3   117.8  1649.7  117.07
  2321.5  116.65  2436.2  117.49  2450.8  118.69  2529.9  117.21  2607.2  117.31
  2765.8  119.51  2957.7   119.2  3115.4  120.45  3322.8  119.01    3552  122.48
#Mann= 3 , 0 , 0
       0     .17       0   233.6     .06       0   483.6     .17       0
Bank Sta=233.6,483.6
XS Rating Curve= 0 ,0
Exp/Cntr=0.3,0.1

Type RM Length L Ch R = 1 ,3133    ,0,0,0
BEGIN DESCRIPTION:
GRAND LAKE CREEK 6.0
END DESCRIPTION:
XS GIS Cut Line= 3
      3831538.61     10088955.71      3831040.87     10088707.48
      3830679.19     10088321.99
#Sta/Elev= 30
  4443.8  118.85  4543.3  116.82  4575.3  116.92  4609.3  115.54  4642.4  116.31
  4871.9  117.54    4911  118.35  4947.5  116.48    5002  109.63  5011.6  109.63
  5013.7  112.21    5021  113.51  5035.2  112.71    5042  113.19  5049.3  111.39
  5091.4   115.1  5098.7  115.02  5105.5   116.4  5115.6   116.4  5141.2  114.96
  5169.5  114.47  5197.8   115.7  5268.6  115.86  5296.7  117.05  5337.9  117.48
  5381.8   117.1    5424   115.1  5455.6  117.22  5487.9  118.55  5528.6  118.93
#Mann= 10 ,-1 , 0
  4443.8     .11       0  4543.3     .15       0  4609.3     .11       0
  4871.9     .15       0  4947.5     .06       0  5105.5     .15       0
  5115.6     .11       0  5337.9     .17       0  5381.8     .15       0
  5455.6     .17       0
Bank Sta=4947.5,5105.5
XS Rating Curve= 0 ,0
Exp/Cntr=0.3,0.1

Chan Stop Cuts=-1
Use User Specified Reach Order=0
Composite Channel Slope=5

--- GRAND LAKE CREEK.g10 (geometry) ---

Geom Title=Existing Conditions
Program Version=4.10

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
River Reach=GRAND LAKE CREEK,Reach-1

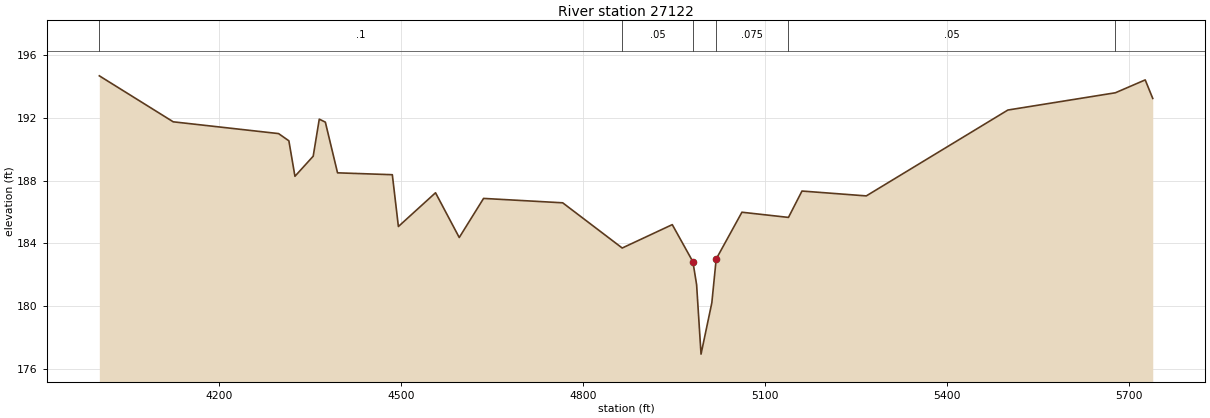
Type RM Length L Ch R = 1 ,27122   ,578,578,578
BEGIN DESCRIPTION:
GRAND LAKE CREEK 53.0
END DESCRIPTION:
XS GIS Cut Line= 3
      3834899.25      10106823.2      3833904.79     10106900.93
      3833376.11     10107416.85
#Sta/Elev= 30
  4002.5  194.67  4124.3  191.74  4297.9  190.99  4314.9  190.53  4324.9  188.27
    4355  189.55    4365  191.91    4375  191.72  4395.1  188.49  4485.4  188.37
  4495.4  185.07  4556.6  187.22  4595.7  184.37  4635.8  186.86  4766.2  186.58
  4864.3   183.7  4946.8  185.19 4980.78 182.827  4986.9  181.37  4994.2  176.94
    5012  180.21  5019.2     183  5061.6  185.98  5138.3  185.65  5160.6  187.33
  5266.6  187.02  5499.9  192.49  5677.1  193.59  5726.3  194.41  5738.7  193.23
#Mann= 6 ,-1 , 0
  4002.5      .1       0  4864.3     .05       0 4980.78     .07       0
  5019.2    .075       0  5138.3     .05       0  5677.1    .075       0
Bank Sta=4980.78,5019.2
XS Rating Curve= 0 ,0
Exp/Cntr=0.3,0.1