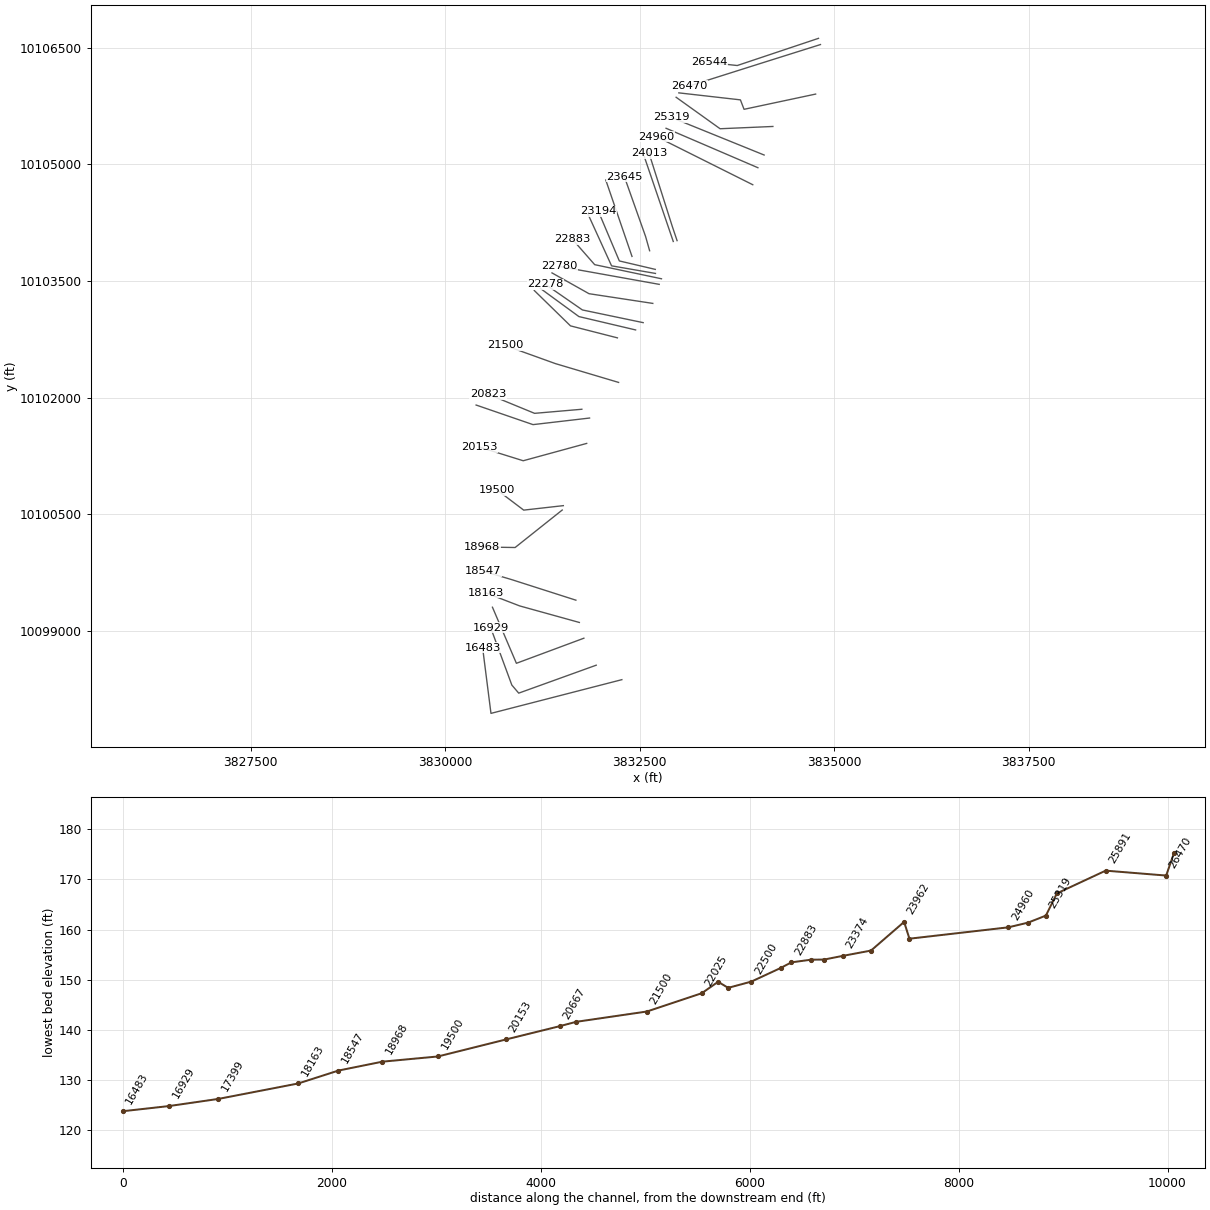
HEC-RAS study GRAND LAKE CREEK.prj: GRAND LAKE CREEK Base Level Engineering

--- GRAND LAKE CREEK.g10 (geometry) --- (continued)

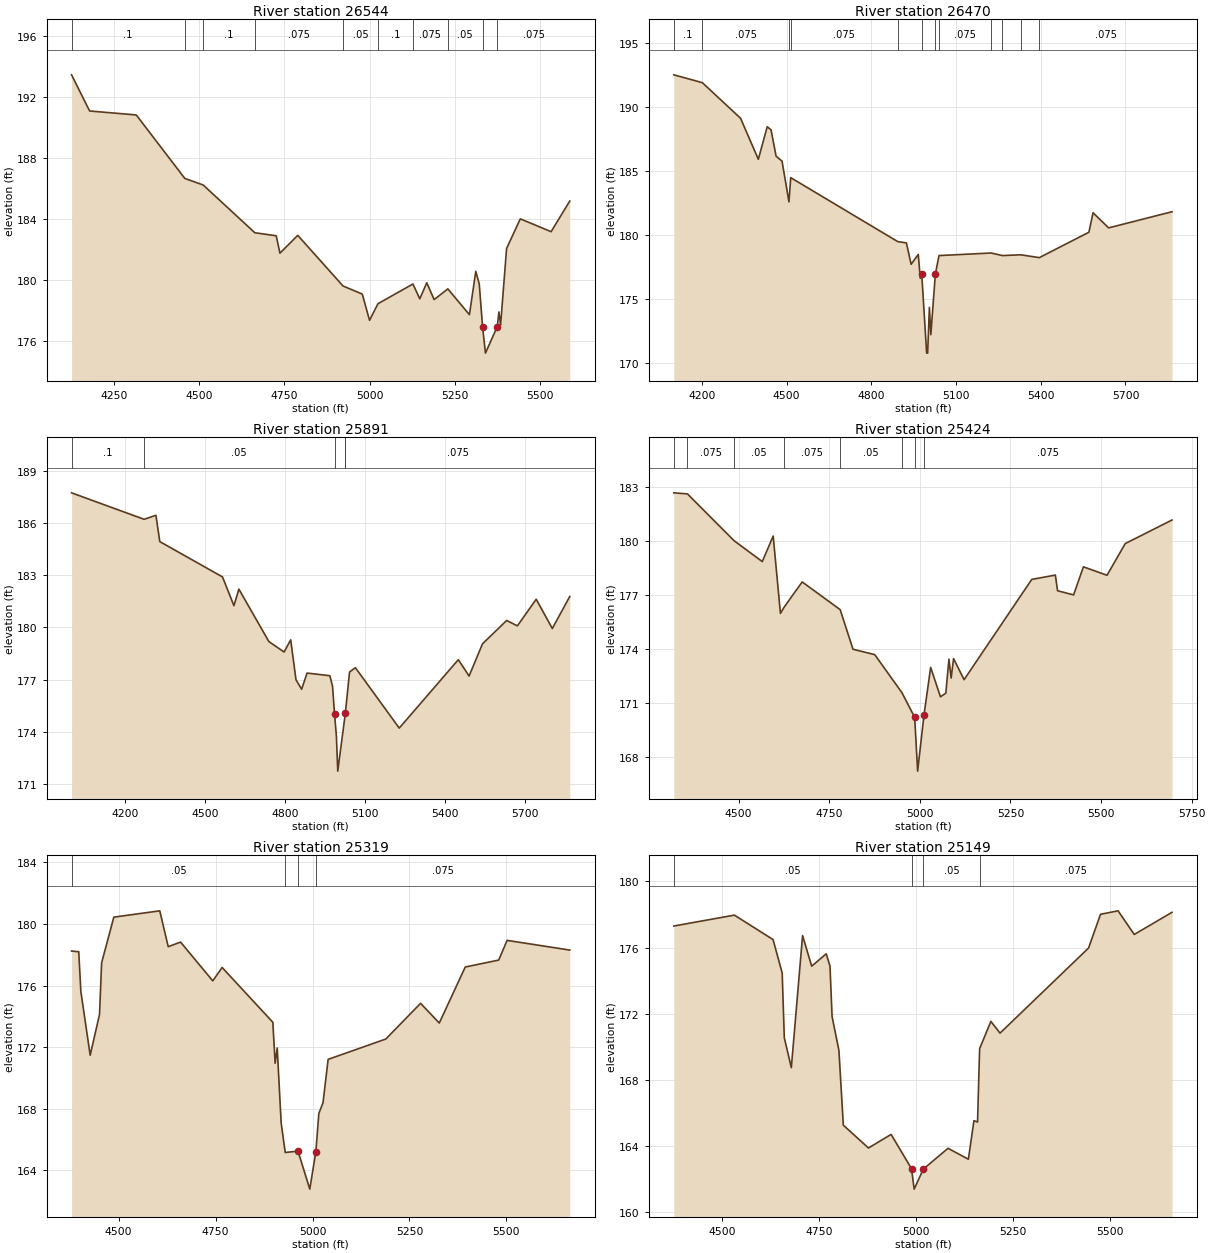
Type RM Length L Ch R = 1 ,26544   ,74,74,74
BEGIN DESCRIPTION:
GRAND LAKE CREEK 52.0
END DESCRIPTION:
XS GIS Cut Line= 3
      3834798.13     10106618.73       3833753.5     10106269.19
      3833393.26     10106308.26
#Sta/Elev= 30
  4124.6  193.43  4177.6  191.06  4314.7   190.8  4457.3  186.64  4511.3  186.21
  4663.1  183.08    4726  182.88  4736.8  181.74  4789.2  182.91  4922.2  179.59
  4978.8  179.06  5000.1  177.34  5024.9  178.43  5127.6  179.72  5147.7  178.75
  5168.3   179.8  5189.9   178.7  5230.2   179.4  5293.6  177.71  5312.3  180.55
  5322.4  179.73  5332.4  176.88  5340.7  175.19 5375.44 176.932  5380.2  177.89
  5385.2  177.04  5402.8  182.05  5443.1  183.99  5533.6  183.15  5588.5  185.16
#Mann= 10 ,-1 , 0
  4124.6      .1       0  4457.3    .075       0  4511.3      .1       0
  4663.1    .075       0  4922.2     .05       0  5024.9      .1       0
  5127.6    .075       0  5230.2     .05       0  5332.4     .07       0
 5375.44    .075       0
Bank Sta=5332.4,5375.44
XS Rating Curve= 0 ,0
Exp/Cntr=0.3,0.1

Type RM Length L Ch R = 1 ,26470   ,579,579,579
BEGIN DESCRIPTION:
GRAND LAKE CREEK 51.0
END DESCRIPTION:
XS GIS Cut Line= 3
      3834823.32      10106538.8       3834068.1     10106300.95
      3833141.41     10106007.58
#Sta/Elev= 30
  4100.9  192.48  4201.9  191.87  4337.3  189.09  4400.2  185.89  4431.6  188.43
  4445.1  188.19  4463.1  186.13  4484.1  185.75  4508.6  182.57  4514.8  184.46
  4893.7  179.47  4924.4  179.37  4941.1   177.7  4966.4  178.47  4973.4  176.61
  4978.6  176.97  4996.1  170.77  4999.6  170.77  5005.7  174.34  5010.9  172.21
  5026.8 176.911  5039.7  178.38  5224.2  178.58  5264.1  178.38  5328.7  178.44
    5395  178.22  5570.5   180.2  5585.2  181.72  5640.3  180.54  5864.7   181.8
#Mann= 12 ,-1 , 0
  4100.9      .1       0  4201.9    .075       0  4508.6      .1       0
  4514.8    .075       0  4893.7     .05       0  4978.6     .07       0
  5026.8     .05       0  5039.7    .075       0  5224.2     .05       0
  5264.1    .075       0  5328.7     .05       0    5395    .075       0
Bank Sta=4978.6,5026.8
XS Rating Curve= 0 ,0
Exp/Cntr=0.3,0.1

Type RM Length L Ch R = 1 ,25891   ,467,467,467
BEGIN DESCRIPTION:
GRAND LAKE CREEK 50.0
END DESCRIPTION:
XS GIS Cut Line= 4
      3834761.28     10105902.09      3833841.06     10105706.25
      3833794.18     10105827.77      3833002.75     10105917.68
#Sta/Elev= 30
  3999.4  187.73  4271.2  186.21  4315.6  186.44  4330.1  184.93  4565.2   182.9
    4608  181.25  4626.6   182.2    4739  179.19  4796.1  178.59  4820.8  179.29
  4840.6     177  4861.7  176.45  4882.2  177.38  4967.6  177.23  4977.6  176.63
 4985.09 175.043  4992.2  173.74  4997.2  171.75  5025.7  175.08  5041.4  177.44
  5063.3  177.69  5227.7  174.22  5449.2  178.15  5489.5  177.21  5539.8  179.06
  5630.4   180.4  5670.6  180.09  5741.1  181.62  5801.5  179.94    5867  181.78
#Mann= 5 ,-1 , 0
  3999.4      .1       0  4271.2     .05       0 4985.09     .07       0
  5025.7     .05       0  5025.7    .075       0
Bank Sta=4985.09,5025.7
XS Rating Curve= 0 ,0
Exp/Cntr=0.3,0.1

Type RM Length L Ch R = 1 ,25424   ,105,105,105
BEGIN DESCRIPTION:
GRAND LAKE CREEK 49.0
END DESCRIPTION:
XS GIS Cut Line= 3
      3834211.75     10105485.76       3833532.9     10105456.51
      3832967.87     10105861.06
#Sta/Elev= 30
  4321.4  182.67  4359.1  182.61  4487.7  180.01  4565.5  178.85  4595.6  180.27
  4615.6  175.97  4626.5  176.34  4675.6  177.72  4780.4  176.18  4815.8  173.98
  4875.8  173.68  4950.7  171.57  4985.9   170.2  4994.1  167.21 5011.48 170.309
    5030  172.97    5057  171.34  5071.8  171.54  5080.4  173.43  5086.5  172.38
  5093.2  173.46  5122.2  172.29  5308.9  177.86    5374   178.1  5380.1  177.23
  5424.3     177  5451.4  178.56  5516.5  178.09  5566.8  179.85  5695.8  181.16
#Mann= 8 ,-1 , 0
  4321.4      .1       0  4359.1    .075       0  4487.7     .05       0
  4626.5    .075       0  4780.4     .05       0  4950.7    .075       0
  4985.9     .07       0 5011.48    .075       0
Bank Sta=4985.9,5011.48
XS Rating Curve= 0 ,0
Exp/Cntr=0.3,0.1

Type RM Length L Ch R = 1 ,25319   ,170,170,170
BEGIN DESCRIPTION:
Mapping XS 13ca7db6
END DESCRIPTION:
XS GIS Cut Line= 2
      3834098.92     10105118.71      3832907.99     10105601.33
#Sta/Elev= 30
  4378.6  178.25  4397.1   178.2  4402.5  175.63  4426.6  171.48  4450.7  174.13
  4456.1  177.48  4487.6  180.45  4606.1  180.86  4627.9  178.53  4659.7  178.83
  4742.8  176.31  4766.9  177.18  4897.7  173.62  4903.6  170.96    4909  171.95
  4919.2  167.07  4929.7  165.16  4962.6  165.25    4993  162.78 5008.63 165.218
  5016.4   167.7  5027.1  168.39  5040.3  171.21    5189  172.53  5278.8  174.85
    5327  173.57    5394  177.21  5480.3  177.66  5501.9  178.94  5663.6  178.31
#Mann= 4 ,-1 , 0
  4378.6     .05       0  4929.7    .075       0  4962.6     .07       0
 5008.63    .075       0
Bank Sta=4962.6,5008.63
XS Rating Curve= 0 ,0
Exp/Cntr=0.3,0.1

Type RM Length L Ch R = 1 ,25149   ,189,189,189
BEGIN DESCRIPTION:
Mapping XS a82165a5
END DESCRIPTION:
XS GIS Cut Line= 2
      3834019.08     10104955.51      3832838.52     10105462.45
#Sta/Elev= 30
  4375.1   177.3  4531.4  177.96  4631.1  176.48  4654.6  174.46  4660.1  170.54
  4678.2  168.73  4707.2  176.72  4730.7  174.87  4768.2  175.62  4777.9  174.87
  4783.3  171.82  4800.9  169.78  4812.3  165.25  4877.1  163.87  4935.5  164.69
  4988.1  162.62    4995  161.38  5018.5  162.59  5082.3  163.85  5134.8  163.19
  5149.1  165.52  5158.4  165.44  5163.8  169.88  5192.8  171.53  5216.4  170.82
  5444.7  175.97  5475.6  178.01  5520.8  178.22  5562.5  176.79  5659.9  178.13
#Mann= 4 ,-1 , 0
  4375.1     .05       0  4988.1     .03       0  5018.5     .05       0
  5163.8    .075       0
Bank Sta=4988.1,5018.5
XS Rating Curve= 0 ,0
Exp/Cntr=0.3,0.1

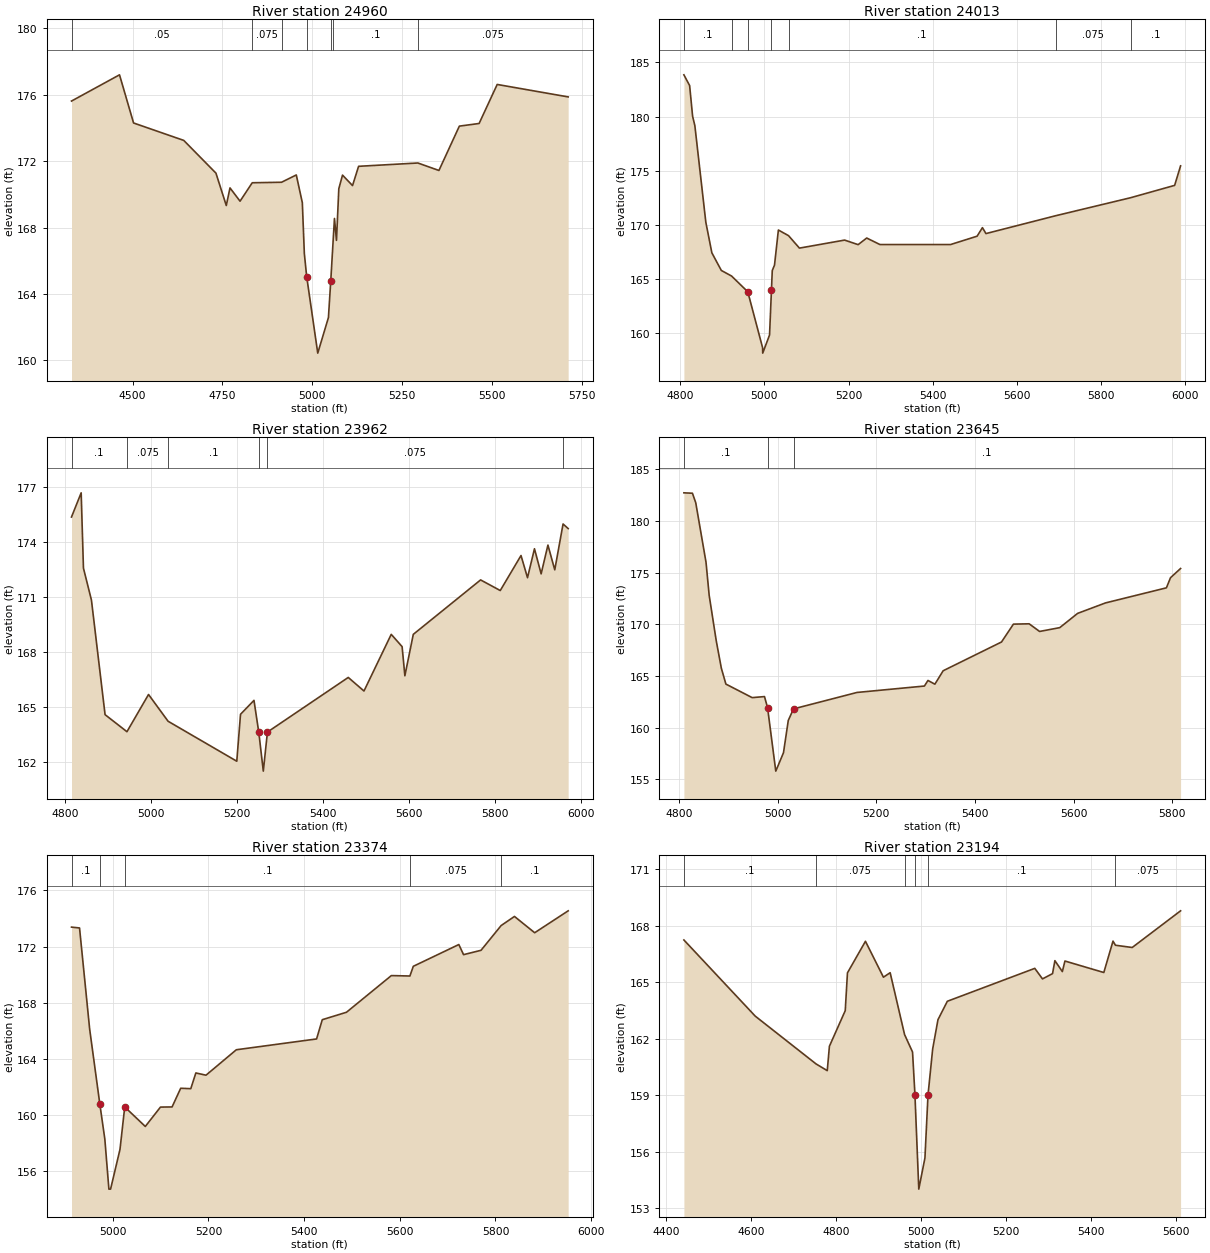
Type RM Length L Ch R = 1 ,24960   ,947,947,947
BEGIN DESCRIPTION:
Mapping XS 167192f8
END DESCRIPTION:
XS GIS Cut Line= 2
      3833953.12     10104736.75      3832717.03      10105354.8
#Sta/Elev= 30
    4330  175.62  4463.6   177.2  4502.7   174.3  4642.4  173.25  4731.9  171.28
  4760.7  169.33    4771  170.39    4799  169.59  4832.9   170.7  4914.4  170.73
  4955.5  171.17  4972.3   169.5  4977.9  166.43  4984.4  165.05  5015.2  160.44
  5044.9  162.58  5051.4  164.79  5057.8  167.13  5061.7  168.55  5067.3  167.23
  5073.8  170.34  5084.1  171.16    5112  170.53  5128.8  171.69  5293.8  171.89
  5352.4  171.44  5409.2  174.11  5464.2  174.27  5514.5  176.62    5712  175.87
#Mann= 7 ,-1 , 0
    4330     .05       0  4832.9    .075       0  4914.4     .05       0
  4984.4     .07       0  5051.4     .05       0  5057.8      .1       0
  5293.8    .075       0
Bank Sta=4984.4,5051.4
XS Rating Curve= 0 ,0
Exp/Cntr=0.3,0.1

Type RM Length L Ch R = 1 ,24013   ,51,51,51
BEGIN DESCRIPTION:
GRAND LAKE CREEK 48.0
END DESCRIPTION:
XS GIS Cut Line= 3
      3832980.03     10104018.17      3832919.19      10104198.5
      3832619.35     10105141.88
#Sta/Elev= 30
  4808.8  183.85  4822.4  182.86  4829.5  180.02  4834.8  179.17  4860.9  170.25
  4875.2  167.43  4897.7   165.8  4922.2  165.28  4960.6  163.83  4995.8  158.67
  4996.1  158.17  5012.3  159.84 5016.81 163.969  5018.8  165.79  5024.1  166.29
  5033.3  169.53  5057.4  169.01  5083.3  167.86  5190.7   168.6  5222.8  168.18
  5243.2  168.79  5274.6  168.19  5442.5  168.19  5505.5  168.96  5518.2  169.75
  5526.5   169.2  5692.4  170.85  5870.3  172.51  5974.9  173.65    5989  175.45
#Mann= 7 ,-1 , 0
  4808.8      .1       0  4922.2    .075       0  4960.6     .07       0
 5016.81    .075       0  5057.4      .1       0  5692.4    .075       0
  5870.3      .1       0
Bank Sta=4960.6,5016.81
XS Rating Curve= 0 ,0
Exp/Cntr=0.3,0.1

Type RM Length L Ch R = 1 ,23962   ,317,317,317
BEGIN DESCRIPTION:
Mapping XS 1b719646
END DESCRIPTION:
XS GIS Cut Line= 2
      3832930.96     10104007.17      3832557.64      10105100.6
#Sta/Elev= 30
  4814.6  175.38  4837.1   176.7  4842.4  172.59    4861  170.85  4892.7   164.6
  4943.6  163.67  4993.8   165.7  5039.3  164.24  5199.1  162.06  5207.8  164.62
  5239.1  165.38 5250.32 163.632  5260.8  161.52  5270.4  163.65  5458.4  166.63
    5495  165.89  5558.4  168.98  5583.7  168.31  5590.1  166.72  5609.7  168.98
  5766.3  171.95    5812  171.37  5860.3  173.28  5875.4  172.07  5891.6  173.65
  5907.1  172.28  5922.9  173.85  5938.8   172.5  5958.1     175    5970  174.75
#Mann= 6 ,-1 , 0
  4814.6      .1       0  4943.6    .075       0  5039.3      .1       0
 5250.32     .07       0  5270.4    .075       0  5958.1      .1       0
Bank Sta=5250.32,5270.4
XS Rating Curve= 0 ,0
Exp/Cntr=0.3,0.1

Type RM Length L Ch R = 1 ,23645   ,271,271,271
BEGIN DESCRIPTION:
GRAND LAKE CREEK 47.0
END DESCRIPTION:
XS GIS Cut Line= 3
      3832627.15     10103888.01      3832575.07     10104071.59
      3832302.24     10104840.29
#Sta/Elev= 30
  4810.1  182.72  4827.4  182.68  4834.1  181.76  4854.9  176.01  4861.3  172.81
  4875.6  168.42    4886  165.75  4895.2  164.22  4948.4  162.91  4973.4  163.01
  4979.6  161.95  4996.3   155.8  5011.9  157.58  5021.6   160.7  5032.2  161.82
  5160.9  163.41  5297.5  164.03  5304.7  164.57  5318.7  164.21  5335.5  165.51
  5453.7  168.29  5477.9  170.02  5509.7  170.05  5530.9  169.31  5571.8  169.68
    5608  171.06  5664.4  172.07  5787.9  173.53  5796.2  174.51  5816.6   175.4
#Mann= 3 , 0 , 0
  4810.1      .1       0  4979.6     .07       0  5032.2      .1       0
Bank Sta=4979.6,5032.2
XS Rating Curve= 0 ,0
Exp/Cntr=0.3,0.1

Type RM Length L Ch R = 1 ,23374   ,180,180,180
BEGIN DESCRIPTION:
GRAND LAKE CREEK 46.0
END DESCRIPTION:
XS GIS Cut Line= 2
      3832400.45     10103815.15      3832063.36     10104797.31
#Sta/Elev= 30
  4913.6  173.39  4930.4  173.33  4951.6  166.12  4972.9  160.78  4983.3   158.3
  4991.8  154.74  4995.3  154.74    5015  157.57  5024.9  160.59  5067.9   159.2
  5099.6  160.58  5123.9  160.59  5141.9  161.92    5163  161.89  5173.6  163.01
  5194.8  162.85  5258.2  164.66    5426  165.43  5437.9   166.8  5488.5  167.33
  5582.3  169.94  5621.1  169.91  5628.2   170.6  5723.4  172.15  5733.3  171.43
  5769.8  171.74  5811.8   173.5  5839.7  174.15    5882  172.99    5952  174.55
#Mann= 5 ,-1 , 0
  4913.6      .1       0  4972.9     .07       0  5024.9      .1       0
  5621.1    .075       0  5811.8      .1       0
Bank Sta=4972.9,5024.9
XS Rating Curve= 0 ,0
Exp/Cntr=0.3,0.1

Type RM Length L Ch R = 1 ,23194   ,119,119,119
BEGIN DESCRIPTION:
Mapping XS a37c6d0b
END DESCRIPTION:
XS GIS Cut Line= 3
      3832699.96     10103648.47      3832237.69     10103756.98
      3831967.09     10104397.75
#Sta/Elev= 30
  4441.4  167.25  4609.5   163.2  4752.7  160.66  4779.2   160.3  4784.3   161.6
  4821.6  163.49  4826.8   165.5  4869.2  167.18  4911.6  165.27  4927.4  165.51
  4961.4  162.22  4980.2  161.29  4985.8  159.03  4994.9     154  5009.4  155.66
  5016.6 158.996  5027.6  161.45  5040.1  163.01  5062.2  163.99  5268.2  165.74
  5286.4  165.18  5310.1  165.46  5315.6  166.15  5333.2  165.57  5339.3  166.13
  5430.9  165.52  5452.6  167.19  5458.2  166.97  5497.8  166.85  5611.8   168.8
#Mann= 6 ,-1 , 0
  4441.4      .1       0  4752.7    .075       0  4961.4      .1       0
  4985.8     .07       0  5016.6      .1       0  5458.2    .075       0
Bank Sta=4985.8,5016.6
XS Rating Curve= 0 ,0
Exp/Cntr=0.3,0.1

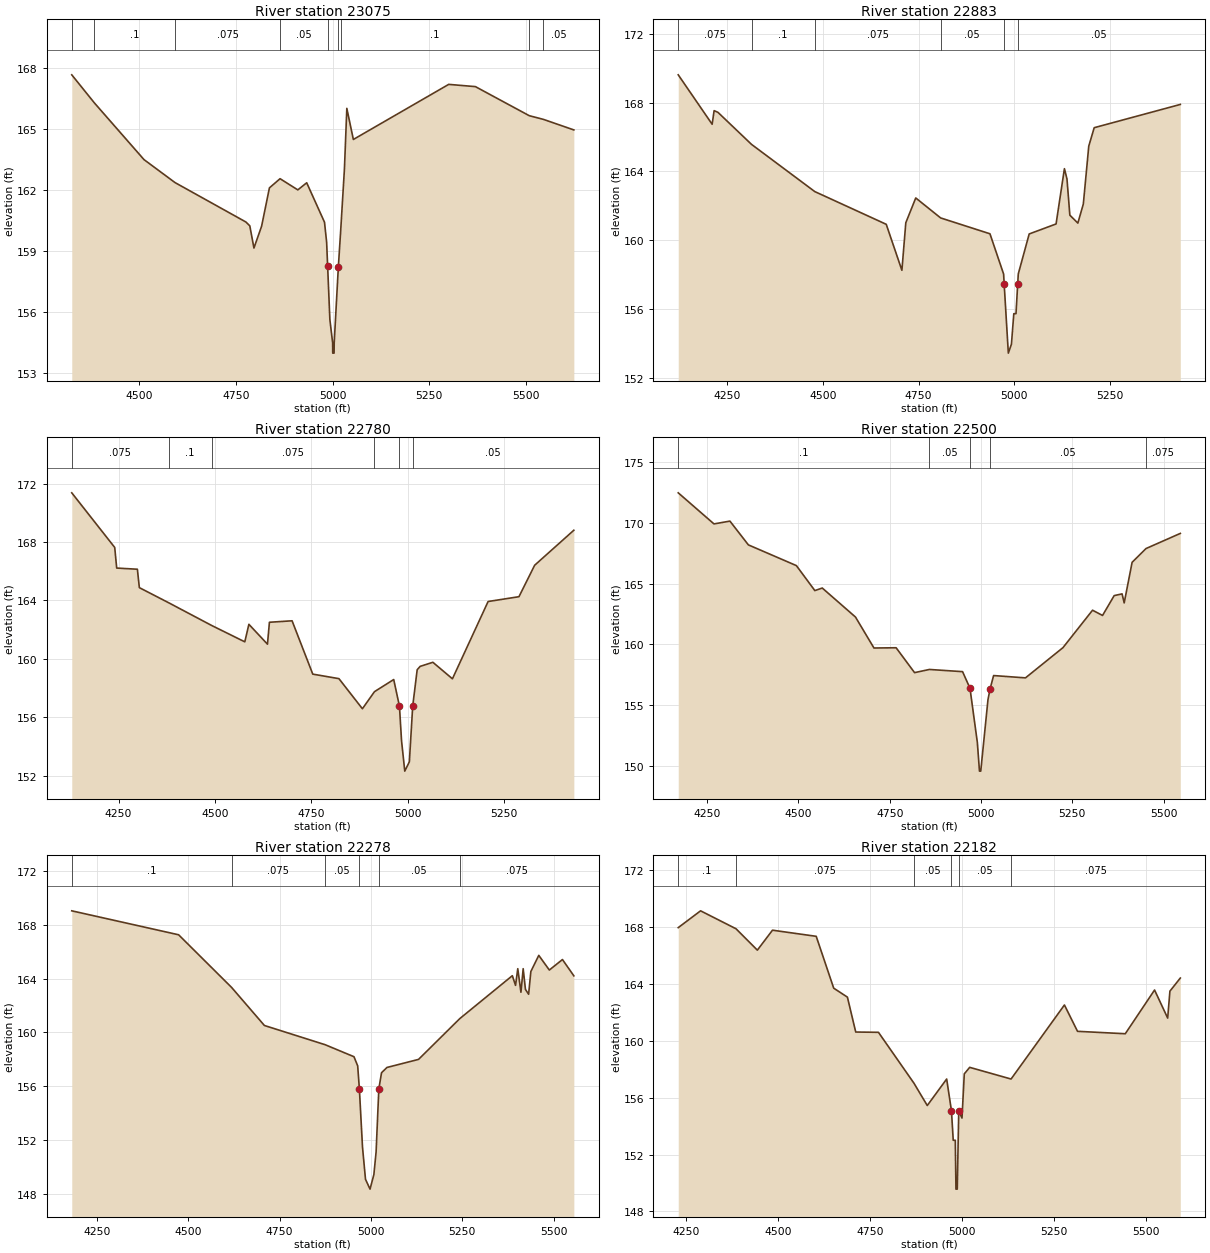
Type RM Length L Ch R = 1 ,23075   ,192,192,192
BEGIN DESCRIPTION:
Mapping XS 51d8a445
END DESCRIPTION:
XS GIS Cut Line= 3
      3832702.12     10103596.39      3832137.86     10103694.05
      3831836.22     10104355.91
#Sta/Elev= 30
  4324.7  167.68  4383.2   166.3  4511.7  163.51    4592  162.38  4775.6  160.44
  4785.7  160.25  4796.4  159.16  4816.2  160.23  4836.5  162.12    4864  162.57
    4910  162.02    4933  162.37  4979.1  160.43  4984.6  159.45 4987.24 158.253
    4993  155.64  5000.2  154.49  5000.4  153.99  5003.9  153.99  5004.2  154.49
    5015  158.25    5021  160.01  5030.7  163.05  5036.9  166.03  5053.8   164.5
  5300.7  167.21  5369.8   167.1  5509.2  165.67  5545.7  165.49  5624.7  164.97
#Mann= 9 ,-1 , 0
  4324.7    .075       0  4383.2      .1       0    4592    .075       0
    4864     .05       0 4987.24     .05       0    5015     .05       0
    5021      .1       0  5509.2    .075       0  5545.7     .05       0
Bank Sta=4987.24,5015
XS Rating Curve= 0 ,0
Exp/Cntr=0.3,0.1

Type RM Length L Ch R = 1 ,22883   ,103,103,103
BEGIN DESCRIPTION:
GRAND LAKE CREEK 45.0
END DESCRIPTION:
XS GIS Cut Line= 3
      3832779.38     10103527.71      3831920.74     10103709.15
      3831634.83      10104035.4
#Sta/Elev= 30
  4122.4  169.61    4211  166.74  4216.1  167.53  4226.2  167.43  4313.9  165.57
  4479.1  162.83  4665.7  160.93  4706.6  158.26  4716.8  161.02  4742.8  162.46
  4807.8   161.3  4936.6  160.38  4972.3  158.04 4973.66 157.491  4984.6  153.45
  4992.7  153.97  4998.9  155.74  5004.6  155.74 5009.07 157.461  5010.6  158.05
  5039.1  160.37  5109.3  160.95  5131.1  164.16  5137.8  163.56  5145.3  161.46
  5166.2     161  5180.5  162.11  5194.7  165.47  5208.9  166.54  5433.8  167.89
#Mann= 6 ,-1 , 0
  4122.4    .075       0  4313.9      .1       0  4479.1    .075       0
  4807.8     .05       0  4972.3     .07       0  5010.6     .05       0
Bank Sta=4973.66,5009.07
XS Rating Curve= 0 ,0
Exp/Cntr=0.3,0.1

Type RM Length L Ch R = 1 ,22780   ,280,280,280
BEGIN DESCRIPTION:
Mapping XS 2c55a276
END DESCRIPTION:
XS GIS Cut Line= 2
      3832750.32     10103455.98      3831467.69     10103686.03
#Sta/Elev= 30
  4128.5  171.37    4240  167.63  4245.1  166.22  4298.8  166.14  4303.9  164.88
  4380.4  163.84  4491.6  162.29  4577.6  161.17  4588.2  162.37  4636.4  161.01
  4641.5  162.51  4700.3  162.61    4754  158.96  4821.9  158.65  4882.8  156.59
  4914.2  157.76  4964.1  158.59    4979  156.76  4984.4   154.4  4992.8  152.32
  5004.7  152.96 5013.38 156.772    5025  159.26  5032.7  159.49  5065.7  159.77
  5116.5  158.64  5209.1  163.93  5289.2  164.26  5329.8  166.41  5431.6  168.81
#Mann= 6 ,-1 , 0
  4128.5    .075       0  4380.4      .1       0  4491.6    .075       0
  4914.2     .05       0    4979     .05       0 5013.38     .05       0
Bank Sta=4979,5013.38
XS Rating Curve= 0 ,0
Exp/Cntr=0.3,0.1

Type RM Length L Ch R = 1 ,22500   ,222,222,222
BEGIN DESCRIPTION:
GRAND LAKE CREEK 44.0
END DESCRIPTION:
XS GIS Cut Line= 3
      3832667.82     10103211.08      3831847.95     10103335.82
      3831371.97     10103603.12
#Sta/Elev= 30
  4170.7  172.44  4268.6  169.89  4312.3  170.12  4362.8  168.17  4494.3  166.47
  4544.9  164.42  4565.2  164.63  4656.2  162.25  4706.8  159.71  4767.5  159.73
    4818  157.69  4858.7  157.95  4949.5  157.77  4969.8  156.41    4990  151.96
  4995.8  149.61  4999.3  149.61  5019.1  155.47  5024.9  156.36  5034.5  157.45
  5121.8  157.26  5224.5  159.74  5305.5  162.81  5332.9  162.38  5364.8  164.01
  5386.4  164.15  5392.2  163.41  5413.9  166.74    5452  167.87  5545.9  169.11
#Mann= 5 ,-1 , 0
  4170.7      .1       0  4858.7     .05       0  4969.8     .07       0
  5024.9     .05       0    5452    .075       0
Bank Sta=4969.8,5024.9
XS Rating Curve= 0 ,0
Exp/Cntr=0.3,0.1

Type RM Length L Ch R = 1 ,22278   ,96,96,96
BEGIN DESCRIPTION:
Mapping XS a75d59a9
END DESCRIPTION:
XS GIS Cut Line= 3
      3832544.15     10102963.75      3831762.86     10103126.95
      3831288.91     10103455.07
#Sta/Elev= 30
  4180.8  169.04  4473.3  167.26  4618.3  163.35  4708.2  160.52  4874.6  159.09
  4953.4   158.2  4963.6  157.52 4968.17 155.828  4976.8  151.48    4985  149.09
  4997.4  148.36  5007.9  149.44    5014  151.12  5021.5  155.81  5028.9  157.01
  5043.7   157.4  5130.2     158  5243.1  161.03    5387  164.22  5395.8   163.5
  5401.9  164.74  5410.6  162.99  5416.7  164.74  5422.9   163.2  5431.6  162.84
  5437.7  164.53  5459.4  165.73  5488.3  164.64  5524.2  165.42  5555.4  164.21
#Mann= 6 ,-1 , 0
  4180.8      .1       0  4618.3    .075       0  4874.6     .05       0
 4968.17     .07       0  5021.5     .05       0  5243.1    .075       0
Bank Sta=4968.17,5021.5
XS Rating Curve= 0 ,0
Exp/Cntr=0.3,0.1

Type RM Length L Ch R = 1 ,22182   ,157,157,157
BEGIN DESCRIPTION:
Mapping XS 81bb6785
END DESCRIPTION:
XS GIS Cut Line= 3
      3832446.93     10102869.99      3831717.72     10103041.88
      3831222.06      10103404.1
#Sta/Elev= 30
  4229.3  167.93    4290  169.11  4386.2  167.85  4444.1  166.35  4485.2  167.75
  4603.9  167.32  4651.4  163.68  4688.6  163.05  4711.2   160.6  4772.9  160.58
  4869.2  157.01  4905.4  155.44  4958.1   157.3  4971.1 155.068  4975.9     153
  4981.5     153  4983.3  149.57  4986.8  149.57  4990.9 155.055  4999.7  154.56
  5005.9  157.66  5020.6  158.12  5132.9   157.3  5277.8   162.5  5313.3  160.65
    5443  160.48  5522.5  163.55  5558.1  161.58  5564.2  163.47  5592.4  164.39
#Mann= 6 ,-1 , 0
  4229.3      .1       0  4386.2    .075       0  4869.2     .05       0
  4971.1     .07       0  4990.9     .05       0  5132.9    .075       0
Bank Sta=4971.1,4990.9
XS Rating Curve= 0 ,0
Exp/Cntr=0.3,0.1

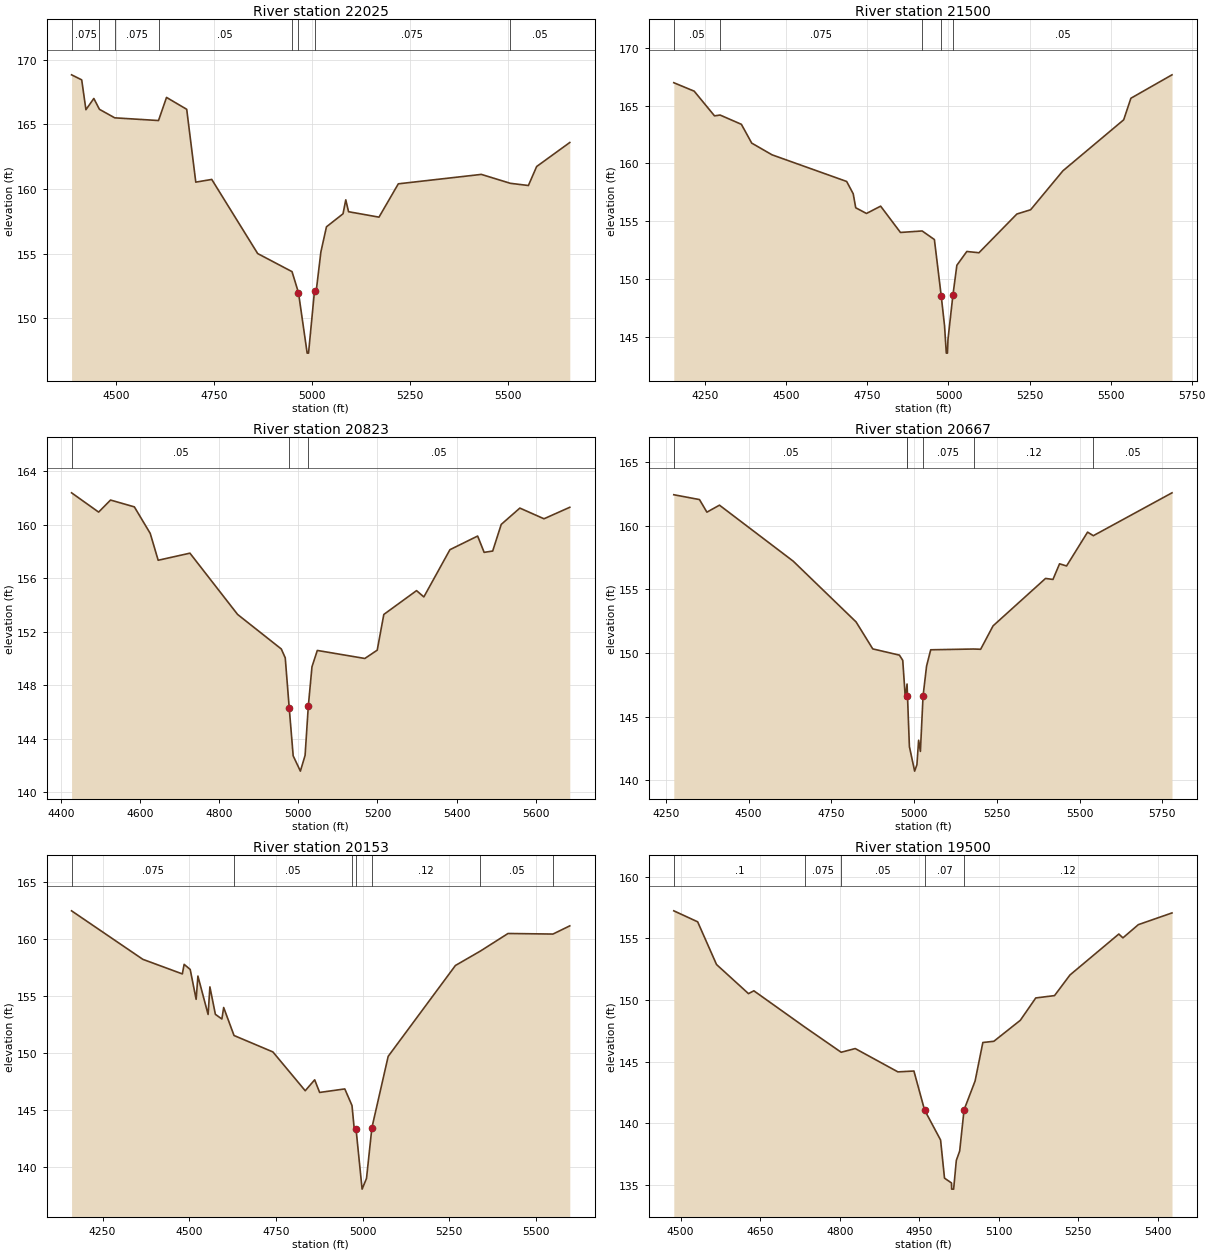
Type RM Length L Ch R = 1 ,22025   ,525,525,525
BEGIN DESCRIPTION:
GRAND LAKE CREEK 43.0
END DESCRIPTION:
XS GIS Cut Line= 3
      3832212.97     10102768.17      3831609.72     10102922.23
      3831144.09     10103377.03
#Sta/Elev= 30
  4385.5  168.84  4411.4  168.45  4422.2  166.14  4442.4  167.01  4456.7  166.17
  4495.8  165.51  4607.7   165.3  4628.2  167.09  4679.8  166.17    4703  160.53
  4743.8  160.74  4861.2     155    4949   153.6  4965.5 151.971  4987.7  147.29
  4991.2  147.29  5006.5  152.12  5010.9  152.12  5022.8  155.13    5037  157.07
  5079.4  158.08  5086.4  159.16  5093.5  158.24  5171.3  157.82  5220.7   160.4
  5432.9  161.13    5507  160.44  5553.2  160.27  5574.3  161.74    5659   163.6
#Mann= 8 ,-1 , 0
  4385.5    .075       0  4456.7      .1       0  4495.8    .075       0
  4607.7     .05       0    4949    .075       0  4965.5     .07       0
  5006.5    .075       0    5507     .05       0
Bank Sta=4965.5,5006.5
XS Rating Curve= 0 ,0
Exp/Cntr=0.3,0.1

Type RM Length L Ch R = 1 ,21500   ,677,677,677
BEGIN DESCRIPTION:
GRAND LAKE CREEK 42.0
END DESCRIPTION:
XS GIS Cut Line= 3
      3832228.18     10102195.25       3831416.3     10102436.95
      3830767.67     10102670.51
#Sta/Elev= 30
  4152.9  166.97  4215.8  166.24  4278.5  164.11  4295.7  164.18  4361.4  163.38
  4393.2  161.76  4455.8  160.75    4686  158.45  4706.2  157.39    4714  156.18
  4747.2  155.69  4790.8  156.32  4851.9  154.05  4918.8  154.18  4956.6  153.44
  4977.5  148.61  4987.9     146  4993.3  143.64  4996.8  143.64  4998.5  144.83
 5013.68 148.634  5025.9  151.22  5056.6  152.41    5094   152.3  5210.9  155.64
  5253.4  156.01    5353  159.37  5540.4  163.77  5562.6  165.63  5689.4  167.65
#Mann= 5 ,-1 , 0
  4152.9     .05       0  4295.7    .075       0  4918.8     .05       0
  4977.5     .05       0 5013.68     .05       0
Bank Sta=4977.5,5013.68
XS Rating Curve= 0 ,0
Exp/Cntr=0.3,0.1

Type RM Length L Ch R = 1 ,20823   ,156,156,156
BEGIN DESCRIPTION:
GRAND LAKE CREEK 41.0
END DESCRIPTION:
XS GIS Cut Line= 3
      3831755.95     10101850.22      3831148.06     10101797.78
      3830547.58     10102044.66
#Sta/Elev= 30
  4426.8  162.38  4495.2  160.94  4525.3  161.84  4585.5  161.33  4625.6  159.35
  4645.7  157.34    4726  157.87  4846.5  153.29  4956.9  150.71  4966.9  150.05
  4976.9  146.33    4987  142.72  5005.2  141.58  5017.1  142.76 5025.25 146.444
  5034.5  149.38    5048   150.6  5168.1     150  5199.4  150.62  5216.1  153.29
  5298.8  155.07  5317.3   154.6  5383.2  158.13  5453.3  159.15  5469.7  157.93
  5491.3  158.03  5512.9  160.02    5560  161.24    5621  160.44  5686.2   161.3
#Mann= 3 , 0 , 0
  4426.8     .05       0  4976.9     .07       0 5025.25     .05       0
Bank Sta=4976.9,5025.25
XS Rating Curve= 0 ,0
Exp/Cntr=0.3,0.1

Type RM Length L Ch R = 1 ,20667   ,514,514,514
BEGIN DESCRIPTION:
GRAND LAKE CREEK 40.0
END DESCRIPTION:
XS GIS Cut Line= 3
      3831854.97     10101737.34      3831127.95      10101652.7
       3830396.6     10101904.44
#Sta/Elev= 30
  4274.1  162.45  4351.7  162.07  4374.2  161.08  4412.1  161.63  4634.8  157.23
  4824.9  152.45  4875.3  150.33  4955.8  149.84  4965.9  149.43  4973.9  146.39
  4978.9  147.57 4980.23 146.648    4986  142.65  5001.8  140.72  5008.7  141.22
  5013.9  143.15  5019.2  142.27  5027.3  146.63  5037.9  148.98  5050.4  150.26
  5179.8  150.32  5201.3   150.3  5238.8  152.14  5397.4  155.87  5419.8  155.79
  5439.7  157.02  5460.9  156.85  5524.4  159.51  5541.8  159.23  5779.5   162.6
#Mann= 6 ,-1 , 0
  4274.1     .05       0  4978.9    .075       0 4980.23     .07       0
  5027.3    .075       0  5179.8     .12       0  5541.8     .05       0
Bank Sta=4980.23,5027.3
XS Rating Curve= 0 ,0
Exp/Cntr=0.3,0.1

Type RM Length L Ch R = 1 ,20153   ,653,653,653
BEGIN DESCRIPTION:
GRAND LAKE CREEK 39.0
END DESCRIPTION:
XS GIS Cut Line= 3
      3831817.89     10101411.08      3831002.08     10101188.29
      3830437.81     10101364.09
#Sta/Elev= 30
  4160.7  162.51  4366.2  158.25  4480.1  156.97  4485.3  157.81  4502.8  157.36
  4519.9  154.74    4525  156.78  4554.4  153.41  4559.6  155.83  4575.4  153.42
  4594.1  153.01  4599.3  154.02  4629.2  151.56  4741.2  150.12  4834.5  146.71
  4861.7  147.67    4876  146.56  4948.6  146.87  4969.4  145.41  4975.7  143.39
  4980.9  143.38  4998.5  138.07  5011.2  139.01 5026.75 143.464  5073.7  149.73
  5267.6  157.71  5339.8  158.98  5419.3  160.52  5548.9  160.47  5597.4  161.19
#Mann= 7 ,-1 , 0
  4160.7    .075       0  4629.2     .05       0  4969.4     .12       0
  4980.9     .07       0 5026.75     .12       0  5339.8     .05       0
  5548.9     .12       0
Bank Sta=4980.9,5026.75
XS Rating Curve= 0 ,0
Exp/Cntr=0.3,0.1

Type RM Length L Ch R = 1 ,19500   ,532,532,532
BEGIN DESCRIPTION:
GRAND LAKE CREEK 38.0
END DESCRIPTION:
XS GIS Cut Line= 3
       3831517.9     10100611.08      3831008.24     10100553.55
      3830667.87     10100811.06
#Sta/Elev= 30
  4487.1  157.22  4532.1  156.33  4567.7  152.87    4628  150.51  4638.1  150.74
  4735.2  147.77  4802.8  145.76  4829.3  146.06  4909.8  144.17    4940  144.24
  4960.1  141.08  4990.3  138.65  4997.7  135.56  5010.9  135.17  5011.2  134.67
  5014.9  134.67    5020     137  5026.3  137.75  5034.6   141.1  5055.4  143.43
    5070  146.55  5090.8  146.65  5140.7  148.35  5169.8  150.16  5205.2  150.35
  5234.3  152.02  5326.5  155.34  5334.2  155.03  5363.3   156.1  5426.8  157.05
#Mann= 5 ,-1 , 0
  4487.1      .1       0  4735.2    .075       0  4802.8     .05       0
  4960.1     .07       0  5034.6     .12       0
Bank Sta=4960.1,5034.6
XS Rating Curve= 0 ,0
Exp/Cntr=0.3,0.1

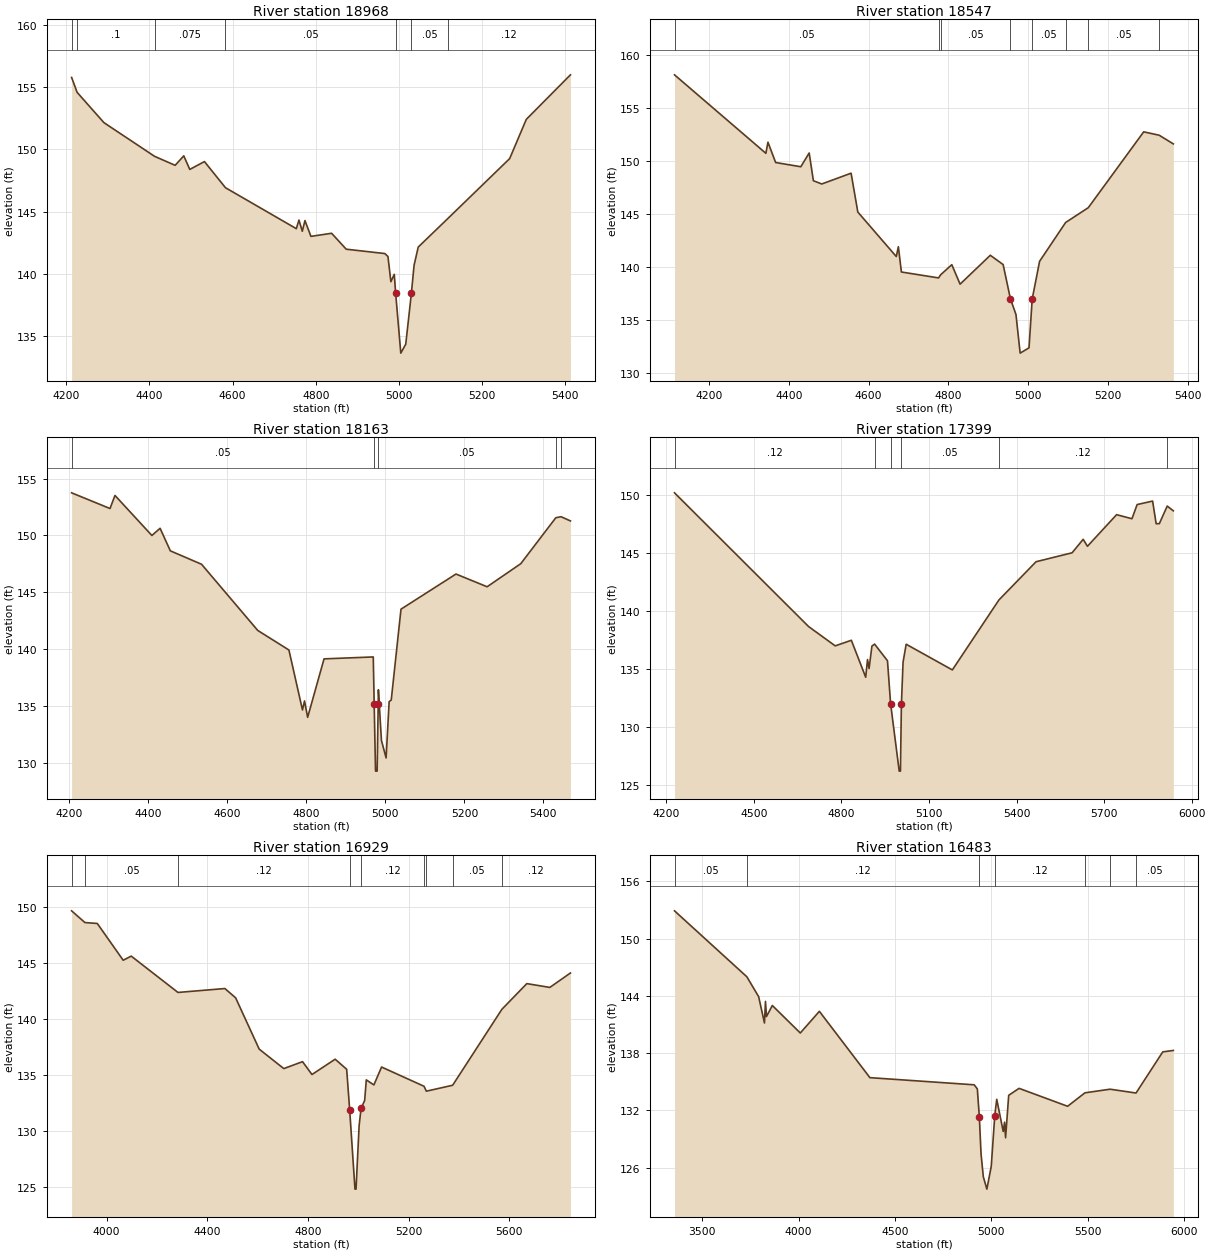
Type RM Length L Ch R = 1 ,18968   ,421,421,421
BEGIN DESCRIPTION:
GRAND LAKE CREEK 37.0
END DESCRIPTION:
XS GIS Cut Line= 3
      3831503.42     10100554.64      3830897.91     10100072.84
      3830471.67     10100079.33
#Sta/Elev= 30
  4212.7  155.78    4226  154.58  4290.4  152.15  4412.4  149.44  4461.8  148.72
  4482.6  149.48    4497  148.39  4532.3  149.02  4582.9  146.92  4753.3  143.63
  4759.7  144.32  4767.7  143.42  4774.1  144.28  4788.5  143.01  4838.2  143.26
  4873.4  141.98  4966.3  141.63  4973.8  141.39  4980.8  139.37    4989  139.96
 4992.35  138.43  5004.7  133.63  5016.6  134.35 5030.14 138.432  5036.6  140.68
  5046.6  142.15  5117.1  144.42  5266.6  149.26  5306.6  152.41  5412.8  155.99
#Mann= 7 ,-1 , 0
  4212.7    .075       0    4226      .1       0  4412.4    .075       0
  4582.9     .05       0 4992.35     .07       0 5030.14     .05       0
  5117.1     .12       0
Bank Sta=4992.35,5030.14
XS Rating Curve= 0 ,0
Exp/Cntr=0.3,0.1

Type RM Length L Ch R = 1 ,18547   ,384,384,384
BEGIN DESCRIPTION:
GRAND LAKE CREEK 36.0
END DESCRIPTION:
XS GIS Cut Line= 3
       3831679.2     10099395.75      3830852.34     10099660.52
      3830486.71     10099769.01
#Sta/Elev= 30
  4113.9  158.16  4342.8  150.74    4348  151.79  4367.3  149.87  4430.3  149.47
  4451.3  150.77  4461.8  148.15  4482.8  147.84  4556.3  148.86  4573.1  145.19
  4669.5  140.98  4674.7  141.91  4682.3  139.52  4775.4  138.96  4780.7  139.26
  4808.6  140.21  4829.3  138.37    4905   141.1  4937.2  140.22  4955.3     137
  4969.3   135.5  4979.8  131.85    5002  132.35 5009.92 136.953  5028.5  140.53
  5093.7   144.2  5150.5   145.6  5289.3  152.77  5328.1  152.45  5363.5  151.63
#Mann= 8 ,-1 , 0
  4113.9     .05       0  4775.4     .12       0  4780.7     .05       0
  4955.3     .05       0 5009.92     .05       0  5093.7     .12       0
  5150.5     .05       0  5328.1     .12       0
Bank Sta=4955.3,5009.92
XS Rating Curve= 0 ,0
Exp/Cntr=0.3,0.1

Type RM Length L Ch R = 1 ,18163   ,764,764,764
BEGIN DESCRIPTION:
GRAND LAKE CREEK 35.0
END DESCRIPTION:
XS GIS Cut Line= 3
      3831723.67      10099109.3      3830956.51     10099321.97
        3830521.     10099489.48
#Sta/Elev= 30
  4205.7  153.75  4302.9  152.37  4315.5  153.52  4408.9     150  4429.7  150.63
  4455.6  148.65  4534.6  147.47  4676.9  141.65  4755.8  139.93  4790.1  134.66
  4795.3  135.45  4803.2  134.01  4844.7  139.15  4969.3  139.32 4971.62 135.221
    4975  129.28  4979.1  129.28 4981.79 135.219  4982.3  136.43    4990  131.98
  5001.8  130.44  5009.5  135.39  5014.8  135.53  5039.5  143.52  5178.7  146.61
  5257.5  145.49  5342.7  147.52  5431.4  151.56  5444.6  151.65  5468.4  151.28
#Mann= 5 ,-1 , 0
  4205.7     .05       0 4971.62     .05       0 4981.79     .05       0
  5431.4     .12       0  5444.6     .05       0
Bank Sta=4971.62,4981.79
XS Rating Curve= 0 ,0
Exp/Cntr=0.3,0.1

Type RM Length L Ch R = 1 ,17399   ,470,470,470
BEGIN DESCRIPTION:
GRAND LAKE CREEK 34.0
END DESCRIPTION:
XS GIS Cut Line= 3
      3831781.93      10098906.9      3830914.41     10098584.34
      3830606.59     10099305.12
#Sta/Elev= 30
  4227.9  150.15  4687.5  138.64  4778.6  136.98  4833.9  137.46  4883.1  134.28
  4889.3   135.8  4894.6  135.03  4904.4  136.96  4913.6  137.13  4957.7   135.7
  4968.4  132.01  4997.9   126.2  5002.1   126.2  5005.4  131.96  5011.1  135.57
  5021.7  137.12    5180  134.91  5339.6  140.93  5466.8  144.22  5590.3  144.99
  5628.3  146.15  5642.9  145.55  5742.8  148.27  5795.4  147.92  5813.2  149.14
  5866.2  149.44  5878.4  147.49  5889.3   147.5  5916.3  149.01  5937.2   148.6
#Mann= 6 ,-1 , 0
  4227.9     .12       0  4913.6     .05       0  4968.4     .07       0
  5005.4     .05       0  5339.6     .12       0  5916.3     .05       0
Bank Sta=4968.4,5005.4
XS Rating Curve= 0 ,0
Exp/Cntr=0.3,0.1

Type RM Length L Ch R = 1 ,16929   ,446,446,446
BEGIN DESCRIPTION:
GRAND LAKE CREEK 33.0
END DESCRIPTION:
XS GIS Cut Line= 4
      3831940.58     10098560.02       3830944.1     10098200.66
      3830855.55     10098304.83      3830584.04     10099041.47
#Sta/Elev= 30
  3861.2  149.67  3914.2  148.62  3963.2  148.54  4066.1  145.25    4098  145.62
  4283.7  142.37    4470  142.72  4512.6  141.89  4606.3   137.3  4703.9  135.56
  4778.3  136.18  4815.8  135.03  4907.9   136.4  4953.6   135.5 4965.67 131.839
  4986.6  124.78  4990.8  124.78    5003  130.43  5010.7     132    5025   132.7
  5031.6  134.55  5061.8   134.1  5092.2   135.7  5260.8  133.98  5270.1  133.54
  5374.5  134.07    5570  140.86  5669.1  143.16  5760.5  142.82  5842.3  144.11
#Mann= 9 ,-1 , 0
  3861.2     .12       0  3914.2     .05       0  4283.7     .12       0
 4965.67     .07       0  5010.7     .12       0  5260.8      .1       0
  5270.1     .12       0  5374.5     .05       0    5570     .12       0
Bank Sta=4965.67,5010.7
XS Rating Curve= 0 ,0
Exp/Cntr=0.3,0.1

Type RM Length L Ch R = 1 ,16483   ,462,462,462
BEGIN DESCRIPTION:
GRAND LAKE CREEK 32.0
END DESCRIPTION:
XS GIS Cut Line= 3
      3832270.09     10098373.87      3830587.47     10097940.53
      3830479.87     10098785.38
#Sta/Elev= 30
  3356.2   152.9  3731.8  145.99  3792.9  143.91  3823.2  141.15  3828.4  143.41
  3833.6  141.82    3864  142.98  4009.1   140.1  4108.2  142.37  4370.5  135.42
  4911.9  134.67  4928.1  134.24  4938.4  131.34  4947.4  127.42  4959.1  125.04
  4977.6  123.74  5000.4  126.14 5018.55 131.444  5028.8  133.15  5062.4  129.78
  5069.5  130.75  5074.7  129.12  5090.9  133.57  5144.7   134.3  5396.7  132.42
  5486.5  133.83    5617  134.21  5751.8  133.81  5890.6  138.12  5945.4  138.27
#Mann= 7 ,-1 , 0
  3356.2     .05       0  3731.8     .12       0  4938.4     .07       0
 5018.55     .12       0  5486.5      .1       0    5617     .12       0
  5751.8     .05       0
Bank Sta=4938.4,5018.55
XS Rating Curve= 0 ,0
Exp/Cntr=0.3,0.1