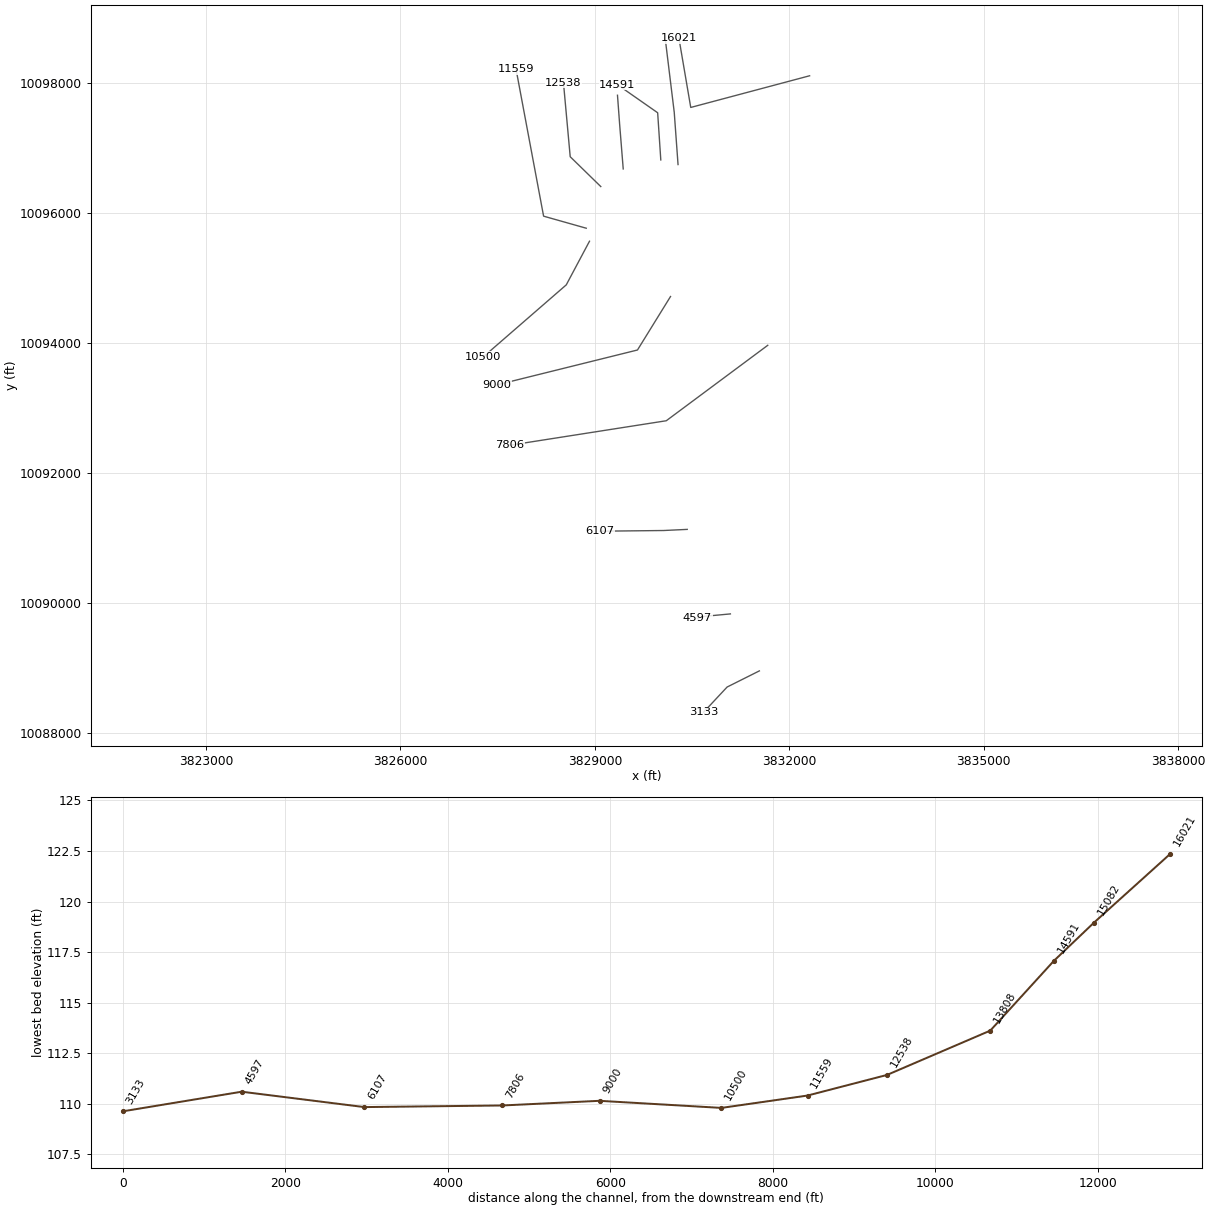
HEC-RAS study GRAND LAKE CREEK.prj: GRAND LAKE CREEK Base Level Engineering

--- GRAND LAKE CREEK.g10 (geometry) --- (continued)

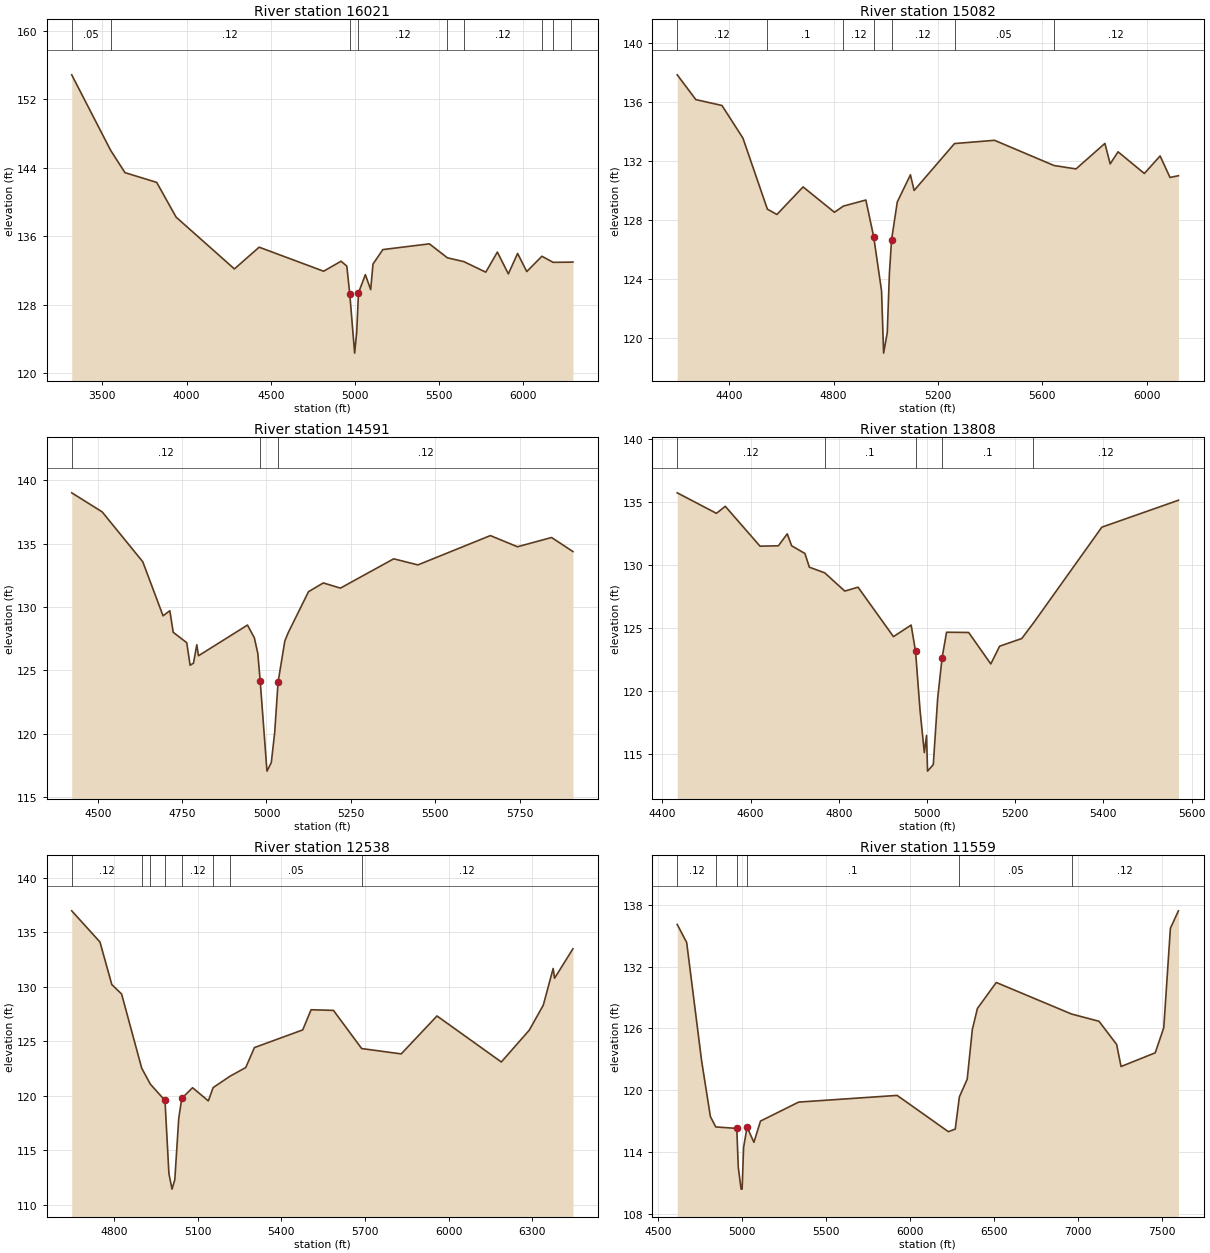
Type RM Length L Ch R = 1 ,16021   ,939,939,939
BEGIN DESCRIPTION:
GRAND LAKE CREEK 31.0
END DESCRIPTION:
XS GIS Cut Line= 3
       3832313.5     10098104.78      3830479.87     10097617.84
      3830297.58     10098681.25
#Sta/Elev= 30
  3318.4  154.87  3549.1  146.06  3634.6  143.44    3823   142.3  3938.3  138.24
  4284.4  132.19  4431.3  134.73  4814.2  131.92  4917.6  133.09  4951.8  132.52
  4969.4  129.26  4998.3  122.35  5010.7  124.83  5021.1   129.4    5062  131.52
  5093.5  129.77  5107.3  132.76  5165.9  134.45  5442.1  135.12  5548.9  133.49
  5647.1  133.04  5776.9  131.81  5845.9  134.16    5911  131.61    5966     134
  6020.4  131.88  6110.2  133.67  6176.7  132.96  6280.1  132.98  6294.5     133
#Mann= 9 ,-1 , 0
  3318.4     .05       0  3549.1     .12       0  4969.4     .07       0
  5021.1     .12       0  5548.9     .05       0  5647.1     .12       0
  6110.2     .05       0  6176.7     .12       0  6280.1     .05       0
Bank Sta=4969.4,5021.1
XS Rating Curve= 0 ,0
Exp/Cntr=0.3,0.1

Type RM Length L Ch R = 1 ,15082   ,491,491,491
BEGIN DESCRIPTION:
GRAND LAKE CREEK 30.0
END DESCRIPTION:
XS GIS Cut Line= 3
      3830283.86     10096739.98      3830225.26     10097542.98
      3830089.25     10098650.83
#Sta/Elev= 30
    4201  137.82  4272.3  136.14  4372.5  135.74  4452.8  133.53  4546.6  128.71
  4583.1  128.35  4683.4  130.22  4803.7   128.5    4838  128.92    4924  129.33
  4954.1  126.84  4984.2  123.17  4992.1  118.95  5006.1  120.34  5014.3  124.35
  5022.6  126.64  5044.5   129.2  5094.9  131.04    5109  129.98  5263.9  133.16
  5417.3  133.38  5645.4  131.67  5729.6  131.44  5840.4  133.17  5860.6  131.78
  5890.8   132.6  5991.6  131.13    6052  132.32    6090  130.86  6122.3  130.98
#Mann= 7 ,-1 , 0
    4201     .12       0  4546.6      .1       0    4838     .12       0
  4954.1     .07       0  5022.6     .12       0  5263.9     .05       0
  5645.4     .12       0
Bank Sta=4954.1,5022.6
XS Rating Curve= 0 ,0
Exp/Cntr=0.3,0.1

Type RM Length L Ch R = 1 ,14591   ,783,783,783
BEGIN DESCRIPTION:
GRAND LAKE CREEK 29.0
END DESCRIPTION:
XS GIS Cut Line= 3
      3830017.85     10096811.04      3829969.44     10097536.25
      3829347.06     10097969.41
#Sta/Elev= 30
  4422.9     139  4513.1   137.5  4633.4  133.57  4693.5  129.31  4713.6  129.71
  4723.6  128.01  4763.7  127.19  4773.7  125.41  4783.7  125.58  4793.5  127.03
  4798.5  126.16  4943.7  128.58  4964.1  127.57  4974.2  126.36 4981.47 124.135
  5001.4  117.07  5014.2  117.74  5024.3  120.11  5034.3  124.08  5054.3  127.32
  5064.4  127.98  5124.5  131.21  5168.4   131.9    5219  131.49    5377   133.8
  5448.6  133.32  5663.4  135.63  5743.6  134.75  5844.8  135.48    5908  134.37
#Mann= 3 , 0 , 0
  4422.9     .12       0 4981.47     .07       0  5034.3     .12       0
Bank Sta=4981.47,5034.3
XS Rating Curve= 0 ,0
Exp/Cntr=0.3,0.1

Type RM Length L Ch R = 1 ,13808   ,1270,1270,1270
BEGIN DESCRIPTION:
GRAND LAKE CREEK 27.0
END DESCRIPTION:
XS GIS Cut Line= 3
       3829438.2     10096672.49      3829382.64     10097362.64
      3829349.65     10097805.33
#Sta/Elev= 30
  4433.8  135.74  4522.7  134.11  4542.7  134.67  4621.5   131.5  4663.1  131.53
  4683.2  132.48  4693.2  131.53  4723.3  130.92  4733.3  129.83  4768.2  129.38
  4813.6  127.93  4843.7  128.24    4924  124.31  4964.1  125.23  4974.1  123.13
  4984.2  118.48    4994  115.09    4999  116.46  5001.3  113.62  5014.3  114.14
  5024.3  119.43  5034.3  122.64  5044.4  124.66  5094.5  124.64  5144.7  122.14
  5164.7  123.55  5214.9  124.16  5241.1  125.38  5396.4  133.01  5570.1  135.15
#Mann= 5 ,-1 , 0
  4433.8     .12       0  4768.2      .1       0  4974.1     .07       0
  5034.3      .1       0  5241.1     .12       0
Bank Sta=4974.1,5034.3
XS Rating Curve= 0 ,0
Exp/Cntr=0.3,0.1

Type RM Length L Ch R = 1 ,12538   ,979,979,979
BEGIN DESCRIPTION:
GRAND LAKE CREEK 25.0
END DESCRIPTION:
XS GIS Cut Line= 3
      3829091.83     10096401.71      3828620.48     10096860.04
      3828516.41     10097997.04
#Sta/Elev= 30
  4647.3  136.95  4748.7  134.09  4791.2  130.19  4826.4  129.32  4898.4  122.53
  4929.5  121.06  4982.1  119.56  4996.2  112.85  5007.3  111.43  5017.3  112.29
  5031.5  117.92  5042.3 119.751  5081.1  120.73  5137.7  119.52  5154.9  120.74
  5215.3  121.78    5272  122.58  5303.1  124.41  5476.5  126.03  5506.6  127.88
  5586.9  127.82  5688.1  124.32  5830.1  123.83  5958.5  127.31  6189.5  123.09
  6289.9  126.01  6340.1   128.3  6375.5  131.66  6380.6  130.77  6446.5  133.47
#Mann= 8 ,-1 , 0
  4647.3     .12       0  4898.4      .1       0  4929.5     .12       0
  4982.1     .07       0  5042.3     .12       0  5154.9      .1       0
  5215.3     .05       0  5688.1     .12       0
Bank Sta=4982.1,5042.3
XS Rating Curve= 0 ,0
Exp/Cntr=0.3,0.1

Type RM Length L Ch R = 1 ,11559   ,1059,1059,1059
BEGIN DESCRIPTION:
GRAND LAKE CREEK 23.0
END DESCRIPTION:
XS GIS Cut Line= 3
      3828867.85     10095761.07      3828209.89     10095946.41
       3827784.7      10098206.9
#Sta/Elev= 30
    4616  136.08  4672.2  134.33  4761.4  122.82  4813.4  117.45  4845.4  116.44
  4970.4   116.3  4979.6   112.5  4996.1  110.41  5002.3  110.41  5010.8  114.43
  5031.6  116.42  5072.5  114.95  5111.7  117.01  5338.8  118.85    5925   119.5
  6230.3  115.98    6271  116.23  6295.7  119.36  6342.2  121.07  6372.7  125.89
  6403.2  127.94  6515.2  130.45  6963.6  127.39  7126.8  126.69  7231.8  124.44
    7258   122.3  7461.5  123.63  7512.4  126.07  7551.8  135.71  7599.7   137.4
#Mann= 6 ,-1 , 0
    4616     .12       0  4845.4      .1       0  4970.4     .07       0
  5031.6      .1       0  6295.7     .05       0  6963.6     .12       0
Bank Sta=4970.4,5031.6
XS Rating Curve= 0 ,0
Exp/Cntr=0.3,0.1

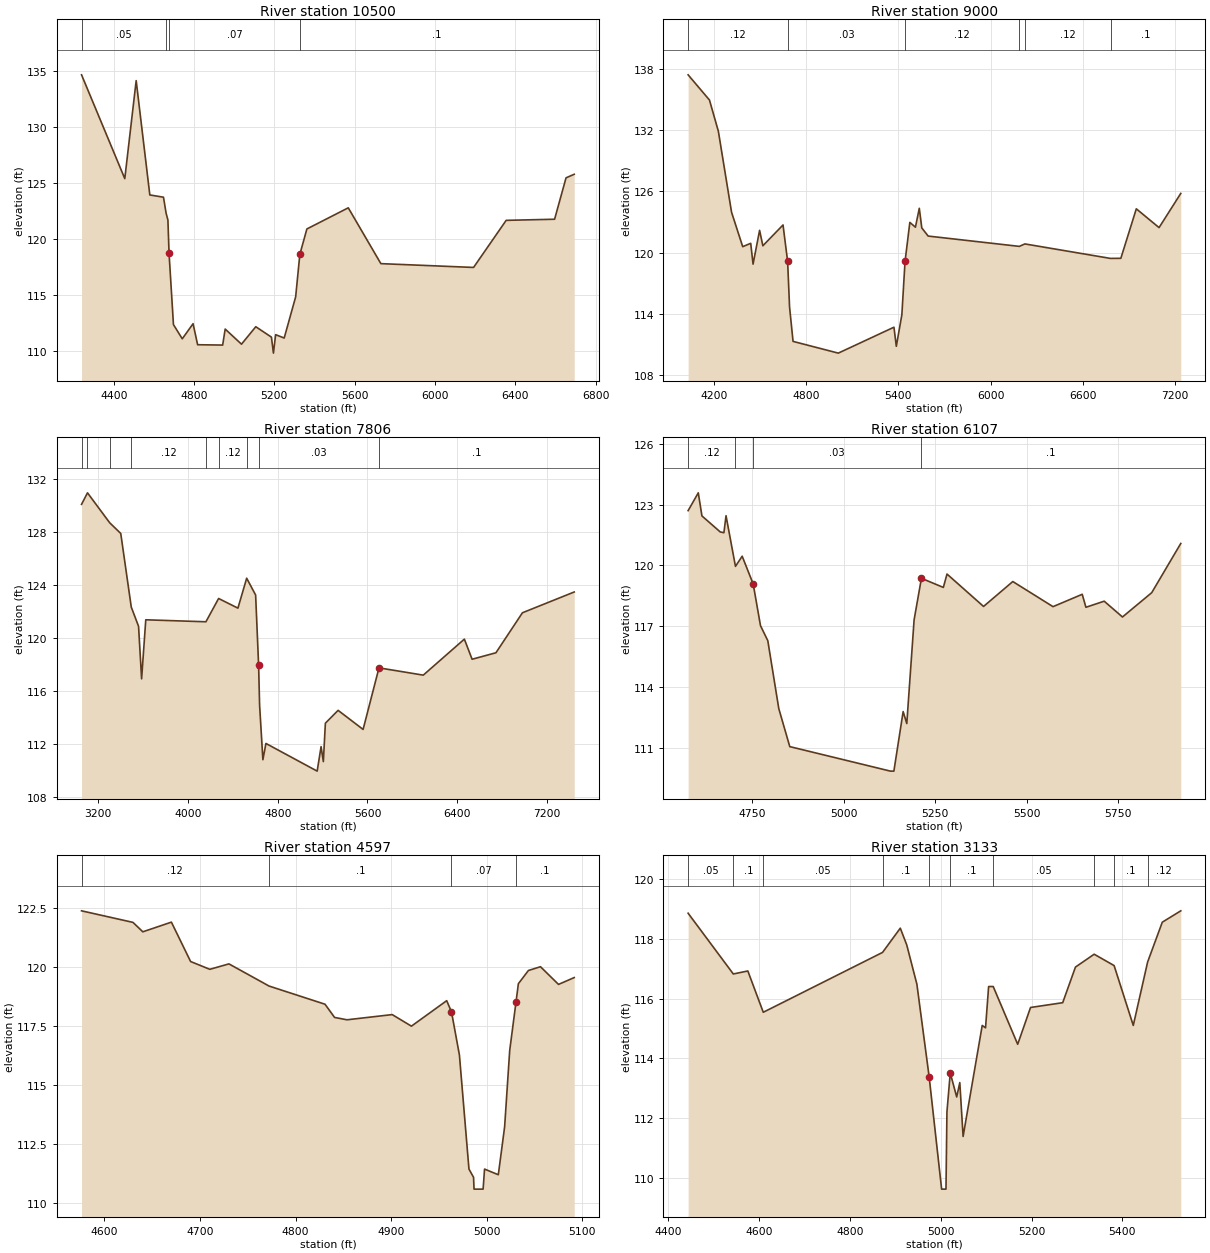
Type RM Length L Ch R = 1 ,10500   ,1500,1500,1500
BEGIN DESCRIPTION:
GRAND LAKE CREEK 21.0
END DESCRIPTION:
XS GIS Cut Line= 3
      3828917.86     10095561.08      3828559.73     10094890.41
      3827278.77     10093782.36
#Sta/Elev= 30
  4239.7  134.68  4455.1   125.4  4511.8  134.16  4579.8  123.94  4647.8  123.74
    4661   122.3  4669.9   121.7  4675.5  118.75  4697.5  112.35  4741.4  111.08
  4795.2  112.43  4817.9  110.55  4942.6  110.52  4955.2  111.95  5036.4   110.6
  5107.6  112.16  5185.5  111.23  5195.5   109.8  5206.4  111.45  5249.1  111.15
  5306.2  114.83    5327  118.62  5362.1   120.9  5568.3  122.79  5730.7   117.8
  6192.4  117.46  6354.8  121.67    6596  121.77    6653  125.47  6693.7  125.79
#Mann= 4 ,-1 , 0
  4239.7     .05       0    4661     .12       0  4675.5     .07       0
    5327      .1       0
Bank Sta=4675.5,5327
XS Rating Curve= 0 ,0
Exp/Cntr=0.3,0.1

Type RM Length L Ch R = 1 ,9000    ,1194,1194,1194
BEGIN DESCRIPTION:
GRAND LAKE CREEK 18.0
END DESCRIPTION:
XS GIS Cut Line= 3
      3830167.85     10094711.07      3829658.07     10093888.89
      3827487.12      10093351.8
#Sta/Elev= 30
  4032.6  137.42  4171.4  134.95  4229.3  131.89    4315  123.96  4387.6  120.58
  4439.6  120.91  4454.9  118.87  4497.4  122.18  4518.7  120.67  4649.8  122.71
  4679.7  119.14  4692.3  114.66    4715   111.3  5009.3  110.15  5371.1  112.69
  5386.5  110.82  5422.6  113.91  5443.2  119.13  5474.5  122.96  5510.8  122.49
  5535.9  124.34  5552.2  122.42  5593.6  121.62  6186.5  120.61  6222.7  120.85
  6779.4  119.43  6846.6  119.44  6947.2  124.29  7095.1  122.45  7236.4   125.8
#Mann= 6 ,-1 , 0
  4032.6     .12       0  4679.7     .03       0  5443.2     .12       0
  6186.5      .1       0  6222.7     .12       0  6779.4      .1       0
Bank Sta=4679.7,5443.2
XS Rating Curve= 0 ,0
Exp/Cntr=0.3,0.1

Type RM Length L Ch R = 1 ,7806    ,1699,1699,1699
BEGIN DESCRIPTION:
GRAND LAKE CREEK 15.0
END DESCRIPTION:
XS GIS Cut Line= 3
      3831667.86     10093961.08      3830102.21     10092801.17
      3827688.49     10092424.71
#Sta/Elev= 30
  3051.5  130.07  3104.5  130.94  3302.3  128.68    3401  127.87  3494.7  122.31
  3559.7  120.86  3586.8  116.89    3624  121.35    4160   121.2  4273.3  122.96
  4445.4  122.23  4523.4  124.49  4603.2  123.22 4629.64 117.962  4638.6   114.9
  4667.9  110.78    4695  112.01  5151.8  109.92  5186.6  111.77  5206.8  110.64
  5224.9  113.54  5338.4  114.51  5561.1  113.07  5702.8  117.72  6097.5  117.17
  6463.8  119.89  6532.7  118.37  6745.2  118.86  6981.4  121.88  7442.9  123.45
#Mann= 9 ,-1 , 0
  3051.5     .05       0  3104.5     .12       0  3302.3     .05       0
  3494.7     .12       0    4160     .05       0  4273.3     .12       0
  4523.4     .05       0 4629.64     .03       0  5702.8      .1       0
Bank Sta=4629.64,5702.8
XS Rating Curve= 0 ,0
Exp/Cntr=0.3,0.1

Type RM Length L Ch R = 1 ,6107    ,1510,1510,1510
BEGIN DESCRIPTION:
GRAND LAKE CREEK 12.0
END DESCRIPTION:
XS GIS Cut Line= 3
       3830425.6     10091131.04      3830061.02     10091113.68
      3829078.37     10091103.27
#Sta/Elev= 30
  4573.9   122.7  4601.7  123.58  4611.7  122.44  4661.7  121.65  4671.8  121.61
  4677.6  122.45  4703.4  119.95  4721.8  120.45  4751.9  119.08  4771.9  117.02
  4791.9  116.28  4821.9  112.93    4852  111.05  5127.4  109.84  5136.8  109.84
  5162.1  112.78  5172.1  112.19  5192.1  117.31  5212.1  119.36  5272.1  118.91
  5282.1  119.57  5382.1  117.97  5462.1   119.2  5572.1  117.96    5652  118.57
  5662.1  117.93  5712.1  118.23  5762.1  117.45  5842.1  118.65  5921.6  121.08
#Mann= 4 ,-1 , 0
  4573.9     .12       0  4703.4     .05       0  4751.9     .03       0
  5212.1      .1       0
Bank Sta=4751.9,5212.1
XS Rating Curve= 0 ,0
Exp/Cntr=0.3,0.1

Type RM Length L Ch R = 1 ,4597    ,1464,1464,1464
BEGIN DESCRIPTION:
GRAND LAKE CREEK 9.0
END DESCRIPTION:
XS GIS Cut Line= 3
      3831091.43     10089831.57      3830670.32     10089792.46
      3830582.19     10089764.42
#Sta/Elev= 30
  4576.1   122.4  4629.9  121.91  4640.2  121.51  4670.1  121.92  4690.2  120.25
  4710.3  119.92  4730.3  120.15  4772.3  119.21  4830.8  118.44  4840.8  117.88
  4853.8  117.78  4901.1     118  4921.2  117.51  4958.1  118.59  4963.1  118.12
  4971.4  116.29  4981.4  111.45  4986.2   111.1  4986.7   110.6  4996.2   110.6
  4997.7  111.45  5012.1  111.21  5018.7  113.24    5024  116.47 5030.56 118.517
  5033.1  119.31  5043.6  119.87  5056.2  120.03  5075.1  119.28  5091.5  119.57
#Mann= 4 ,-1 , 0
  4576.1     .12       0  4772.3      .1       0  4963.1     .07       0
 5030.56      .1       0
Bank Sta=4963.1,5030.56
XS Rating Curve= 0 ,0
Exp/Cntr=0.3,0.1

Type RM Length L Ch R = 1 ,3133    ,0,0,0
BEGIN DESCRIPTION:
GRAND LAKE CREEK 6.0
END DESCRIPTION:
XS GIS Cut Line= 3
      3831538.61     10088955.71      3831040.87     10088707.48
      3830679.19     10088321.99
#Sta/Elev= 30
  4443.8  118.85  4543.3  116.82  4575.3  116.92  4609.3  115.54  4871.9  117.54
    4911  118.35  4925.2  117.79  4947.5  116.48 4974.49 113.388    5002  109.63
  5011.6  109.63  5013.7  112.21    5021  113.51  5035.2  112.71    5042  113.19
  5049.3  111.39  5091.4   115.1  5098.7  115.02  5105.5   116.4  5115.6   116.4
  5169.5  114.47  5197.8   115.7  5268.6  115.86  5296.7  117.05  5337.9  117.48
  5381.8   117.1    5424   115.1  5455.6  117.22  5487.9  118.55  5528.6  118.93
#Mann= 10 ,-1 , 0
  4443.8     .05       0  4543.3      .1       0  4609.3     .05       0
  4871.9      .1       0 4974.49     .07       0    5021      .1       0
  5115.6     .05       0  5337.9     .12       0  5381.8      .1       0
  5455.6     .12       0
Bank Sta=4974.49,5021
XS Rating Curve= 0 ,0
Exp/Cntr=0.3,0.1