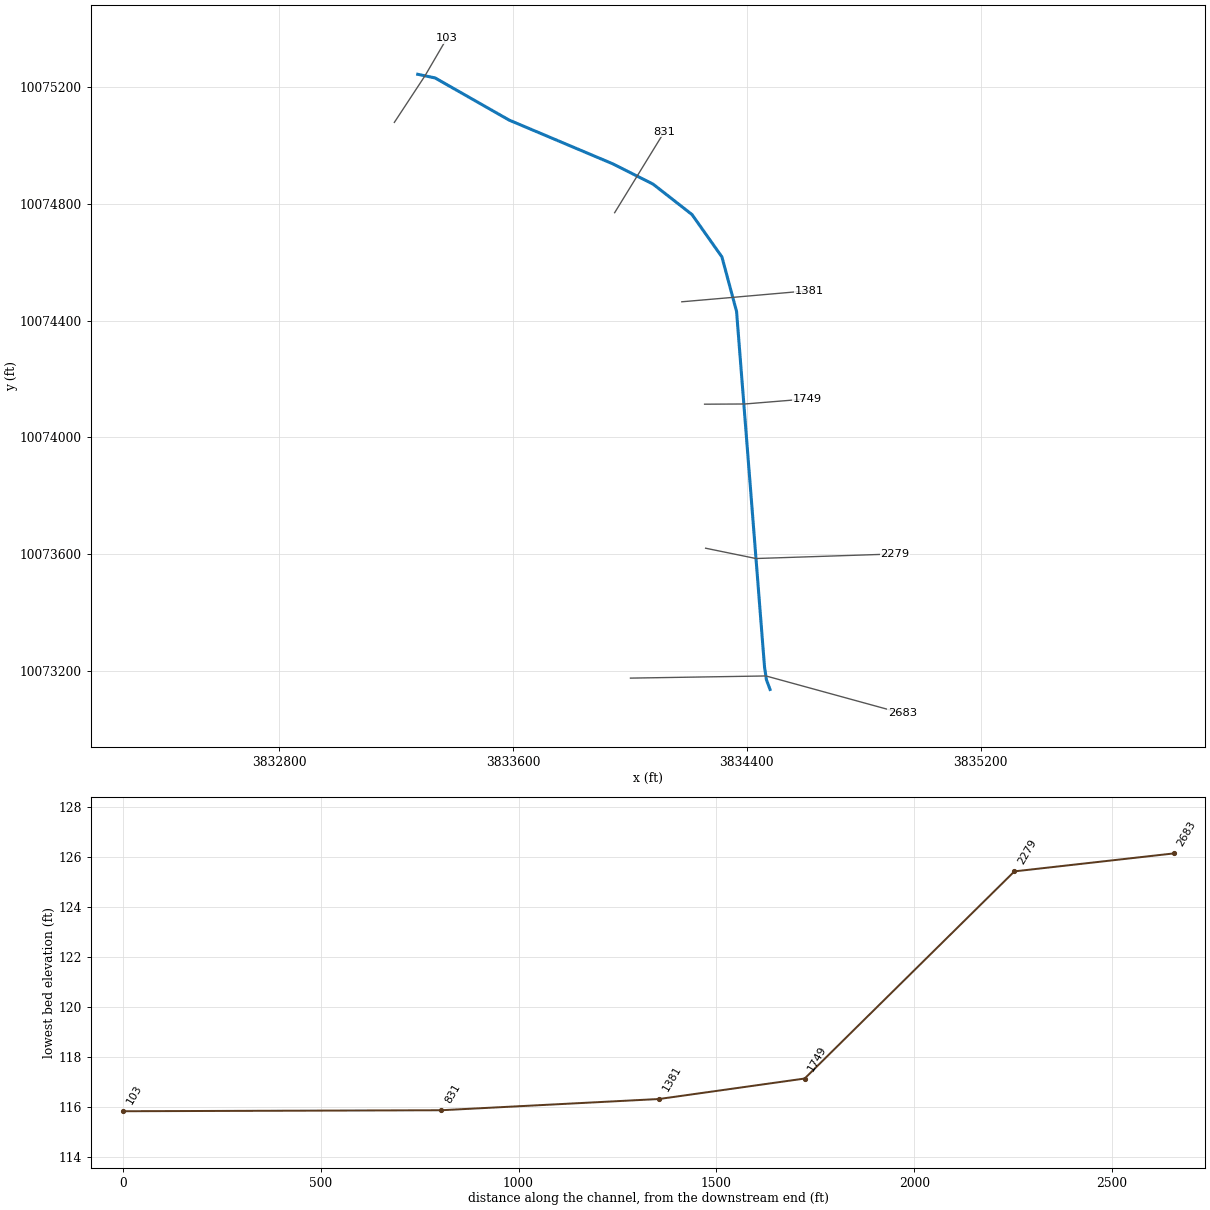
--- HARPERS HORSEPEN BRANCH.prj (project) ---

Proj Title=HARPERS HORSEPEN BRANCH Base Level Engineering
Current Plan=p01
Default Exp/Contr=0.3,0.1
English Units
Geom File=g01
Flow File=f01
Plan File=p01
Y Axis Title=Elevation
X Axis Title(PF)=Main Channel Distance
X Axis Title(XS)=Station
BEGIN DESCRIPTION:
HARPERS HORSEPEN BRANCH
END DESCRIPTION:
DSS Export Rating Curves= 0
DSS Export Rating Curve Sorted= 0
DSS Export Volume Flow Curves= 0
DXF OffsetX= 0
DXF OffsetY= 0
DXF ScaleX= 1
DXF ScaleY= 10

--- HARPERS HORSEPEN BRANCH.p01 (plan) ---

Plan Title=Multiple Run
Short Identifier=Multiple
Geom File=g01
Flow File=f01
Subcritical Flow
K Sum by GR= 0
Std Step Tol= 0.01
Critical Tol= 0.01
Num of Std Step Trials= 20
Max Error Tol= 0.3
Flow Tol Ratio= 0.001
Split Flow NTrial= 30
Split Flow Tol= 0.02
Split Flow Ratio= 0.02
Log Output Level= 0
Friction Slope Method= 1
Unsteady Friction Slope Method= 2
Unsteady Bridges Friction Slope Method= 1
Parabolic Critical Depth
Global Vel Dist=  1 , 1 , 1
Global Log Level= 0
CheckData=True
Encroach Param= -1, 0, 0, 0
BEGIN DESCRIPTION:
Multiple Run
END DESCRIPTION:

--- HARPERS HORSEPEN BRANCH.f01 (steady flow) ---

Flow Title=Multiple
Program Version=4.10
Number of Profiles= 7
Profile Names=10-year,25-year,50-year,1pct_min,100-year,1pct_plu,500-year
River Rch & RM=HARPERS HORSEPEN,Reach-1         ,2683
     398     518     682     296     893    2697    1581
Boundary for River Rch & Prof#=HARPERS HORSEPEN,Reach-1         , 1
Up Type= 0
Dn Type= 3
Dn Slope=0.005
Boundary for River Rch & Prof#=HARPERS HORSEPEN,Reach-1         , 2
Up Type= 0
Dn Type= 3
Dn Slope=0.005
Boundary for River Rch & Prof#=HARPERS HORSEPEN,Reach-1         , 3
Up Type= 0
Dn Type= 3
Dn Slope=0.005
Boundary for River Rch & Prof#=HARPERS HORSEPEN,Reach-1         , 4
Up Type= 0
Dn Type= 3
Dn Slope=0.005
Boundary for River Rch & Prof#=HARPERS HORSEPEN,Reach-1         , 5
Up Type= 0
Dn Type= 3
Dn Slope=0.005
Boundary for River Rch & Prof#=HARPERS HORSEPEN,Reach-1         , 6
Up Type= 0
Dn Type= 3
Dn Slope=0.005
Boundary for River Rch & Prof#=HARPERS HORSEPEN,Reach-1         , 7
Up Type= 0
Dn Type= 3
Dn Slope=0.005
DSS Import GetInterval= 0
DSS Import GetPeak= 0
DSS Import FillOption= 0

--- HARPERS HORSEPEN BRANCH.g01 (geometry) ---

Geom Title=Existing Conditions
Program Version=4.10

River Reach=HARPERS HORSEPEN,Reach-1
Reach XY= 11
      3834479.93     10073137.54      3834467.44     10073170.85
      3834460.96     10073214.38      3834365.29     10074430.89
       3834315.2     10074617.57      3834212.84     10074762.52
      3834079.73     10074866.58      3833942.55     10074935.74
        3833587.     10075085.81      3833333.95     10075229.92
      3833274.26      10075242.5

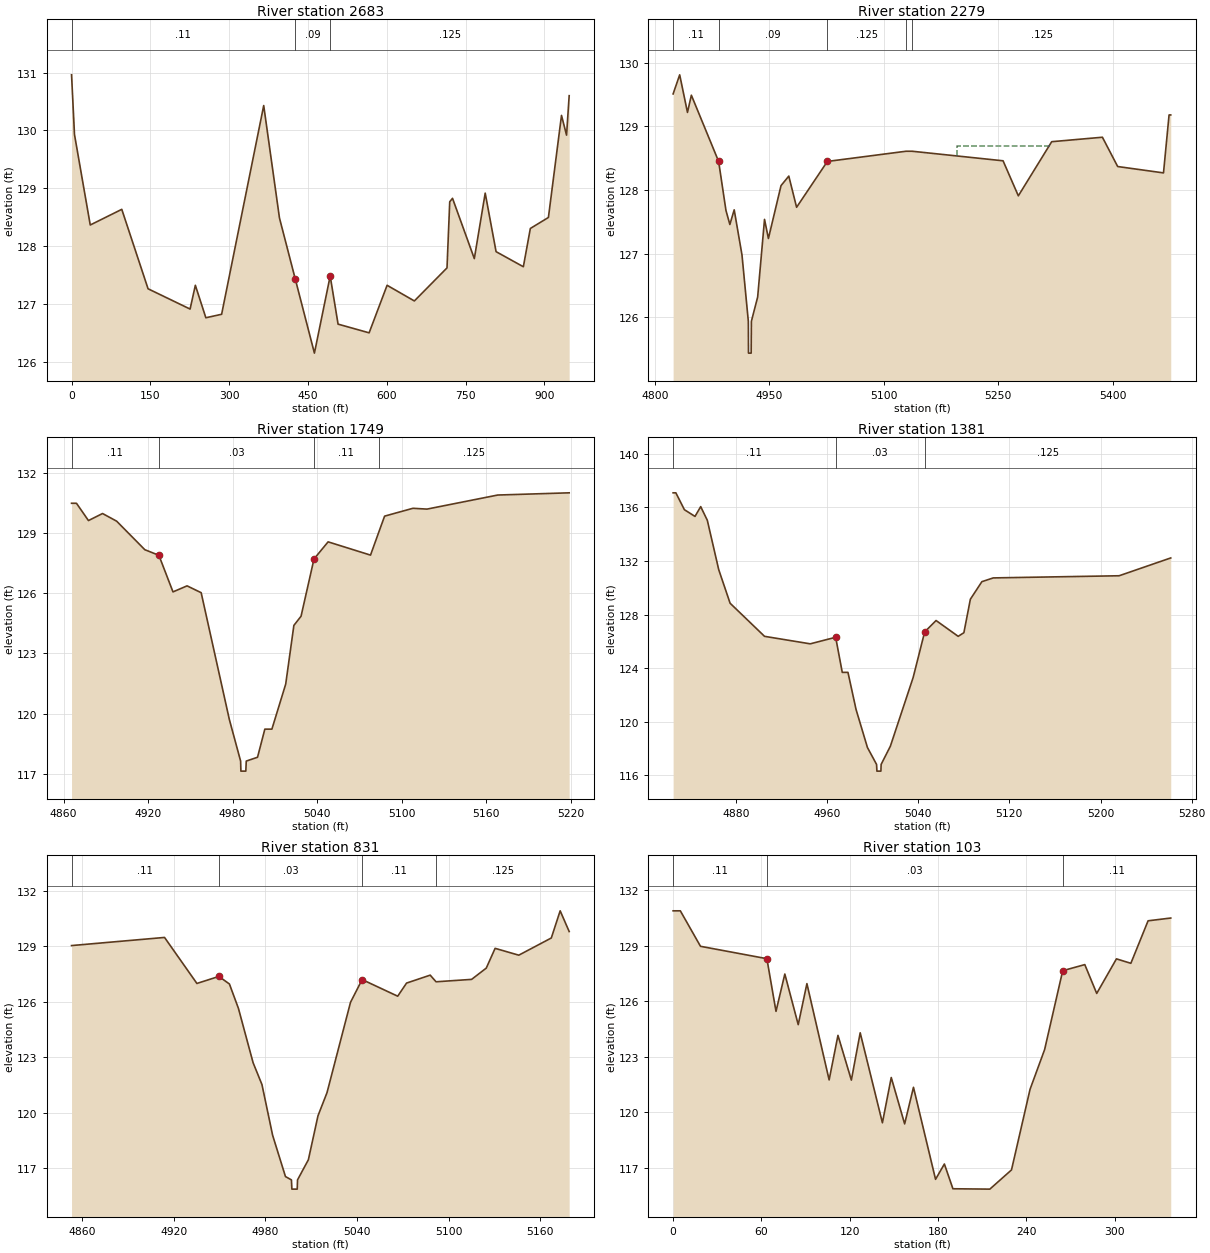
Type RM Length L Ch R = 1 ,2683    ,403,403,403
XS GIS Cut Line= 3
      3834002.24     10073176.39      3834465.88     10073183.77
      3834932.58     10073055.74
#Sta/Elev= 30
       0  130.96     5.6  129.93    35.6  128.37    95.6  128.64   145.6  127.27
   225.6  126.92   235.6  127.33   255.6  126.77   285.6  126.83   365.7  130.43
   395.7  128.49   425.7  127.44   462.2  126.16   492.2  127.49   507.2  126.66
   566.3  126.51   600.5  127.33   652.4  127.06   714.5  127.63   719.7  128.77
     725  128.83   766.5  127.79   787.2  128.92   807.9  127.91   859.8  127.65
   873.1  128.31   907.5   128.5   932.4  130.26     942  129.92     947   130.6
#Mann= 3 , 0 , 0
       0     .11       0   425.7     .09       0   492.2    .125       0
Bank Sta=425.7,492.2
XS Rating Curve= 0 ,0
Exp/Cntr=0.3,0.1

Type RM Length L Ch R = 1 ,2279    ,530,530,530
BEGIN DESCRIPTION:
HARPERS HORSEPEN BRANCH 5.0
END DESCRIPTION:
XS GIS Cut Line= 3
      3834259.44     10073620.86      3834431.77     10073585.58
      3834907.31     10073601.25
#Sta/Elev= 30
  4824.1  129.51  4832.7  129.81  4842.9  129.22    4848  129.49  4883.7  128.45
  4893.3  127.68  4898.4  127.46  4904.1  127.69  4914.3  126.98  4922.6  125.94
  4922.8  125.44  4926.3  125.44  4926.6  125.94  4934.8  126.32  4943.8  127.54
  4948.9  127.24  4965.4  128.07  4975.6  128.22  4985.8  127.73  5026.1  128.45
  5129.1  128.61  5137.3128.6098  5256.2  128.46  5276.2  127.91  5319.9  128.76
  5386.3  128.83  5406.3  128.37  5466.3  128.27  5473.6  129.18  5475.8  129.18
#Mann= 5 ,-1 , 0
  4824.1     .11       0  4883.7     .09       0  5026.1    .125       0
  5129.1     .15       0  5137.3    .125       0
#XS Ineff= 3 ,-1
  5196.2  5319.9   128.7  5319.9  5386.3  128.76  5386.3  5473.6  128.83
Permanent Ineff=
       F       F       F
Bank Sta=4883.7,5026.1
XS Rating Curve= 0 ,0
Exp/Cntr=0.3,0.1

Type RM Length L Ch R = 1 ,1749    ,368,368,368
BEGIN DESCRIPTION:
HARPERS HORSEPEN BRANCH 4.0
END DESCRIPTION:
XS GIS Cut Line= 3
      3834255.89     10074113.66      3834393.37     10074114.35
      3834608.37     10074131.87
#Sta/Elev= 30
  4865.7  130.47  4869.2  130.47  4877.7  129.61  4887.7  129.96  4897.7  129.58
  4917.7  128.16  4927.7  127.88  4937.7  126.06  4947.7  126.36  4957.7  126.02
  4977.7  119.71  4985.7  117.64  4985.9  117.14  4989.4  117.14  4989.7  117.64
  4997.7  117.83  5002.9  119.23  5007.9  119.23  5017.7  121.47  5023.5  124.39
  5028.6  124.85  5037.8   127.7  5047.8  128.55  5077.9  127.89  5083.6     129
  5087.9  129.83    5108  130.22    5118  130.18  5168.2  130.88  5218.9  130.99
#Mann= 4 ,-1 , 0
  4865.7     .11       0  4927.7     .03       0  5037.8     .11       0
  5083.6    .125       0
Bank Sta=4927.7,5037.8
XS Rating Curve= 0 ,0
Exp/Cntr=0.3,0.1

Type RM Length L Ch R = 1 ,1381    ,550,550,550
BEGIN DESCRIPTION:
HARPERS HORSEPEN BRANCH 3.0
END DESCRIPTION:
XS GIS Cut Line= 3
        3834178.     10074464.05      3834328.83     10074477.07
      3834612.94     10074502.01
#Sta/Elev= 30
    4825  137.09  4827.4  137.09  4834.9  135.83  4844.2  135.33  4849.2  136.06
    4855  135.04    4865  131.36    4875  128.85  4905.2  126.38  4945.3  125.82
  4967.6  126.31  4973.4  123.69  4978.4  123.69  4985.5  120.92  4995.5  118.08
  5003.5  116.82  5003.8  116.32  5007.3  116.32  5007.5  116.82  5015.6  118.18
  5035.6  123.31  5045.7  126.71  5055.7  127.56  5075.1  126.38  5080.1  126.65
  5085.8  129.15  5095.9  130.46  5105.9  130.74  5216.3   130.9  5261.6  132.23
#Mann= 3 , 0 , 0
    4825     .11       0  4967.6     .03       0  5045.7    .125       0
Bank Sta=4967.6,5045.7
XS Rating Curve= 0 ,0
Exp/Cntr=0.3,0.1

Type RM Length L Ch R = 1 ,831     ,805,805,805
BEGIN DESCRIPTION:
HARPERS HORSEPEN BRANCH 2.0
END DESCRIPTION:
XS GIS Cut Line= 2
      3833948.15     10074768.87      3834118.69     10075046.58
#Sta/Elev= 30
    4853  129.05  4913.9  129.49  4935.1     127  4949.5  127.38  4956.4  126.97
  4962.3  125.65  4971.9  122.71  4977.7  121.53  4984.7  118.78  4993.1  116.55
    4997  116.37  4997.3  115.87  5000.8  115.87    5001  116.37  5008.1  117.46
  5014.4  119.84  5020.3  121.09  5035.7  125.98  5043.3  127.21  5066.6  126.31
  5072.4  127.02  5087.9  127.45  5091.7  127.09    5115  127.22  5124.6  127.83
  5130.4   128.9  5145.9  128.53  5167.2  129.46    5173  130.93  5178.9  129.81
#Mann= 4 ,-1 , 0
    4853     .11       0  4949.5     .03       0  5043.3     .11       0
  5091.7    .125       0
Bank Sta=4949.5,5043.3
XS Rating Curve= 0 ,0
Exp/Cntr=0.3,0.1

Type RM Length L Ch R = 1 ,103     ,0,0,0
XS GIS Cut Line= 3
      3833194.36     10075077.85      3833299.15     10075237.25
      3833374.02     10075365.48
#Sta/Elev= 30
       0  130.89     4.9  130.89    18.6  128.97    63.7   128.3    69.9  125.45
    75.9  127.47      85  124.73    90.9  126.95     106  121.74     112  124.15
   121.1  121.73   127.1  124.29   142.2  119.42   148.2  121.87   157.3  119.36
   163.3  121.34   178.3  116.36   184.3  117.19   190.1  115.85   215.2  115.83
   229.9  116.87   242.5  121.23   252.4  123.38   264.7  127.65   279.7  127.98
   287.8  126.42   301.2  128.29     311  128.05   322.7  130.35   338.1   130.5
#Mann= 3 , 0 , 0
       0     .11       0    63.7     .03       0   264.7     .11       0
Bank Sta=63.7,264.7
XS Rating Curve= 0 ,0
Exp/Cntr=0.3,0.1

Chan Stop Cuts=-1
Use User Specified Reach Order=0
Composite Channel Slope=5

--- HARPERS HORSEPEN BRANCH.g10 (geometry) ---

Geom Title=Existing Conditions
Program Version=4.10

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
River Reach=HARPERS HORSEPEN,Reach-1

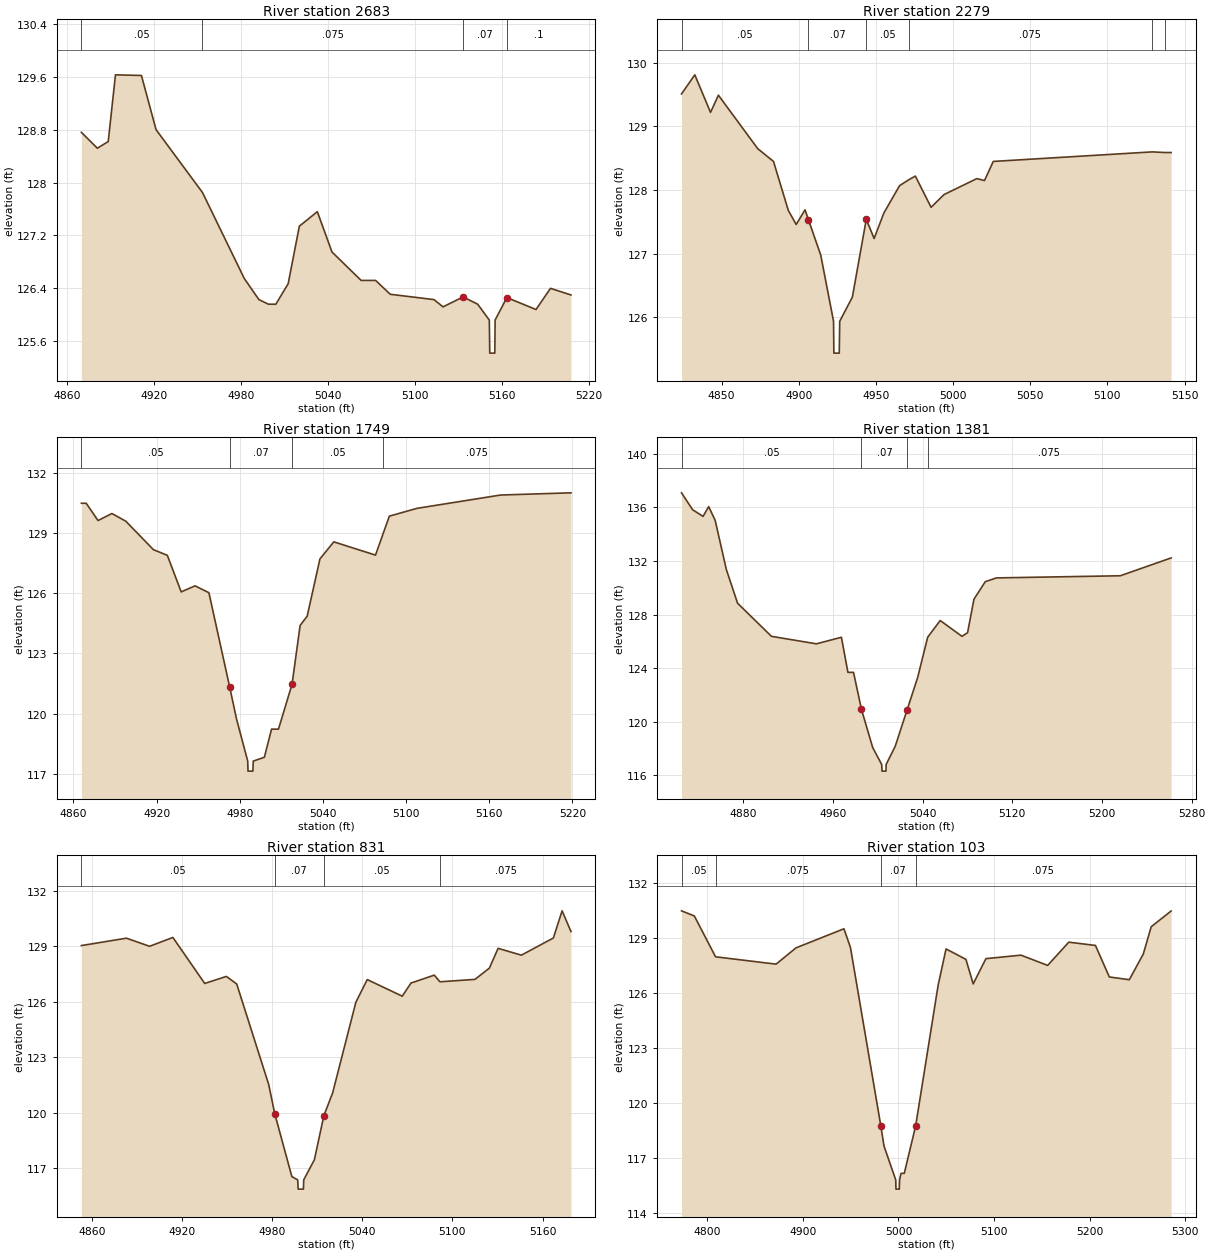
Type RM Length L Ch R = 1 ,2683    ,404,404,404
BEGIN DESCRIPTION:
HARPERS HORSEPEN BRANCH 6.0
END DESCRIPTION:
XS GIS Cut Line= 3
      3834337.03      10073162.7      3834465.88     10073183.77
      3834671.83     10073204.99
#Sta/Elev= 30
  4869.8  128.76  4880.8  128.52  4888.3  128.62  4893.3  129.63  4911.2  129.62
  4921.3   128.8  4953.3  127.85  4982.1  126.55  4992.2  126.23  4998.8  126.16
  5003.9  126.16  5012.4  126.47  5020.1  127.34  5032.5  127.56  5042.6  126.95
  5062.7  126.52  5072.7  126.52  5082.8  126.31  5112.9  126.23  5119.2  126.12
    5133  126.27  5143.1  126.16  5151.1  125.92  5151.4  125.42  5154.9  125.42
  5155.1  125.92  5163.2  126.26  5183.3  126.08  5193.3   126.4  5207.4   126.3
#Mann= 4 ,-1 , 0
  4869.8     .05       0  4953.3    .075       0    5133     .07       0
  5163.2      .1       0
Bank Sta=5133,5163.2
XS Rating Curve= 0 ,0
Exp/Cntr=0.3,0.1

Type RM Length L Ch R = 1 ,2279    ,530,530,530
BEGIN DESCRIPTION:
HARPERS HORSEPEN BRANCH 5.0
END DESCRIPTION:
XS GIS Cut Line= 3
      3834259.44     10073620.86      3834431.77     10073585.58
      3834573.02     10073589.13
#Sta/Elev= 30
  4824.1  129.51  4832.7  129.81  4842.9  129.22    4848  129.49  4873.5  128.65
  4883.7  128.45  4893.3  127.68  4898.4  127.46  4904.1  127.69 4906.33 127.535
  4914.3  126.98  4922.6  125.94  4922.8  125.44  4926.3  125.44  4926.6  125.94
  4934.8  126.32  4943.8  127.54  4948.9  127.24  4955.2  127.64  4965.4  128.07
  4971.2  128.16  4975.6  128.22  4985.8  127.73  4994.2  127.93  5015.4  128.18
  5020.4  128.15  5026.1  128.45  5129.1   128.6  5137.3  128.59  5141.3  128.59
#Mann= 6 ,-1 , 0
  4824.1     .05       0 4906.33     .07       0  4943.8     .05       0
  4971.2    .075       0  5129.1      .1       0  5137.3    .075       0
Bank Sta=4906.33,4943.8
XS Rating Curve= 0 ,0
Exp/Cntr=0.3,0.1

Type RM Length L Ch R = 1 ,1749    ,368,368,368
BEGIN DESCRIPTION:
HARPERS HORSEPEN BRANCH 4.0
END DESCRIPTION:
XS GIS Cut Line= 3
      3834255.89     10074113.66      3834393.37     10074114.35
      3834608.37     10074131.87
#Sta/Elev= 30
  4865.7  130.47  4869.2  130.47  4877.7  129.61  4887.7  129.96  4897.7  129.58
  4917.7  128.16  4927.7  127.88  4937.7  126.06  4947.7  126.36  4957.7  126.02
 4972.67  121.33  4977.7  119.71  4985.7  117.64  4985.9  117.14  4989.4  117.14
  4989.7  117.64  4997.7  117.83  5002.9  119.23  5007.9  119.23  5017.7  121.47
  5023.5  124.39  5028.6  124.85  5037.8   127.7  5047.8  128.55  5077.9  127.89
  5083.6     129  5087.9  129.83    5108  130.22  5168.2  130.88  5218.9  130.99
#Mann= 4 ,-1 , 0
  4865.7     .05       0 4972.67     .07       0  5017.7     .05       0
  5083.6    .075       0
Bank Sta=4972.67,5017.7
XS Rating Curve= 0 ,0
Exp/Cntr=0.3,0.1

Type RM Length L Ch R = 1 ,1381    ,550,550,550
BEGIN DESCRIPTION:
HARPERS HORSEPEN BRANCH 3.0
END DESCRIPTION:
XS GIS Cut Line= 3
        3834178.     10074464.05      3834328.83     10074477.07
      3834612.94     10074502.01
#Sta/Elev= 30
    4825  137.09  4834.9  135.83  4844.2  135.33  4849.2  136.06    4855  135.04
    4865  131.36    4875  128.85  4905.2  126.38  4945.3  125.82  4967.6  126.31
  4973.4  123.69  4978.4  123.69  4985.5  120.92  4995.5  118.08  5003.5  116.82
  5003.8  116.32  5007.3  116.32  5007.5  116.82  5015.6  118.18 5026.21 120.901
  5035.6  123.31  5044.5  126.31  5055.7  127.56  5075.1  126.38  5080.1  126.65
  5085.8  129.15  5095.9  130.46  5105.9  130.74  5216.3   130.9  5261.6  132.23
#Mann= 4 ,-1 , 0
    4825     .05       0  4985.5     .07       0 5026.21     .05       0
  5044.5    .075       0
Bank Sta=4985.5,5026.21
XS Rating Curve= 0 ,0
Exp/Cntr=0.3,0.1

Type RM Length L Ch R = 1 ,831     ,728,728,728
BEGIN DESCRIPTION:
HARPERS HORSEPEN BRANCH 2.0
END DESCRIPTION:
XS GIS Cut Line= 2
      3833948.15     10074768.87      3834118.69     10075046.58
#Sta/Elev= 30
    4853  129.05    4883  129.45  4898.4  129.01  4913.9  129.49  4935.1     127
  4949.5  127.38  4956.4  126.97  4977.7  121.53 4981.72 119.951  4993.1  116.55
    4997  116.37  4997.3  115.87  5000.8  115.87    5001  116.37  5008.1  117.46
  5014.4  119.84  5020.3  121.09  5035.7  125.98  5043.3  127.21  5066.6  126.31
  5072.4  127.02  5087.9  127.45  5091.7  127.09    5115  127.22  5124.6  127.83
  5130.4   128.9  5145.9  128.53  5167.2  129.46    5173  130.93  5178.9  129.81
#Mann= 4 ,-1 , 0
    4853     .05       0 4981.72     .07       0  5014.4     .05       0
  5091.7    .075       0
Bank Sta=4981.72,5014.4
XS Rating Curve= 0 ,0
Exp/Cntr=0.3,0.1

Type RM Length L Ch R = 1 ,103     ,0,0,0
BEGIN DESCRIPTION:
HARPERS HORSEPEN BRANCH 1.0
END DESCRIPTION:
XS GIS Cut Line= 3
      3833199.87     10075059.72      3833372.93     10075210.76
      3833542.37     10075436.68
#Sta/Elev= 30
  4773.1   130.5  4786.5  130.22  4808.7  127.99    4872  127.59  4892.9  128.48
    4943  129.52  4949.8   128.5 4981.52 118.782  4984.9  117.66  4997.2  115.81
  4997.4  115.31  5000.9  115.31  5001.2  115.81  5002.7  116.17  5006.1  116.17
    5018 118.757  5041.5  126.43  5049.8  128.42  5070.6  127.85  5078.2  126.51
  5091.5  127.89  5128.2  128.08  5156.1  127.52  5178.2  128.79  5206.1  128.61
  5220.6  126.89  5241.5  126.74  5256.1  128.14  5264.4  129.63  5285.2  130.49
#Mann= 4 ,-1 , 0
  4773.1     .05       0  4808.7    .075       0 4981.52     .07       0
    5018    .075       0
Bank Sta=4981.52,5018
XS Rating Curve= 0 ,0
Exp/Cntr=0.3,0.1