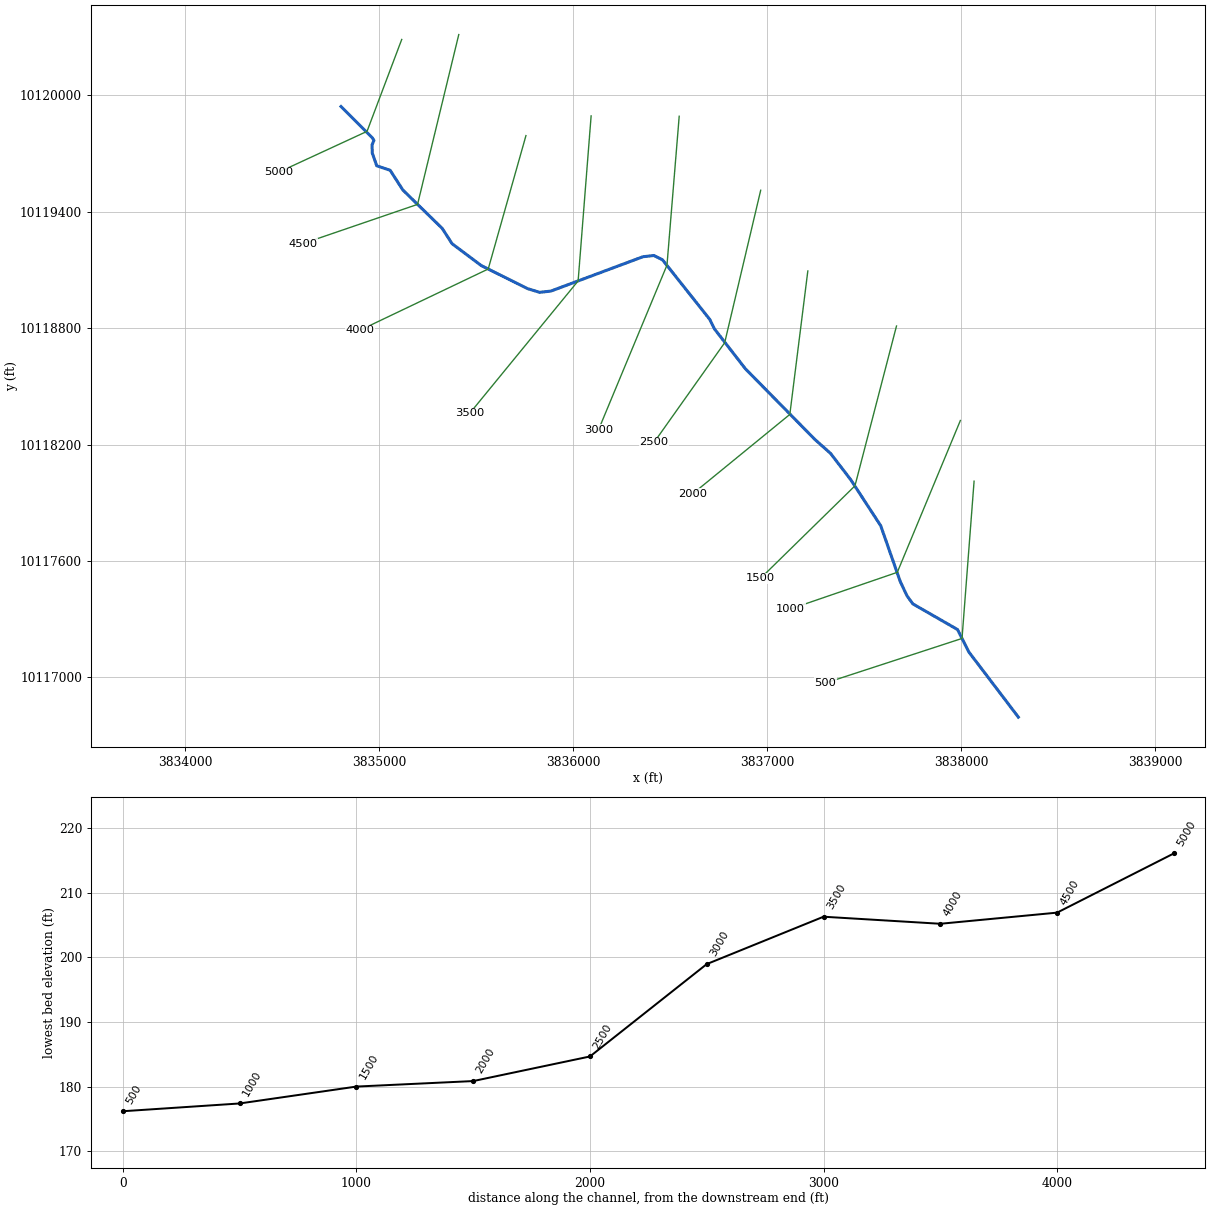
--- NORTH FORK STEWARTS CREEK.prj (project) ---

Proj Title=NORTH FORK STEWARTS CREEK Base Level Engineering
Current Plan=p01
Default Exp/Contr=0.3,0.1
English Units
Geom File=g01
Flow File=f01
Plan File=p01
Y Axis Title=Elevation
X Axis Title(PF)=Main Channel Distance
X Axis Title(XS)=Station
BEGIN DESCRIPTION:
NORTH FORK STEWARTS CREEK
END DESCRIPTION:
DSS Export Rating Curves= 0
DSS Export Rating Curve Sorted= 0
DSS Export Volume Flow Curves= 0
DXF OffsetX= 0
DXF OffsetY= 0
DXF ScaleX= 1
DXF ScaleY= 10

--- NORTH FORK STEWARTS CREEK.p01 (plan) ---

Plan Title=Multiple Run
Short Identifier=Multiple
Geom File=g01
Flow File=f01
Subcritical Flow
K Sum by GR= 0
Std Step Tol= 0.01
Critical Tol= 0.01
Num of Std Step Trials= 20
Max Error Tol= 0.3
Flow Tol Ratio= 0.001
Split Flow NTrial= 30
Split Flow Tol= 0.02
Split Flow Ratio= 0.02
Log Output Level= 0
Friction Slope Method= 1
Unsteady Friction Slope Method= 2
Unsteady Bridges Friction Slope Method= 1
Parabolic Critical Depth
Global Vel Dist=  1 , 1 , 1
Global Log Level= 0
CheckData=True
Encroach Param= -1, 0, 0, 0
BEGIN DESCRIPTION:
Multiple Run
END DESCRIPTION:

--- NORTH FORK STEWARTS CREEK.f01 (steady flow) ---

Flow Title=Multiple
Program Version=4.10
Number of Profiles= 7
Profile Names=10-year,25-year,50-year,1pct_min,100-year,1pct_plu,500-year
River Rch & RM=NORTH FORK STEWA,Reach-1         ,5000
     437     577     767     337    1017    3071    1839
Boundary for River Rch & Prof#=NORTH FORK STEWA,Reach-1         , 1
Up Type= 0
Dn Type= 3
Dn Slope=0.005
Boundary for River Rch & Prof#=NORTH FORK STEWA,Reach-1         , 2
Up Type= 0
Dn Type= 3
Dn Slope=0.005
Boundary for River Rch & Prof#=NORTH FORK STEWA,Reach-1         , 3
Up Type= 0
Dn Type= 3
Dn Slope=0.005
Boundary for River Rch & Prof#=NORTH FORK STEWA,Reach-1         , 4
Up Type= 0
Dn Type= 3
Dn Slope=0.005
Boundary for River Rch & Prof#=NORTH FORK STEWA,Reach-1         , 5
Up Type= 0
Dn Type= 3
Dn Slope=0.005
Boundary for River Rch & Prof#=NORTH FORK STEWA,Reach-1         , 6
Up Type= 0
Dn Type= 3
Dn Slope=0.005
Boundary for River Rch & Prof#=NORTH FORK STEWA,Reach-1         , 7
Up Type= 0
Dn Type= 3
Dn Slope=0.005
DSS Import GetInterval= 0
DSS Import GetPeak= 0
DSS Import FillOption= 0

--- NORTH FORK STEWARTS CREEK.g01 (geometry) ---

Geom Title=Existing Conditions
Program Version=4.10

River Reach=NORTH FORK STEWA,Reach-1
Reach XY= 30
      3834804.23     10119942.61      3834966.19     10119780.46
      3834973.75      10119767.7      3834964.63     10119746.35
      3834965.15     10119703.38      3834988.24     10119637.06
      3835057.51     10119613.97      3835122.96     10119512.23
      3835325.56     10119314.67      3835377.12     10119234.91
      3835526.13      10119123.4      3835765.56     10119003.88
      3835828.42      10118984.6      3835886.18     10118991.14
      3836360.68      10119168.2      3836416.41     10119174.67
       3836461.4      10119152.6      3836705.11     10118845.16
       3836729.3      10118796.2      3836888.43     10118591.08
      3837246.74     10118226.64      3837327.98     10118154.18
      3837432.02     10118018.67      3837586.54     10117781.33
      3837687.29     10117493.59      3837722.63     10117419.08
       3837752.4     10117378.38      3837982.47     10117246.32
      3838040.63     10117130.87      3838296.07      10116794.7

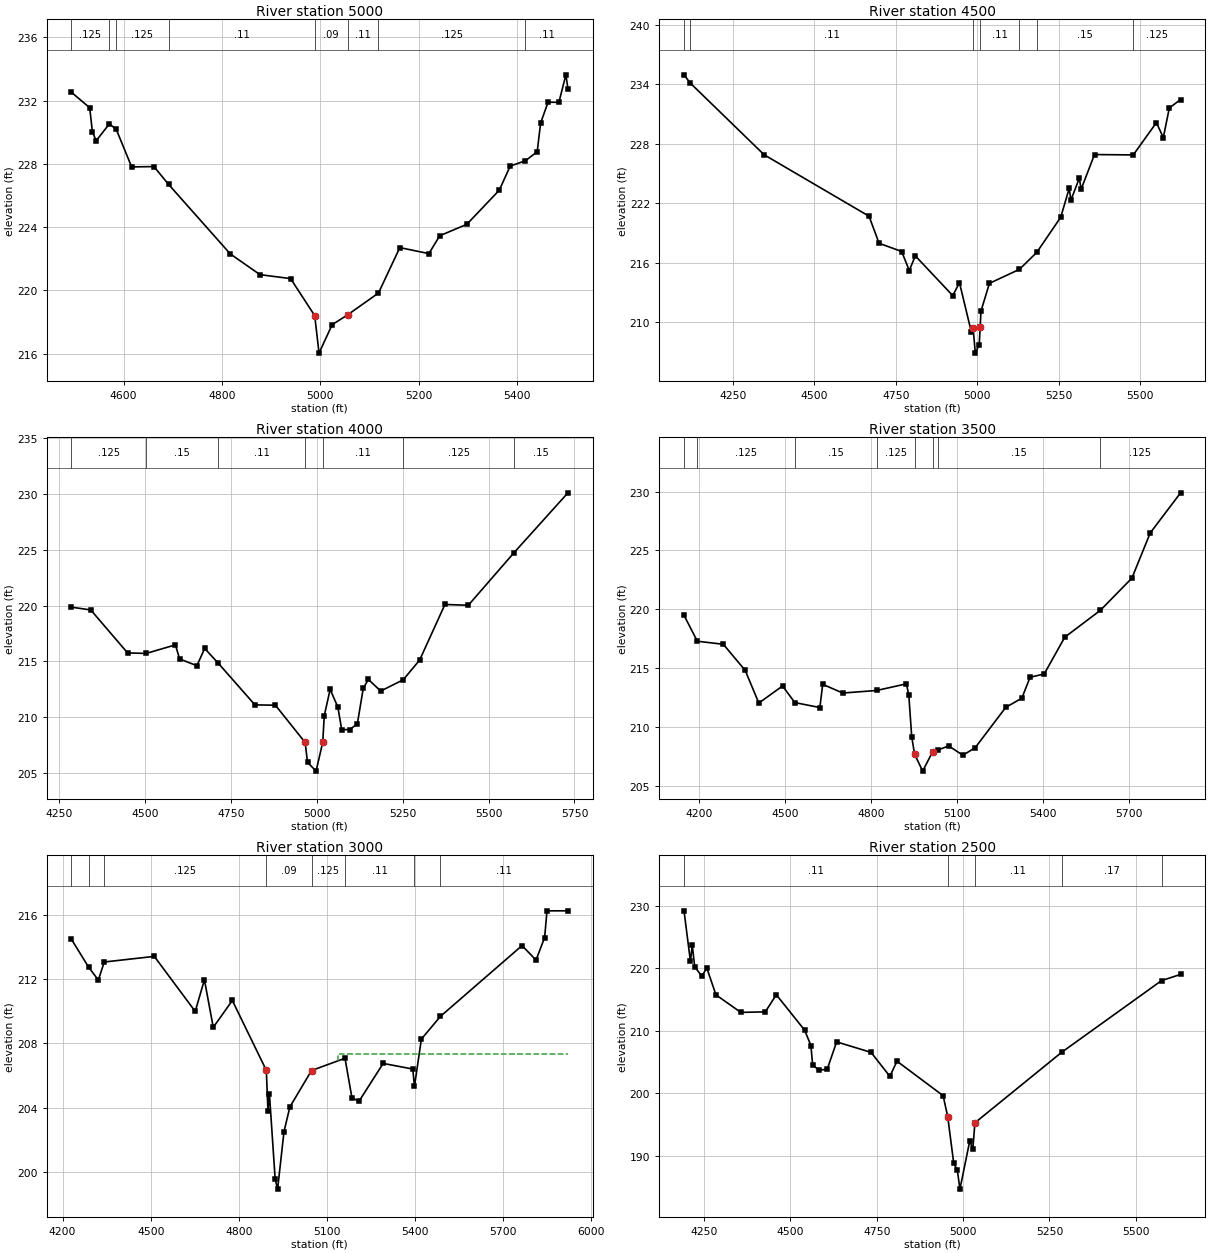
Type RM Length L Ch R = 1 ,5000    ,500,500,500
BEGIN DESCRIPTION:
NORTH FORK STEWARTS CREEK 10.0
END DESCRIPTION:
XS GIS Cut Line= 3
      3835117.08     10120288.24       3834938.3     10119814.56
      3834481.15     10119603.31
#Sta/Elev= 30
  4493.7  232.53    4531  231.55  4536.4  230.04  4544.1  229.46    4571  230.53
  4584.9  230.19  4616.3  227.81  4661.7  227.83  4691.5   226.7  4816.9  222.31
  4877.3     221  4939.6  220.75 4988.61218.4075  4997.4  216.04  5024.1  217.84
  5055.6  218.46  5118.3  219.84  5161.7  222.71  5220.8  222.33  5242.9  223.46
  5297.9  224.18    5364  226.34  5386.1  227.86  5417.1   228.2  5441.1  228.77
    5448  230.58  5463.2   231.9  5485.2  231.89  5499.4  233.63  5503.6  232.76
#Mann= 8 ,-1 , 0
  4493.7    .125       0    4571     .15       0  4584.9    .125       0
  4691.5     .11       0 4988.61     .09       0  5055.6     .11       0
  5118.3    .125       0  5417.1     .11       0
Bank Sta=4988.61,5055.6
XS Rating Curve= 0 ,0
Exp/Cntr=0.3,0.1

Type RM Length L Ch R = 1 ,4500    ,500,500,500
BEGIN DESCRIPTION:
NORTH FORK STEWARTS CREEK 9.0
END DESCRIPTION:
XS GIS Cut Line= 3
      3835411.25     10120313.51      3835198.79     10119438.13
      3834607.57     10119235.75
#Sta/Elev= 30
  4099.2  234.96  4118.4  234.13  4345.2   226.9  4667.7   220.7  4698.5  217.97
  4768.1  217.14  4791.2  215.22  4809.9   216.7  4924.9  212.69  4945.5     214
  4982.2  208.99  4987.3  209.45  4994.2  206.89  5006.3  207.76 5009.08209.5277
  5011.6  211.13  5037.6  213.93  5129.7  215.34    5183  217.05  5256.7   220.6
  5282.7  223.52  5287.9  222.32    5314  224.55  5319.2  223.41  5360.4  226.92
  5479.5  226.88  5550.6  230.14  5571.8  228.63  5590.3  231.62  5624.9  232.47
#Mann= 7 ,-1 , 0
  4099.2    .125       0  4118.4     .11       0  4987.3     .09       0
 5009.08     .11       0  5129.7    .125       0    5183     .15       0
  5479.5    .125       0
Bank Sta=4987.3,5009.08
XS Rating Curve= 0 ,0
Exp/Cntr=0.3,0.1

Type RM Length L Ch R = 1 ,4000    ,500,500,500
BEGIN DESCRIPTION:
NORTH FORK STEWARTS CREEK 8.0
END DESCRIPTION:
XS GIS Cut Line= 3
       3835757.6     10119792.67      3835563.11     10119104.94
       3834903.4     10118790.07
#Sta/Elev= 30
  4285.3  219.87  4341.8  219.62  4448.9  215.77  4502.8  215.72  4588.3  216.49
  4600.3  215.23  4650.7  214.62  4673.4  216.17  4713.1  214.84  4819.7  211.11
  4879.3  211.08  4965.9  207.74  4972.8  205.96  4997.7  205.17 5017.15207.7572
  5021.5  210.13  5038.7   212.5  5061.2   210.9  5072.4  208.88  5095.1   208.9
  5117.8  209.39    5135  212.58  5149.9  213.39  5185.9  212.35  5251.5  213.36
  5299.3  215.13  5372.9  220.11    5441  220.04  5573.6  224.74    5731  230.12
#Mann= 7 ,-1 , 0
  4285.3    .125       0  4502.8     .15       0  4713.1     .11       0
  4965.9     .09       0 5017.15     .11       0  5251.5    .125       0
  5573.6     .15       0
#XS Ineff= 2 , 0
       0                  5038.7       0   212.5
Permanent Ineff=
       F       F
Bank Sta=4965.9,5017.15
XS Rating Curve= 0 ,0
Exp/Cntr=0.3,0.1

Type RM Length L Ch R = 1 ,3500    ,500,500,500
BEGIN DESCRIPTION:
NORTH FORK STEWARTS CREEK 7.0
END DESCRIPTION:
XS GIS Cut Line= 3
      3836093.54      10119894.3      3836026.57     10119043.53
      3835467.85     10118361.07
#Sta/Elev= 30
  4146.6  219.49  4193.1  217.29    4284  217.03  4360.5  214.81    4408  212.04
  4490.9  213.49  4533.9  212.08  4621.3  211.66  4631.3  213.63  4701.5  212.89
  4820.2  213.11  4923.6  213.67  4932.2  212.73  4942.3  209.19  4952.3   207.7
  4980.7  206.26  5015.6  207.92  5033.6  208.05  5071.6   208.4  5121.2  207.61
  5164.2  208.25  5271.2  211.68  5327.2  212.45  5355.9  214.23  5405.4  214.51
  5477.2  217.63  5601.5  219.91  5711.9  222.65  5775.8  226.48    5882  229.89
#Mann= 8 ,-1 , 0
  4146.6     .11       0  4193.1    .125       0  4533.9     .15       0
  4820.2    .125       0  4952.3     .09       0  5015.6    .125       0
  5033.6     .15       0  5601.5    .125       0
Bank Sta=4952.3,5015.6
XS Rating Curve= 0 ,0
Exp/Cntr=0.3,0.1

Type RM Length L Ch R = 1 ,3000    ,500,500,500
BEGIN DESCRIPTION:
NORTH FORK STEWARTS CREEK 6.0
END DESCRIPTION:
XS GIS Cut Line= 3
      3836547.66     10119892.47      3836484.65     10119124.95
      3836131.35     10118275.27
#Sta/Elev= 30
  4229.9  214.47  4288.6  212.73  4321.6  211.93  4341.9  213.05  4512.2   213.4
  4651.5  209.98  4682.8  211.95  4712.9  208.99  4777.8  210.66  4893.5  206.32
  4899.1   203.8  4904.1  204.85  4923.6  199.57  4931.9  198.94  4953.7  202.52
  4973.8  204.05  5047.5  206.31  5161.3  207.07  5184.9  204.62  5208.8  204.39
  5291.2  206.75    5392   206.4  5397.8  205.33  5421.3  208.26  5486.1  209.67
  5763.9  214.07  5811.6  213.17  5840.8  214.57  5848.9  216.23  5920.2  216.23
#Mann= 8 ,-1 , 0
  4229.9    .125       0  4288.6     .11       0  4341.9    .125       0
  4893.5     .09       0  5047.5    .125       0  5161.3     .11       0
  5397.8    .125       0  5486.1     .11       0
#XS Ineff= 2 , 0
       0                  5137.2       0  207.36
Permanent Ineff=
       F       F
Bank Sta=4893.5,5047.5
XS Rating Curve= 0 ,0
Exp/Cntr=0.3,0.1

Type RM Length L Ch R = 1 ,2500    ,500,500,500
BEGIN DESCRIPTION:
NORTH FORK STEWARTS CREEK 5.0
END DESCRIPTION:
XS GIS Cut Line= 3
      3836967.86     10119511.11      3836782.12     10118724.85
      3836417.86     10118211.08
#Sta/Elev= 30
  4192.1  229.18  4210.7  221.08  4215.9  223.73    4223  220.23  4243.5  218.74
  4258.2  220.01  4284.6  215.74  4356.5  212.94  4427.4  213.02  4459.3  215.76
  4541.5  210.08  4559.4  207.64  4564.5  204.57  4582.6  203.67  4606.8  203.87
    4634  208.22  4733.7  206.54  4788.1  202.71  4808.7  205.13  4942.2  199.62
  4955.5  196.28  4973.1  188.77  4983.3  187.74  4990.9  184.67  5019.5  192.41
  5028.2  191.01  5034.3  195.28  5285.9  206.57  5574.7  218.02  5629.8  219.01
#Mann= 5 ,-1 , 0
  4192.1     .11       0  4955.5     .09       0  5034.3     .11       0
  5285.9     .17       0  5574.7     .11       0
#XS Ineff= 2 , 0
       0                  5019.5       0  192.41
Permanent Ineff=
       F       F
Bank Sta=4955.5,5034.3
XS Rating Curve= 0 ,0
Exp/Cntr=0.3,0.1

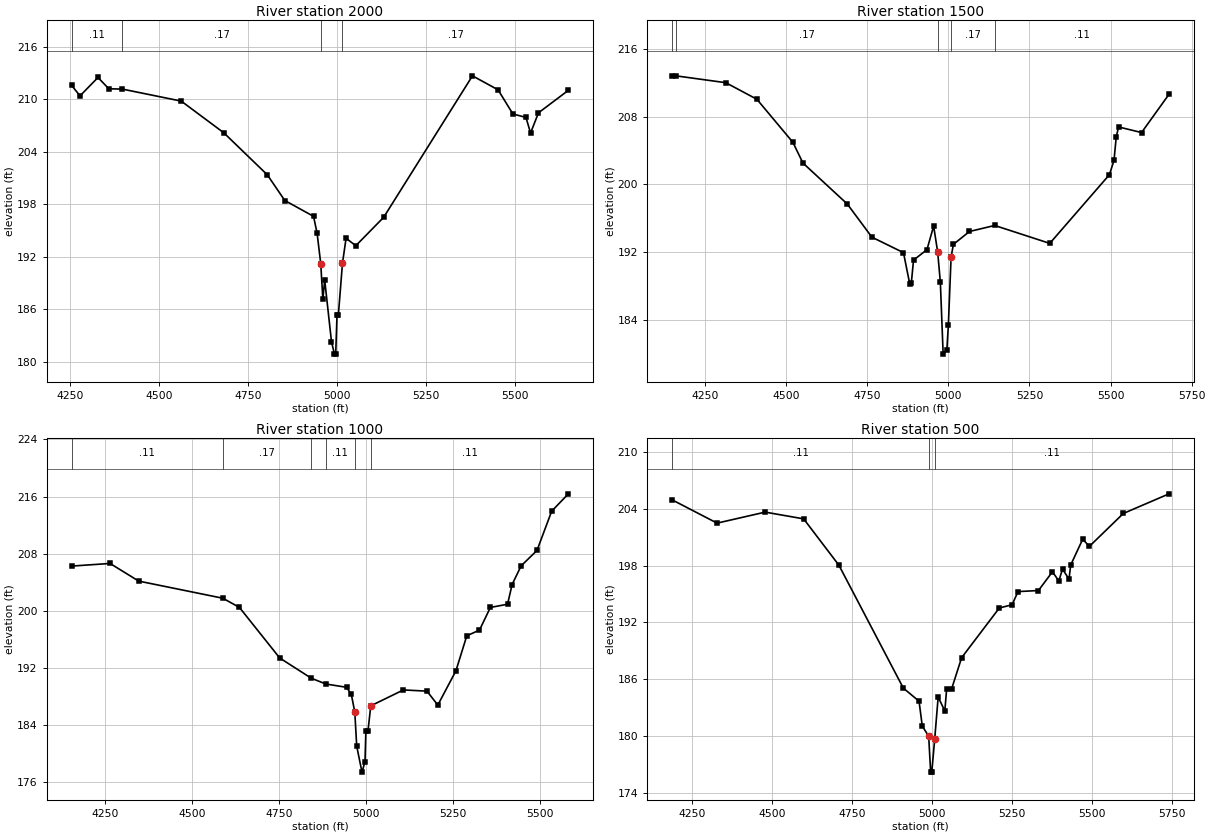
Type RM Length L Ch R = 1 ,2000    ,500,500,500
BEGIN DESCRIPTION:
NORTH FORK STEWARTS CREEK 4.0
END DESCRIPTION:
XS GIS Cut Line= 3
      3837210.73     10119094.82      3837117.99     10118355.31
      3836615.77     10117944.88
#Sta/Elev= 30
  4254.7  211.62  4278.6  210.41    4329  212.51  4359.3  211.22  4397.6  211.18
  4562.5  209.81  4681.8  206.19    4804  201.38  4853.1  198.44  4933.7  196.63
  4943.8  194.68  4953.9  191.23  4959.9  187.13    4965  189.35  4984.1  182.29
  4992.4  180.87  4995.9  180.87  4999.6  185.31  5003.3  185.31  5014.9  191.27
    5025  194.12  5052.3  193.27  5130.5  196.52  5379.6   212.7  5451.4   211.1
    5493  208.34  5529.7  207.94  5542.6  206.16  5564.8  208.47  5648.6  211.04
#Mann= 4 ,-1 , 0
  4254.7     .11       0  4397.6     .17       0  4953.9     .09       0
  5014.9     .17       0
Bank Sta=4953.9,5014.9
XS Rating Curve= 0 ,0
Exp/Cntr=0.3,0.1

Type RM Length L Ch R = 1 ,1500    ,500,500,500
BEGIN DESCRIPTION:
NORTH FORK STEWARTS CREEK 3.0
END DESCRIPTION:
XS GIS Cut Line= 3
      3837667.86      10118811.1      3837453.76     10117987.17
      3836967.83     10117511.05
#Sta/Elev= 30
  4148.7  212.72  4159.9  212.79    4314  211.98  4409.7  210.03  4520.7  204.96
  4551.7  202.52  4688.3   197.7  4764.3  193.79  4861.6  191.97  4880.7  188.33
  4885.9  188.43  4892.6  191.09    4934  192.32  4954.6   195.1    4967  192.05
  4975.3  188.48  4983.9  180.02  4995.4  180.56    5000  183.45  5008.4  191.47
  5015.6  192.95    5065  194.46  5142.8  195.17  5312.6  193.06  5496.5  201.15
  5510.6  202.84  5517.6  205.63  5524.8  206.77  5595.5  206.11  5680.3  210.62
#Mann= 5 ,-1 , 0
  4148.7     .11       0  4159.9     .17       0    4967     .09       0
  5008.4     .17       0  5142.8     .11       0
#XS Ineff= 2 , 0
       0  4954.6   195.1               0
Permanent Ineff=
       F       F
Bank Sta=4967,5008.4
XS Rating Curve= 0 ,0
Exp/Cntr=0.3,0.1

Type RM Length L Ch R = 1 ,1000    ,500,500,500
BEGIN DESCRIPTION:
NORTH FORK STEWARTS CREEK 2.0
END DESCRIPTION:
XS GIS Cut Line= 3
      3837997.19     10118323.96      3837671.95     10117541.24
       3837122.5      10117352.7
#Sta/Elev= 30
  4152.4  206.26  4263.2  206.63  4345.6  204.16  4587.5  201.76  4635.1  200.48
  4751.1  193.39  4841.8  190.56  4883.6  189.75  4943.1  189.29  4956.9   188.3
  4966.9  185.82  4972.4  181.05  4987.6  177.41  4996.2  178.86  4998.8  183.16
  5004.8  183.16  5012.8  186.69  5106.6  188.92  5174.4  188.75  5205.6   186.8
  5257.6  191.59  5288.9   196.5  5325.4   197.3  5356.7  200.47  5406.1  200.92
  5419.2  203.68  5445.2   206.3  5490.7  208.45    5533  213.95  5580.9  216.38
#Mann= 6 ,-1 , 0
  4152.4     .11       0  4587.5     .17       0  4841.8     .15       0
  4883.6     .11       0  4966.9     .09       0  5012.8     .11       0
Bank Sta=4966.9,5012.8
XS Rating Curve= 0 ,0
Exp/Cntr=0.3,0.1

Type RM Length L Ch R = 1 ,500     ,0,0,0
BEGIN DESCRIPTION:
NORTH FORK STEWARTS CREEK 1.0
END DESCRIPTION:
XS GIS Cut Line= 3
      3838067.85     10118011.06      3838005.64     10117200.34
      3837301.02     10116970.35
#Sta/Elev= 30
  4186.9  204.92  4327.3  202.47  4477.7  203.63  4598.1  202.92  4708.4  198.03
  4909.9  185.07  4959.1  183.69  4969.2  181.06  4989.2     180  4995.4  176.21
  4998.9  176.21  5008.2  179.75  5018.9  184.13  5039.7  182.66  5045.5     185
  5060.8  184.97  5092.3  188.28  5210.2  193.52  5250.1  193.86  5268.7  195.25
  5332.5  195.36  5376.4  197.34  5396.3  196.37  5407.9  197.62  5428.2  196.56
  5433.5  198.05    5471  200.77    5492  200.02  5598.2  203.49  5741.2  205.56
#Mann= 3 , 0 , 0
  4186.9     .11       0  4989.2     .09       0  5008.2     .11       0
#XS Ineff= 2 , 0
       0                  5018.9       0  184.13
Permanent Ineff=
       F       F
Bank Sta=4989.2,5008.2
XS Rating Curve= 0 ,0
Exp/Cntr=0.3,0.1

Chan Stop Cuts=-1
Use User Specified Reach Order=0
Composite Channel Slope=5

--- NORTH FORK STEWARTS CREEK.g10 (geometry) ---

Geom Title=Existing Conditions
Program Version=4.10

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
River Reach=NORTH FORK STEWA,Reach-1

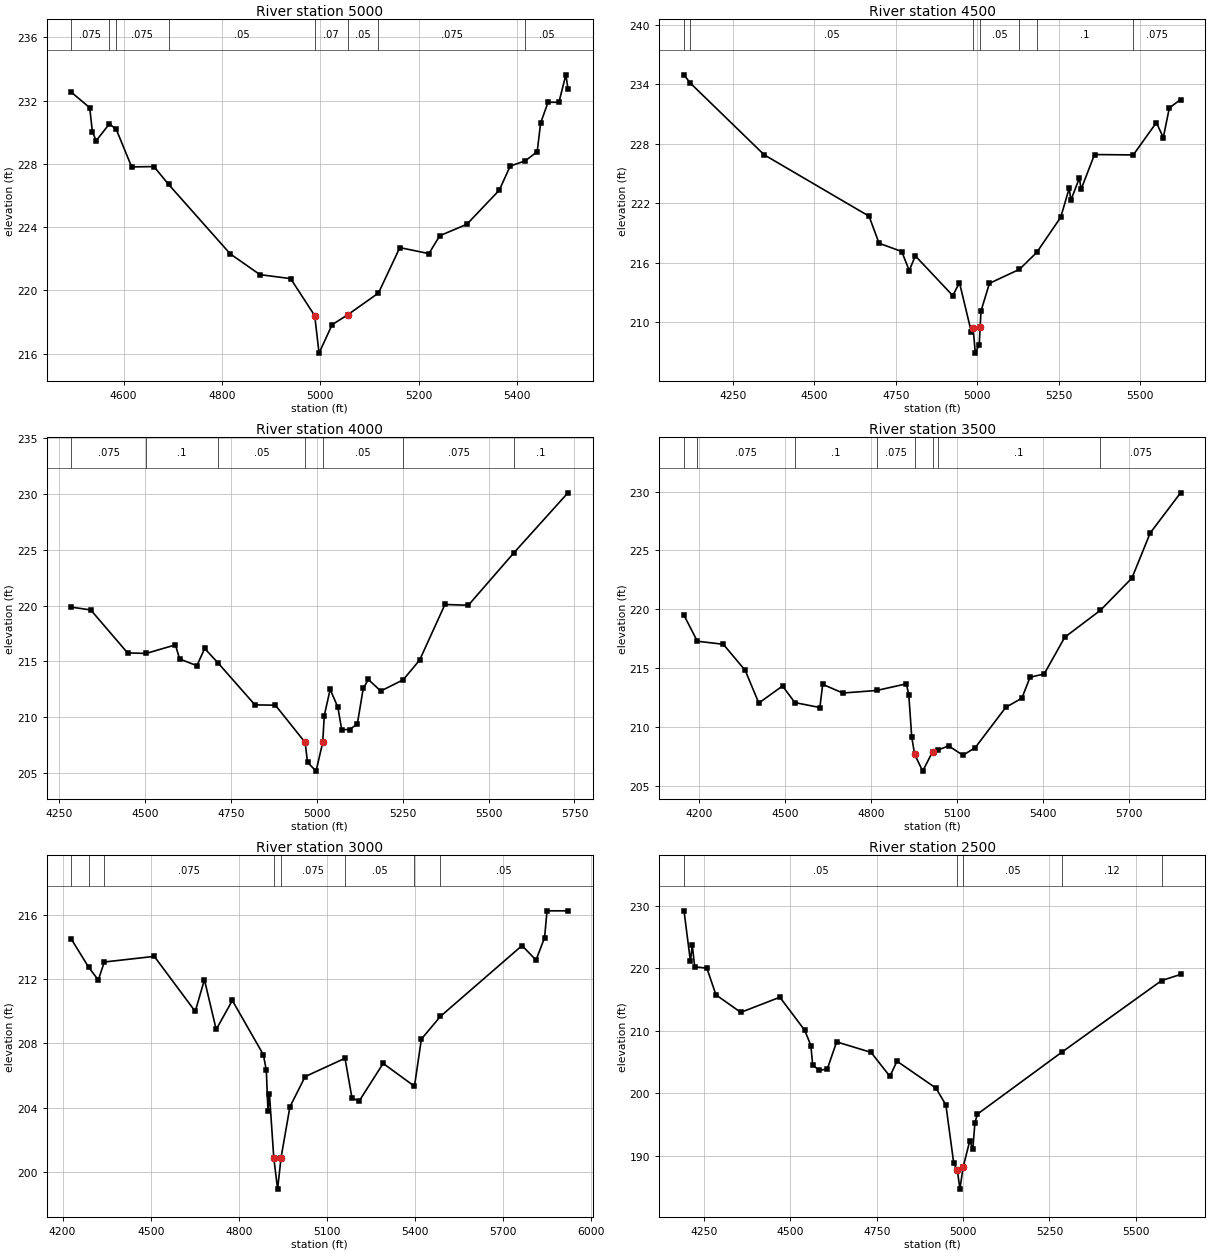
Type RM Length L Ch R = 1 ,5000    ,500,500,500
BEGIN DESCRIPTION:
NORTH FORK STEWARTS CREEK 10.0
END DESCRIPTION:
XS GIS Cut Line= 3
      3835117.08     10120288.24       3834938.3     10119814.56
      3834481.15     10119603.31
#Sta/Elev= 30
  4493.7  232.53    4531  231.55  4536.4  230.04  4544.1  229.46    4571  230.53
  4584.9  230.19  4616.3  227.81  4661.7  227.83  4691.5   226.7  4816.9  222.31
  4877.3     221  4939.6  220.75 4988.61 218.408  4997.4  216.04  5024.1  217.84
  5055.6  218.46  5118.3  219.84  5161.7  222.71  5220.8  222.33  5242.9  223.46
  5297.9  224.18    5364  226.34  5386.1  227.86  5417.1   228.2  5441.1  228.77
    5448  230.58  5463.2   231.9  5485.2  231.89  5499.4  233.63  5503.6  232.76
#Mann= 8 ,-1 , 0
  4493.7    .075       0    4571      .1       0  4584.9    .075       0
  4691.5     .05       0 4988.61     .07       0  5055.6     .05       0
  5118.3    .075       0  5417.1     .05       0
Bank Sta=4988.61,5055.6
XS Rating Curve= 0 ,0
Exp/Cntr=0.3,0.1

Type RM Length L Ch R = 1 ,4500    ,500,500,500
BEGIN DESCRIPTION:
NORTH FORK STEWARTS CREEK 9.0
END DESCRIPTION:
XS GIS Cut Line= 3
      3835411.25     10120313.51      3835198.79     10119438.13
      3834607.57     10119235.75
#Sta/Elev= 30
  4099.2  234.96  4118.4  234.13  4345.2   226.9  4667.7   220.7  4698.5  217.97
  4768.1  217.14  4791.2  215.22  4809.9   216.7  4924.9  212.69  4945.5     214
  4982.2  208.99  4987.3  209.45  4994.2  206.89  5006.3  207.76 5009.08 209.528
  5011.6  211.13  5037.6  213.93  5129.7  215.34    5183  217.05  5256.7   220.6
  5282.7  223.52  5287.9  222.32    5314  224.55  5319.2  223.41  5360.4  226.92
  5479.5  226.88  5550.6  230.14  5571.8  228.63  5590.3  231.62  5624.9  232.47
#Mann= 7 ,-1 , 0
  4099.2    .075       0  4118.4     .05       0  4987.3     .07       0
 5009.08     .05       0  5129.7    .075       0    5183      .1       0
  5479.5    .075       0
Bank Sta=4987.3,5009.08
XS Rating Curve= 0 ,0
Exp/Cntr=0.3,0.1

Type RM Length L Ch R = 1 ,4000    ,500,500,500
BEGIN DESCRIPTION:
NORTH FORK STEWARTS CREEK 8.0
END DESCRIPTION:
XS GIS Cut Line= 3
       3835757.6     10119792.67      3835563.11     10119104.94
       3834903.4     10118790.07
#Sta/Elev= 30
  4285.3  219.87  4341.8  219.62  4448.9  215.77  4502.8  215.72  4588.3  216.49
  4600.3  215.23  4650.7  214.62  4673.4  216.17  4713.1  214.84  4819.7  211.11
  4879.3  211.08  4965.9  207.74  4972.8  205.96  4997.7  205.17 5017.15 207.757
  5021.5  210.13  5038.7   212.5  5061.2   210.9  5072.4  208.88  5095.1   208.9
  5117.8  209.39    5135  212.58  5149.9  213.39  5185.9  212.35  5251.5  213.36
  5299.3  215.13  5372.9  220.11    5441  220.04  5573.6  224.74    5731  230.12
#Mann= 7 ,-1 , 0
  4285.3    .075       0  4502.8      .1       0  4713.1     .05       0
  4965.9     .07       0 5017.15     .05       0  5251.5    .075       0
  5573.6      .1       0
Bank Sta=4965.9,5017.15
XS Rating Curve= 0 ,0
Exp/Cntr=0.3,0.1

Type RM Length L Ch R = 1 ,3500    ,500,500,500
BEGIN DESCRIPTION:
NORTH FORK STEWARTS CREEK 7.0
END DESCRIPTION:
XS GIS Cut Line= 3
      3836093.54      10119894.3      3836026.57     10119043.53
      3835467.85     10118361.07
#Sta/Elev= 30
  4146.6  219.49  4193.1  217.29    4284  217.03  4360.5  214.81    4408  212.04
  4490.9  213.49  4533.9  212.08  4621.3  211.66  4631.3  213.63  4701.5  212.89
  4820.2  213.11  4923.6  213.67  4932.2  212.73  4942.3  209.19  4952.3   207.7
  4980.7  206.26  5015.6  207.92  5033.6  208.05  5071.6   208.4  5121.2  207.61
  5164.2  208.25  5271.2  211.68  5327.2  212.45  5355.9  214.23  5405.4  214.51
  5477.2  217.63  5601.5  219.91  5711.9  222.65  5775.8  226.48    5882  229.89
#Mann= 8 ,-1 , 0
  4146.6     .05       0  4193.1    .075       0  4533.9      .1       0
  4820.2    .075       0  4952.3     .07       0  5015.6    .075       0
  5033.6      .1       0  5601.5    .075       0
Bank Sta=4952.3,5015.6
XS Rating Curve= 0 ,0
Exp/Cntr=0.3,0.1

Type RM Length L Ch R = 1 ,3000    ,500,500,500
BEGIN DESCRIPTION:
NORTH FORK STEWARTS CREEK 6.0
END DESCRIPTION:
XS GIS Cut Line= 3
      3836547.66     10119892.47      3836484.65     10119124.95
      3836131.35     10118275.27
#Sta/Elev= 30
  4229.9  214.47  4288.6  212.73  4321.6  211.93  4341.9  213.05  4512.2   213.4
  4651.5  209.98  4682.8  211.95  4722.9  208.86  4777.8  210.66  4883.5  207.29
  4893.5  206.32  4899.1   203.8  4904.1  204.85 4918.83 200.896  4931.9  198.94
  4943.7   200.9  4973.8  204.05  5025.6  205.93  5161.3  207.07  5184.9  204.62
  5208.8  204.39  5291.2  206.75  5397.8  205.33  5421.3  208.26  5486.1  209.67
  5763.9  214.07  5811.6  213.17  5840.8  214.57  5848.9  216.23  5920.2  216.23
#Mann= 8 ,-1 , 0
  4229.9    .075       0  4288.6     .05       0  4341.9    .075       0
 4918.83     .07       0  4943.7    .075       0  5161.3     .05       0
  5397.8    .075       0  5486.1     .05       0
Bank Sta=4918.83,4943.7
XS Rating Curve= 0 ,0
Exp/Cntr=0.3,0.1

Type RM Length L Ch R = 1 ,2500    ,500,500,500
BEGIN DESCRIPTION:
NORTH FORK STEWARTS CREEK 5.0
END DESCRIPTION:
XS GIS Cut Line= 3
      3836967.86     10119511.11      3836782.12     10118724.85
      3836417.86     10118211.08
#Sta/Elev= 30
  4192.1  229.18  4210.7  221.08  4215.9  223.73    4223  220.23  4258.2  220.01
  4284.6  215.74  4356.5  212.94  4469.6  215.36  4541.5  210.08  4559.4  207.64
  4564.5  204.57  4582.6  203.67  4606.8  203.87    4634  208.22  4733.7  206.54
  4788.1  202.71  4808.7  205.13  4921.7  200.82  4950.3  198.12  4973.1  188.77
  4983.3  187.74  4990.9  184.67    5000  188.14  5019.5  192.41  5028.2  191.01
  5034.3  195.28  5041.4  196.66  5285.9  206.57  5574.7  218.02  5629.8  219.01
#Mann= 5 ,-1 , 0
  4192.1     .05       0  4983.3     .07       0    5000     .05       0
  5285.9     .12       0  5574.7     .05       0
Bank Sta=4983.3,5000
XS Rating Curve= 0 ,0
Exp/Cntr=0.3,0.1

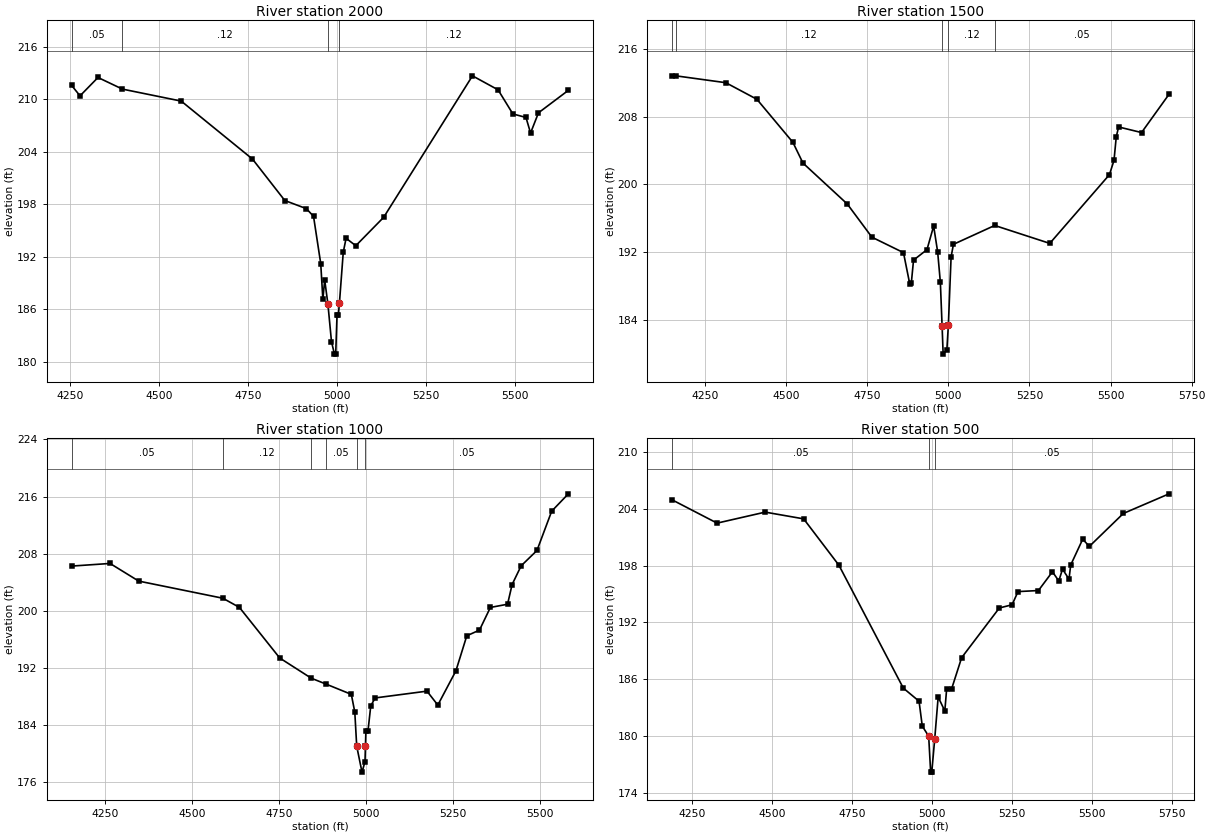
Type RM Length L Ch R = 1 ,2000    ,500,500,500
BEGIN DESCRIPTION:
NORTH FORK STEWARTS CREEK 4.0
END DESCRIPTION:
XS GIS Cut Line= 3
      3837210.73     10119094.82      3837117.99     10118355.31
      3836615.77     10117944.88
#Sta/Elev= 30
  4254.7  211.62  4278.6  210.41    4329  212.51  4397.6  211.18  4562.5  209.81
  4762.4  203.18  4853.1  198.44  4913.6  197.51  4933.7  196.63  4953.9  191.23
  4959.9  187.13    4965  189.35    4974  186.61  4984.1  182.29  4992.4  180.87
  4995.9  180.87  4999.6  185.31  5003.3  185.31 5006.44 186.764  5017.1  192.52
    5025  194.12  5052.3  193.27  5130.5  196.52  5379.6   212.7  5451.4   211.1
    5493  208.34  5529.7  207.94  5542.6  206.16  5564.8  208.47  5648.6  211.04
#Mann= 4 ,-1 , 0
  4254.7     .05       0  4397.6     .12       0    4974     .07       0
 5006.44     .12       0
Bank Sta=4974,5006.44
XS Rating Curve= 0 ,0
Exp/Cntr=0.3,0.1

Type RM Length L Ch R = 1 ,1500    ,500,500,500
BEGIN DESCRIPTION:
NORTH FORK STEWARTS CREEK 3.0
END DESCRIPTION:
XS GIS Cut Line= 3
      3837667.86      10118811.1      3837453.76     10117987.17
      3836967.83     10117511.05
#Sta/Elev= 30
  4148.7  212.72  4159.9  212.79    4314  211.98  4409.7  210.03  4520.7  204.96
  4551.7  202.52  4688.3   197.7  4764.3  193.79  4861.6  191.97  4880.7  188.33
  4885.9  188.43  4892.6  191.09    4934  192.32  4954.6   195.1    4967  192.05
  4975.3  188.48 4980.63 183.368  4983.9  180.02  4995.4  180.56    5000  183.45
  5008.4  191.47  5015.6  192.95  5142.8  195.17  5312.6  193.06  5496.5  201.15
  5510.6  202.84  5517.6  205.63  5524.8  206.77  5595.5  206.11  5680.3  210.62
#Mann= 5 ,-1 , 0
  4148.7     .05       0  4159.9     .12       0 4980.63     .07       0
    5000     .12       0  5142.8     .05       0
Bank Sta=4980.63,5000
XS Rating Curve= 0 ,0
Exp/Cntr=0.3,0.1

Type RM Length L Ch R = 1 ,1000    ,500,500,500
BEGIN DESCRIPTION:
NORTH FORK STEWARTS CREEK 2.0
END DESCRIPTION:
XS GIS Cut Line= 3
      3837997.19     10118323.96      3837671.95     10117541.24
       3837122.5      10117352.7
#Sta/Elev= 30
  4152.4  206.26  4263.2  206.63  4345.6  204.16  4587.5  201.76  4635.1  200.48
  4751.1  193.39  4841.8  190.56  4883.6  189.75  4956.9   188.3  4966.9  185.82
  4972.4  181.05  4987.6  177.41  4996.2  178.86 4997.54 181.076  4998.8  183.16
  5004.8  183.16  5012.8  186.69  5025.5   187.8  5174.4  188.75  5205.6   186.8
  5257.6  191.59  5288.9   196.5  5325.4   197.3  5356.7  200.47  5406.1  200.92
  5419.2  203.68  5445.2   206.3  5490.7  208.45    5533  213.95  5580.9  216.38
#Mann= 6 ,-1 , 0
  4152.4     .05       0  4587.5     .12       0  4841.8      .1       0
  4883.6     .05       0  4972.4     .07       0 4997.54     .05       0
Bank Sta=4972.4,4997.54
XS Rating Curve= 0 ,0
Exp/Cntr=0.3,0.1

Type RM Length L Ch R = 1 ,500     ,0,0,0
BEGIN DESCRIPTION:
NORTH FORK STEWARTS CREEK 1.0
END DESCRIPTION:
XS GIS Cut Line= 3
      3838067.85     10118011.06      3838005.64     10117200.34
      3837301.02     10116970.35
#Sta/Elev= 30
  4186.9  204.92  4327.3  202.47  4477.7  203.63  4598.1  202.92  4708.4  198.03
  4909.9  185.07  4959.1  183.69  4969.2  181.06  4989.2     180  4995.4  176.21
  4998.9  176.21  5008.2  179.75  5018.9  184.13  5039.7  182.66  5045.5     185
  5060.8  184.97  5092.3  188.28  5210.2  193.52  5250.1  193.86  5268.7  195.25
  5332.5  195.36  5376.4  197.34  5396.3  196.37  5407.9  197.62  5428.2  196.56
  5433.5  198.05    5471  200.77    5492  200.02  5598.2  203.49  5741.2  205.56
#Mann= 3 , 0 , 0
  4186.9     .05       0  4989.2     .07       0  5008.2     .05       0
Bank Sta=4989.2,5008.2
XS Rating Curve= 0 ,0
Exp/Cntr=0.3,0.1