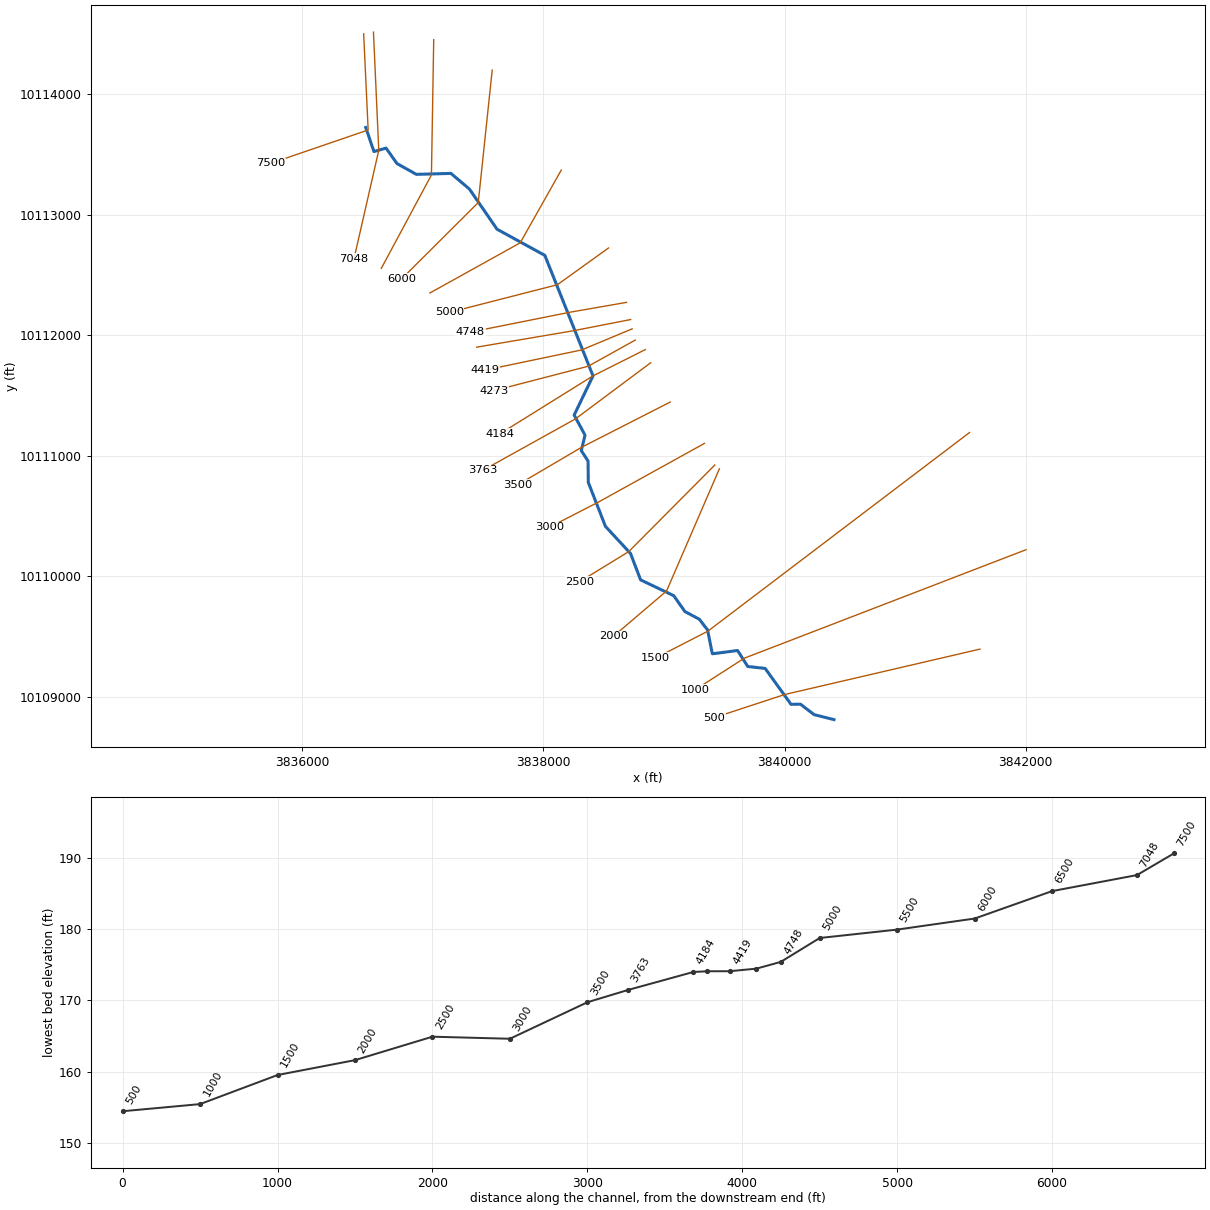
--- POSSUM BRANCH.prj (project) ---

Proj Title=POSSUM BRANCH Base Level Engineering
Current Plan=p01
Default Exp/Contr=0.3,0.1
English Units
Geom File=g01
Flow File=f01
Flow File=f02
Plan File=p01
Y Axis Title=Elevation
X Axis Title(PF)=Main Channel Distance
X Axis Title(XS)=Station
BEGIN DESCRIPTION:
POSSUM BRANCH
END DESCRIPTION:
DSS File=dss
DSS Export Rating Curves= 0
DSS Export Rating Curve Sorted= 0
DSS Export Volume Flow Curves= 0
DXF OffsetX= 0
DXF OffsetY= 0
DXF ScaleX= 1
DXF ScaleY= 10

--- POSSUM BRANCH.p01 (plan) ---

Plan Title=Multiple Run
Program Version=4.10
Short Identifier=1
Geom File=g01
Flow File=f01
Subcritical Flow
K Sum by GR= 0
Std Step Tol= 0.01
Critical Tol= 0.01
Num of Std Step Trials= 20
Max Error Tol= 0.3
Flow Tol Ratio= 0.001
Split Flow NTrial= 30
Split Flow Tol= 0.02
Split Flow Ratio= 0.02
Log Output Level= 0
Friction Slope Method= 1
Unsteady Friction Slope Method= 2
Unsteady Bridges Friction Slope Method= 1
Parabolic Critical Depth
Global Vel Dist= 1 , 1 , 1
Global Log Level= 0
CheckData=True
Encroach Param=-1 ,0,0, 0
BEGIN DESCRIPTION:
Multiple Run
END DESCRIPTION:
Computation Interval=1HOUR
Output Interval=1HOUR
Run HTab= 0
Run UNet= 0
Run PostProcess= 0
Run WQNet= 0
UNET Theta= 1
UNET Theta Warmup= 1
UNET ZTol= 0.02
UNET ZSATol= 0.05
UNET MxIter= 20
UNET MaxInSteps= 0
UNET DtIC= 0
UNET DtMin= 0
UNET MaxCRTS= 20
UNET WFStab= 2
UNET SFStab= 1
UNET WFX= 1
UNET SFX= 1
UNET DSS MLevel= 4
UNET DZMax Abort= 100
UNET Convert EG Bridges= 0
UNET Use Existing IB Tables=-1
UNET Froude Reduction=False
UNET Froude Limit= 1
UNET Froude Power= 10
UNET Time Slicing=0,0, 5
UNET Junction Losses=0
Instantaneous Interval=1HOUR
DSS File=dss
Write IC File= 0
Write IC File at Sim End=0
Echo Input=False
Echo Parameters=False
Echo Output=False
Write Detailed= 0
WQ AD Non Conservative
WQ ULTIMATE=-1
WQ Max Comp Step=1HOUR
WQ Output Interval=15MIN
WQ Output Selected Increments= 0
WQ Output face flow=0
WQ Output face velocity=0
WQ Output face area=0
WQ Output face dispersion=0
WQ Output cell volume=0
WQ Output cell surface area=0
WQ Output cell continuity=0
WQ Output cumulative cell continuity=0
WQ Output face conc=0
WQ Output face dconc_dx=0
WQ Output face courant=0
WQ Output face peclet=0
WQ Output face adv mass=0
WQ Output face disp mass=0
WQ Output cell mass=0
WQ Output cell source sink temp=0
WQ Output cell source sink nsm=0
WQ Output MaxMinRange=-1
WQ Daily Max Min Mean=-1
WQ Daily Range=0
WQ Daily Time=0
WQ Create Restart=0
WQ Fixed Restart=0
WQ System Summary=0
WQ Use Fixed Temperature=0
Sorting and Armoring Iterations= 10
XS Update Threshold= 0.02
Hydraulics Update Threshold= 0.02
Energy Slope Method= 1
Volume Change Method= 0
XS Weighting Method= 0
Number of US Weighted Cross Sections= 1
Number of DS Weighted Cross Sections= 1
Upstream XS Weight=0.25
Main XS Weight=0.5
Downstream XS Weight=0.25
Number of DS XS's Weighted with US Boundary= 1
Upstream Boundary Weight= 1
Weight of XSs Associated with US Boundary= 0
Number of US XS's Weighted with DS Boundary= 1
Downstream Boundary Weight= 0.5
Weight of XSs Associated with DS Boundary= 0.5
Sediment Output Level= 4
Mass or Volume Output= 0
Output Increment Type= 1
Profile and TS Output Increment= 10
XS Output Flag= 0
XS Output Increment= 10
Disregard all LS=0
Disregard all Conn=0
Disregard all Breaches=0
Disregard all Pumps=0

--- POSSUM BRANCH.f01 (steady flow) ---

Flow Title=Multiple
Program Version=4.10
Number of Profiles= 7
Profile Names=10-year,25-year,50-year,1pct_min,100-year,1pct_plu,500-year
River Rch & RM=POSSUM BRANCH,Reach-1         ,7500
     583     772    1028     450    1359    4104    2451
River Rch & RM=POSSUM BRANCH,Reach-1         ,7048
     583     772    1028     450    1359    4104    2451
River Rch & RM=POSSUM BRANCH,Reach-1         ,1500
    3857    5521    7738    3542   10696   32301   21149
River Rch & RM=POSSUM BRANCH,Reach-1         ,1000
    3857    5521    7738    3542   10696   32301   21149
River Rch & RM=POSSUM BRANCH,Reach-1         ,500
    3857    5521    7738    3542   10696   32301   21149
Boundary for River Rch & Prof#=POSSUM BRANCH,Reach-1         , 1
Up Type= 0
Dn Type= 3
Dn Slope=0.01
Boundary for River Rch & Prof#=POSSUM BRANCH,Reach-1         , 2
Up Type= 0
Dn Type= 3
Dn Slope=0.01
Boundary for River Rch & Prof#=POSSUM BRANCH,Reach-1         , 3
Up Type= 0
Dn Type= 3
Dn Slope=0.01
Boundary for River Rch & Prof#=POSSUM BRANCH,Reach-1         , 4
Up Type= 0
Dn Type= 3
Dn Slope=0.01
Boundary for River Rch & Prof#=POSSUM BRANCH,Reach-1         , 5
Up Type= 0
Dn Type= 3
Dn Slope=0.01
Boundary for River Rch & Prof#=POSSUM BRANCH,Reach-1         , 6
Up Type= 0
Dn Type= 3
Dn Slope=0.01
Boundary for River Rch & Prof#=POSSUM BRANCH,Reach-1         , 7
Up Type= 0
Dn Type= 3
Dn Slope=0.01
DSS Import GetInterval= 0
DSS Import GetPeak= 0
DSS Import FillOption= 0

--- POSSUM BRANCH.f02 (steady flow) ---

Flow Title=Flow 02
Program Version=4.10
Number of Profiles= 1
Profile Names=PF 1
DSS Import GetInterval= 0
DSS Import GetPeak= 0
DSS Import FillOption= 0

--- POSSUM BRANCH.g01 (geometry) ---

Geom Title=Existing Conditions
Program Version=4.10

River Reach=POSSUM BRANCH   ,Reach-1
Reach XY= 30
      3836525.11     10113724.35      3836593.31     10113524.52
      3836693.66     10113553.34      3836784.63     10113424.87
      3836945.32     10113335.49      3837232.01      10113343.5
      3837384.99     10113213.92      3837614.56     10112880.32
      3838010.92     10112663.31      3838410.64     10111663.56
      3838254.39     10111338.33      3838344.66     10111171.66
      3838313.41     10111043.88      3838369.66     10110957.08
      3838371.75      10110779.3      3838514.11     10110414.72
      3838721.69     10110190.48      3838805.74     10109970.94
      3839080.78     10109839.71      3839173.14     10109708.46
      3839292.58     10109644.58      3839361.33     10109555.69
      3839400.82     10109357.86      3839609.94     10109384.85
      3839695.36     10109252.22      3839839.11     10109236.24
      3840053.69     10108938.34      3840131.69     10108939.78
      3840245.59     10108852.76       3840409.5     10108811.92

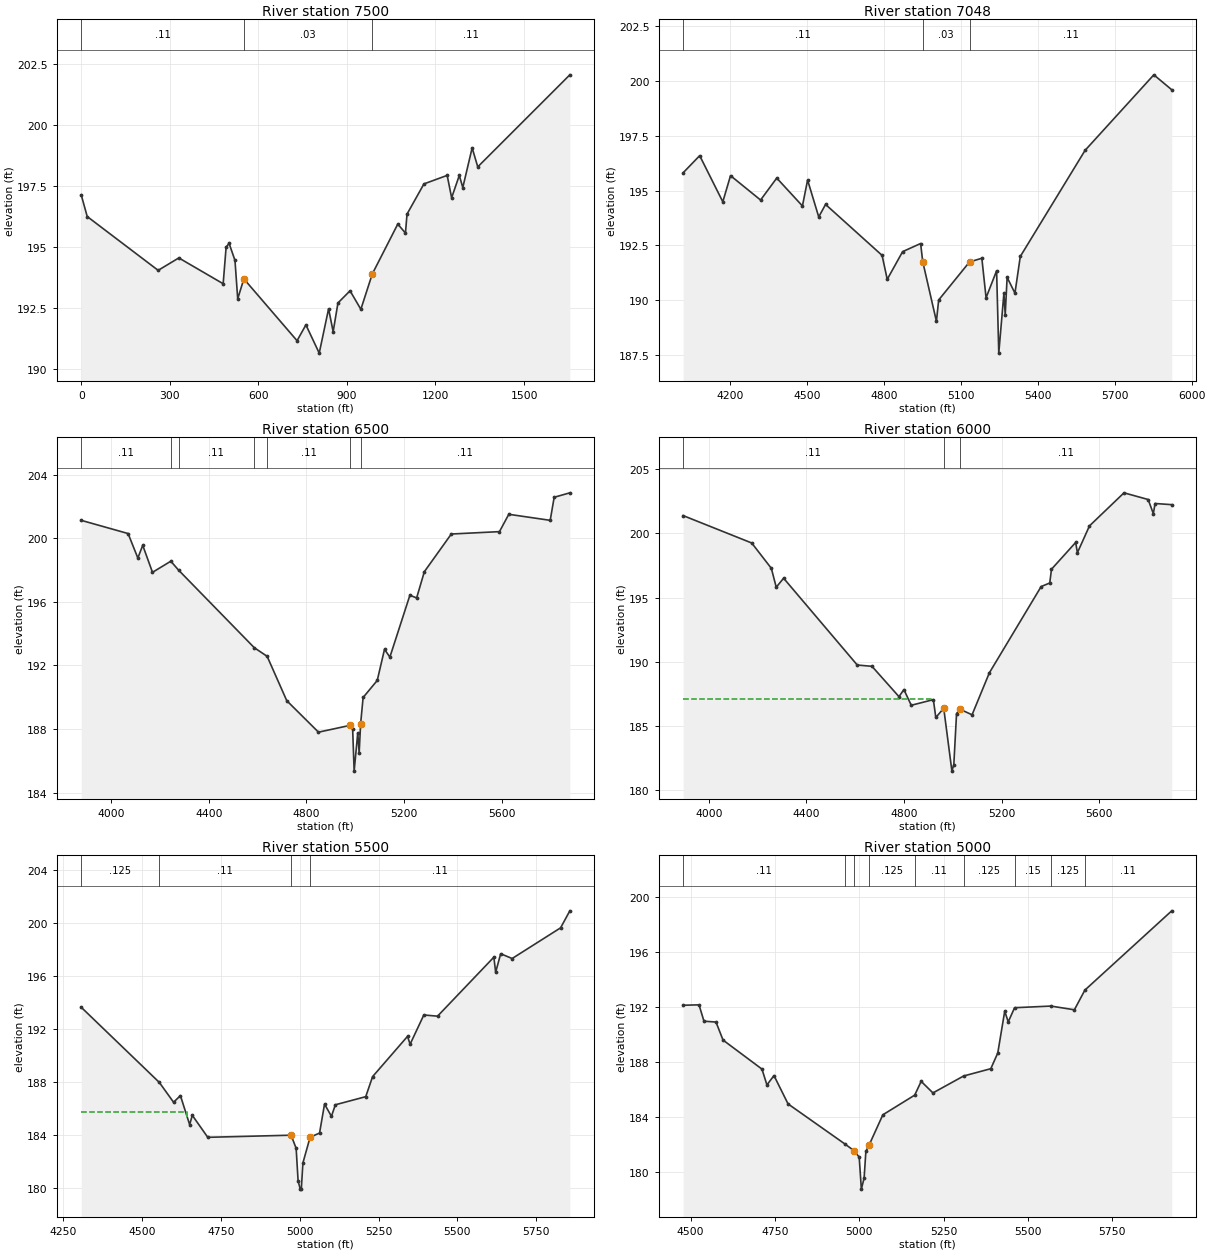
Type RM Length L Ch R = 1 ,7500    ,238,238,238
XS GIS Cut Line= 3
      3836507.92     10114501.35      3836545.17     10113703.75
      3835734.48     10113425.83
#Sta/Elev= 30
       0  197.14    20.3  196.25   260.6  194.04   330.6  194.55   480.8  193.49
   490.8  194.99   500.8  195.15   520.8  194.45   530.1  192.87   550.9  193.69
   731.1  191.15   761.1   191.8   806.2  190.64   837.9  192.46   853.4  191.52
   869.6   192.7   910.6   193.2   947.2  192.44   985.9  193.89  1072.3  195.94
  1098.3  195.57  1103.6  196.35  1160.9  197.59  1239.6  197.94  1254.7  197.02
  1280.7  197.94  1292.5  197.44  1324.2  199.07  1343.2  198.29  1655.1  202.07
#Mann= 3 , 0 , 0
       0     .11       0   550.9     .03       0   985.9     .11       0
Bank Sta=550.9,985.9
XS Rating Curve= 0 ,0
Exp/Cntr=0.3,0.1

Type RM Length L Ch R = 1 ,7048    ,548,548,548
BEGIN DESCRIPTION:
POSSUM BRANCH 14.0
END DESCRIPTION:
XS GIS Cut Line= 3
      3836589.23     10114515.55      3836633.25     10113534.94
      3836427.86      10112635.7
#Sta/Elev= 30
  4018.4  195.81  4082.9  196.59    4173  194.49  4203.1  195.68  4320.2  194.57
  4383.2  195.57  4483.3   194.3  4503.4  195.48  4546.8   193.8  4573.4  194.37
  4793.7  192.05  4813.7  190.96  4873.7  192.22  4943.8  192.59 4951.98  191.77
  5005.4  189.05  5014.2  190.02  5134.3  191.75  5182.4  191.92  5198.9  190.12
  5239.9  191.35  5248.4   187.6  5268.4  190.33  5273.5  189.35  5280.9  191.05
  5311.4  190.33  5332.2     192  5584.6  196.83  5852.6  200.27  5922.4  199.59
#Mann= 3 , 0 , 0
  4018.4     .11       0 4951.98     .03       0  5134.3     .11       0
#XS Ineff= 3 ,-1
  5332.2  5359.5     192  5359.5  5373.2  192.41  4943.8  4673.5  192.59
Permanent Ineff=
       F       F       F
Bank Sta=4951.98,5134.3
XS Rating Curve= 0 ,0
Exp/Cntr=0.3,0.1

Type RM Length L Ch R = 1 ,6500    ,500,500,500
BEGIN DESCRIPTION:
POSSUM BRANCH 13.0
END DESCRIPTION:
XS GIS Cut Line= 3
      3837089.23     10114453.03       3837070.2     10113330.39
      3836654.51     10112555.78
#Sta/Elev= 30
  3877.2  201.12  4069.2  200.29  4109.2  198.75  4129.2  199.55  4169.2  197.85
  4244.2  198.55    4276  197.99  4586.3  193.11  4638.9  192.57  4719.3  189.78
  4849.3   187.8  4979.3  188.23  4989.3  187.99  4995.4  185.35  5010.2  187.76
  5015.9  186.49  5021.9  188.32  5032.1  189.98    5090  191.05  5119.8  193.01
  5141.8  192.52  5223.8  196.41  5251.4  196.24    5283  197.89  5393.5  200.26
  5590.8  200.41    5629   201.5  5798.7  201.12  5814.9  202.57  5879.1  202.85
#Mann= 7 ,-1 , 0
  3877.2     .11       0  4244.2    .125       0    4276     .11       0
  4586.3    .125       0  4638.9     .11       0  4979.3     .03       0
  5021.9     .11       0
Bank Sta=4979.3,5021.9
XS Rating Curve= 0 ,0
Exp/Cntr=0.3,0.1

Type RM Length L Ch R = 1 ,6000    ,500,500,500
BEGIN DESCRIPTION:
POSSUM BRANCH 12.0
END DESCRIPTION:
XS GIS Cut Line= 3
      3837574.47     10114200.41      3837458.63      10113101.5
      3836823.63     10112468.67
#Sta/Elev= 30
    3895  201.37  4175.9  199.24  4256.3  197.27  4276.4   195.8  4306.6   196.5
  4608.3  189.75  4668.6  189.65  4779.2  187.29  4799.3  187.84  4829.5  186.62
    4920  187.06    4930  185.67  4962.5  186.39    4996   181.5  5003.8     182
    5015  185.98  5029.2  186.31  5078.6  185.88  5149.3  189.14  5361.5  195.85
  5396.8  196.13  5403.9   197.2  5502.9  199.28    5510  198.48  5559.5  200.57
  5700.9  203.14  5799.9  202.62  5821.1  201.52  5828.2  202.31  5896.5  202.22
#Mann= 3 , 0 , 0
    3895     .11       0  4962.5     .03       0  5029.2     .11       0
#XS Ineff= 2 , 0
       0  4909.9  187.12               0
Permanent Ineff=
       F       F
Bank Sta=4962.5,5029.2
XS Rating Curve= 0 ,0
Exp/Cntr=0.3,0.1

Type RM Length L Ch R = 1 ,5500    ,500,500,500
BEGIN DESCRIPTION:
POSSUM BRANCH 11.0
END DESCRIPTION:
XS GIS Cut Line= 3
      3838147.08     10113370.52      3837806.76     10112767.29
      3837057.98     10112351.46
#Sta/Elev= 30
  4307.4  193.64  4555.1  187.98  4600.2  186.49  4621.9  186.99  4651.2   184.8
  4659.5  185.51  4708.6  183.85  4972.8  184.01  4988.8  183.02    4995  180.57
  5001.7  179.95  5005.2  179.95  5010.2  181.92  5033.1  183.86    5063  184.17
  5078.8  186.35  5100.7  185.43  5113.1   186.3  5209.4  186.91  5231.2  188.42
  5341.9  191.45  5350.1  190.86  5393.6  193.06  5437.1  192.97  5615.6  197.41
  5621.3  196.28  5637.3  197.67  5673.6  197.31  5827.2  199.62  5856.5   200.9
#Mann= 4 ,-1 , 0
  4307.4    .125       0  4555.1     .11       0  4972.8     .03       0
  5033.1     .11       0
#XS Ineff= 2 , 0
       0  4643.5  185.75  5078.8       0  186.35
Permanent Ineff=
       F       F
Bank Sta=4972.8,5033.1
XS Rating Curve= 0 ,0
Exp/Cntr=0.3,0.1

Type RM Length L Ch R = 1 ,5000    ,252,252,252
BEGIN DESCRIPTION:
POSSUM BRANCH 10.0
END DESCRIPTION:
XS GIS Cut Line= 3
      3838539.48     10112724.74      3838115.78     10112420.02
      3837218.28       10112190.
#Sta/Elev= 30
  4478.1  192.13  4525.2  192.16  4539.9  190.97  4575.5  190.91  4596.4   189.6
  4711.8  187.49  4726.5  186.34  4747.4  187.02  4789.2  184.96  4956.5  182.07
  4984.3  181.57    5000   181.1  5006.4  178.77  5014.6  179.57  5019.8  181.51
  5028.8  181.94  5070.1  184.17  5164.6   185.6  5183.7   186.6  5218.6  185.76
  5309.6  186.99  5390.1  187.52  5410.8  188.66  5431.4   191.7  5441.8  190.92
  5460.6  191.95  5568.1  192.07  5637.9   191.8    5669  193.23  5926.5  198.99
#Mann= 9 ,-1 , 0
  4478.1     .11       0  4956.5    .125       0  4984.3     .03       0
  5028.8    .125       0  5164.6     .11       0  5309.6    .125       0
  5460.6     .15       0  5568.1    .125       0    5669     .11       0
Bank Sta=4984.3,5028.8
XS Rating Curve= 0 ,0
Exp/Cntr=0.3,0.1

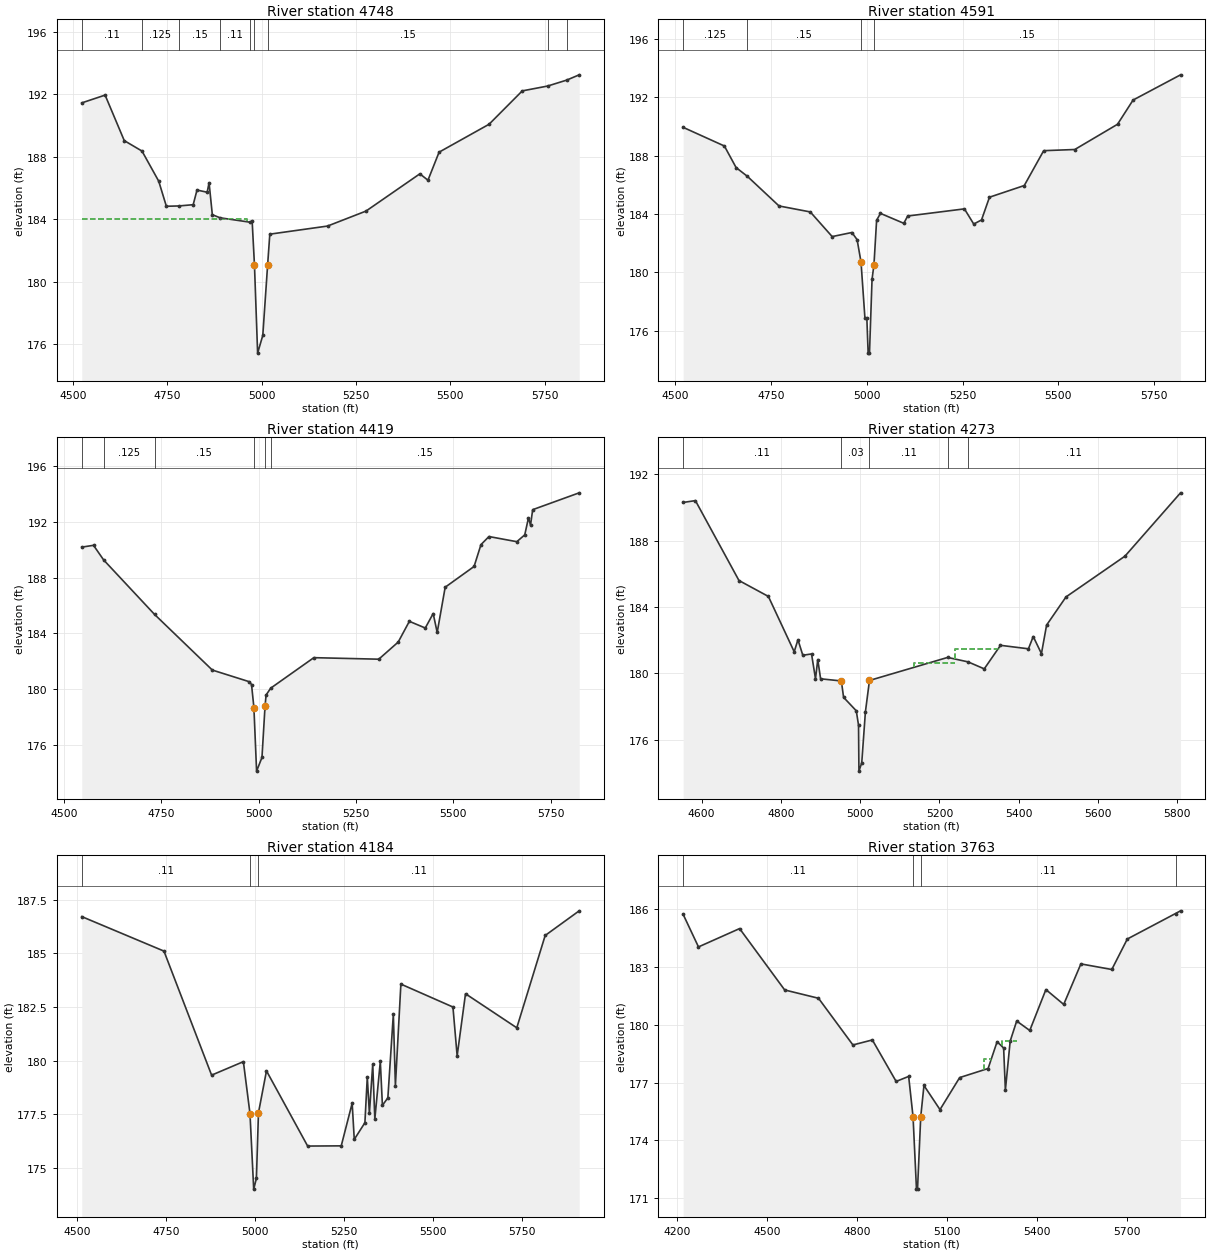
Type RM Length L Ch R = 1 ,4748    ,157,157,157
BEGIN DESCRIPTION:
Mapping XS 3f61720d
END DESCRIPTION:
XS GIS Cut Line= 3
      3838688.76     10112273.33      3838219.22      10112191.6
      3837393.61      10112026.8
#Sta/Elev= 30
  4523.4  191.46  4585.2  191.96    4636  189.04    4683  188.37  4727.3  186.44
  4747.6  184.83  4780.6  184.85  4818.7  184.93  4828.8  185.87  4855.8  185.73
  4860.8  186.34  4869.4  184.29  4889.9  184.09  4968.7  183.81    4975  183.87
  4981.1  181.07  4989.5  175.41  5003.2  176.55 5016.07181.0906  5021.8  183.04
  5174.8  183.56  5276.7  184.52  5419.5  186.91    5441   186.5  5470.5   188.3
    5603  190.09    5691  192.23  5758.1  192.54  5808.6  192.92  5841.9  193.26
#Mann= 9 ,-1 , 0
  4523.4     .11       0    4683    .125       0  4780.6     .15       0
  4889.9     .11       0  4968.7     .15       0  4981.1     .03       0
 5016.07     .15       0  5758.1    .125       0  5808.6     .15       0
#XS Ineff= 2 , 0
       0  4960.8  184.04               0
Permanent Ineff=
       F       F
Bank Sta=4981.1,5016.07
XS Rating Curve= 0 ,0
Exp/Cntr=0.3,0.1

Type RM Length L Ch R = 1 ,4591    ,172,172,172
BEGIN DESCRIPTION:
POSSUM BRANCH 9.0
END DESCRIPTION:
XS GIS Cut Line= 3
      3838723.54     10112130.98      3838252.96      10112038.9
      3837445.72     10111901.81
#Sta/Elev= 30
  4520.5  189.95  4628.2  188.67  4658.8  187.19  4688.2  186.59  4770.8  184.56
  4852.4  184.15  4909.5  182.46    4961  182.74  4974.6  182.25  4984.8  180.72
    4995  176.88    5000  176.88  5003.4  174.47  5006.9  174.47  5013.6  179.54
  5018.6  180.53  5025.5  183.58  5035.6  184.05  5096.5  183.37  5106.6  183.87
  5254.7  184.36    5279  183.32  5299.3   183.6  5320.1  185.16  5410.9  185.96
  5461.6  188.35  5542.8  188.43  5654.3  190.16  5694.9  191.82  5818.8  193.55
#Mann= 4 ,-1 , 0
  4520.5    .125       0  4688.2     .15       0  4984.8     .03       0
  5018.6     .15       0
Bank Sta=4984.8,5018.6
XS Rating Curve= 0 ,0
Exp/Cntr=0.3,0.1

Type RM Length L Ch R = 1 ,4419    ,146,146,146
BEGIN DESCRIPTION:
Mapping XS c79e3b19
END DESCRIPTION:
XS GIS Cut Line= 3
      3838735.64     10112053.71      3838316.89     10111878.84
      3837511.01     10111710.37
#Sta/Elev= 30
  4546.2   190.2  4576.3  190.33  4602.3  189.28  4732.9  185.37  4881.3  181.37
  4976.5  180.53    4982  180.33  4988.1  178.68    4995  174.11  5008.8  175.09
 5016.71178.7779  5019.4  179.58  5031.3  180.07    5142  182.26  5308.7  182.15
  5358.6  183.38  5387.2  184.87  5428.1  184.39  5448.4  185.43  5458.7  184.07
  5479.2  187.32  5553.4  188.81  5571.1  190.38  5591.6  190.96  5663.1  190.59
  5683.5  191.08  5693.1  192.31  5698.3  191.78  5703.9  192.89  5823.3   194.1
#Mann= 6 ,-1 , 0
  4546.2     .11       0  4602.3    .125       0  4732.9     .15       0
  4988.1     .03       0 5016.71     .11       0  5031.3     .15       0
Bank Sta=4988.1,5016.71
XS Rating Curve= 0 ,0
Exp/Cntr=0.3,0.1

Type RM Length L Ch R = 1 ,4273    ,89,89,89
BEGIN DESCRIPTION:
POSSUM BRANCH 8.0
END DESCRIPTION:
XS GIS Cut Line= 3
      3838760.97     10111960.55      3838370.71     10111743.42
      3837588.04     10111540.68
#Sta/Elev= 30
  4553.4  190.31  4584.4  190.42  4694.3   185.6  4768.5  184.64  4833.7   181.3
  4843.1  182.03  4855.4  181.09  4877.4  181.17  4887.4  179.67  4893.1  180.83
  4900.3  179.67  4952.6  179.54  4958.3  178.55  4990.3  177.74    4996  176.87
    4997   174.1  5004.1   174.6  5013.3  177.67  5023.6  179.57  5220.9  180.96
  5272.5  180.69  5313.2  180.27  5354.2  181.69  5424.7  181.48  5436.8  182.22
  5457.5  181.19  5470.5  182.91  5519.5  184.61  5668.3  187.07  5808.5  190.89
#Mann= 5 ,-1 , 0
  4553.4     .11       0  4952.6     .03       0  5023.6     .11       0
  5220.9     .15       0  5272.5     .11       0
#XS Ineff= 3 ,-1
  4893.1  4877.4  180.83  5137.2  5240.5  180.61  5240.5  5354.2  181.44
Permanent Ineff=
       F       F       F
Bank Sta=4952.6,5023.6
XS Rating Curve= 0 ,0
Exp/Cntr=0.3,0.1

Type RM Length L Ch R = 1 ,4184    ,421,421,421
BEGIN DESCRIPTION:
Mapping XS 73a9c07d
END DESCRIPTION:
XS GIS Cut Line= 3
      3838844.98     10111881.82      3838410.64     10111663.56
      3837636.66     10111181.74
#Sta/Elev= 30
  4513.9  186.72  4744.8  185.11  4878.7  179.32    4968  179.95 4986.55177.5271
    4997     174  5004.6   174.5  5010.4177.5632  5032.9  179.52  5148.6  176.01
    5243  176.02  5273.7  178.01  5279.6  176.32  5309.5   177.1  5316.2  179.23
  5322.1  177.54  5331.5  179.83  5337.4  177.27  5352.8  179.96  5358.7  177.91
    5374  178.26  5389.4  182.16  5395.2  178.83  5410.6  183.57  5556.9   182.5
  5568.7  180.22  5592.2  183.12  5736.3  181.53  5816.1  185.84  5911.7  186.99
#Mann= 3 , 0 , 0
  4513.9     .11       0 4986.55     .03       0  5010.4     .11       0
Bank Sta=4986.55,5010.4
XS Rating Curve= 0 ,0
Exp/Cntr=0.3,0.1

Type RM Length L Ch R = 1 ,3763    ,263,263,263
BEGIN DESCRIPTION:
Mapping XS 28265cf5
END DESCRIPTION:
XS GIS Cut Line= 3
      3838888.83     10111772.01       3838264.8     10111306.38
       3837497.8     10110880.11
#Sta/Elev= 30
  4221.4  185.72  4272.5  184.03  4409.4  184.98  4559.5   181.8  4672.1  181.37
  4786.7  178.95  4851.4  179.21  4930.6  177.06  4972.3  177.32  4986.9  175.23
  4998.3  171.48  5001.8  171.48  5012.5175.2346  5023.2  176.85  5076.6   175.6
  5142.1  177.26  5236.8  177.73  5266.8  179.12  5288.5  178.79  5294.3  176.61
  5310.3  179.15    5332  180.19  5375.5   179.7  5429.2  181.82  5488.5  181.05
  5545.7  183.15  5648.6  182.86  5700.3  184.44  5860.8  185.76  5877.5   185.9
#Mann= 4 ,-1 , 0
  4221.4     .11       0  4986.9     .03       0  5012.5     .11       0
  5860.8    .125       0
#XS Ineff= 2 ,-1
  5223.3  5245.1  178.23  5282.5    5332  179.16
Permanent Ineff=
       F       F
Bank Sta=4986.9,5012.5
XS Rating Curve= 0 ,0
Exp/Cntr=0.3,0.1

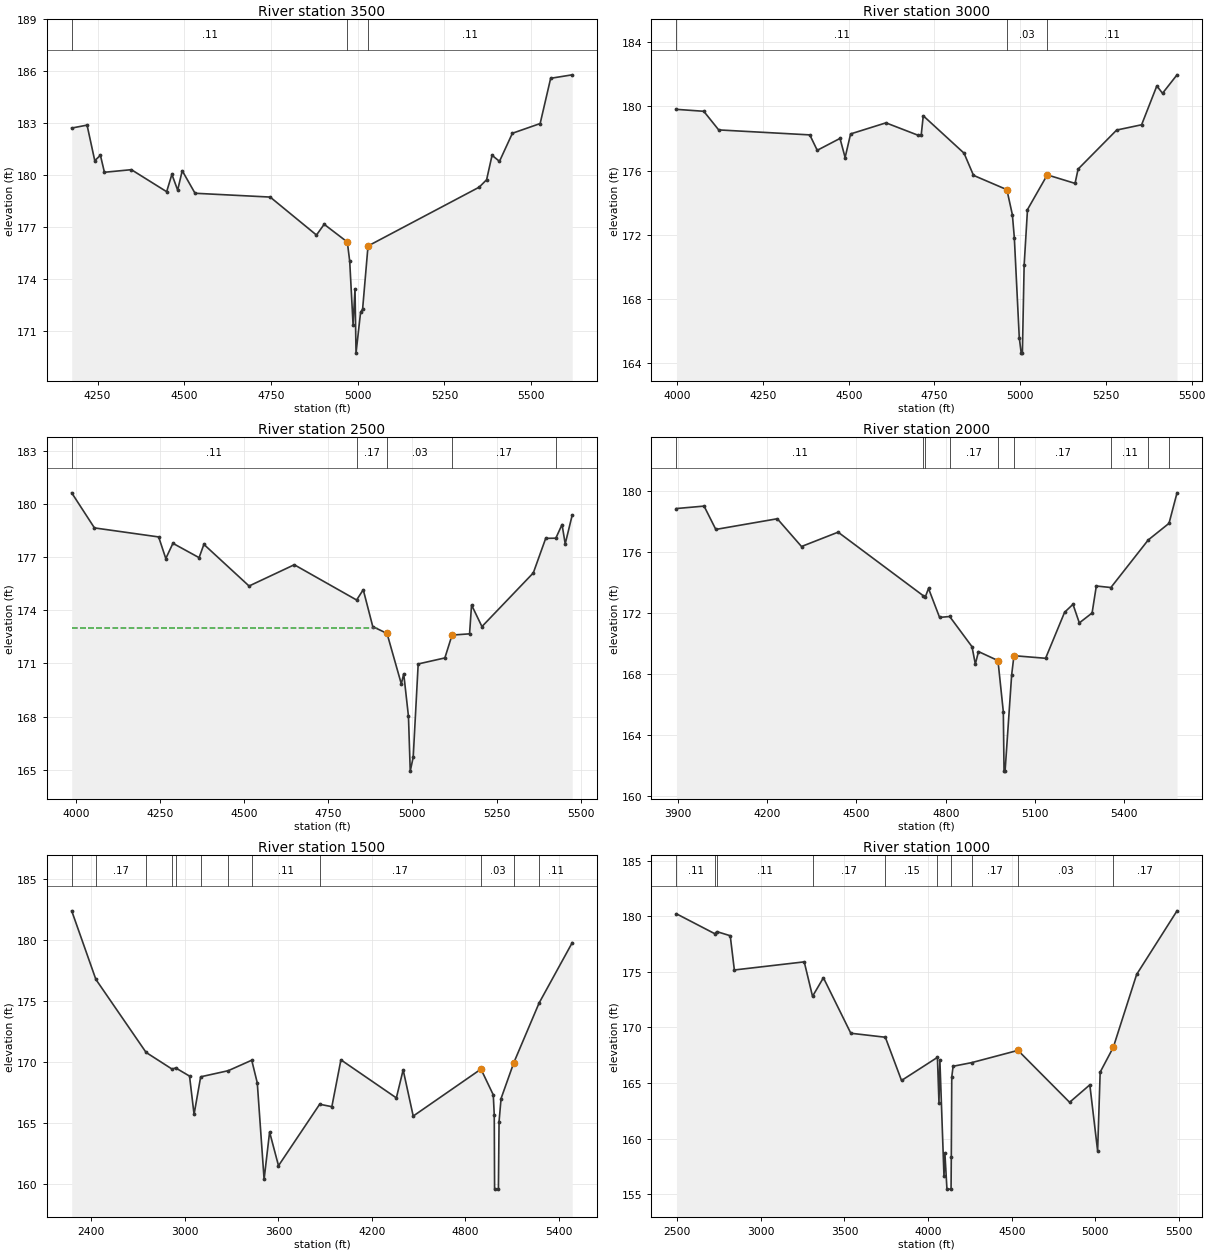
Type RM Length L Ch R = 1 ,3500    ,500,500,500
BEGIN DESCRIPTION:
POSSUM BRANCH 7.0
END DESCRIPTION:
XS GIS Cut Line= 3
      3839051.65     10111446.53      3838317.32     10111071.83
      3837784.25     10110758.57
#Sta/Elev= 30
  4175.6  182.73  4219.9   182.9  4242.1  180.85  4258.4  181.16  4269.9  180.18
  4347.6  180.33  4449.3  179.06  4464.4  180.06    4481  179.15  4494.2  180.27
  4531.1  178.97  4747.7  178.75  4881.1  176.56  4903.3  177.18    4970  176.16
  4976.9  175.05  4986.6  171.39  4992.2  173.46  4995.1  169.75  5008.3  172.11
  5014.1  172.29  5029.7  175.93    5350  179.32  5371.5  179.75  5387.2  181.16
  5408.6  180.81  5445.8  182.43  5525.8  182.99  5556.1   185.6  5618.3   185.8
#Mann= 3 , 0 , 0
  4175.6     .11       0    4970     .03       0  5029.7     .11       0
Bank Sta=4970,5029.7
XS Rating Curve= 0 ,0
Exp/Cntr=0.3,0.1

Type RM Length L Ch R = 1 ,3000    ,500,500,500
BEGIN DESCRIPTION:
POSSUM BRANCH 6.0
END DESCRIPTION:
XS GIS Cut Line= 3
      3839335.06     10111103.21      3838458.11     10110617.67
      3838051.19     10110408.78
#Sta/Elev= 30
  3997.6  179.81  4077.2  179.69  4120.7  178.53  4386.4  178.22  4408.1  177.26
  4474.5     178  4489.4  176.81  4505.4  178.28  4608.5  178.97  4703.1  178.19
  4711.5  178.24  4717.3  179.41  4836.3  177.08  4863.8   175.7  4961.1  174.81
  4977.2  173.25  4982.9  171.82  4997.3   165.6  5002.9  164.63  5006.4  164.63
  5011.5   170.1  5021.3  173.57    5079  175.73    5160   175.2  5168.9  176.09
  5281.3  178.52  5354.1  178.85  5398.5  181.27  5415.1  180.81  5457.4  181.96
#Mann= 3 , 0 , 0
  3997.6     .11       0  4961.1     .03       0    5079     .11       0
Bank Sta=4961.1,5079
XS Rating Curve= 0 ,0
Exp/Cntr=0.3,0.1

Type RM Length L Ch R = 1 ,2500    ,500,500,500
BEGIN DESCRIPTION:
POSSUM BRANCH 5.0
END DESCRIPTION:
XS GIS Cut Line= 3
      3839420.99     10110923.53      3838707.01     10110205.35
      3838301.99     10109956.99
#Sta/Elev= 30
  3987.3  180.63  4054.9  178.65  4245.8  178.14    4267  176.92  4288.2  177.78
    4366  176.97  4380.2  177.72  4514.5  175.37  4648.9  176.57  4834.2  174.58
  4853.9  175.16  4882.2  173.08  4924.6  172.69  4967.1  169.84  4974.2  170.42
  4988.3  168.01  4993.6  164.92  5002.4  165.71  5017.2  170.97  5096.5  171.31
  5117.8   172.6  5169.9  172.67  5175.8   174.3  5206.7  173.08  5359.4  176.11
  5396.2  178.06  5426.3  178.07  5444.8  178.84  5454.2  177.75  5475.1  179.38
#Mann= 5 ,-1 , 0
  3987.3     .11       0  4834.2     .17       0  4924.6     .03       0
  5117.8     .17       0  5426.3     .11       0
#XS Ineff= 2 , 0
       0  4896.3     173  5175.8       0   174.3
Permanent Ineff=
       F       F
Bank Sta=4924.6,5117.8
XS Rating Curve= 0 ,0
Exp/Cntr=0.3,0.1

Type RM Length L Ch R = 1 ,2000    ,500,500,500
BEGIN DESCRIPTION:
POSSUM BRANCH 4.0
END DESCRIPTION:
XS GIS Cut Line= 3
      3839459.18      10110892.3      3839020.91     10109878.47
       3838581.8     10109504.31
#Sta/Elev= 30
  3895.5  178.85  3988.2  179.01  4027.6  177.48  4234.1  178.18  4315.5  176.36
  4438.4   177.3    4724  173.14  4731.5  173.06  4742.1  173.61  4779.3  171.71
  4813.2  171.77  4888.2  169.79  4899.4  168.65    4910  169.47  4975.4  168.88
  4993.4  165.52  4995.8  161.63  4999.3  161.63  5021.4  167.94  5029.1   169.2
  5135.4  169.03  5199.3  172.05  5227.4  172.57  5248.7  171.35  5291.6     172
  5305.8  173.77  5354.7  173.67  5480.2  176.79    5550  177.88  5576.9  179.88
#Mann= 9 ,-1 , 0
  3895.5     .11       0    4724     .17       0  4731.5     .11       0
  4813.2     .17       0  4975.4     .03       0  5029.1     .17       0
  5354.7     .11       0  5480.2     .17       0    5550     .11       0
Bank Sta=4975.4,5029.1
XS Rating Curve= 0 ,0
Exp/Cntr=0.3,0.1

Type RM Length L Ch R = 1 ,1500    ,500,500,500
BEGIN DESCRIPTION:
POSSUM BRANCH 3.0
END DESCRIPTION:
XS GIS Cut Line= 3
      3841534.67     10111193.45      3839363.13     10109544.92
      3838931.67      10109323.4
#Sta/Elev= 30
  2273.6  182.36  2428.6  176.74  2750.8  170.75  2917.9  169.38  2940.5  169.48
  3029.6  168.81  3058.7  165.67  3101.1  168.75  3277.7  169.25  3428.7  170.11
  3464.3  168.25    3508  160.34  3543.3  164.22  3600.4  161.46  3864.5   166.5
  3942.7   166.3  4000.9  170.14  4356.6  167.02  4400.2  169.32  4464.7  165.53
  4899.4  169.38  4978.4  167.27  4984.7  165.61  4986.8  159.54  5011.3  159.54
  5015.5  165.08  5028.4  166.97  5109.8   169.9  5272.3   174.8    5485  179.75
#Mann= 12 ,-1 , 0
  2273.6     .11       0  2428.6     .17       0  2750.8     .15       0
  2917.9     .17       0  2940.5     .15       0  3101.1     .17       0
  3277.7     .15       0  3428.7     .11       0  3864.5     .17       0
  4899.4     .03       0  5109.8     .17       0  5272.3     .11       0
Bank Sta=4899.4,5109.8
XS Rating Curve= 0 ,0
Exp/Cntr=0.3,0.1

Type RM Length L Ch R = 1 ,1000    ,500,500,500
BEGIN DESCRIPTION:
POSSUM BRANCH 2.0
END DESCRIPTION:
XS GIS Cut Line= 3
      3842003.39     10110221.23      3839666.73     10109321.49
      3839256.06     10109058.06
#Sta/Elev= 30
  2496.1  180.22    2724  178.44  2737.5  178.62  2817.4  178.25    2842  175.17
  3259.7   175.9  3309.3   172.8  3374.3  174.47  3538.1  169.48  3744.4  169.12
  3841.2  165.23  4055.8  167.31    4065  163.24  4070.4  167.07    4095  156.62
  4100.4  158.69  4112.7  155.46  4137.3  155.46 4138.72158.3455  4141.5  165.55
  4149.6  166.51  4261.3  166.84  4537.3  167.94  4845.8  163.27  4966.7  164.84
  5013.3   158.9  5028.5  165.98  5107.1  168.22  5246.5  174.77  5487.9  180.49
#Mann= 10 ,-1 , 0
  2496.1     .11       0    2724     .17       0  2737.5     .11       0
  3309.3     .17       0  3744.4     .15       0  4055.8     .12       0
 4138.72     .15       0  4261.3     .17       0  4537.3     .03       0
  5107.1     .17       0
Bank Sta=4537.3,5107.1
XS Rating Curve= 0 ,0
Exp/Cntr=0.3,0.1

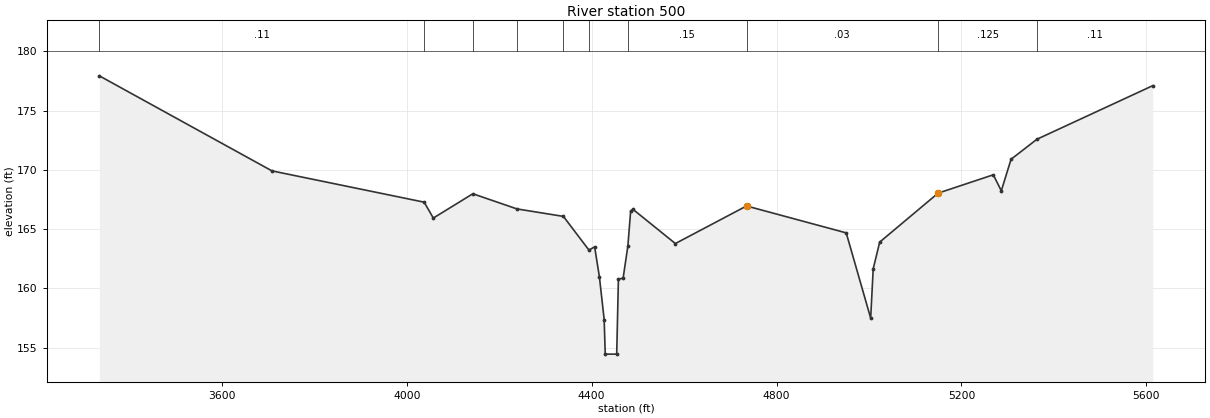
Type RM Length L Ch R = 1 ,500     ,0,0,0
BEGIN DESCRIPTION:
POSSUM BRANCH 1.0
END DESCRIPTION:
XS GIS Cut Line= 3
      3841621.54     10109396.61      3839999.91     10109019.52
      3839416.64     10108828.02
#Sta/Elev= 30
  3335.1  177.94  3708.5  169.92  4037.8  167.28  4057.6  165.94  4143.1  167.99
  4238.6  166.71    4339  166.08  4394.2  163.24  4406.6  163.51  4416.9  160.97
  4427.2  157.38  4429.5  154.46  4454.3  154.46    4458  160.79  4468.2  160.87
  4478.5  163.59  4484.5  166.55  4489.7  166.67  4581.2  163.79  4735.2  166.96
  4950.8  164.69  5003.7   157.5  5009.2  161.66  5023.2  163.91  5149.5  168.04
    5269  169.59  5286.3  168.24  5307.4   170.9  5363.4  172.59  5613.9  177.11
#Mann= 10 ,-1 , 0
  3335.1     .11       0  4037.8     .17       0  4143.1     .11       0
  4238.6     .17       0    4339     .15       0  4394.2     .12       0
  4478.5     .15       0  4735.2     .03       0  5149.5    .125       0
  5363.4     .11       0
Bank Sta=4735.2,5149.5
XS Rating Curve= 0 ,0
Exp/Cntr=0.3,0.1

Chan Stop Cuts=-1
Use User Specified Reach Order=0
Composite Channel Slope=5

--- POSSUM BRANCH.g10 (geometry) ---

Geom Title=Existing Conditions
Program Version=4.10

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
River Reach=POSSUM BRANCH   ,Reach-1

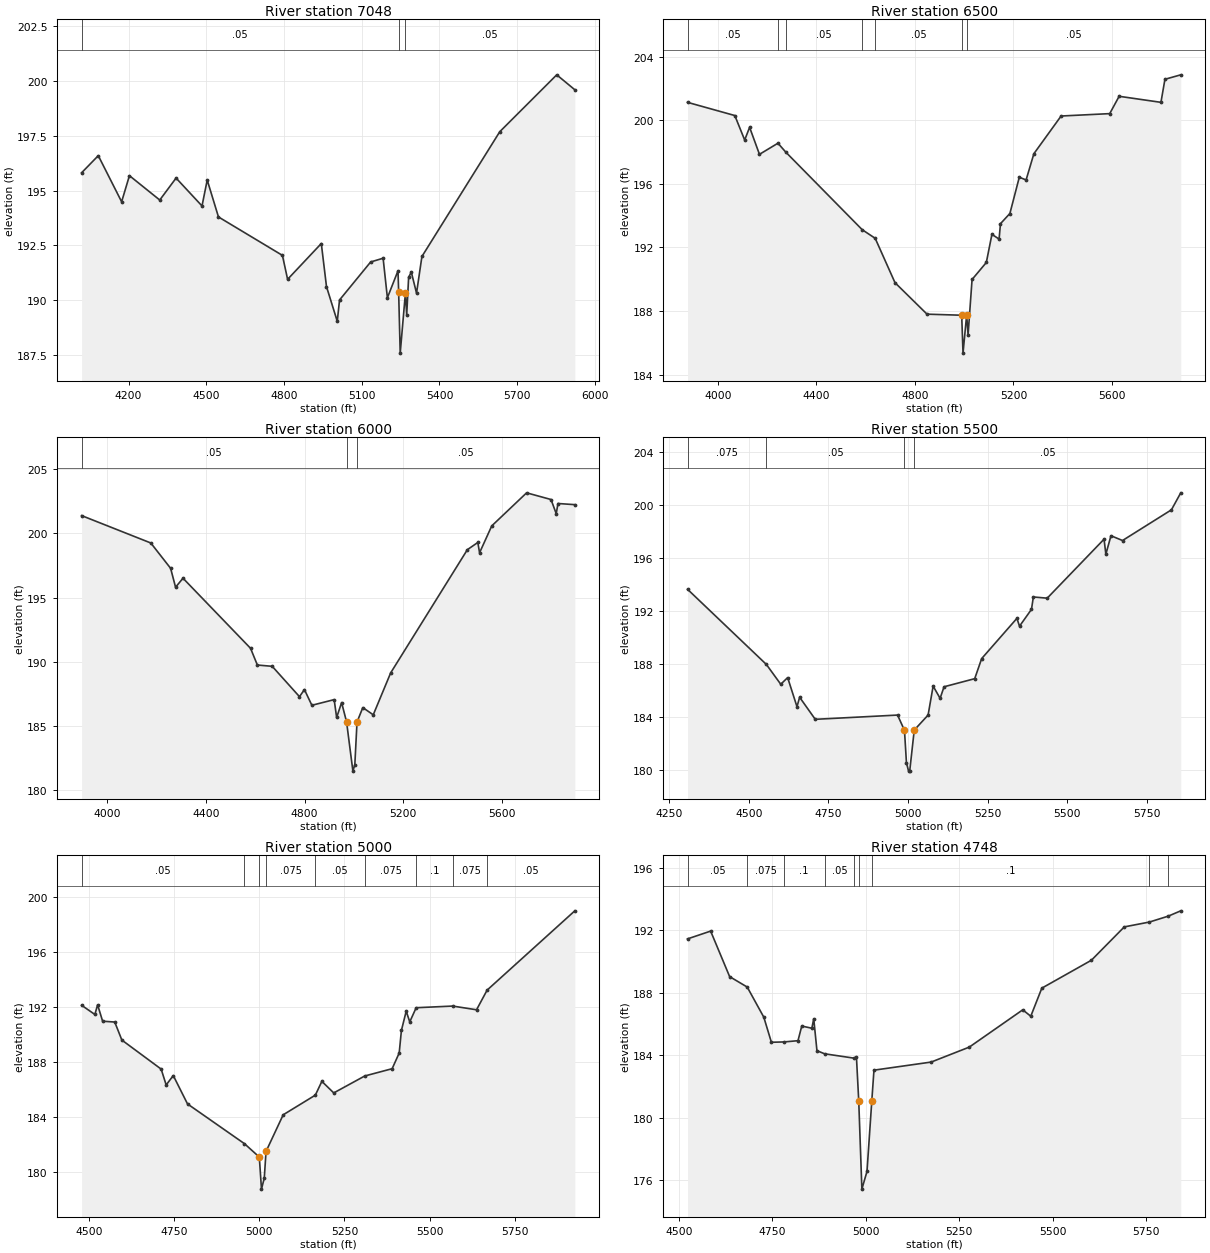
Type RM Length L Ch R = 1 ,7048    ,548,548,548
BEGIN DESCRIPTION:
POSSUM BRANCH 14.0
END DESCRIPTION:
XS GIS Cut Line= 3
      3836589.23     10114515.55      3836633.25     10113534.94
      3836427.86      10112635.7
#Sta/Elev= 30
  4018.4  195.81  4082.9  196.59    4173  194.49  4203.1  195.68  4320.2  194.57
  4383.2  195.57  4483.3   194.3  4503.4  195.48  4546.8   193.8  4793.7  192.05
  4813.7  190.96  4943.8  192.59  4963.8  190.63  5005.4  189.05  5014.2  190.02
  5134.3  191.75  5182.4  191.92  5198.9  190.12  5239.9  191.35 5242.31 190.395
  5248.4   187.6  5268.4  190.33  5273.5  189.35  5280.9  191.05  5291.2  191.29
  5311.4  190.33  5332.2     192  5632.7  197.68  5852.6  200.27  5922.4  199.59
#Mann= 3 , 0 , 0
  4018.4     .05       0 5242.31     .07       0  5268.4     .05       0
Bank Sta=5242.31,5268.4
XS Rating Curve= 0 ,0
Exp/Cntr=0.3,0.1

Type RM Length L Ch R = 1 ,6500    ,500,500,500
BEGIN DESCRIPTION:
POSSUM BRANCH 13.0
END DESCRIPTION:
XS GIS Cut Line= 3
      3837089.23     10114453.03       3837070.2     10113330.39
      3836654.51     10112555.78
#Sta/Elev= 30
  3877.2  201.12  4069.2  200.29  4109.2  198.75  4129.2  199.55  4169.2  197.85
  4244.2  198.55    4276  197.99  4586.3  193.11  4638.9  192.57  4719.3  189.78
  4849.3   187.8 4990.01 187.733  4995.4  185.35  5010.2  187.76  5015.9  186.49
  5032.1  189.98    5090  191.05  5112.7  192.82  5141.8  192.52  5147.4  193.49
  5185.6  194.13  5223.8  196.41  5251.4  196.24    5283  197.89  5393.5  200.26
  5590.8  200.41    5629   201.5  5798.7  201.12  5814.9  202.57  5879.1  202.85
#Mann= 7 ,-1 , 0
  3877.2     .05       0  4244.2    .075       0    4276     .05       0
  4586.3    .075       0  4638.9     .05       0 4990.01     .07       0
  5010.2     .05       0
Bank Sta=4990.01,5010.2
XS Rating Curve= 0 ,0
Exp/Cntr=0.3,0.1

Type RM Length L Ch R = 1 ,6000    ,500,500,500
BEGIN DESCRIPTION:
POSSUM BRANCH 12.0
END DESCRIPTION:
XS GIS Cut Line= 3
      3837574.47     10114200.41      3837458.63      10113101.5
      3836823.63     10112468.67
#Sta/Elev= 30
    3895  201.37  4175.9  199.24  4256.3  197.27  4276.4   195.8  4306.6   196.5
  4580.7  191.05  4608.3  189.75  4668.6  189.65  4779.2  187.29  4799.3  187.84
  4829.5  186.62    4920  187.06    4930  185.67  4950.2  186.83  4970.3  185.33
    4996   181.5  5003.8     182 5012.71 185.316  5036.2  186.44  5078.6  185.88
  5149.3  189.14  5460.5  198.72  5502.9  199.28    5510  198.48  5559.5  200.57
  5700.9  203.14  5799.9  202.62  5821.1  201.52  5828.2  202.31  5896.5  202.22
#Mann= 3 , 0 , 0
    3895     .05       0  4970.3     .07       0 5012.71     .05       0
Bank Sta=4970.3,5012.71
XS Rating Curve= 0 ,0
Exp/Cntr=0.3,0.1

Type RM Length L Ch R = 1 ,5500    ,500,500,500
BEGIN DESCRIPTION:
POSSUM BRANCH 11.0
END DESCRIPTION:
XS GIS Cut Line= 3
      3838147.08     10113370.52      3837806.76     10112767.29
      3837057.98     10112351.46
#Sta/Elev= 30
  4307.4  193.64  4555.1  187.98  4600.2  186.49  4621.9  186.99  4651.2   184.8
  4659.5  185.51  4708.6  183.85  4967.1  184.17  4988.8  183.02    4995  180.57
  5001.7  179.95  5005.2  179.95  5019.5  183.04    5063  184.17  5078.8  186.35
  5100.7  185.43  5113.1   186.3  5209.4  186.91  5231.2  188.42  5341.9  191.45
  5350.1  190.86  5387.7  192.13  5393.6  193.06  5437.1  192.97  5615.6  197.41
  5621.3  196.28  5637.3  197.67  5673.6  197.31  5827.2  199.62  5856.5   200.9
#Mann= 4 ,-1 , 0
  4307.4    .075       0  4555.1     .05       0  4988.8     .07       0
  5019.5     .05       0
Bank Sta=4988.8,5019.5
XS Rating Curve= 0 ,0
Exp/Cntr=0.3,0.1

Type RM Length L Ch R = 1 ,5000    ,252,252,252
BEGIN DESCRIPTION:
POSSUM BRANCH 10.0
END DESCRIPTION:
XS GIS Cut Line= 3
      3838539.48     10112724.74      3838115.78     10112420.02
      3837218.28       10112190.
#Sta/Elev= 30
  4478.1  192.13  4517.1  191.46  4525.2  192.16  4539.9  190.97  4575.5  190.91
  4596.4   189.6  4711.8  187.49  4726.5  186.34  4747.4  187.02  4789.2  184.96
  4956.5  182.07    5000   181.1  5006.4  178.77  5014.6  179.57  5019.8  181.51
  5070.1  184.17  5164.6   185.6  5183.7   186.6  5218.6  185.76  5309.6  186.99
  5390.1  187.52  5410.8  188.66  5417.3   190.3  5431.4   191.7  5441.8  190.92
  5460.6  191.95  5568.1  192.07  5637.9   191.8    5669  193.23  5926.5  198.99
#Mann= 9 ,-1 , 0
  4478.1     .05       0  4956.5    .075       0    5000     .07       0
  5019.8    .075       0  5164.6     .05       0  5309.6    .075       0
  5460.6      .1       0  5568.1    .075       0    5669     .05       0
Bank Sta=5000,5019.8
XS Rating Curve= 0 ,0
Exp/Cntr=0.3,0.1

Type RM Length L Ch R = 1 ,4748    ,157,157,157
BEGIN DESCRIPTION:
Mapping XS 3f61720d
END DESCRIPTION:
XS GIS Cut Line= 3
      3838688.76     10112273.33      3838219.22      10112191.6
      3837393.61      10112026.8
#Sta/Elev= 30
  4523.4  191.46  4585.2  191.96    4636  189.04    4683  188.37  4727.3  186.44
  4747.6  184.83  4780.6  184.85  4818.7  184.93  4828.8  185.87  4855.8  185.73
  4860.8  186.34  4869.4  184.29  4889.9  184.09  4968.7  183.81    4975  183.87
  4981.1  181.07  4989.5  175.41  5003.2  176.55 5016.07 181.091  5021.8  183.04
  5174.8  183.56  5276.7  184.52  5419.5  186.91    5441   186.5  5470.5   188.3
    5603  190.09    5691  192.23  5758.1  192.54  5808.6  192.92  5841.9  193.26
#Mann= 9 ,-1 , 0
  4523.4     .05       0    4683    .075       0  4780.6      .1       0
  4889.9     .05       0  4968.7      .1       0  4981.1     .07       0
 5016.07      .1       0  5758.1    .075       0  5808.6      .1       0
Bank Sta=4981.1,5016.07
XS Rating Curve= 0 ,0
Exp/Cntr=0.3,0.1