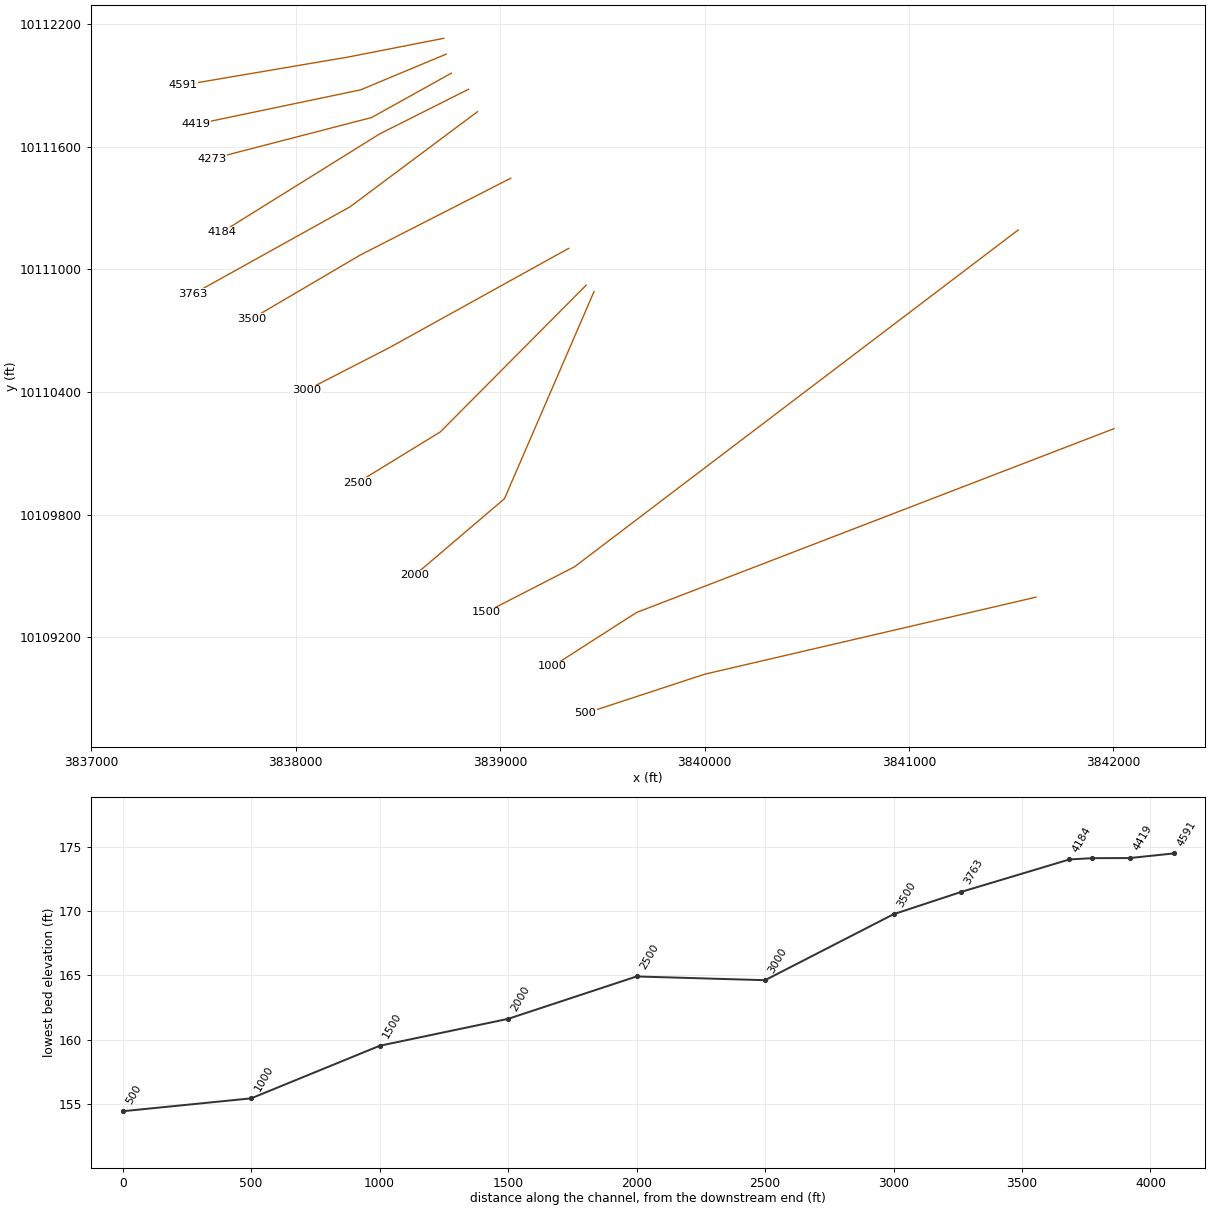
HEC-RAS study POSSUM BRANCH.prj: POSSUM BRANCH Base Level Engineering

--- POSSUM BRANCH.g10 (geometry) --- (continued)

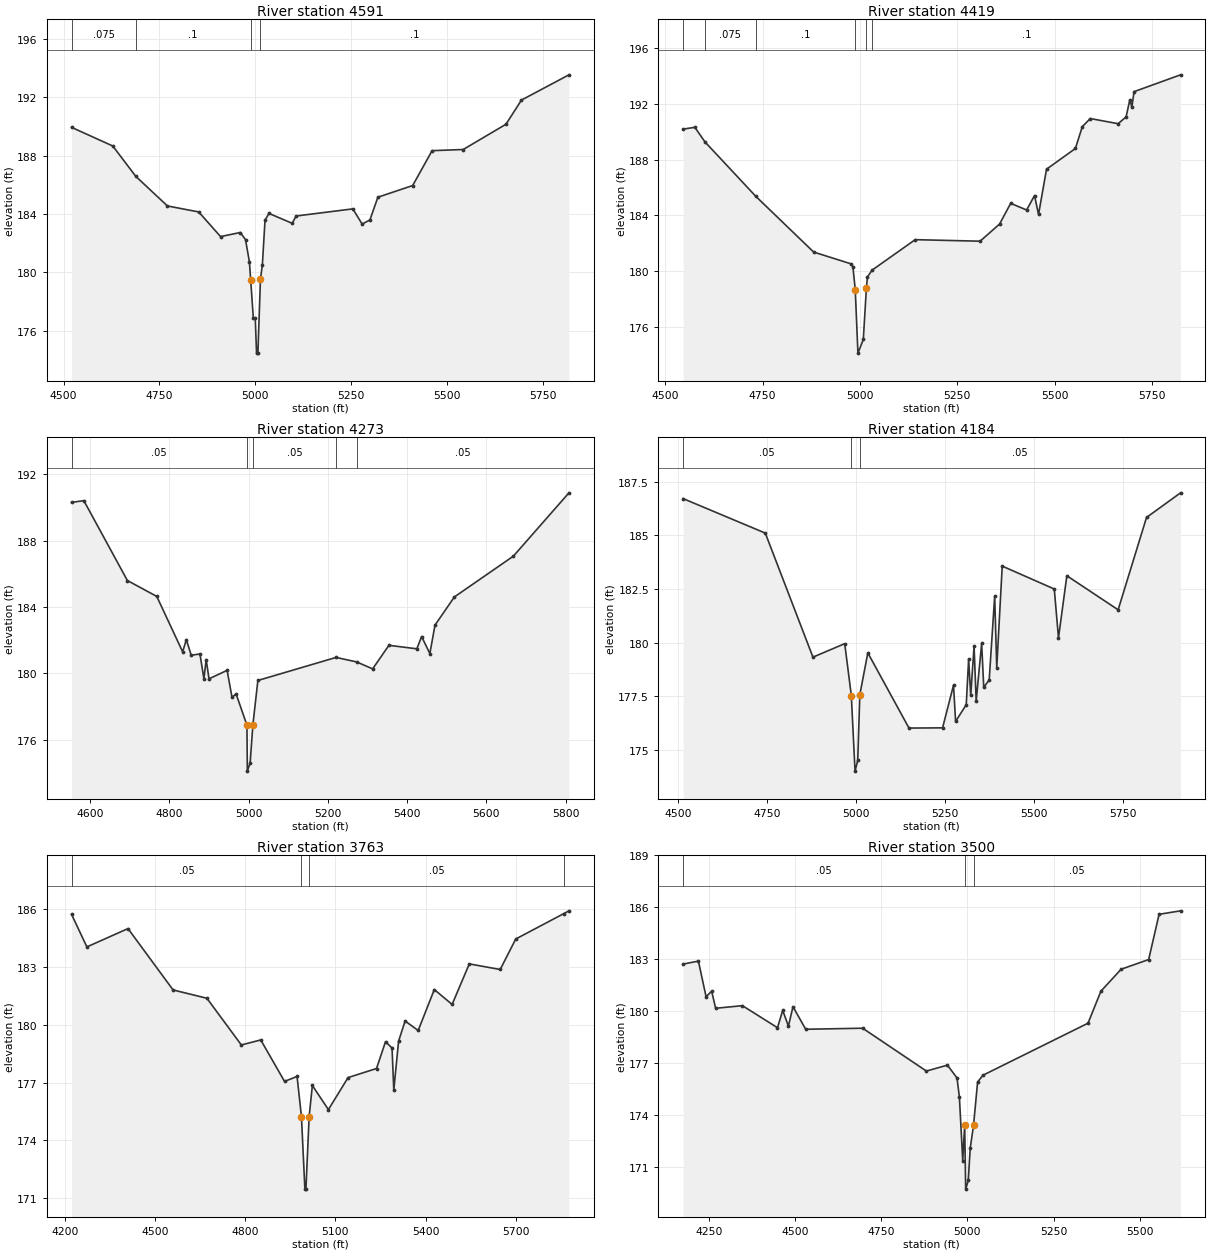
Type RM Length L Ch R = 1 ,4591    ,172,172,172
BEGIN DESCRIPTION:
POSSUM BRANCH 9.0
END DESCRIPTION:
XS GIS Cut Line= 3
      3838723.54     10112130.98      3838252.96      10112038.9
      3837445.72     10111901.81
#Sta/Elev= 30
  4520.5  189.95  4628.2  188.67  4688.2  186.59  4770.8  184.56  4852.4  184.15
  4909.5  182.46    4961  182.74  4974.6  182.25  4984.8  180.72 4988.03 179.504
    4995  176.88    5000  176.88  5003.4  174.47  5006.9  174.47  5013.6  179.54
  5018.6  180.53  5025.5  183.58  5035.6  184.05  5096.5  183.37  5106.6  183.87
  5254.7  184.36    5279  183.32  5299.3   183.6  5320.1  185.16  5410.9  185.96
  5461.6  188.35  5542.8  188.43  5654.3  190.16  5694.9  191.82  5818.8  193.55
#Mann= 4 ,-1 , 0
  4520.5    .075       0  4688.2      .1       0 4988.03     .07       0
  5013.6      .1       0
Bank Sta=4988.03,5013.6
XS Rating Curve= 0 ,0
Exp/Cntr=0.3,0.1

Type RM Length L Ch R = 1 ,4419    ,146,146,146
BEGIN DESCRIPTION:
Mapping XS c79e3b19
END DESCRIPTION:
XS GIS Cut Line= 3
      3838735.64     10112053.71      3838316.89     10111878.84
      3837511.01     10111710.37
#Sta/Elev= 30
  4546.2   190.2  4576.3  190.33  4602.3  189.28  4732.9  185.37  4881.3  181.37
  4976.5  180.53    4982  180.33  4988.1  178.68    4995  174.11  5008.8  175.09
 5016.71 178.778  5019.4  179.58  5031.3  180.07    5142  182.26  5308.7  182.15
  5358.6  183.38  5387.2  184.87  5428.1  184.39  5448.4  185.43  5458.7  184.07
  5479.2  187.32  5553.4  188.81  5571.1  190.38  5591.6  190.96  5663.1  190.59
  5683.5  191.08  5693.1  192.31  5698.3  191.78  5703.9  192.89  5823.3   194.1
#Mann= 6 ,-1 , 0
  4546.2     .05       0  4602.3    .075       0  4732.9      .1       0
  4988.1     .07       0 5016.71     .05       0  5031.3      .1       0
Bank Sta=4988.1,5016.71
XS Rating Curve= 0 ,0
Exp/Cntr=0.3,0.1

Type RM Length L Ch R = 1 ,4273    ,89,89,89
BEGIN DESCRIPTION:
POSSUM BRANCH 8.0
END DESCRIPTION:
XS GIS Cut Line= 3
      3838760.97     10111960.55      3838370.71     10111743.42
      3837588.04     10111540.68
#Sta/Elev= 30
  4553.4  190.31  4584.4  190.42  4694.3   185.6  4768.5  184.64  4833.7   181.3
  4843.1  182.03  4855.4  181.09  4877.4  181.17  4887.4  179.67  4893.1  180.83
  4900.3  179.67    4946  180.18  4958.3  178.55  4968.6  178.76    4996  176.87
    4997   174.1  5004.1   174.6 5010.98 176.896  5023.6  179.57  5220.9  180.96
  5272.5  180.69  5313.2  180.27  5354.2  181.69  5424.7  181.48  5436.8  182.22
  5457.5  181.19  5470.5  182.91  5519.5  184.61  5668.3  187.07  5808.5  190.89
#Mann= 5 ,-1 , 0
  4553.4     .05       0    4996     .07       0 5010.98     .05       0
  5220.9      .1       0  5272.5     .05       0
Bank Sta=4996,5010.98
XS Rating Curve= 0 ,0
Exp/Cntr=0.3,0.1

Type RM Length L Ch R = 1 ,4184    ,421,421,421
BEGIN DESCRIPTION:
Mapping XS 73a9c07d
END DESCRIPTION:
XS GIS Cut Line= 3
      3838844.98     10111881.82      3838410.64     10111663.56
      3837636.66     10111181.74
#Sta/Elev= 30
  4513.9  186.72  4744.8  185.11  4878.7  179.32    4968  179.95 4986.55 177.527
    4997     174  5004.6   174.5  5010.4 177.563  5032.9  179.52  5148.6  176.01
    5243  176.02  5273.7  178.01  5279.6  176.32  5309.5   177.1  5316.2  179.23
  5322.1  177.54  5331.5  179.83  5337.4  177.27  5352.8  179.96  5358.7  177.91
    5374  178.26  5389.4  182.16  5395.2  178.83  5410.6  183.57  5556.9   182.5
  5568.7  180.22  5592.2  183.12  5736.3  181.53  5816.1  185.84  5911.7  186.99
#Mann= 3 , 0 , 0
  4513.9     .05       0 4986.55     .07       0  5010.4     .05       0
Bank Sta=4986.55,5010.4
XS Rating Curve= 0 ,0
Exp/Cntr=0.3,0.1

Type RM Length L Ch R = 1 ,3763    ,263,263,263
BEGIN DESCRIPTION:
Mapping XS 28265cf5
END DESCRIPTION:
XS GIS Cut Line= 3
      3838888.83     10111772.01       3838264.8     10111306.38
       3837497.8     10110880.11
#Sta/Elev= 30
  4221.4  185.72  4272.5  184.03  4409.4  184.98  4559.5   181.8  4672.1  181.37
  4786.7  178.95  4851.4  179.21  4930.6  177.06  4972.3  177.32  4986.9  175.23
  4998.3  171.48  5001.8  171.48  5012.5 175.235  5023.2  176.85  5076.6   175.6
  5142.1  177.26  5236.8  177.73  5266.8  179.12  5288.5  178.79  5294.3  176.61
  5310.3  179.15    5332  180.19  5375.5   179.7  5429.2  181.82  5488.5  181.05
  5545.7  183.15  5648.6  182.86  5700.3  184.44  5860.8  185.76  5877.5   185.9
#Mann= 4 ,-1 , 0
  4221.4     .05       0  4986.9     .07       0  5012.5     .05       0
  5860.8    .075       0
Bank Sta=4986.9,5012.5
XS Rating Curve= 0 ,0
Exp/Cntr=0.3,0.1

Type RM Length L Ch R = 1 ,3500    ,500,500,500
BEGIN DESCRIPTION:
POSSUM BRANCH 7.0
END DESCRIPTION:
XS GIS Cut Line= 3
      3839051.65     10111446.53      3838317.32     10111071.83
      3837784.25     10110758.57
#Sta/Elev= 30
  4175.6  182.73  4219.9   182.9  4242.1  180.85  4258.4  181.16  4269.9  180.18
  4347.6  180.33  4449.3  179.06  4464.4  180.06    4481  179.15  4494.2  180.27
  4531.1  178.97  4696.3  179.03  4881.1  176.56  4942.2   176.9    4970  176.16
  4976.9  175.05  4986.6  171.39  4992.2  173.46  4995.1  169.75  5002.6  170.25
  5008.3  172.11 5017.91 173.429  5029.7  175.93  5045.4  176.32    5350  179.32
  5387.2  181.16  5445.8  182.43  5525.8  182.99  5556.1   185.6  5618.3   185.8
#Mann= 3 , 0 , 0
  4175.6     .05       0  4992.2     .07       0 5017.91     .05       0
Bank Sta=4992.2,5017.91
XS Rating Curve= 0 ,0
Exp/Cntr=0.3,0.1

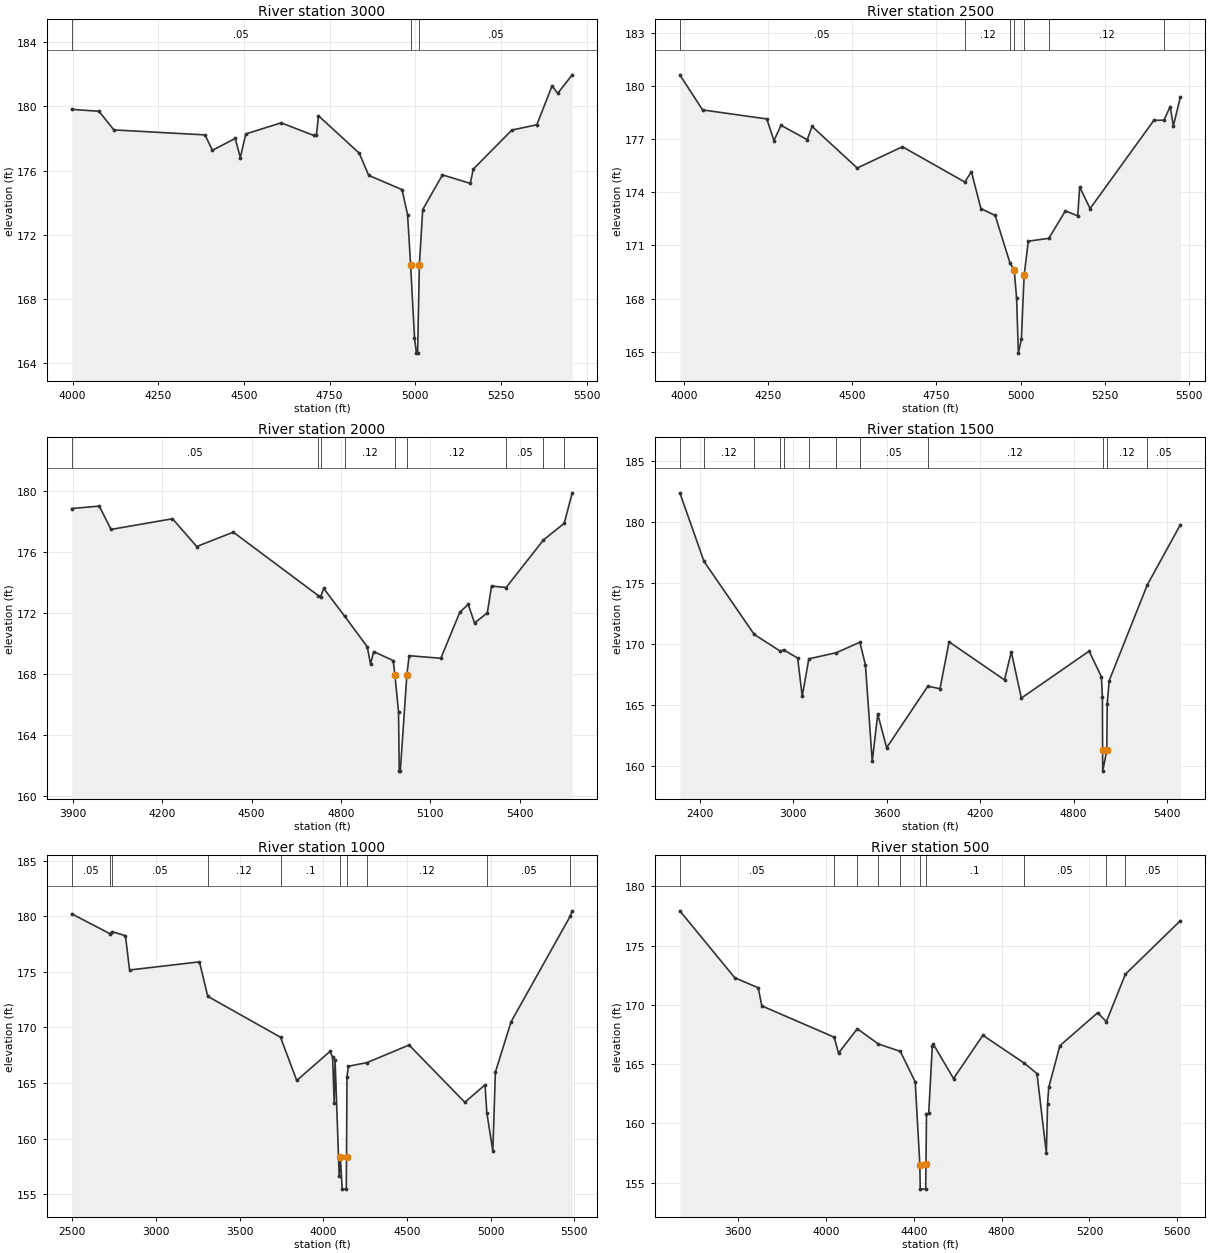
Type RM Length L Ch R = 1 ,3000    ,500,500,500
BEGIN DESCRIPTION:
POSSUM BRANCH 6.0
END DESCRIPTION:
XS GIS Cut Line= 3
      3839335.06     10111103.21      3838458.11     10110617.67
      3838051.19     10110408.78
#Sta/Elev= 30
  3997.6  179.81  4077.2  179.69  4120.7  178.53  4386.4  178.22  4408.1  177.26
  4474.5     178  4489.4  176.81  4505.4  178.28  4608.5  178.97  4703.1  178.19
  4711.5  178.24  4717.3  179.41  4836.3  177.08  4863.8   175.7  4961.1  174.81
  4977.2  173.25 4986.13 170.097  4997.3   165.6  5002.9  164.63  5006.4  164.63
  5011.5   170.1  5021.3  173.57    5079  175.73    5160   175.2  5168.9  176.09
  5281.3  178.52  5354.1  178.85  5398.5  181.27  5415.1  180.81  5457.4  181.96
#Mann= 3 , 0 , 0
  3997.6     .05       0 4986.13     .07       0  5011.5     .05       0
Bank Sta=4986.13,5011.5
XS Rating Curve= 0 ,0
Exp/Cntr=0.3,0.1

Type RM Length L Ch R = 1 ,2500    ,500,500,500
BEGIN DESCRIPTION:
POSSUM BRANCH 5.0
END DESCRIPTION:
XS GIS Cut Line= 3
      3839420.99     10110923.53      3838707.01     10110205.35
      3838301.99     10109956.99
#Sta/Elev= 30
  3987.3  180.63  4054.9  178.65  4245.8  178.14    4267  176.92  4288.2  177.78
    4366  176.97  4380.2  177.72  4514.5  175.37  4648.9  176.57  4834.2  174.58
  4853.9  175.16  4882.2  173.08  4924.6  172.69  4968.9  169.99  4981.2  169.62
  4988.3  168.01  4993.6  164.92  5002.4  165.71  5010.7  169.31    5023  171.24
  5084.1   171.4  5133.2  172.95  5169.9  172.67  5175.8   174.3  5206.7  173.08
  5396.2  178.06  5426.3  178.07  5444.8  178.84  5454.2  177.75  5475.1  179.38
#Mann= 7 ,-1 , 0
  3987.3     .05       0  4834.2     .12       0  4968.9     .05       0
  4981.2     .07       0  5010.7     .05       0  5084.1     .12       0
  5426.3     .05       0
Bank Sta=4981.2,5010.7
XS Rating Curve= 0 ,0
Exp/Cntr=0.3,0.1

Type RM Length L Ch R = 1 ,2000    ,500,500,500
BEGIN DESCRIPTION:
POSSUM BRANCH 4.0
END DESCRIPTION:
XS GIS Cut Line= 3
      3839459.18      10110892.3      3839020.91     10109878.47
       3838581.8     10109504.31
#Sta/Elev= 30
  3895.5  178.85  3988.2  179.01  4027.6  177.48  4234.1  178.18  4315.5  176.36
  4438.4   177.3    4724  173.14  4731.5  173.06  4742.1  173.61  4813.2  171.77
  4888.2  169.79  4899.4  168.65    4910  169.47  4975.4  168.88 4981.18 167.952
  4993.4  165.52  4995.8  161.63  4999.3  161.63  5021.4  167.94  5029.1   169.2
  5135.4  169.03  5199.3  172.05  5227.4  172.57  5248.7  171.35  5291.6     172
  5305.8  173.77  5354.7  173.67  5480.2  176.79    5550  177.88  5576.9  179.88
#Mann= 9 ,-1 , 0
  3895.5     .05       0    4724     .12       0  4731.5     .05       0
  4813.2     .12       0 4981.18     .07       0  5021.4     .12       0
  5354.7     .05       0  5480.2     .12       0    5550     .05       0
Bank Sta=4981.18,5021.4
XS Rating Curve= 0 ,0
Exp/Cntr=0.3,0.1

Type RM Length L Ch R = 1 ,1500    ,500,500,500
BEGIN DESCRIPTION:
POSSUM BRANCH 3.0
END DESCRIPTION:
XS GIS Cut Line= 3
      3841534.67     10111193.45      3839363.13     10109544.92
      3838931.67      10109323.4
#Sta/Elev= 30
  2273.6  182.36  2428.6  176.74  2750.8  170.75  2917.9  169.38  2940.5  169.48
  3029.6  168.81  3058.7  165.67  3101.1  168.75  3277.7  169.25  3428.7  170.11
  3464.3  168.25    3508  160.34  3543.3  164.22  3600.4  161.46  3864.5   166.5
  3942.7   166.3  4000.9  170.14  4356.6  167.02  4400.2  169.32  4464.7  165.53
  4899.4  169.38  4978.4  167.27  4984.7  165.61 4985.94 161.293  4986.8  159.54
 5012.69 161.252  5015.5  165.08  5028.4  166.97  5272.3   174.8    5485  179.75
#Mann= 12 ,-1 , 0
  2273.6     .05       0  2428.6     .12       0  2750.8      .1       0
  2917.9     .12       0  2940.5      .1       0  3101.1     .12       0
  3277.7      .1       0  3428.7     .05       0  3864.5     .12       0
 4985.94     .07       0 5012.69     .12       0  5272.3     .05       0
Bank Sta=4985.94,5012.69
XS Rating Curve= 0 ,0
Exp/Cntr=0.3,0.1

Type RM Length L Ch R = 1 ,1000    ,500,500,500
BEGIN DESCRIPTION:
POSSUM BRANCH 2.0
END DESCRIPTION:
XS GIS Cut Line= 3
      3842003.39     10110221.23      3839666.73     10109321.49
      3839256.06     10109058.06
#Sta/Elev= 30
  2496.1  180.22    2724  178.44  2737.5  178.62  2817.4  178.25    2842  175.17
  3259.7   175.9  3309.3   172.8  3744.4  169.12  3841.2  165.23  4040.4  167.85
  4055.8  167.31    4065  163.24  4070.4  167.07    4095  156.62 4102.31 158.308
  4112.7  155.46  4137.3  155.46 4138.72 158.346  4141.5  165.55  4149.6  166.51
  4261.3  166.84  4512.7  168.42  4845.8  163.27  4966.7  164.84  4977.4  162.33
  5013.3   158.9  5028.5  165.98  5122.3  170.51  5475.5     180  5487.9  180.49
#Mann= 10 ,-1 , 0
  2496.1     .05       0    2724     .12       0  2737.5     .05       0
  3309.3     .12       0  3744.4      .1       0 4102.31     .07       0
 4138.72      .1       0  4261.3     .12       0  4977.4     .05       0
  5475.5     .12       0
Bank Sta=4102.31,4138.72
XS Rating Curve= 0 ,0
Exp/Cntr=0.3,0.1

Type RM Length L Ch R = 1 ,500     ,0,0,0
BEGIN DESCRIPTION:
POSSUM BRANCH 1.0
END DESCRIPTION:
XS GIS Cut Line= 3
      3841621.54     10109396.61      3839999.91     10109019.52
      3839416.64     10108828.02
#Sta/Elev= 30
  3335.1  177.94  3585.3  172.29  3691.9  171.45  3708.5  169.92  4037.8  167.28
  4057.6  165.94  4143.1  167.99  4238.6  166.71    4339  166.08  4406.6  163.51
 4427.83 156.533  4429.5  154.46  4454.3  154.46 4455.67 156.545    4458  160.79
  4468.2  160.87  4484.5  166.55  4489.7  166.67  4581.2  163.79  4714.6  167.44
  4901.5  165.11    4961  164.21  5003.7   157.5  5009.2  161.66  5014.5  163.04
  5065.3  166.56  5237.2  169.34    5277  168.59  5363.4  172.59  5613.9  177.11
#Mann= 10 ,-1 , 0
  3335.1     .05       0  4037.8     .12       0  4143.1     .05       0
  4238.6     .12       0    4339      .1       0 4427.83     .07       0
 4455.67      .1       0  4901.5     .05       0    5277    .075       0
  5363.4     .05       0
Bank Sta=4427.83,4455.67
XS Rating Curve= 0 ,0
Exp/Cntr=0.3,0.1