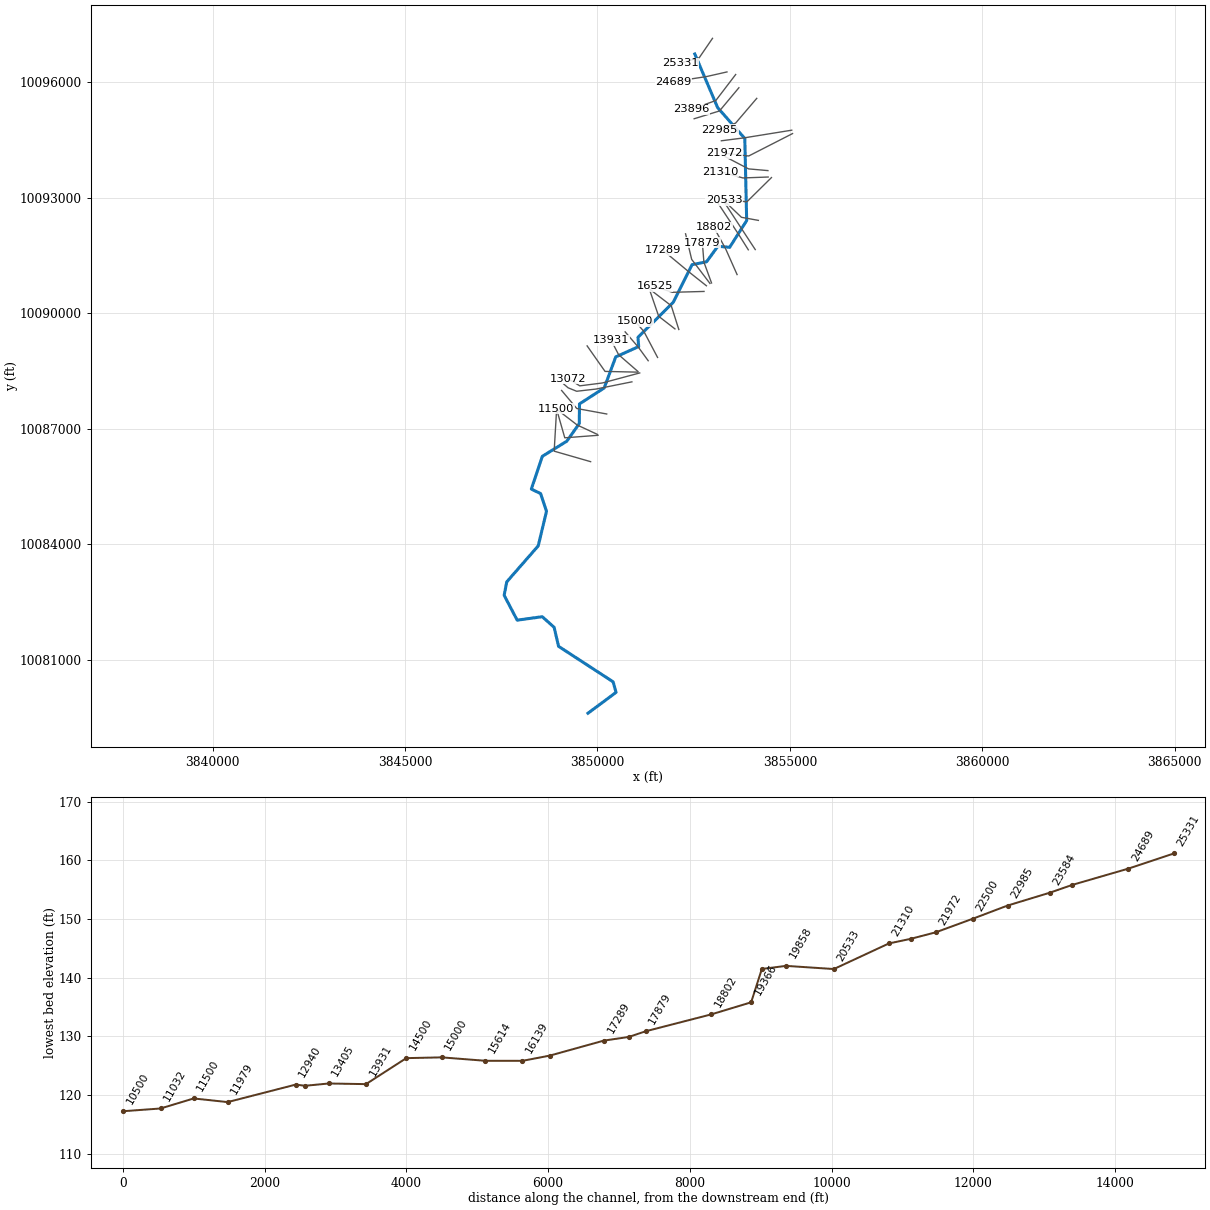
--- SANDY BRANCH.prj (project) ---

Proj Title=SANDY BRANCH Base Level Engineering
Current Plan=p01
Default Exp/Contr=0.3,0.1
English Units
Geom File=g01
Flow File=f01
Plan File=p01
Y Axis Title=Elevation
X Axis Title(PF)=Main Channel Distance
X Axis Title(XS)=Station
BEGIN DESCRIPTION:
SANDY BRANCH
END DESCRIPTION:
DSS Export Rating Curves= 0
DSS Export Rating Curve Sorted= 0
DSS Export Volume Flow Curves= 0
DXF OffsetX= 0
DXF OffsetY= 0
DXF ScaleX= 1
DXF ScaleY= 10

--- SANDY BRANCH.p01 (plan) ---

Plan Title=Multiple Run
Short Identifier=Multiple
Geom File=g01
Flow File=f01
Subcritical Flow
K Sum by GR= 0
Std Step Tol= 0.01
Critical Tol= 0.01
Num of Std Step Trials= 20
Max Error Tol= 0.3
Flow Tol Ratio= 0.001
Split Flow NTrial= 30
Split Flow Tol= 0.02
Split Flow Ratio= 0.02
Log Output Level= 0
Friction Slope Method= 1
Unsteady Friction Slope Method= 2
Unsteady Bridges Friction Slope Method= 1
Parabolic Critical Depth
Global Vel Dist=  1 , 1 , 1
Global Log Level= 0
CheckData=True
Encroach Param= -1, 0, 0, 0
BEGIN DESCRIPTION:
Multiple Run
END DESCRIPTION:

--- SANDY BRANCH.f01 (steady flow) ---

Flow Title=Multiple
Program Version=4.10
Number of Profiles= 7
Profile Names=10-year,25-year,50-year,1pct_min,100-year,1pct_plu,500-year
River Rch & RM=SANDY BRANCH,Reach-1         ,25331
     676     904    1210     533    1609    4859    2943
River Rch & RM=SANDY BRANCH,Reach-1         ,21972
    1071    1471    2007     898    2713    8193    5127
River Rch & RM=SANDY BRANCH,Reach-1         ,15614
    1293    1784    2440    1095    3306    9984    6275
River Rch & RM=SANDY BRANCH,Reach-1         ,5209
    1404    1943    2662    1196    3611   10905    6871
Boundary for River Rch & Prof#=SANDY BRANCH,Reach-1         , 1
Up Type= 0
Dn Type= 3
Dn Slope=0.013
Boundary for River Rch & Prof#=SANDY BRANCH,Reach-1         , 2
Up Type= 0
Dn Type= 3
Dn Slope=0.013
Boundary for River Rch & Prof#=SANDY BRANCH,Reach-1         , 3
Up Type= 0
Dn Type= 3
Dn Slope=0.013
Boundary for River Rch & Prof#=SANDY BRANCH,Reach-1         , 4
Up Type= 0
Dn Type= 3
Dn Slope=0.013
Boundary for River Rch & Prof#=SANDY BRANCH,Reach-1         , 5
Up Type= 0
Dn Type= 3
Dn Slope=0.013
Boundary for River Rch & Prof#=SANDY BRANCH,Reach-1         , 6
Up Type= 0
Dn Type= 3
Dn Slope=0.013
Boundary for River Rch & Prof#=SANDY BRANCH,Reach-1         , 7
Up Type= 0
Dn Type= 3
Dn Slope=0.013
DSS Import GetInterval= 0
DSS Import GetPeak= 0
DSS Import FillOption= 0

--- SANDY BRANCH.g01 (geometry) ---

Geom Title=Existing Conditions
Program Version=4.10

River Reach=SANDY BRANCH    ,Reach-1
Reach XY= 30
      3852528.24     10096726.86      3853121.19     10095335.31
      3853826.92     10094534.42      3853875.76      10092401.2
      3853433.09     10091706.61      3853128.26     10091734.91
      3852833.12     10091331.76      3852455.61     10091254.77
      3851964.73     10090274.66      3851051.85     10089369.14
      3851070.26     10089128.96      3850474.32     10088861.39
      3850174.69     10088054.75      3849532.34     10087640.03
      3849526.98     10087129.25      3849202.85     10086671.77
      3848568.04     10086279.71      3848280.61     10085428.37
       3848521.5     10085311.19      3848675.14     10084850.25
       3848460.3     10083953.11      3847642.59     10083018.22
      3847574.88     10082669.26      3847913.42     10082023.42
      3848564.47     10082113.27      3848873.06     10081837.23
      3848988.94     10081343.74      3850405.61     10080421.86
      3850482.43     10080148.42       3849752.6      10079606.5

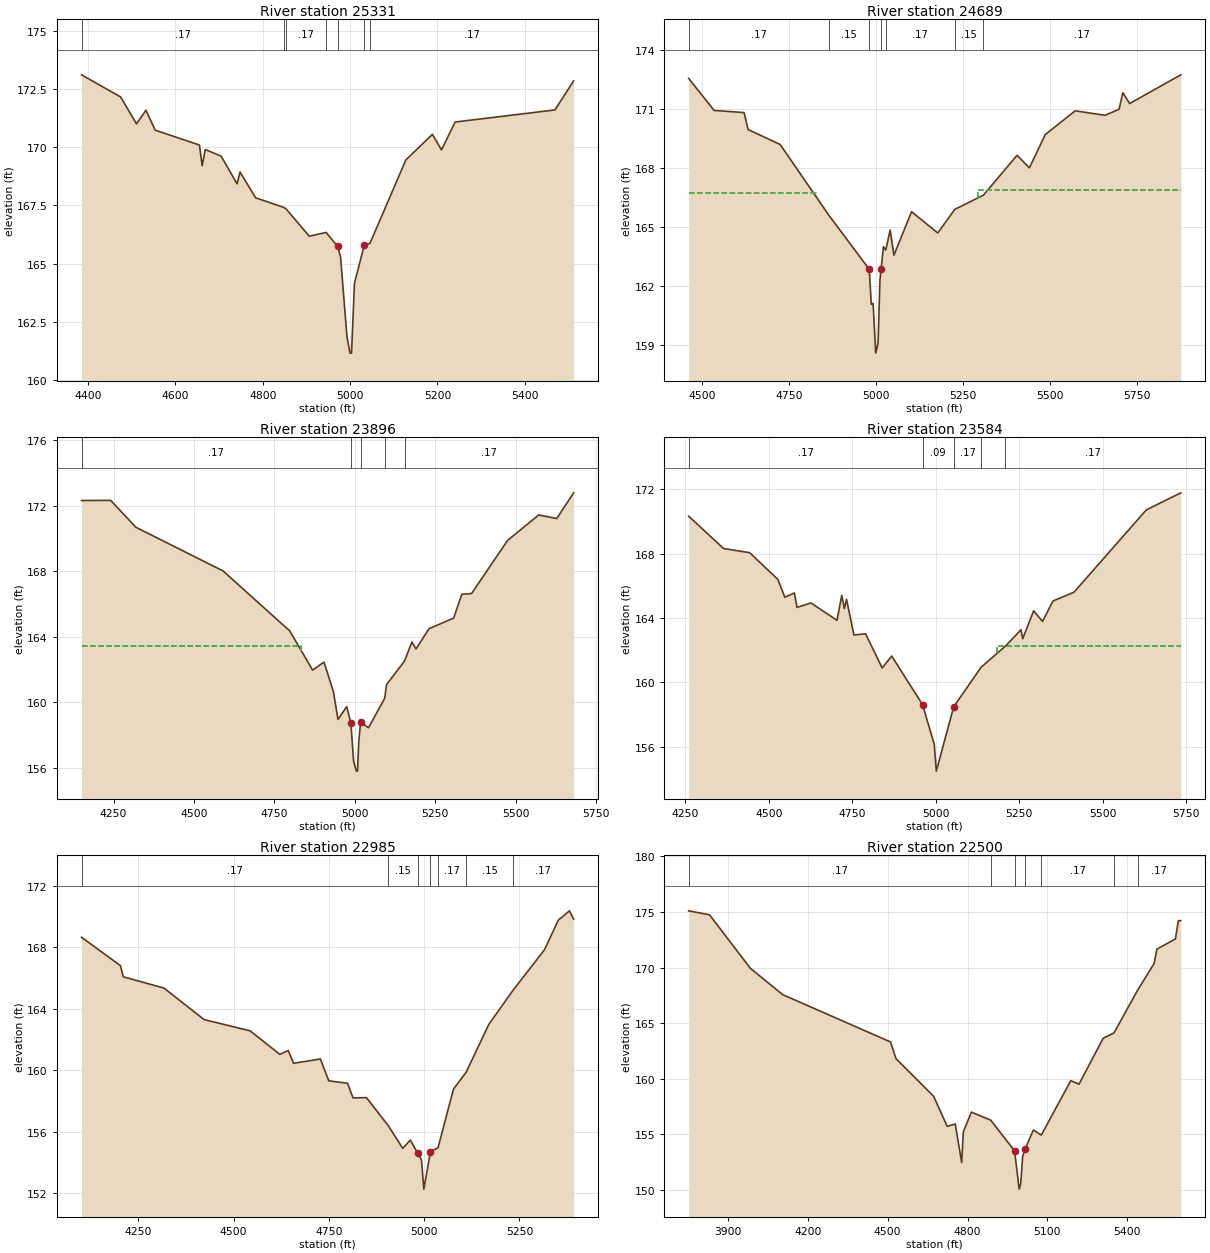
Type RM Length L Ch R = 1 ,25331   ,642,642,642
BEGIN DESCRIPTION:
SANDY BRANCH 50.0
END DESCRIPTION:
XS GIS Cut Line= 3
      3852988.23     10097134.93      3852643.01     10096630.68
      3852146.57     10096491.06
#Sta/Elev= 30
  4385.1  173.12  4474.6  172.17    4511  171.01  4532.7   171.6  4553.7  170.74
  4655.2   170.1  4661.3  169.21  4668.5  169.91  4704.9  169.62  4741.2  168.43
    4748  168.94  4783.8  167.83  4847.9  167.42  4853.2  167.36  4906.4  166.18
  4945.1  166.34  4971.5  165.74  4978.2  165.28  4992.9  161.86  4999.8  161.15
  5003.3  161.15    5010  164.15  5032.7  165.81  5045.5  165.87  5127.7  169.46
  5188.5  170.56  5209.3  169.89  5240.5  171.09    5469  171.61  5511.9  172.86
#Mann= 7 ,-1 , 0
  4385.1     .17       0  4847.9     .15       0  4853.2     .17       0
  4945.1     .15       0  4971.5     .09       0  5032.7     .15       0
  5045.5     .17       0
#XS Ineff= 2 , 0
       0    4748  168.94  5127.7       0  169.46
Permanent Ineff=
       F       F
Bank Sta=4971.5,5032.7
XS Rating Curve= 0 ,0
Exp/Cntr=0.3,0.1

Type RM Length L Ch R = 1 ,24689   ,793,793,793
BEGIN DESCRIPTION:
SANDY BRANCH 49.0
END DESCRIPTION:
XS GIS Cut Line= 3
      3853364.44      10096262.2      3852833.07     10096141.96
      3851972.41     10096010.15
#Sta/Elev= 30
  4460.4  172.54  4533.6  170.91  4619.9   170.8  4631.2  169.94  4723.5  169.18
  4862.8   165.6  4979.8  162.83  4985.7  161.05  4990.9   161.1  4998.4  158.57
  5005.2  159.07  5010.5  162.26 5014.04162.8629  5020.6  163.98  5027.2  163.81
  5039.9  164.83  5050.9  163.55  5101.5  165.76  5176.8  164.68  5225.9  165.88
  5308.1   166.6    5405  168.63  5440.4  167.99    5486  169.68  5572.2  170.89
  5657.9  170.66  5698.4  170.97  5709.1  171.81  5728.8  171.26  5875.9  172.72
#Mann= 7 ,-1 , 0
  4460.4     .17       0  4862.8     .15       0  4979.8     .09       0
 5014.04     .15       0  5027.2     .17       0  5225.9     .15       0
  5308.1     .17       0
#XS Ineff= 2 , 0
       0    4826  166.71  5293.7       0  166.85
Permanent Ineff=
       F       F
Bank Sta=4979.8,5014.04
XS Rating Curve= 0 ,0
Exp/Cntr=0.3,0.1

Type RM Length L Ch R = 1 ,23896   ,312,312,312
BEGIN DESCRIPTION:
SANDY BRANCH 48.0
END DESCRIPTION:
XS GIS Cut Line= 3
      3853590.04     10096195.25      3853074.44     10095519.94
      3852435.52     10095287.29
#Sta/Elev= 30
  4150.6  172.32  4241.2  172.33  4319.4  170.69  4590.4  168.02  4797.5  164.36
  4868.9  161.96  4904.2  162.45  4933.3  160.66  4947.8  158.95  4974.9  159.73
 4987.76158.7154  4996.4  156.38    5005  155.79  5008.5  155.79  5012.1  157.53
  5017.9  158.77  5042.6  158.44  5092.9  160.24  5098.5  161.07  5154.7  162.52
  5177.5  163.68  5190.2  163.25  5230.7  164.49  5307.2  165.14  5332.4  166.59
    5363  166.64  5474.7  169.88  5571.7  171.44  5627.6  171.22  5680.2  172.79
#Mann= 5 ,-1 , 0
  4150.6     .17       0 4987.76     .09       0  5017.9     .17       0
  5092.9     .15       0  5154.7     .17       0
#XS Ineff= 2 , 0
       0  4833.5  163.42  5177.5       0  163.68
Permanent Ineff=
       F       F
Bank Sta=4987.76,5017.9
XS Rating Curve= 0 ,0
Exp/Cntr=0.3,0.1

Type RM Length L Ch R = 1 ,23584   ,599,599,599
BEGIN DESCRIPTION:
SANDY BRANCH 47.0
END DESCRIPTION:
XS GIS Cut Line= 3
      3853673.76     10095851.73       3853169.6     10095248.69
      3852511.84     10095046.38
#Sta/Elev= 30
  4260.1  170.32  4364.7  168.31  4442.8  168.05  4527.4  166.39  4548.2  165.28
  4576.8  165.55  4584.6  164.65  4626.3  164.93  4704.4  163.85  4718.7   165.4
  4726.5  164.58    4733  165.15  4755.1  162.94  4790.2  163.01  4839.7  160.89
  4868.3  161.63  4960.7  158.61  4995.8  156.14  5001.9  154.48  5054.1  158.48
  5136.3  160.94  5208.7  162.24  5255.5  163.26  5260.8  162.71  5293.5  164.44
    5320  163.78  5351.4  165.05  5414.1  165.59    5631  170.71  5734.3  171.77
#Mann= 5 ,-1 , 0
  4260.1     .17       0  4960.7     .09       0  5054.1     .17       0
  5136.3     .15       0  5208.7     .17       0
#XS Ineff= 2 , 0
       0  4868.3  161.63    5184       0  162.27
Permanent Ineff=
       F       F
Bank Sta=4960.7,5054.1
XS Rating Curve= 0 ,0
Exp/Cntr=0.3,0.1

Type RM Length L Ch R = 1 ,22985   ,485,485,485
BEGIN DESCRIPTION:
SANDY BRANCH 46.0
END DESCRIPTION:
XS GIS Cut Line= 3
      3854137.32     10095575.71      3853588.72     10094933.37
      3853177.27     10094759.76
#Sta/Elev= 30
    4101  168.65    4203  166.81  4210.7  166.08  4317.2  165.35  4422.7   163.3
  4543.3  162.57  4621.3  161.04  4643.3  161.29  4657.5  160.46  4727.8  160.74
  4749.7  159.32  4799.1  159.16  4813.4  158.21  4848.5  158.23  4905.1  156.43
  4943.9  154.93  4963.7  155.47 4983.18154.6143  4992.9  154.19  4999.2  152.28
  5016.6  154.72  5036.5  154.97  5076.9  158.78  5110.4  159.89  5169.7  162.99
  5232.5  165.18  5315.7  167.84    5352  169.76  5381.2  170.37  5392.3  169.83
#Mann= 7 ,-1 , 0
    4101     .17       0  4905.1     .15       0 4983.18     .09       0
  5016.6     .15       0  5036.5     .17       0  5110.4     .15       0
  5232.5     .17       0
Bank Sta=4983.18,5016.6
XS Rating Curve= 0 ,0
Exp/Cntr=0.3,0.1

Type RM Length L Ch R = 1 ,22500   ,528,528,528
BEGIN DESCRIPTION:
SANDY BRANCH 45.0
END DESCRIPTION:
XS GIS Cut Line= 3
      3855046.59     10094749.19       3853814.9     10094550.57
      3853218.49     10094474.02
#Sta/Elev= 30
  3752.4   175.1  3830.9  174.74  3984.1  169.93  4105.6  167.56  4510.8   163.3
  4531.1  161.81  4672.9  158.41  4723.5  155.71  4753.9  155.92  4778.1  152.45
  4784.3  155.22  4814.7  156.99  4887.4  156.26  4976.7  153.51  4994.2  150.06
    5000  150.56  5007.1  152.99  5017.2  153.71  5047.4  155.38  5077.1  154.92
    5188  159.82  5218.8   159.5  5309.6  163.63  5350.4  164.12  5439.6  167.98
  5501.1  170.36  5511.4  171.65    5581  172.57  5591.9   174.2  5601.3  174.22
#Mann= 7 ,-1 , 0
  3752.4     .17       0  4887.4     .15       0  4976.7     .09       0
  5017.2     .15       0  5077.1     .17       0  5350.4     .11       0
  5439.6     .17       0
#XS Ineff= 2 , 0
       0  4672.9  158.41               0
Permanent Ineff=
       F       F
Bank Sta=4976.7,5017.2
XS Rating Curve= 0 ,0
Exp/Cntr=0.3,0.1

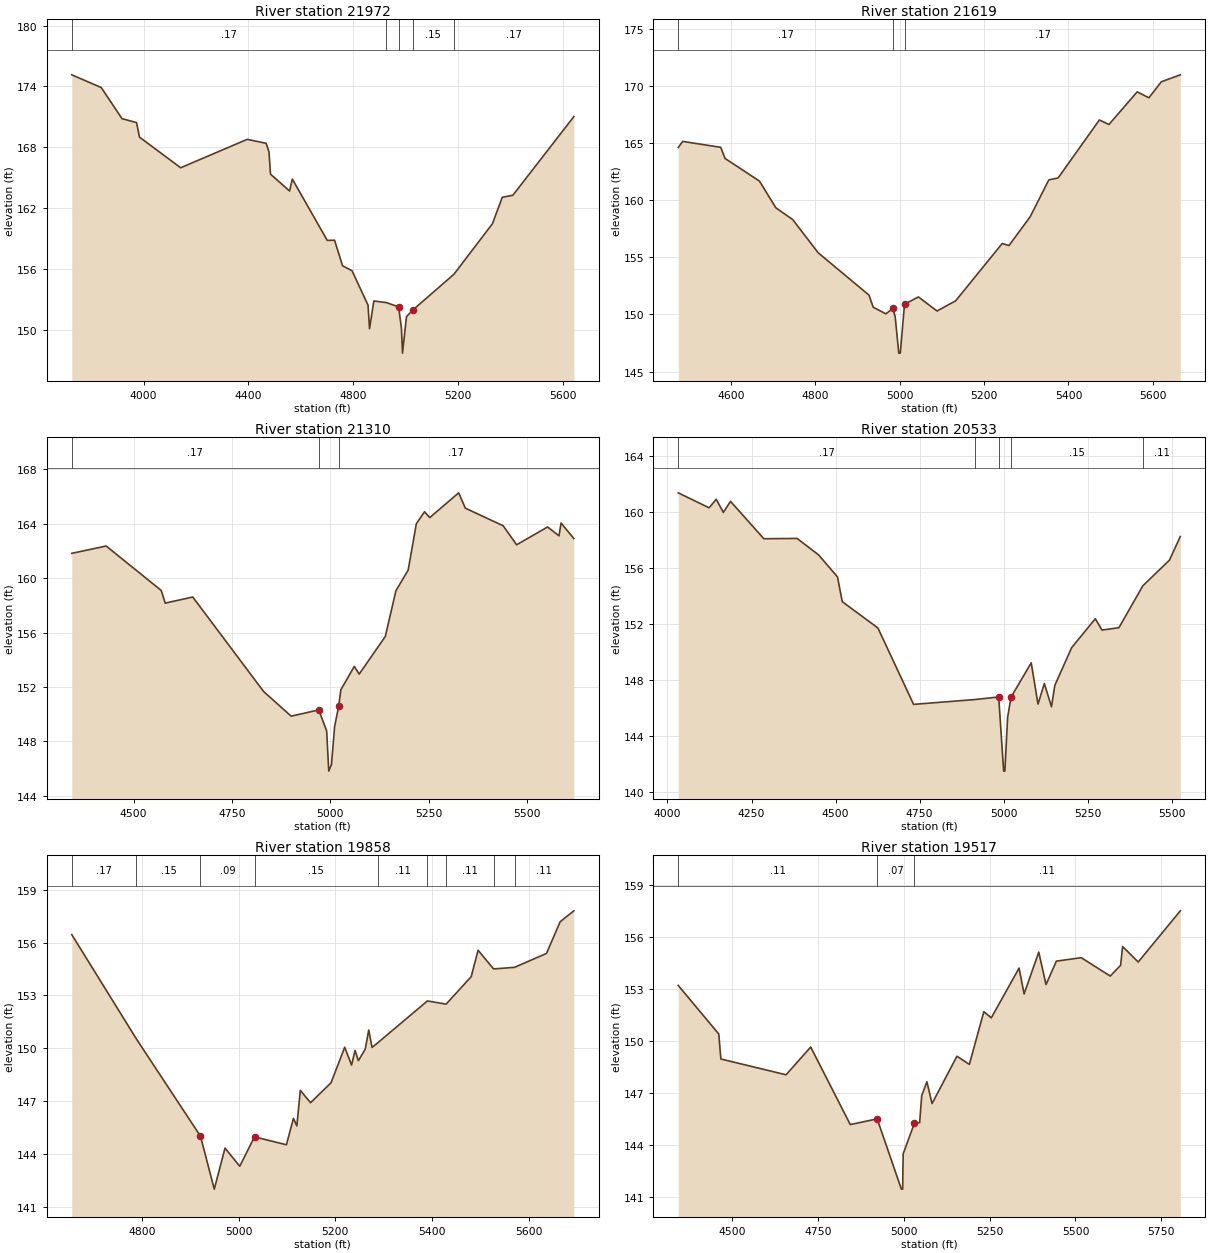
Type RM Length L Ch R = 1 ,21972   ,353,353,353
BEGIN DESCRIPTION:
SANDY BRANCH 44.0
END DESCRIPTION:
XS GIS Cut Line= 3
      3855067.89     10094661.09      3853928.57     10094079.05
      3853296.64     10094151.97
#Sta/Elev= 30
  3726.3  175.15  3838.6   173.9    3918  170.83  3973.4  170.44  3984.7  169.01
  4141.8  165.99  4395.6  168.79  4467.9   168.4  4478.7  167.56  4484.5  165.36
  4557.3   163.7  4567.8  164.87  4701.1  158.83  4728.9  158.85  4759.4  156.33
  4795.6  155.84  4856.6  152.45  4862.2  150.12  4878.8  152.86  4926.6   152.7
  4973.3  152.28    4984  150.16  4988.1  147.72  5003.3  151.32  5026.5  151.95
  5184.2  155.49  5331.1  160.47  5368.8  163.08  5409.1  163.28  5641.8  171.03
#Mann= 5 ,-1 , 0
  3726.3     .17       0  4926.6     .15       0  4973.3     .09       0
  5026.5     .15       0  5184.2     .17       0
Bank Sta=4973.3,5026.5
XS Rating Curve= 0 ,0
Exp/Cntr=0.3,0.1

Type RM Length L Ch R = 1 ,21619   ,309,309,309
BEGIN DESCRIPTION:
SANDY BRANCH 43.0
END DESCRIPTION:
XS GIS Cut Line= 3
      3854428.28     10093699.44      3853925.09     10093743.98
      3853317.85     10094061.07
#Sta/Elev= 30
  4474.9  164.61  4485.4  165.15  4575.7  164.63  4585.8  163.66  4667.3  161.68
  4706.2  159.34  4746.4   158.3  4806.6   155.4  4927.1  151.69  4937.1  150.63
  4967.2  150.05  4983.6  150.52  4989.2  149.79  4997.7  146.61  5001.3  146.61
  5011.3  150.89  5044.2  151.53  5088.4   150.3  5132.5  151.19  5242.9  156.21
    5259  156.03  5309.2  158.55  5353.4  161.78  5375.4  161.95  5473.3  167.03
  5495.9  166.63  5562.9  169.49  5590.6  168.97    5620  170.37  5665.1  170.98
#Mann= 3 , 0 , 0
  4474.9     .17       0  4983.6     .09       0  5011.3     .17       0
#XS Ineff= 2 , 0
       0                  5242.9       0  156.21
Permanent Ineff=
       F       F
Bank Sta=4983.6,5011.3
XS Rating Curve= 0 ,0
Exp/Cntr=0.3,0.1

Type RM Length L Ch R = 1 ,21310   ,777,777,777
BEGIN DESCRIPTION:
SANDY BRANCH 42.0
END DESCRIPTION:
XS GIS Cut Line= 3
      3854435.19     10093532.78      3853778.42     10093508.85
      3853182.24     10093674.99
#Sta/Elev= 30
  4342.8  161.83  4430.2  162.37  4570.3   159.1  4580.3  158.17  4650.3  158.62
  4830.5  151.67  4900.5  149.86  4970.6  150.32  4990.6  148.78    4996  145.82
  5002.9  146.32    5011  149.12  5021.4  150.62  5026.7   151.8  5060.9  153.52
  5073.3  152.95  5139.7  155.72  5166.7  159.08  5197.8   160.6  5218.6  164.01
  5239.4  164.89  5252.7  164.46  5326.2  166.28  5343.2  165.15  5439.2  163.86
  5473.4  162.46  5552.2  163.77  5581.2  163.12  5586.4  164.06  5618.9  162.92
#Mann= 3 , 0 , 0
  4342.8     .17       0  4970.6     .09       0  5021.4     .17       0
#XS Ineff= 2 , 0
       0                  5060.9       0  153.52
Permanent Ineff=
       F       F
Bank Sta=4970.6,5021.4
XS Rating Curve= 0 ,0
Exp/Cntr=0.3,0.1

Type RM Length L Ch R = 1 ,20533   ,675,675,675
BEGIN DESCRIPTION:
SANDY BRANCH 41.0
END DESCRIPTION:
XS GIS Cut Line= 3
      3854520.09     10093518.66      3853884.64      10092891.9
      3853285.69     10092934.44
#Sta/Elev= 30
  4032.1  161.35  4123.9  160.28  4145.1  160.89  4166.3  159.95  4187.6  160.74
  4286.6  158.07  4385.6  158.09  4449.2  156.92  4505.7  155.34  4519.9  153.57
  4625.9  151.69    4732  146.23    4916  146.58    4985  146.76  4999.8  141.46
  5003.4  141.46  5011.6  145.31  5021.7  146.75  5081.8   149.2  5101.9  146.25
  5120.8  147.72    5142  146.06    5152  147.59  5202.1  150.29  5272.3  152.35
  5292.3  151.54  5342.5  151.71  5413.9  154.71  5492.9  156.54  5525.1  158.23
#Mann= 5 ,-1 , 0
  4032.1     .17       0    4916     .15       0    4985     .09       0
  5021.7     .15       0  5413.9     .11       0
Bank Sta=4985,5021.7
XS Rating Curve= 0 ,0
Exp/Cntr=0.3,0.1

Type RM Length L Ch R = 1 ,19858   ,341,341,341
BEGIN DESCRIPTION:
SANDY BRANCH 40.0
END DESCRIPTION:
XS GIS Cut Line= 3
      3854179.75     10092406.66      3853740.54     10092486.52
      3853312.38     10092895.62
#Sta/Elev= 30
  4654.9  156.46  4788.4  150.54  4921.1  145.01  4949.7     142  4971.9  144.33
  5002.4   143.3  5032.9  144.97  5098.9  144.52  5113.5  146.02  5120.5  145.59
  5127.7  147.61  5148.8  146.91  5191.2  148.04  5219.5  150.06  5233.7  149.05
  5240.9  149.88  5247.8   149.3    5262  149.95  5269.2  151.04  5276.1  150.05
  5287.7  150.31  5390.6  152.69  5429.3  152.51  5481.2  154.07  5495.4  155.57
  5527.5  154.51  5570.9   154.6  5636.9  155.39  5665.2  157.19  5693.5  157.81
#Mann= 9 ,-1 , 0
  4654.9     .17       0  4788.4     .15       0  4921.1     .09       0
  5032.9     .15       0  5287.7     .11       0  5390.6     .15       0
  5429.3     .11       0  5527.5     .15       0  5570.9     .11       0
#XS Ineff= 2 , 0
       0                  5219.5       0  150.06
Permanent Ineff=
       F       F
Bank Sta=4921.1,5032.9
XS Rating Curve= 0 ,0
Exp/Cntr=0.3,0.1

Type RM Length L Ch R = 1 ,19517   ,151,151,151
BEGIN DESCRIPTION:
SANDY BRANCH 39.0
END DESCRIPTION:
XS GIS Cut Line= 3
      3854098.38     10091648.44      3853739.24     10092196.37
      3853297.85     10092871.91
#Sta/Elev= 30
  4343.2  153.21  4461.3  150.41  4467.3  148.97  4657.2  148.06    4729  149.66
  4844.2  145.19  4922.5  145.52    4993  141.47  4996.8  141.47  4998.2   143.5
  5031.1  145.28  5046.2   145.3  5052.2  146.85  5067.3  147.66  5082.4   146.4
  5154.8  149.13    5191  148.66  5233.2   151.7  5254.8  151.34  5335.8  154.21
  5350.4  152.72  5393.1  155.13  5414.2  153.26  5444.4  154.61  5516.8  154.81
  5601.2  153.75  5631.4  154.37  5637.3  155.45  5682.7  154.56  5805.3  157.51
#Mann= 3 , 0 , 0
  4343.2     .11       0  4922.5     .07       0  5031.1     .11       0
#XS Ineff= 2 , 0
       0                  5067.3       0  147.66
Permanent Ineff=
       F       F
Bank Sta=4922.5,5031.1
XS Rating Curve= 0 ,0
Exp/Cntr=0.3,0.1

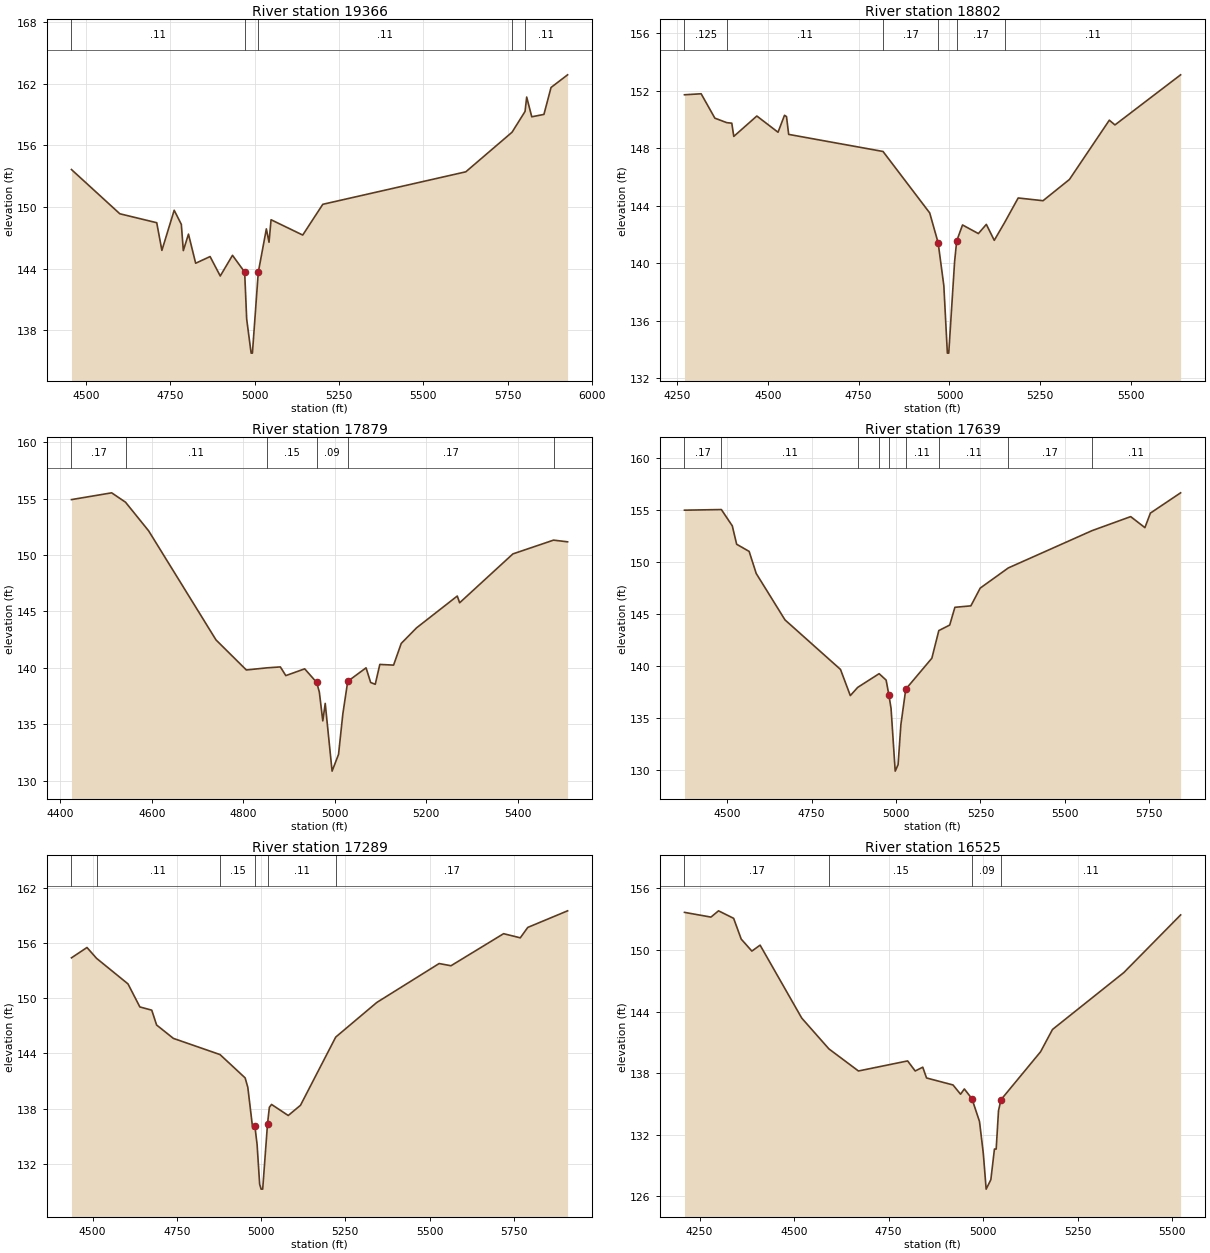
Type RM Length L Ch R = 1 ,19366   ,564,564,564
BEGIN DESCRIPTION:
SANDY BRANCH 38.0
END DESCRIPTION:
XS GIS Cut Line= 3
      3853918.08     10091642.81      3853670.32     10092037.09
      3853115.63     10092876.87
#Sta/Elev= 30
  4456.2  153.64  4599.7  149.34  4709.2  148.47  4724.5  145.78    4761  149.68
  4782.2  148.31  4788.1  145.76  4803.4  147.36  4824.7  144.53  4867.5  145.18
  4897.7  143.29    4934   145.3  4970.1  143.67  4976.1   139.1  4989.3  135.79
  4993.1  135.79 5010.48143.6416  5034.5  147.87  5042.4  146.57  5048.4  148.76
  5142.4  147.27  5201.9  150.26  5626.3  153.42  5763.5  157.27  5802.1  159.29
  5806.9  160.69    5822  158.77  5858.1     159  5879.2  161.62  5928.3  162.85
#Mann= 5 ,-1 , 0
  4456.2     .11       0  4970.1     .09       0 5010.48     .11       0
  5763.5     .17       0  5802.1     .11       0
#XS Ineff= 4 ,-1
  4803.4    4761  147.36    4761  4572.3  149.68  5034.5  5048.4  147.87
  5048.4  5178.3  148.76
Permanent Ineff=
       F       F       F       F
Bank Sta=4970.1,5010.48
XS Rating Curve= 0 ,0
Exp/Cntr=0.3,0.1

Type RM Length L Ch R = 1 ,18802   ,923,923,923
BEGIN DESCRIPTION:
SANDY BRANCH 37.0
END DESCRIPTION:
XS GIS Cut Line= 3
       3853626.6      10090999.2      3853331.47     10091663.24
       3853025.5     10092223.11
#Sta/Elev= 30
  4271.1  151.73  4316.9   151.8  4354.7   150.1  4387.2  149.79  4401.2  149.75
  4406.7  148.83  4470.1  150.25  4528.4  149.12  4546.2   150.3  4551.7  150.21
  4557.7  148.97  4817.2  147.78  4945.6   143.5  4968.9  141.41  4984.5  138.43
  4994.2  133.73    4998  133.73  5014.1   140.1  5019.8  141.54  5035.9  142.66
  5079.5  142.06  5101.4   142.7  5123.2  141.59  5151.7  142.83    5189  144.54
  5257.4  144.35    5330  145.83  5439.7  149.96  5455.2  149.63  5635.8  153.12
#Mann= 6 ,-1 , 0
  4271.1    .125       0  4387.2     .11       0  4817.2     .17       0
  4968.9     .09       0  5019.8     .17       0  5151.7     .11       0
Bank Sta=4968.9,5019.8
XS Rating Curve= 0 ,0
Exp/Cntr=0.3,0.1

Type RM Length L Ch R = 1 ,17879   ,240,240,240
BEGIN DESCRIPTION:
SANDY BRANCH 36.0
END DESCRIPTION:
XS GIS Cut Line= 3
      3852962.56     10090782.14      3852764.63     10091322.85
      3852723.84     10091830.32
#Sta/Elev= 30
  4424.3  154.91  4512.2  155.51  4542.5  154.68  4593.1  152.14  4740.4  142.48
  4806.7  139.82  4852.3  140.01  4881.1  140.09    4893  139.32  4934.3  139.92
 4960.41138.7232  4966.3  137.87  4973.9  135.31  4979.2  136.86  4994.2  130.86
  5008.3  132.34  5017.8  135.95  5028.4  138.81  5068.5  140.01  5078.6  138.71
  5088.6  138.55  5098.6  140.31  5128.7  140.25  5145.4  142.17  5178.9  143.55
    5268  146.37  5273.1  145.77  5389.6   150.1  5478.5  151.32  5509.2  151.17
#Mann= 6 ,-1 , 0
  4424.3     .17       0  4542.5     .11       0  4852.3     .15       0
 4960.41     .09       0  5028.4     .17       0  5478.5     .11       0
Bank Sta=4960.41,5028.4
XS Rating Curve= 0 ,0
Exp/Cntr=0.3,0.1

Type RM Length L Ch R = 1 ,17639   ,350,350,350
BEGIN DESCRIPTION:
SANDY BRANCH 35.0
END DESCRIPTION:
XS GIS Cut Line= 3
      3852922.16      10090768.2      3852446.93     10091393.17
       3852288.1     10092058.02
#Sta/Elev= 30
  4373.8  155.01    4483  155.07  4515.3   153.5  4528.2  151.73  4565.2  151.04
  4586.1  148.92  4671.3  144.45  4835.6  139.68  4864.7  137.16  4886.5  137.95
    4950  139.27  4970.8  138.65    4979  137.19  4985.3  135.93  4997.6  129.89
  5006.1  130.51  5014.4  134.36  5028.9  137.78  5106.1  140.76  5126.7  143.42
  5158.9  143.95  5174.3  145.66  5221.6   145.8  5249.3  147.51  5332.4  149.45
  5580.3  153.04  5694.7  154.39  5736.8  153.33  5753.1  154.73  5842.5  156.68
#Mann= 9 ,-1 , 0
  4373.8     .17       0    4483     .11       0  4886.5     .15       0
    4950     .11       0    4979     .09       0  5028.9     .11       0
  5126.7     .11       0  5332.4     .17       0  5580.3     .11       0
Bank Sta=4979,5028.9
XS Rating Curve= 0 ,0
Exp/Cntr=0.3,0.1

Type RM Length L Ch R = 1 ,17289   ,764,764,764
BEGIN DESCRIPTION:
SANDY BRANCH 34.0
END DESCRIPTION:
XS GIS Cut Line= 3
      3852829.77     10090708.25      3852390.94     10091055.93
      3851688.67     10091638.94
#Sta/Elev= 30
  4437.1  154.37  4483.1  155.49  4511.7  154.31  4604.9  151.54  4640.1  149.04
  4675.4  148.69  4689.8  147.08  4739.5  145.63  4878.1  143.87  4952.6  141.34
  4960.6  140.31  4975.1  135.83  4981.4  136.13  4988.1  134.11  4995.7   129.8
    5000  129.27  5004.7  129.27 5018.98136.3383  5024.5  138.15    5031  138.46
  5080.5  137.26  5116.9  138.37  5221.5  145.77  5343.5  149.53  5528.4  153.75
  5563.6  153.51  5719.8  156.99  5769.3  156.54  5791.5  157.67  5909.7  159.47
#Mann= 6 ,-1 , 0
  4437.1     .17       0  4511.7     .11       0  4878.1     .15       0
  4981.4     .09       0 5018.98     .11       0  5221.5     .17       0
Bank Sta=4981.4,5018.98
XS Rating Curve= 0 ,0
Exp/Cntr=0.3,0.1

Type RM Length L Ch R = 1 ,16525   ,386,386,386
BEGIN DESCRIPTION:
SANDY BRANCH 33.0
END DESCRIPTION:
XS GIS Cut Line= 3
      3852767.82     10090561.07      3851943.78     10090538.35
       3851481.6      10090694.5
#Sta/Elev= 30
  4210.3  153.65  4280.3  153.19  4300.3   153.8  4340.3  153.07  4360.3  151.05
  4388.5  149.88  4410.3  150.46  4520.4  143.36  4592.3  140.36  4670.4  138.21
  4800.5  139.19  4820.5  138.21  4840.5  138.58  4850.5  137.53  4920.5  136.85
  4940.5  135.95  4950.5  136.46  4970.6  135.51  4990.6  133.29  5000.6  130.21
  5008.2  126.71  5020.6  127.63  5030.1  130.61  5034.7  130.61  5040.9  134.36
 5047.51135.4201  5152.1  140.08  5183.6  142.25  5372.3  147.79  5522.5   153.4
#Mann= 4 ,-1 , 0
  4210.3     .17       0  4592.3     .15       0  4970.6     .09       0
 5047.51     .11       0
Bank Sta=4970.6,5047.51
XS Rating Curve= 0 ,0
Exp/Cntr=0.3,0.1

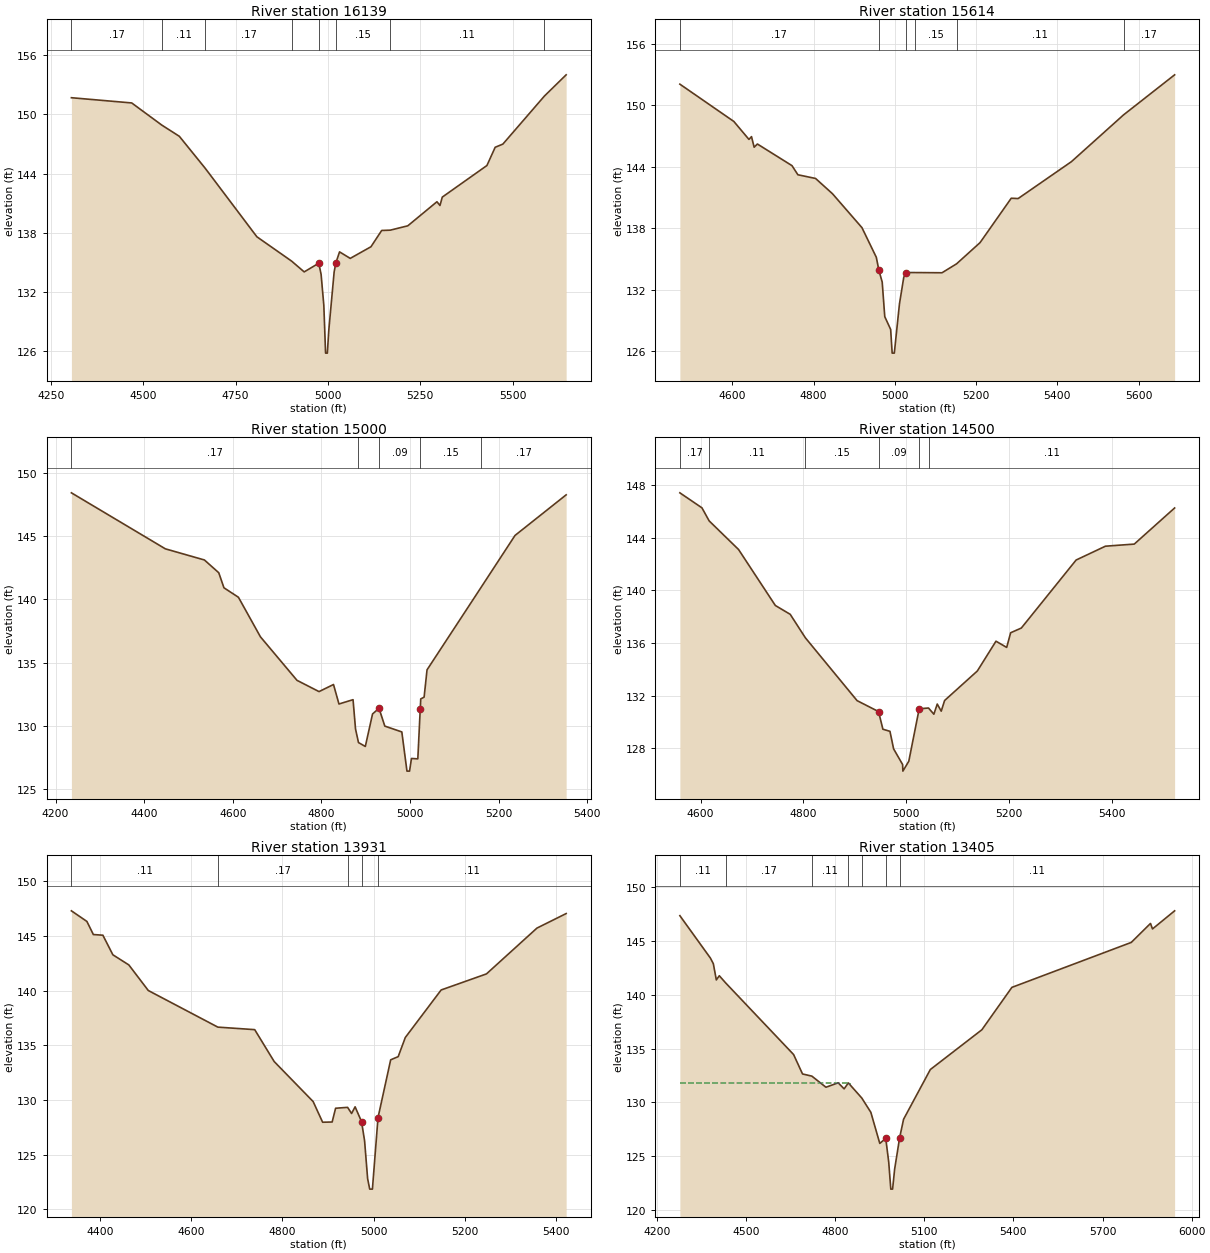
Type RM Length L Ch R = 1 ,16139   ,525,525,525
BEGIN DESCRIPTION:
SANDY BRANCH 32.0
END DESCRIPTION:
XS GIS Cut Line= 3
      3852113.06      10089572.6      3851916.87     10090188.96
      3851367.82     10090611.09
#Sta/Elev= 30
  4305.7   151.7    4469  151.17  4550.3  148.93  4597.9  147.79  4668.2  144.54
  4807.8  137.61    4902  135.14  4935.9  134.05  4975.4  134.93  4981.7   133.8
  4989.1  130.65  4993.8  125.82  4998.6  125.82  5002.5  128.13    5017  134.04
 5021.76134.9745  5031.6  136.08  5060.6  135.42  5116.7   136.6  5145.7  138.25
  5168.9  138.28  5216.4  138.72  5295.3  141.16  5303.5  140.78  5309.8  141.63
  5430.6  144.83    5453  146.68  5473.8     147  5586.3  151.87  5645.1  154.02
#Mann= 8 ,-1 , 0
  4305.7     .17       0  4550.3     .11       0  4668.2     .17       0
    4902     .15       0  4975.4     .09       0 5021.76     .15       0
  5168.9     .11       0  5586.3     .17       0
Bank Sta=4975.4,5021.76
XS Rating Curve= 0 ,0
Exp/Cntr=0.3,0.1

Type RM Length L Ch R = 1 ,15614   ,614,614,614
BEGIN DESCRIPTION:
SANDY BRANCH 31.0
END DESCRIPTION:
XS GIS Cut Line= 3
      3852012.32     10089588.29      3851590.48     10089914.65
      3851367.86     10090561.04
#Sta/Elev= 30
  4471.3  152.07  4604.1  148.43  4641.2  146.68  4647.5  146.95    4654  145.92
    4662  146.23  4747.1  144.12  4761.6  143.23  4805.1  142.87  4846.7  141.38
  4919.2  138.07  4954.5  135.18  4960.8  133.92    4969  132.76  4975.3  129.39
  4989.8  128.14  4993.5  125.83  4998.8  125.83  5011.4  130.62    5022  133.22
  5027.7  133.69  5049.3  133.69  5116.1  133.67  5151.9  134.54  5209.7  136.61
  5286.4  140.94  5303.4  140.91  5434.5  144.51  5562.6  149.07  5688.3  152.98
#Mann= 6 ,-1 , 0
  4471.3     .17       0  4960.8     .09       0  5027.7     .17       0
  5049.3     .15       0  5151.9     .11       0  5562.6     .17       0
Bank Sta=4960.8,5027.7
XS Rating Curve= 0 ,0
Exp/Cntr=0.3,0.1

Type RM Length L Ch R = 1 ,15000   ,500,500,500
BEGIN DESCRIPTION:
SANDY BRANCH 30.0
END DESCRIPTION:
XS GIS Cut Line= 3
      3851560.99      10088846.9      3851204.57     10089522.89
      3850974.15     10089789.66
#Sta/Elev= 30
  4235.8  148.42  4447.9  143.99    4536  143.11  4568.4   142.1  4580.1  140.91
  4612.8  140.16  4662.5  137.03    4745  133.59  4794.7   132.7  4827.4  133.26
  4839.7  131.72  4871.5  132.06  4877.1  129.74  4883.8  128.67  4899.2  128.36
  4915.5  130.93  4930.1  131.38  4943.2  129.97  4981.6  129.51  4993.2  126.41
    4999  126.41  5003.4  127.41  5017.7  127.38 5023.23131.3516  5024.3  132.12
  5031.9  132.26  5038.5  134.42  5159.7   140.9  5237.1  145.05  5352.5  148.26
#Mann= 5 ,-1 , 0
  4235.8     .17       0  4883.8     .15       0  4930.1     .09       0
 5023.23     .15       0  5159.7     .17       0
Bank Sta=4930.1,5023.23
XS Rating Curve= 0 ,0
Exp/Cntr=0.3,0.1

Type RM Length L Ch R = 1 ,14500   ,569,569,569
BEGIN DESCRIPTION:
SANDY BRANCH 29.0
END DESCRIPTION:
XS GIS Cut Line= 3
      3851317.86     10088761.06      3851058.81     10089116.97
      3850717.87     10089511.05
#Sta/Elev= 30
  4559.8   147.4  4602.7  146.26  4616.7  145.27  4673.8   143.1  4745.3  138.85
  4774.2  138.18  4803.6   136.4  4904.1  131.63  4945.8   130.8  4954.3  129.46
    4968   129.3  4975.1  127.97  4992.6  126.78  4993.1  126.28  5004.6  127.03
  5024.8  131.01  5042.9  131.07  5053.3   130.6  5059.9  131.37  5067.6  130.83
  5074.2  131.64  5137.8  133.88    5174  136.14  5194.8  135.67  5202.5  136.78
  5223.3  137.14  5329.7   142.3  5386.7  143.35  5442.7  143.51  5521.1  146.25
#Mann= 6 ,-1 , 0
  4559.8     .17       0  4616.7     .11       0  4803.6     .15       0
  4945.8     .09       0  5024.8     .17       0  5042.9     .11       0
#XS Ineff= 2 , 0
       0                    5174       0  136.14
Permanent Ineff=
       F       F
Bank Sta=4945.8,5024.8
XS Rating Curve= 0 ,0
Exp/Cntr=0.3,0.1

Type RM Length L Ch R = 1 ,13931   ,526,526,526
BEGIN DESCRIPTION:
SANDY BRANCH 28.0
END DESCRIPTION:
XS GIS Cut Line= 3
      3851048.84     10088484.08      3850548.81     10088918.12
      3850354.36     10089294.87
#Sta/Elev= 30
  4336.7  147.31  4370.7  146.34  4384.9  145.14  4405.8  145.08  4427.7  143.29
  4462.8  142.36  4505.5  140.02  4658.2  136.67  4739.1  136.44  4781.9  133.52
  4867.4  129.86  4888.2  127.97  4909.1  127.99  4916.7  129.25    4943  129.33
  4951.8  128.77  4959.5  129.38  4973.6  128.03  4980.3  126.28    4987   122.8
  4991.6  121.85  4997.5  121.85  5009.8  128.39  5037.6  133.68  5054.1  133.97
  5069.7  135.72  5148.4  140.07  5247.9  141.54  5358.7  145.73  5422.8  147.06
#Mann= 5 ,-1 , 0
  4336.7     .11       0  4658.2     .17       0    4943     .11       0
  4973.6     .09       0  5009.8     .11       0
Bank Sta=4973.6,5009.8
XS Rating Curve= 0 ,0
Exp/Cntr=0.3,0.1

Type RM Length L Ch R = 1 ,13405   ,333,333,333
BEGIN DESCRIPTION:
SANDY BRANCH 27.0
END DESCRIPTION:
XS GIS Cut Line= 3
      3851050.53       10088465.      3850196.38      10088484.1
      3849730.41     10089147.54
#Sta/Elev= 30
  4277.6  147.32  4380.3  143.39  4390.3  142.86  4400.3  141.36  4410.3  141.75
  4431.8  141.08  4660.4  134.44  4690.4  132.64  4721.8  132.44  4769.2  131.41
  4810.4  131.82  4830.4  131.26  4844.7  131.81  4889.8  130.41  4920.4  129.08
  4950.4   126.2  4970.5  126.66  4980.5  124.47  4987.5  121.96  4993.5  121.96
  5000.5  123.83 5017.21126.7221  5030.5  128.44  5120.5  133.05    5294  136.74
    5395  140.67  5796.8  144.84  5861.5   146.6  5868.2  146.09  5942.7  147.77
#Mann= 7 ,-1 , 0
  4277.6     .11       0  4431.8     .17       0  4721.8     .11       0
  4844.7     .17       0  4889.8     .11       0  4970.5     .09       0
 5017.21     .11       0
#XS Ineff= 2 , 0
       0  4850.4  131.83               0
Permanent Ineff=
       F       F
Bank Sta=4970.5,5017.21
XS Rating Curve= 0 ,0
Exp/Cntr=0.3,0.1

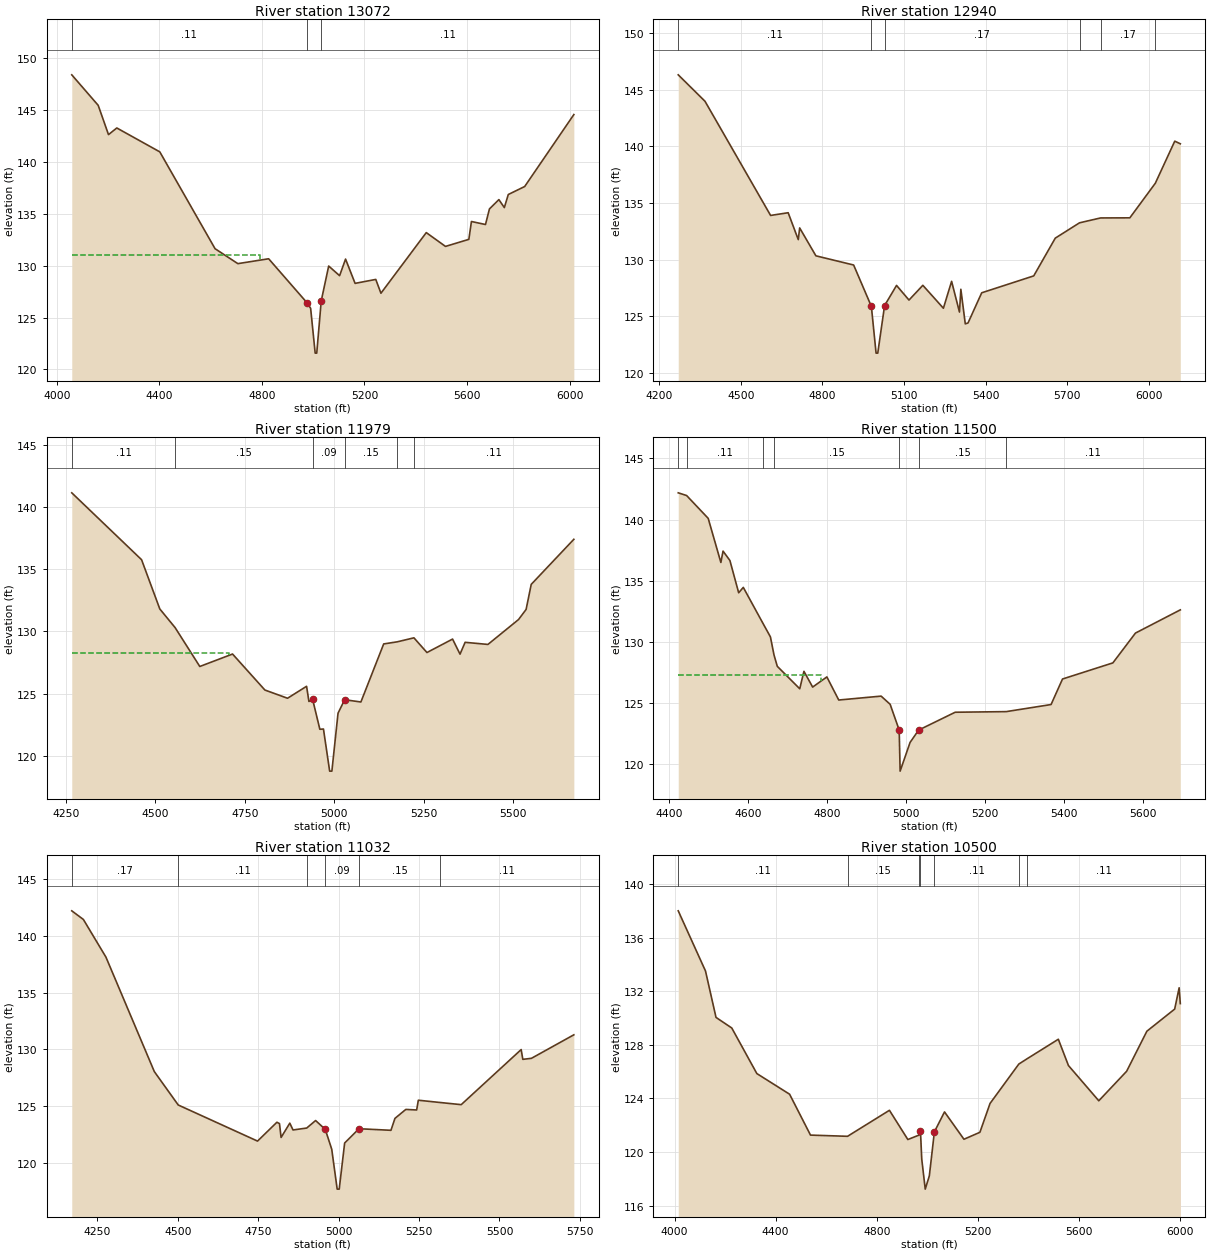
Type RM Length L Ch R = 1 ,13072   ,132,132,132
BEGIN DESCRIPTION:
SANDY BRANCH 26.0
END DESCRIPTION:
XS GIS Cut Line= 4
      3851097.45     10088444.17      3850126.94     10088183.75
      3849540.13      10088109.1        3849232.     10088297.78
#Sta/Elev= 30
  4058.7  148.38  4161.8  145.44  4201.9  142.62  4234.3  143.26  4401.9  140.96
  4617.4  131.63  4706.4  130.19  4826.4  130.66    4976  126.42  4990.1  125.89
  5007.8  121.57  5013.9  121.57  5031.5  126.61  5060.5  129.96    5103  129.03
  5126.3  130.63  5163.4  128.29  5244.1  128.67  5264.2  127.34    5441  133.18
  5515.9  131.85    5607  132.53  5617.1  134.25  5671.9  133.96  5687.3  135.46
  5724.1  136.36  5745.4  135.59  5760.8  136.85  5824.7  137.62  6016.4  144.55
#Mann= 3 , 0 , 0
  4058.7     .11       0    4976     .09       0  5031.5     .11       0
#XS Ineff= 2 , 0
       0  4793.4  131.04  5126.3       0  130.63
Permanent Ineff=
       F       F
Bank Sta=4976,5031.5
XS Rating Curve= 0 ,0
Exp/Cntr=0.3,0.1

Type RM Length L Ch R = 1 ,12940   ,961,961,961
BEGIN DESCRIPTION:
SANDY BRANCH 25.0
END DESCRIPTION:
XS GIS Cut Line= 5
      3850894.29     10088213.26      3849960.27     10088025.76
      3849458.54     10087968.47      3849236.31     10088058.75
      3849123.43       10088156.
#Sta/Elev= 30
  4269.9  146.31  4368.3  143.98  4609.6  133.91  4674.2  134.15  4711.4  131.78
  4716.5  132.81  4776.2  130.35    4915  129.54  4980.2  125.89  4997.5  121.77
  5003.7  121.77 5028.84125.9654  5072.8  127.74  5118.6  126.45  5169.5  127.75
  5245.1  125.73  5275.3   128.1  5304.2  125.39  5309.3   127.4  5325.6  124.35
  5335.7  124.43    5386  127.09  5577.3  128.58  5656.6  131.91  5745.7  133.26
  5823.1  133.69  5930.8   133.7  6024.5  136.75    6096  140.46  6116.4  140.23
#Mann= 6 ,-1 , 0
  4269.9     .11       0  4980.2     .09       0 5028.84     .17       0
  5745.7     .11       0  5823.1     .17       0  6024.5     .11       0
Bank Sta=4980.2,5028.84
XS Rating Curve= 0 ,0
Exp/Cntr=0.3,0.1

Type RM Length L Ch R = 1 ,11979   ,479,479,479
BEGIN DESCRIPTION:
SANDY BRANCH 24.0
END DESCRIPTION:
XS GIS Cut Line= 3
      3850239.79     10087378.19      3849462.01     10087520.55
      3849067.92     10087989.29
#Sta/Elev= 30
  4266.5  141.13  4461.6  135.76  4512.5  131.81  4555.3  130.31  4624.3  127.19
  4715.8  128.19  4806.2   125.3  4869.5  124.64  4922.7   125.6  4929.3  124.38
  4939.4  124.57  4959.8  122.15  4969.9  122.17  4987.2  118.79  4993.4  118.79
  5010.6  123.44  5029.1  124.52  5074.5  124.34  5138.2     129  5176.2  129.17
  5222.7  129.49  5259.1  128.31  5330.7  129.39  5351.5  128.18  5365.8  129.13
  5429.5  128.96  5515.1  130.96  5536.2  131.77  5550.5  133.78  5669.6   137.4
#Mann= 6 ,-1 , 0
  4266.5     .11       0  4555.3     .15       0  4939.4     .09       0
  5029.1     .15       0  5176.2     .17       0  5222.7     .11       0
#XS Ineff= 2 , 0
       0  4705.6  128.26  5138.2       0     129
Permanent Ineff=
       F       F
Bank Sta=4939.4,5029.1
XS Rating Curve= 0 ,0
Exp/Cntr=0.3,0.1

Type RM Length L Ch R = 1 ,11500   ,468,468,468
BEGIN DESCRIPTION:
SANDY BRANCH 23.0
END DESCRIPTION:
XS GIS Cut Line= 3
       3849996.7     10086848.69      3849472.85     10087091.77
      3848922.48     10087515.03
#Sta/Elev= 30
  4422.5  142.19  4443.7  141.97  4498.4   140.1  4530.5  136.49    4536  137.42
  4553.4  136.65  4575.6  134.01  4587.3  134.45  4637.4  131.49    4656   130.4
  4665.1  128.92  4673.4  127.99  4730.3  126.15  4740.9  127.58    4763  126.29
    4799  127.12  4829.1  125.23  4936.4  125.55  4959.3  124.88  4982.2  122.77
  4984.6  119.41  5009.8  121.76  5031.5  122.77    5124  124.23  5253.2  124.28
  5366.9  124.86  5395.9  126.95  5523.5  128.27  5580.7  130.71  5694.3  132.61
#Mann= 7 ,-1 , 0
  4422.5     .17       0  4443.7     .11       0  4637.4     .17       0
  4665.1     .15       0  4982.2     .09       0  5031.5     .15       0
  5253.2     .11       0
#XS Ineff= 2 , 0
       0    4785  127.24  5395.9       0  126.95
Permanent Ineff=
       F       F
Bank Sta=4982.2,5031.5
XS Rating Curve= 0 ,0
Exp/Cntr=0.3,0.1

Type RM Length L Ch R = 1 ,11032   ,532,532,532
BEGIN DESCRIPTION:
SANDY BRANCH 22.0
END DESCRIPTION:
XS GIS Cut Line= 3
      3850013.82     10086824.84      3849150.09     10086759.73
      3848958.97     10087427.75
#Sta/Elev= 30
  4170.2  142.21  4206.3  141.45  4276.5  138.13  4426.9  128.05  4501.2  125.11
  4747.8  121.93    4808  123.59    4816  123.47    4821  122.25  4848.1  123.51
  4858.1  122.91  4900.7  123.08  4928.3  123.74  4958.4  122.96  4978.5  121.21
  4995.4   117.7  5001.7   117.7  5018.6  121.76  5063.2  123.02  5162.6  122.88
    5175  123.93  5208.8  124.72  5242.5  124.67  5247.7  125.53  5315.1  125.33
    5381  125.14  5567.4  129.99  5572.6  129.13  5599.4  129.22  5731.2  131.29
#Mann= 6 ,-1 , 0
  4170.2     .17       0  4501.2     .11       0  4900.7     .15       0
  4958.4     .09       0  5063.2     .15       0  5315.1     .11       0
#XS Ineff= 2 , 0
       0                  5247.7       0  125.53
Permanent Ineff=
       F       F
Bank Sta=4958.4,5063.2
XS Rating Curve= 0 ,0
Exp/Cntr=0.3,0.1

Type RM Length L Ch R = 1 ,10500   ,500,500,500
BEGIN DESCRIPTION:
SANDY BRANCH 21.0
END DESCRIPTION:
XS GIS Cut Line= 3
      3849821.62     10086139.82      3848874.21     10086412.61
      3848932.96     10087413.29
#Sta/Elev= 30
  4014.1  137.99  4122.1   133.5  4163.7  130.04  4226.1  129.25  4325.4  125.85
  4455.1  124.31  4537.9  121.26  4684.6  121.17  4850.5  123.11  4923.4  120.93
  4967.6  121.26  4973.3  121.58  4978.5  119.46  4992.3  117.23  5008.5  118.22
  5028.5   121.5  5068.6  122.99  5145.6  120.95  5208.8  121.47  5248.9  123.62
  5362.9  126.56  5394.4  126.94  5519.4  128.41  5559.4  126.45  5679.6  123.82
  5789.8  126.02    5870  129.01  5980.1  130.66  5997.8  132.25  6002.4  131.07
#Mann= 7 ,-1 , 0
  4014.1     .11       0  4684.6     .15       0  4967.6     .11       0
  4973.3     .09       0  5028.5     .11       0  5362.9     .15       0
  5394.4     .11       0
Bank Sta=4973.3,5028.5
XS Rating Curve= 0 ,0
Exp/Cntr=0.3,0.1