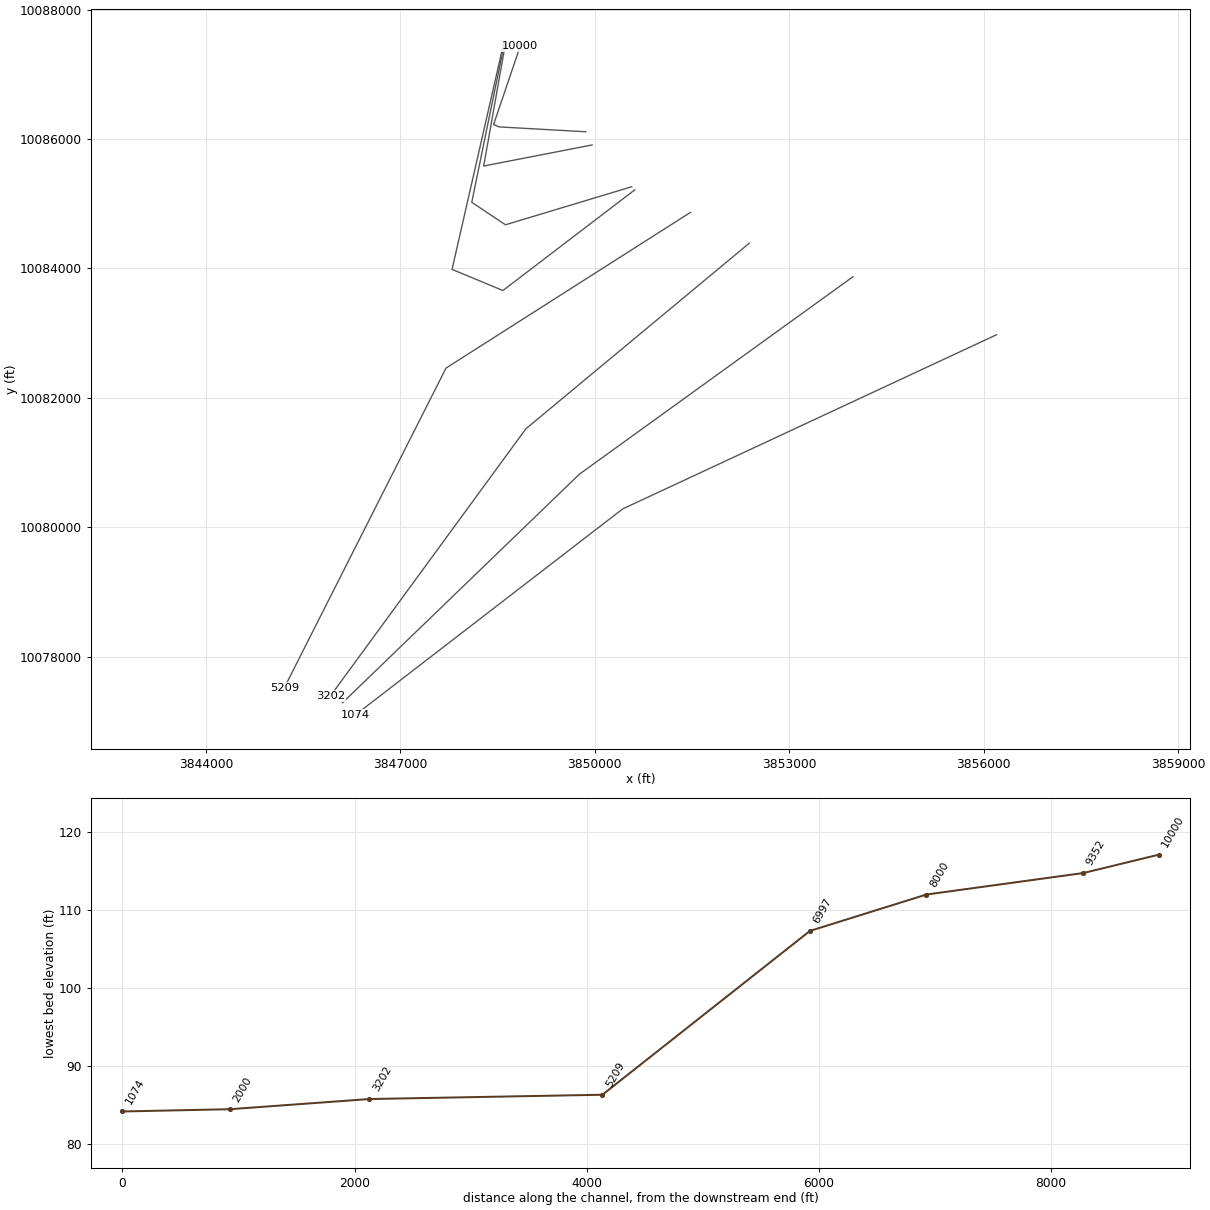
HEC-RAS study SANDY BRANCH.prj: SANDY BRANCH Base Level Engineering

--- SANDY BRANCH.g01 (geometry) --- (continued)

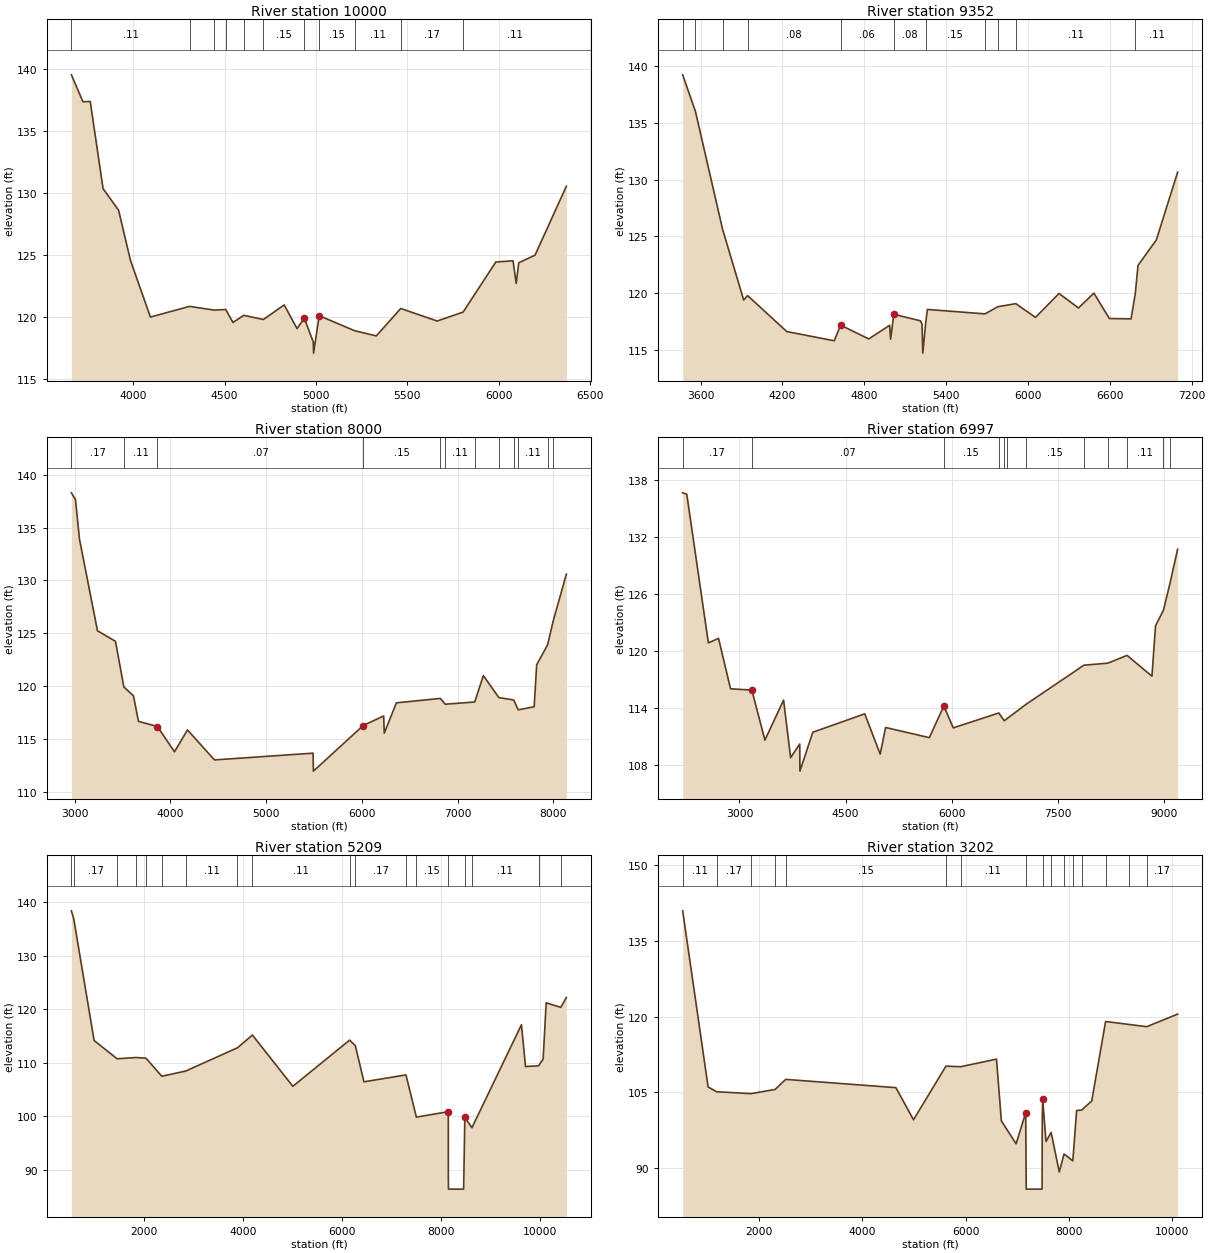
Type RM Length L Ch R = 1 ,10000   ,648,648,648
BEGIN DESCRIPTION:
SANDY BRANCH 20.0
END DESCRIPTION:
XS GIS Cut Line= 4
      3849860.75      10086111.6      3848524.36     10086186.69
      3848437.09     10086222.28      3848847.24     10087431.04
#Sta/Elev= 30
  3661.5   139.5  3724.5  137.33  3764.6  137.35  3834.7  130.32  3919.7  128.58
  3984.9  124.52  4093.9  119.96    4308  120.82  4444.4  120.52    4506  120.57
  4545.8  119.52    4605   120.1    4712  119.76  4826.2  120.94  4896.3  119.03
  4936.4  119.86  4985.2  117.95    4987  117.05  5017.8  120.07  5211.2  118.86
  5330.3  118.44  5464.1  120.65  5663.2  119.64  5805.6  120.36  5984.4   124.4
  6078.6   124.5  6096.2  122.67    6110  124.34    6199  124.95  6370.7  130.51
#Mann= 11 ,-1 , 0
  3661.5     .11       0    4308     .15       0  4444.4     .11       0
    4506     .15       0    4605     .11       0    4712     .15       0
  4936.4     .09       0  5017.8     .15       0  5211.2     .11       0
  5464.1     .17       0  5805.6     .11       0
Bank Sta=4936.4,5017.8
XS Rating Curve= 0 ,0
Exp/Cntr=0.3,0.1

Type RM Length L Ch R = 1 ,9352    ,1352,1352,1352
BEGIN DESCRIPTION:
SANDY BRANCH 18.0
END DESCRIPTION:
XS GIS Cut Line= 3
      3849956.64     10085907.75      3848284.74     10085582.23
       3848620.5     10087477.02
#Sta/Elev= 30
  3469.3  139.24  3562.7  136.02  3761.7  125.63  3916.3  119.39  3945.4  119.78
  4232.2  116.61  4580.3   115.8  4626.8  117.18  4833.2  115.96    4986  117.16
  4993.3  115.94  5016.6  118.13    5212  117.56  5223.2  117.28  5229.2  114.71
 5249.59117.2842  5262.8  118.56  5685.4  118.17  5778.7   118.8  5911.2  119.07
    6055  117.86  6227.6  119.97  6370.1  118.69  6483.3     120  6596.4  117.76
  6755.7  117.73  6786.2  119.93  6806.5  122.44    6941  124.69  7096.9  130.66
#Mann= 11 ,-1 , 0
  3469.3     .11       0  3562.7     .17       0  3761.7     .11       0
  3945.4     .08       0  4626.8     .06       0  5016.6     .08       0
 5249.59     .15       0  5685.4     .11       0  5778.7     .15       0
  5911.2     .11       0  6786.2     .11       0
Bank Sta=4626.8,5016.6
XS Rating Curve= 0 ,0
Exp/Cntr=0.3,0.1

Type RM Length L Ch R = 1 ,8000    ,1003,1003,1003
BEGIN DESCRIPTION:
SANDY BRANCH 16.0
END DESCRIPTION:
XS GIS Cut Line= 4
      3850568.56     10085261.91      3848620.78      10084673.9
      3848100.48     10085021.99      3848605.05     10087480.65
#Sta/Elev= 30
  2965.4  138.29  3007.9  137.65  3049.6  133.91  3237.7  125.24  3425.7  124.24
  3513.1  119.93  3613.8  119.08    3666  116.67  3864.5  116.18    4042  113.79
  4177.8  115.86  4459.9  113.02  5490.1  113.66  5493.4  111.96    6013  116.27
  6227.4  117.18  6233.6  115.55  6360.1  118.42  6819.4  118.84  6869.5  118.29
  7178.2   118.5  7268.6     121  7430.7  118.92  7586.1  118.69    7633  117.76
  7799.5  118.05  7825.7  122.02    7939  123.89    8000  126.22  8135.9   130.6
#Mann= 12 ,-1 , 0
  2965.4     .17       0  3513.1     .11       0  3864.5     .07       0
    6013     .15       0  6819.4     .15       0  6869.5     .11       0
  7178.2     .17       0  7430.7     .11       0  7586.1     .17       0
    7633     .11       0    7939     .17       0    8000     .11       0
Bank Sta=3864.5,6013
XS Rating Curve= 0 ,0
Exp/Cntr=0.3,0.1

Type RM Length L Ch R = 1 ,6997    ,1788,1788,1788
BEGIN DESCRIPTION:
SANDY BRANCH 14.0
END DESCRIPTION:
XS GIS Cut Line= 4
      3850616.02     10085213.65      3848581.29      10083658.1
      3847796.57     10083984.49      3848594.64     10087485.87
#Sta/Elev= 30
  2196.3  136.65  2254.4   136.5  2559.9  120.83  2703.3  121.31  2873.7  115.99
  3174.9  115.85  3359.8  110.58  3623.7   114.8  3723.5  108.73  3852.3  110.17
  3855.1  107.31  4037.2  111.41  4772.1  113.35  4990.4  109.11  5067.3  111.91
    5686  110.84  5891.1  114.18  6024.4  111.87  6669.1  113.44    6745  112.62
  6780.9  112.82  7059.2  114.38  7873.2  118.48  8210.1  118.69  8483.6  119.51
  8835.2  117.32    8886  122.63  8997.4  124.26  9094.1  127.23  9198.6  130.71
#Mann= 12 ,-1 , 0
  2196.3     .17       0  3174.9     .07       0  5891.1     .15       0
  6669.1     .11       0    6745     .15       0  6780.9     .11       0
  7059.2     .15       0  7873.2     .11       0  8210.1     .17       0
  8483.6     .11       0  8997.4     .17       0  9094.1     .11       0
Bank Sta=3174.9,5891.1
XS Rating Curve= 0 ,0
Exp/Cntr=0.3,0.1

Type RM Length L Ch R = 1 ,5209    ,2007,2007,2007
BEGIN DESCRIPTION:
SANDY BRANCH 10.0
END DESCRIPTION:
XS GIS Cut Line= 3
      3851475.51     10084865.66      3847703.79     10082459.62
      3845209.33     10077520.48
#Sta/Elev= 30
   526.2  138.38   573.9  136.86   985.2  114.14  1449.7  110.73  1829.1  110.96
  2031.8  110.85  2353.5  107.46  2836.2  108.43  3883.9  112.78  4185.6  115.16
    5003  105.58  6151.1  114.21  6267.1  113.16  6440.9  106.42  7290.2  107.71
  7500.6   99.82  8135.3  100.82  8146.4  100.06  8146.8   89.06  8149.1   86.36
  8455.9   86.36  8480.8   99.76    8624   97.84  9625.2  117.09    9707  109.28
    9972  109.41 10063.7  110.66   10125  121.18 10421.4  120.34 10533.3  122.18
#Mann= 18 ,-1 , 0
   526.2     .11       0   573.9     .17       0  1449.7     .15       0
  1829.1     .17       0  2031.8     .11       0  2353.5     .15       0
  2836.2     .11       0  3883.9     .15       0  4185.6     .11       0
  6151.1     .17       0  6267.1     .17       0  7290.2     .17       0
  7500.6     .15       0  8135.3     .07       0  8480.8     .17       0
    8624     .11       0    9972    .125       0 10421.4    .125       0
Bank Sta=8135.3,8480.8
XS Rating Curve= 0 ,0
Exp/Cntr=0.3,0.1

Type RM Length L Ch R = 1 ,3202    ,1202,1202,1202
BEGIN DESCRIPTION:
SANDY BRANCH 6.0
END DESCRIPTION:
XS GIS Cut Line= 3
      3852383.58     10084389.93      3848935.56     10081520.82
      3845919.58     10077391.32
#Sta/Elev= 30
   514.4  140.99  1007.4  106.08  1171.3  105.12  1840.1  104.74  2307.4  105.58
  2512.4  107.57  4650.1  105.93  4991.2   99.56    5620  110.19  5906.6  110.08
  6600.8  111.59    6695   99.35    6981    94.8  7166.7  100.95  7177.2   85.81
  7484.2   85.81  7488.7  100.21  7495.9  103.63  7560.8   95.25  7660.3   97.06
    7818   89.21  7910.8   92.78  8080.7   91.42  8154.7   101.4  8250.5  101.48
  8447.4  103.28  8716.6  119.05  9163.4  118.47  9514.6  118.02 10113.6  120.51
#Mann= 16 ,-1 , 0
   514.4     .11       0  1171.3     .17       0  1840.1     .15       0
  2307.4     .17       0  2512.4     .15       0    5620     .11       0
  5906.6     .11       0  7166.7     .07       0  7495.9     .17       0
  7660.3     .17       0  7910.8     .15       0  8080.7     .17       0
  8250.5     .11       0  8716.6     .15       0  9163.4     .15       0
  9514.6     .17       0
Bank Sta=7166.7,7495.9
XS Rating Curve= 0 ,0
Exp/Cntr=0.3,0.1

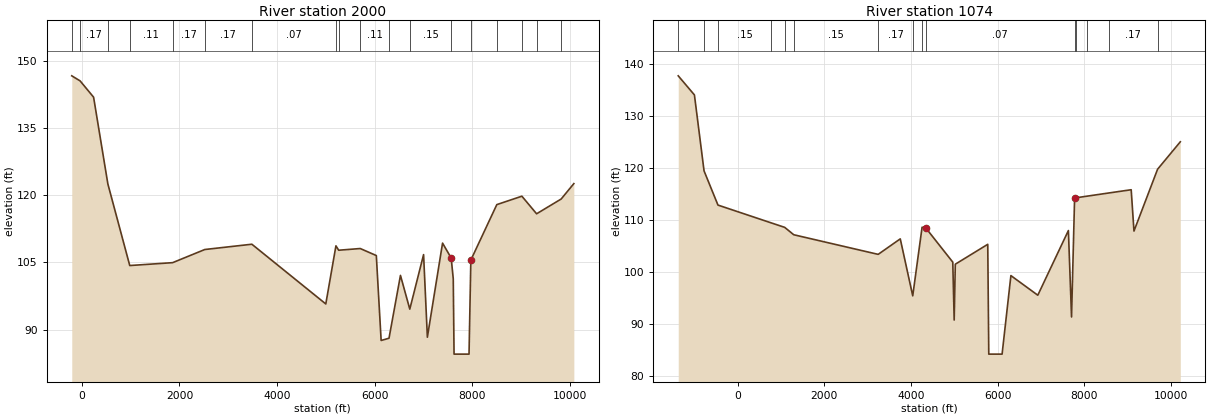
Type RM Length L Ch R = 1 ,2000    ,926,926,926
BEGIN DESCRIPTION:
SANDY BRANCH 4.0
END DESCRIPTION:
XS GIS Cut Line= 3
      3853982.08     10083870.47        3849762.     10080820.09
      3846107.03     10077287.09
#Sta/Elev= 30
  -207.1  146.68   -36.1  145.55   240.2  141.91   532.9  122.52   981.4   104.3
  1859.3  104.94  2519.7  107.88  3484.4  109.06  4999.5   95.72  5207.3   108.7
  5263.9  107.72  5705.8   108.1  6034.9  106.53  6133.7   87.56    6295   88.06
  6529.8   102.1    6721   94.56  7003.7  106.74  7081.4   88.29  7392.6  109.31
  7569.4  105.98  7611.8  101.36  7628.1   84.51  7935.1   84.51  7972.5  105.52
  8504.6  117.91  9018.4  119.79  9320.1  115.86  9823.6  119.16 10083.4   122.6
#Mann= 18 ,-1 , 0
  -207.1     .17       0   -36.1     .17       0   532.9     .17       0
   981.4     .11       0  1859.3     .17       0  2519.7     .17       0
  3484.4     .07       0  5207.3     .15       0  5263.9     .17       0
  5705.8     .11       0    6295     .11       0    6721     .15       0
  7569.4     .07       0  7972.5     .11       0  8504.6     .15       0
  9018.4     .15       0  9320.1     .17       0  9823.6     .17       0
Bank Sta=7569.4,7972.5
XS Rating Curve= 0 ,0
Exp/Cntr=0.3,0.1

Type RM Length L Ch R = 1 ,1074    ,0,0,0
BEGIN DESCRIPTION:
SANDY BRANCH 2.0
END DESCRIPTION:
XS GIS Cut Line= 3
      3856198.73     10082975.02      3850429.05     10080282.54
       3846302.2     10077096.68
#Sta/Elev= 30
   -1367   137.7  -993.7  134.03  -771.4  119.43  -450.5  112.86   770.5  109.46
  1088.7  108.58  1297.5  107.16  3244.5  103.39  3754.3  106.37  4041.8   95.42
  4257.4   108.6  4339.2  108.51  4965.3   101.9  4997.9   90.78  5023.7   101.5
  5772.1  105.32  5795.8   84.22  6102.8   84.22  6306.2   99.31  6926.6   95.54
  7632.2  107.97  7704.7   91.36  7775.3  114.23  7812.2  114.27  8058.5  114.57
  8566.4  115.19  9080.5  115.81  9144.8  107.87  9689.2  119.75 10213.5  125.02
#Mann= 15 ,-1 , 0
   -1367     .11       0  -771.4     .11       0  -450.5     .15       0
   770.5     .11       0  1088.7     .17       0  1297.5     .15       0
  3244.5     .17       0  4041.8     .11       0  4257.4     .17       0
  4339.2     .07       0  7775.3     .17       0  7812.2     .11       0
  8058.5     .15       0  8566.4     .17       0  9689.2     .15       0
Bank Sta=4339.2,7775.3
XS Rating Curve= 0 ,0
Exp/Cntr=0.3,0.1

Chan Stop Cuts=-1
Use User Specified Reach Order=0
Composite Channel Slope=5

--- SANDY BRANCH.g10 (geometry) ---

Geom Title=Existing Conditions
Program Version=4.10

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
River Reach=SANDY BRANCH    ,Reach-1

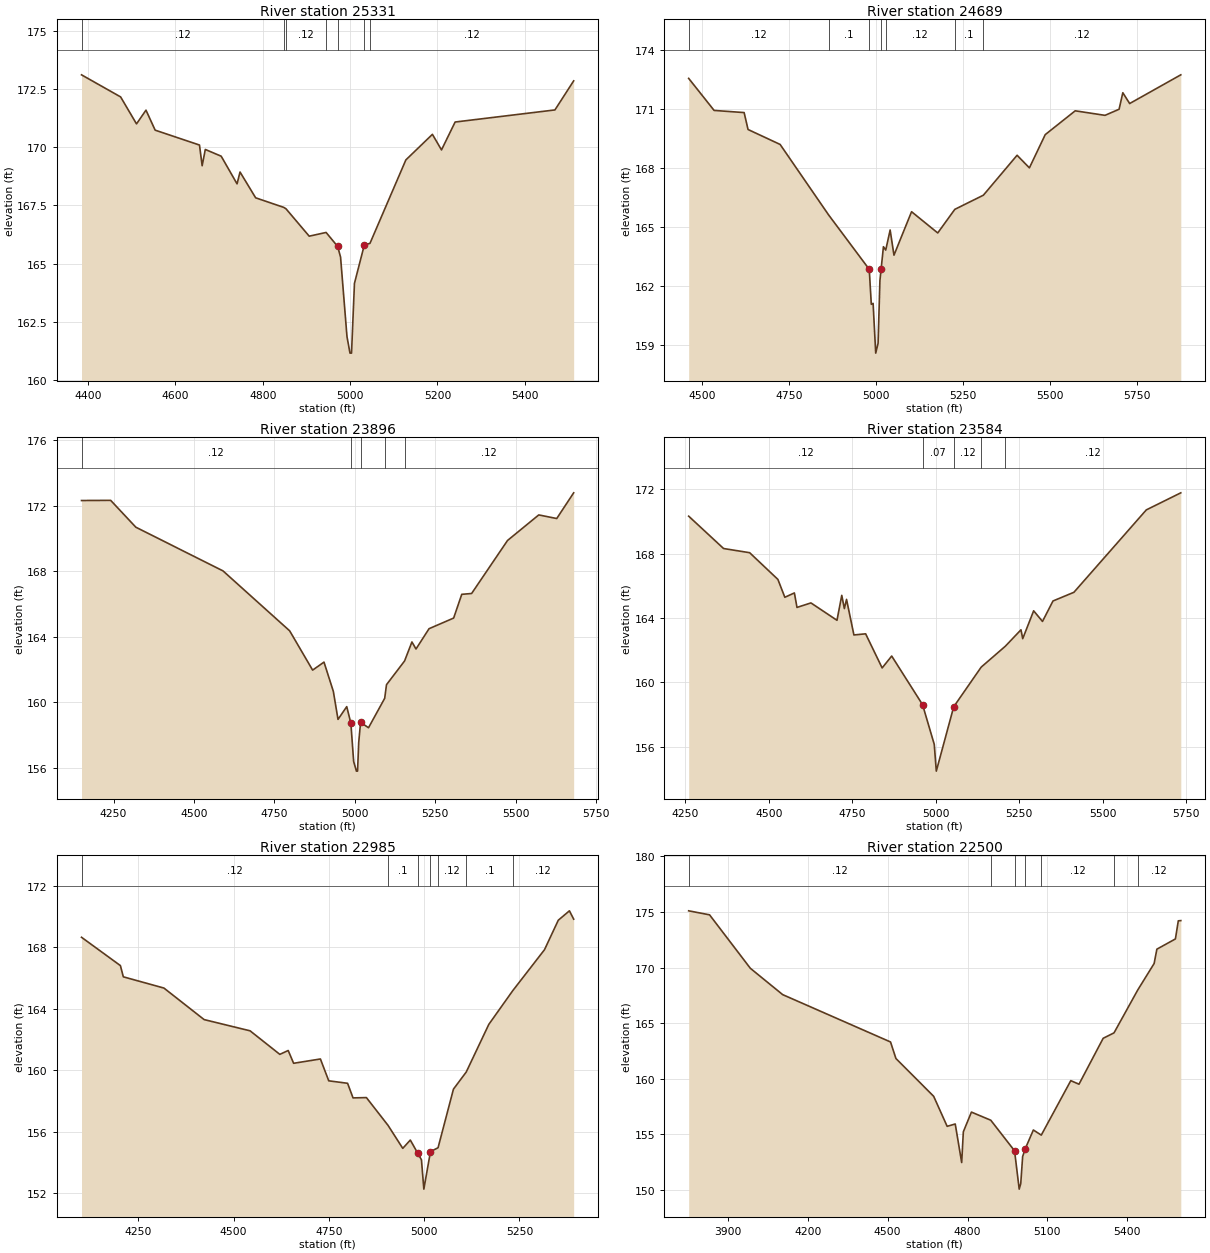
Type RM Length L Ch R = 1 ,25331   ,642,642,642
BEGIN DESCRIPTION:
SANDY BRANCH 50.0
END DESCRIPTION:
XS GIS Cut Line= 3
      3852988.23     10097134.93      3852643.01     10096630.68
      3852146.57     10096491.06
#Sta/Elev= 30
  4385.1  173.12  4474.6  172.17    4511  171.01  4532.7   171.6  4553.7  170.74
  4655.2   170.1  4661.3  169.21  4668.5  169.91  4704.9  169.62  4741.2  168.43
    4748  168.94  4783.8  167.83  4847.9  167.42  4853.2  167.36  4906.4  166.18
  4945.1  166.34  4971.5  165.74  4978.2  165.28  4992.9  161.86  4999.8  161.15
  5003.3  161.15    5010  164.15  5032.7  165.81  5045.5  165.87  5127.7  169.46
  5188.5  170.56  5209.3  169.89  5240.5  171.09    5469  171.61  5511.9  172.86
#Mann= 7 ,-1 , 0
  4385.1     .12       0  4847.9      .1       0  4853.2     .12       0
  4945.1      .1       0  4971.5     .07       0  5032.7      .1       0
  5045.5     .12       0
Bank Sta=4971.5,5032.7
XS Rating Curve= 0 ,0
Exp/Cntr=0.3,0.1

Type RM Length L Ch R = 1 ,24689   ,793,793,793
BEGIN DESCRIPTION:
SANDY BRANCH 49.0
END DESCRIPTION:
XS GIS Cut Line= 3
      3853364.44      10096262.2      3852833.07     10096141.96
      3851972.41     10096010.15
#Sta/Elev= 30
  4460.4  172.54  4533.6  170.91  4619.9   170.8  4631.2  169.94  4723.5  169.18
  4862.8   165.6  4979.8  162.83  4985.7  161.05  4990.9   161.1  4998.4  158.57
  5005.2  159.07  5010.5  162.26 5014.04 162.863  5020.6  163.98  5027.2  163.81
  5039.9  164.83  5050.9  163.55  5101.5  165.76  5176.8  164.68  5225.9  165.88
  5308.1   166.6    5405  168.63  5440.4  167.99    5486  169.68  5572.2  170.89
  5657.9  170.66  5698.4  170.97  5709.1  171.81  5728.8  171.26  5875.9  172.72
#Mann= 7 ,-1 , 0
  4460.4     .12       0  4862.8      .1       0  4979.8     .07       0
 5014.04      .1       0  5027.2     .12       0  5225.9      .1       0
  5308.1     .12       0
Bank Sta=4979.8,5014.04
XS Rating Curve= 0 ,0
Exp/Cntr=0.3,0.1

Type RM Length L Ch R = 1 ,23896   ,312,312,312
BEGIN DESCRIPTION:
SANDY BRANCH 48.0
END DESCRIPTION:
XS GIS Cut Line= 3
      3853590.04     10096195.25      3853074.44     10095519.94
      3852435.52     10095287.29
#Sta/Elev= 30
  4150.6  172.32  4241.2  172.33  4319.4  170.69  4590.4  168.02  4797.5  164.36
  4868.9  161.96  4904.2  162.45  4933.3  160.66  4947.8  158.95  4974.9  159.73
 4987.76 158.715  4996.4  156.38    5005  155.79  5008.5  155.79  5012.1  157.53
  5017.9  158.77  5042.6  158.44  5092.9  160.24  5098.5  161.07  5154.7  162.52
  5177.5  163.68  5190.2  163.25  5230.7  164.49  5307.2  165.14  5332.4  166.59
    5363  166.64  5474.7  169.88  5571.7  171.44  5627.6  171.22  5680.2  172.79
#Mann= 5 ,-1 , 0
  4150.6     .12       0 4987.76     .07       0  5017.9     .12       0
  5092.9      .1       0  5154.7     .12       0
Bank Sta=4987.76,5017.9
XS Rating Curve= 0 ,0
Exp/Cntr=0.3,0.1

Type RM Length L Ch R = 1 ,23584   ,599,599,599
BEGIN DESCRIPTION:
SANDY BRANCH 47.0
END DESCRIPTION:
XS GIS Cut Line= 3
      3853673.76     10095851.73       3853169.6     10095248.69
      3852511.84     10095046.38
#Sta/Elev= 30
  4260.1  170.32  4364.7  168.31  4442.8  168.05  4527.4  166.39  4548.2  165.28
  4576.8  165.55  4584.6  164.65  4626.3  164.93  4704.4  163.85  4718.7   165.4
  4726.5  164.58    4733  165.15  4755.1  162.94  4790.2  163.01  4839.7  160.89
  4868.3  161.63  4960.7  158.61  4995.8  156.14  5001.9  154.48  5054.1  158.48
  5136.3  160.94  5208.7  162.24  5255.5  163.26  5260.8  162.71  5293.5  164.44
    5320  163.78  5351.4  165.05  5414.1  165.59    5631  170.71  5734.3  171.77
#Mann= 5 ,-1 , 0
  4260.1     .12       0  4960.7     .07       0  5054.1     .12       0
  5136.3      .1       0  5208.7     .12       0
Bank Sta=4960.7,5054.1
XS Rating Curve= 0 ,0
Exp/Cntr=0.3,0.1

Type RM Length L Ch R = 1 ,22985   ,485,485,485
BEGIN DESCRIPTION:
SANDY BRANCH 46.0
END DESCRIPTION:
XS GIS Cut Line= 3
      3854137.32     10095575.71      3853588.72     10094933.37
      3853177.27     10094759.76
#Sta/Elev= 30
    4101  168.65    4203  166.81  4210.7  166.08  4317.2  165.35  4422.7   163.3
  4543.3  162.57  4621.3  161.04  4643.3  161.29  4657.5  160.46  4727.8  160.74
  4749.7  159.32  4799.1  159.16  4813.4  158.21  4848.5  158.23  4905.1  156.43
  4943.9  154.93  4963.7  155.47 4983.18 154.614  4992.9  154.19  4999.2  152.28
  5016.6  154.72  5036.5  154.97  5076.9  158.78  5110.4  159.89  5169.7  162.99
  5232.5  165.18  5315.7  167.84    5352  169.76  5381.2  170.37  5392.3  169.83
#Mann= 7 ,-1 , 0
    4101     .12       0  4905.1      .1       0 4983.18     .07       0
  5016.6      .1       0  5036.5     .12       0  5110.4      .1       0
  5232.5     .12       0
Bank Sta=4983.18,5016.6
XS Rating Curve= 0 ,0
Exp/Cntr=0.3,0.1

Type RM Length L Ch R = 1 ,22500   ,528,528,528
BEGIN DESCRIPTION:
SANDY BRANCH 45.0
END DESCRIPTION:
XS GIS Cut Line= 3
      3855046.59     10094749.19       3853814.9     10094550.57
      3853218.49     10094474.02
#Sta/Elev= 30
  3752.4   175.1  3830.9  174.74  3984.1  169.93  4105.6  167.56  4510.8   163.3
  4531.1  161.81  4672.9  158.41  4723.5  155.71  4753.9  155.92  4778.1  152.45
  4784.3  155.22  4814.7  156.99  4887.4  156.26  4976.7  153.51  4994.2  150.06
    5000  150.56  5007.1  152.99  5017.2  153.71  5047.4  155.38  5077.1  154.92
    5188  159.82  5218.8   159.5  5309.6  163.63  5350.4  164.12  5439.6  167.98
  5501.1  170.36  5511.4  171.65    5581  172.57  5591.9   174.2  5601.3  174.22
#Mann= 7 ,-1 , 0
  3752.4     .12       0  4887.4      .1       0  4976.7     .07       0
  5017.2      .1       0  5077.1     .12       0  5350.4     .05       0
  5439.6     .12       0
Bank Sta=4976.7,5017.2
XS Rating Curve= 0 ,0
Exp/Cntr=0.3,0.1

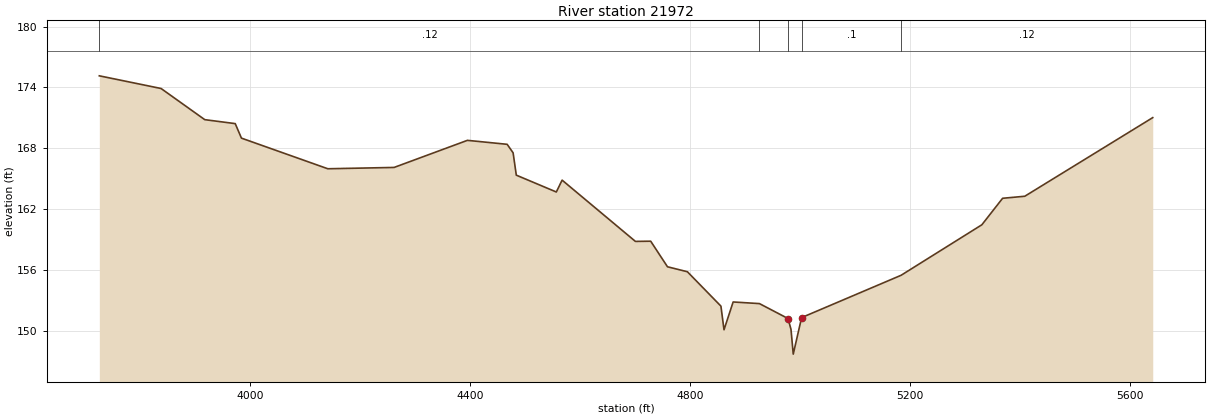
Type RM Length L Ch R = 1 ,21972   ,353,353,353
BEGIN DESCRIPTION:
SANDY BRANCH 44.0
END DESCRIPTION:
XS GIS Cut Line= 3
      3855067.89     10094661.09      3853928.57     10094079.05
      3853296.64     10094151.97
#Sta/Elev= 30
  3726.3  175.15  3838.6   173.9    3918  170.83  3973.4  170.44  3984.7  169.01
  4141.8  165.99  4262.3  166.12  4395.6  168.79  4467.9   168.4  4478.7  167.56
  4484.5  165.36  4557.3   163.7  4567.8  164.87  4701.1  158.83  4728.9  158.85
  4759.4  156.33  4795.6  155.84  4856.6  152.45  4862.2  150.12  4878.8  152.86
  4926.6   152.7 4978.61 151.228    4984  150.16  4988.1  147.72  5003.3  151.32
  5184.2  155.49  5331.1  160.47  5368.8  163.08  5409.1  163.28  5641.8  171.03
#Mann= 5 ,-1 , 0
  3726.3     .12       0  4926.6      .1       0 4978.61     .07       0
  5003.3      .1       0  5184.2     .12       0
Bank Sta=4978.61,5003.3
XS Rating Curve= 0 ,0
Exp/Cntr=0.3,0.1