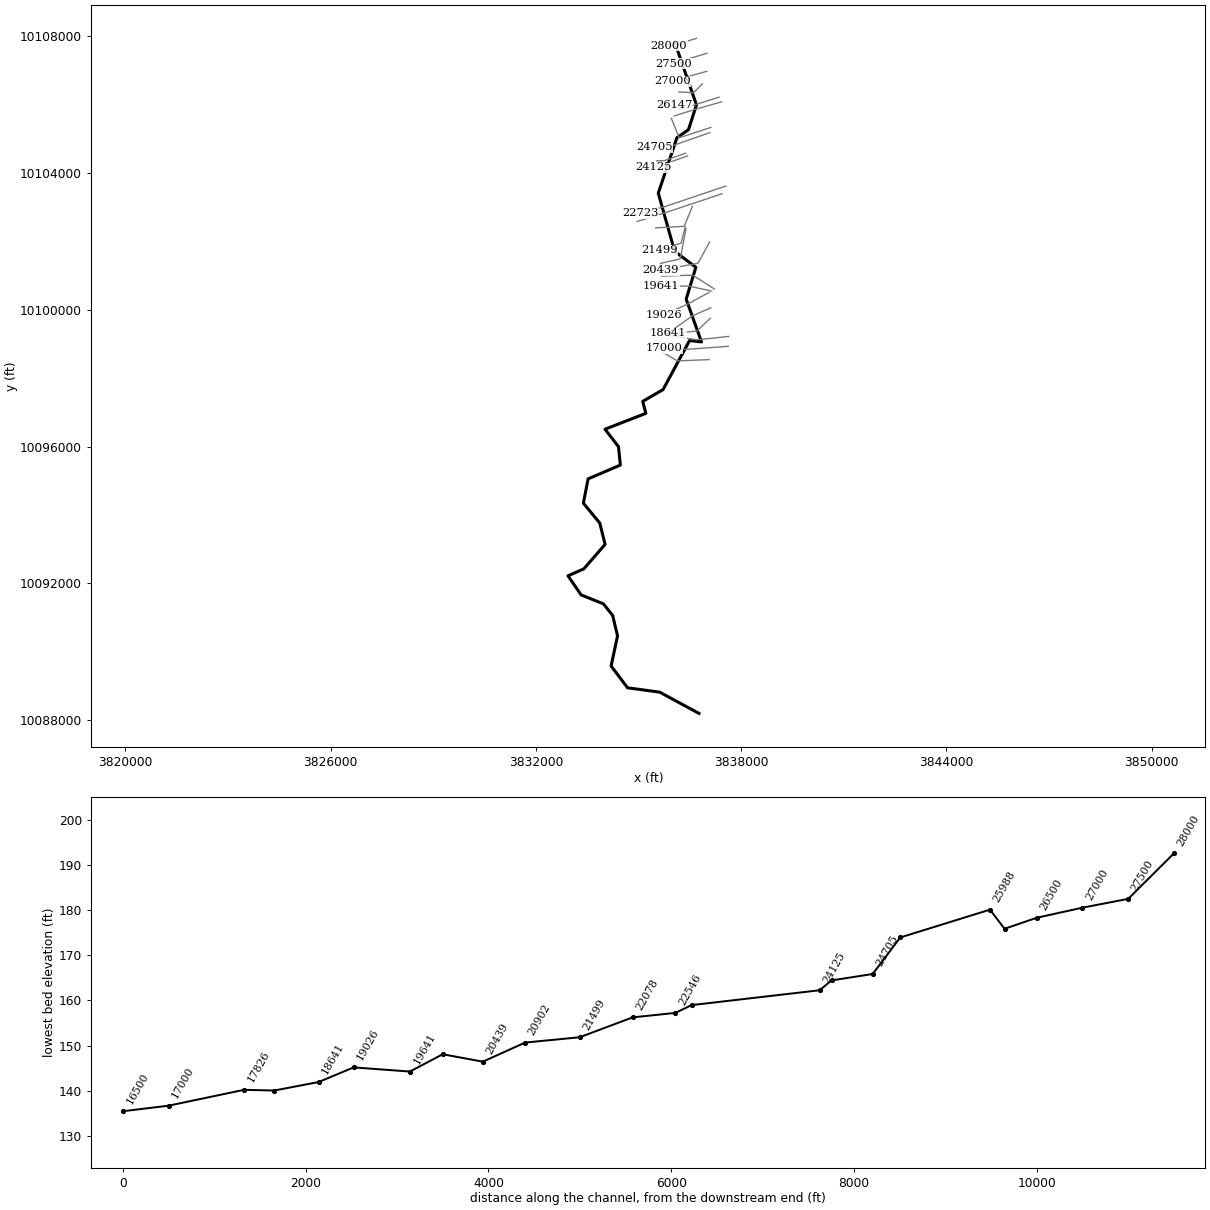
--- SILVERDALE CREEK.prj (project) ---

Proj Title=SILVERDALE CREEK Base Level Engineering
Current Plan=p01
Default Exp/Contr=0.3,0.1
English Units
Geom File=g01
Flow File=f01
Plan File=p01
Y Axis Title=Elevation
X Axis Title(PF)=Main Channel Distance
X Axis Title(XS)=Station
BEGIN DESCRIPTION:
SILVERDALE CREEK
END DESCRIPTION:
DSS File=dss
DSS Export Rating Curves= 0
DSS Export Rating Curve Sorted= 0
DSS Export Volume Flow Curves= 0
DXF OffsetX= 0
DXF OffsetY= 0
DXF ScaleX= 1
DXF ScaleY= 10

--- SILVERDALE CREEK.p01 (plan) ---

Plan Title=Multiple Run
Program Version=4.10
Short Identifier=Multiple Run
Geom File=g01
Flow File=f01
Subcritical Flow
K Sum by GR= 0
Std Step Tol= 0.01
Critical Tol= 0.01
Num of Std Step Trials= 20
Max Error Tol= 0.3
Flow Tol Ratio= 0.001
Split Flow NTrial= 30
Split Flow Tol= 0.02
Split Flow Ratio= 0.02
Log Output Level= 0
Friction Slope Method= 1
Unsteady Friction Slope Method= 2
Unsteady Bridges Friction Slope Method= 1
Parabolic Critical Depth
Global Vel Dist= 1 , 1 , 1
Global Log Level= 0
CheckData=True
Encroach Param=-1 ,0,0, 0
BEGIN DESCRIPTION:
Multiple Run
END DESCRIPTION:
Computation Interval=1HOUR
Output Interval=1HOUR
Run HTab= 0
Run UNet= 0
Run PostProcess= 0
Run WQNet= 0
UNET Theta= 1
UNET Theta Warmup= 1
UNET ZTol= 0.02
UNET ZSATol= 0.05
UNET MxIter= 20
UNET MaxInSteps= 0
UNET DtIC= 0
UNET DtMin= 0
UNET MaxCRTS= 20
UNET WFStab= 2
UNET SFStab= 1
UNET WFX= 1
UNET SFX= 1
UNET DSS MLevel= 4
UNET DZMax Abort= 100
UNET Convert EG Bridges= 0
UNET Use Existing IB Tables=-1
UNET Froude Reduction=False
UNET Froude Limit= 1
UNET Froude Power= 10
UNET Time Slicing=0,0, 5
UNET Junction Losses=0
Instantaneous Interval=1HOUR
DSS File=dss
Write IC File= 0
Write IC File at Sim End=0
Echo Input=False
Echo Parameters=False
Echo Output=False
Write Detailed= 0
WQ AD Non Conservative
WQ ULTIMATE=-1
WQ Max Comp Step=1HOUR
WQ Output Interval=15MIN
WQ Output Selected Increments= 0
WQ Output face flow=0
WQ Output face velocity=0
WQ Output face area=0
WQ Output face dispersion=0
WQ Output cell volume=0
WQ Output cell surface area=0
WQ Output cell continuity=0
WQ Output cumulative cell continuity=0
WQ Output face conc=0
WQ Output face dconc_dx=0
WQ Output face courant=0
WQ Output face peclet=0
WQ Output face adv mass=0
WQ Output face disp mass=0
WQ Output cell mass=0
WQ Output cell source sink temp=0
WQ Output cell source sink nsm=0
WQ Output MaxMinRange=-1
WQ Daily Max Min Mean=-1
WQ Daily Range=0
WQ Daily Time=0
WQ Create Restart=0
WQ Fixed Restart=0
WQ System Summary=0
WQ Use Fixed Temperature=0
Sorting and Armoring Iterations= 10
XS Update Threshold= 0.02
Hydraulics Update Threshold= 0.02
Energy Slope Method= 1
Volume Change Method= 0
XS Weighting Method= 0
Number of US Weighted Cross Sections= 1
Number of DS Weighted Cross Sections= 1
Upstream XS Weight=0.25
Main XS Weight=0.5
Downstream XS Weight=0.25
Number of DS XS's Weighted with US Boundary= 1
Upstream Boundary Weight= 1
Weight of XSs Associated with US Boundary= 0
Number of US XS's Weighted with DS Boundary= 1
Downstream Boundary Weight= 0.5
Weight of XSs Associated with DS Boundary= 0.5
Sediment Output Level= 4
Mass or Volume Output= 0
Output Increment Type= 1
Profile and TS Output Increment= 10
XS Output Flag= 0
XS Output Increment= 10
Disregard all LS=0
Disregard all Conn=0
Disregard all Breaches=0
Disregard all Pumps=0

--- SILVERDALE CREEK.f01 (steady flow) ---

Flow Title=Multiple
Program Version=4.10
Number of Profiles= 7
Profile Names=10-year,25-year,50-year,1pct_min,100-year,1pct_plu,500-year
River Rch & RM=SILVERDALE CREEK,Reach-1         ,28000
     636     850    1139     501    1513    4569    2766
River Rch & RM=SILVERDALE CREEK,Reach-1         ,15555
    1056    1452    1981     887    2679    8090    5069
River Rch & RM=SILVERDALE CREEK,Reach-1         ,8477
    1365    1900    2614    1179    3561   10754    6837
River Rch & RM=SILVERDALE CREEK,Reach-1         ,6505
    1454    2015    2761    1241    3747   11316    7133
Boundary for River Rch & Prof#=SILVERDALE CREEK,Reach-1         , 1
Up Type= 0
Dn Type= 3
Dn Slope=0.015
Boundary for River Rch & Prof#=SILVERDALE CREEK,Reach-1         , 2
Up Type= 0
Dn Type= 3
Dn Slope=0.015
Boundary for River Rch & Prof#=SILVERDALE CREEK,Reach-1         , 3
Up Type= 0
Dn Type= 3
Dn Slope=0.015
Boundary for River Rch & Prof#=SILVERDALE CREEK,Reach-1         , 4
Up Type= 0
Dn Type= 3
Dn Slope=0.015
Boundary for River Rch & Prof#=SILVERDALE CREEK,Reach-1         , 5
Up Type= 0
Dn Type= 3
Dn Slope=0.015
Boundary for River Rch & Prof#=SILVERDALE CREEK,Reach-1         , 6
Up Type= 0
Dn Type= 3
Dn Slope=0.015
Boundary for River Rch & Prof#=SILVERDALE CREEK,Reach-1         , 7
Up Type= 0
Dn Type= 3
Dn Slope=0.015
DSS Import GetInterval= 0
DSS Import GetPeak= 0
DSS Import FillOption= 0

--- SILVERDALE CREEK.g01 (geometry) ---

Geom Title=Existing Conditions
Program Version=4.10

River Reach=SILVERDALE CREEK,Reach-1
Reach XY= 30
      3836061.64     10107825.66      3836696.06     10105994.87
      3836460.94     10105267.06      3836124.57     10105037.03
      3835579.61     10103414.34       3836057.4      10101713.4
      3836678.24     10101246.86      3836394.54       10100312.
      3836843.18     10099061.77      3836493.92     10099102.06
      3835717.87     10097666.04      3835125.06     10097322.66
      3835216.75     10096972.61        3834023.     10096508.23
      3834416.25     10095997.42      3834471.12     10095459.86
      3833528.16     10095055.65      3833390.27     10094344.77
      3833869.19     10093763.21        3834025.     10093138.99
      3833403.11     10092423.09      3832939.62     10092220.59
      3833324.46     10091661.11      3833976.03     10091399.65
       3834245.3     10091061.63      3834388.79     10090462.64
      3834200.91     10089582.55      3834681.37     10088944.44
      3835621.51     10088816.34       3836767.3     10088195.97

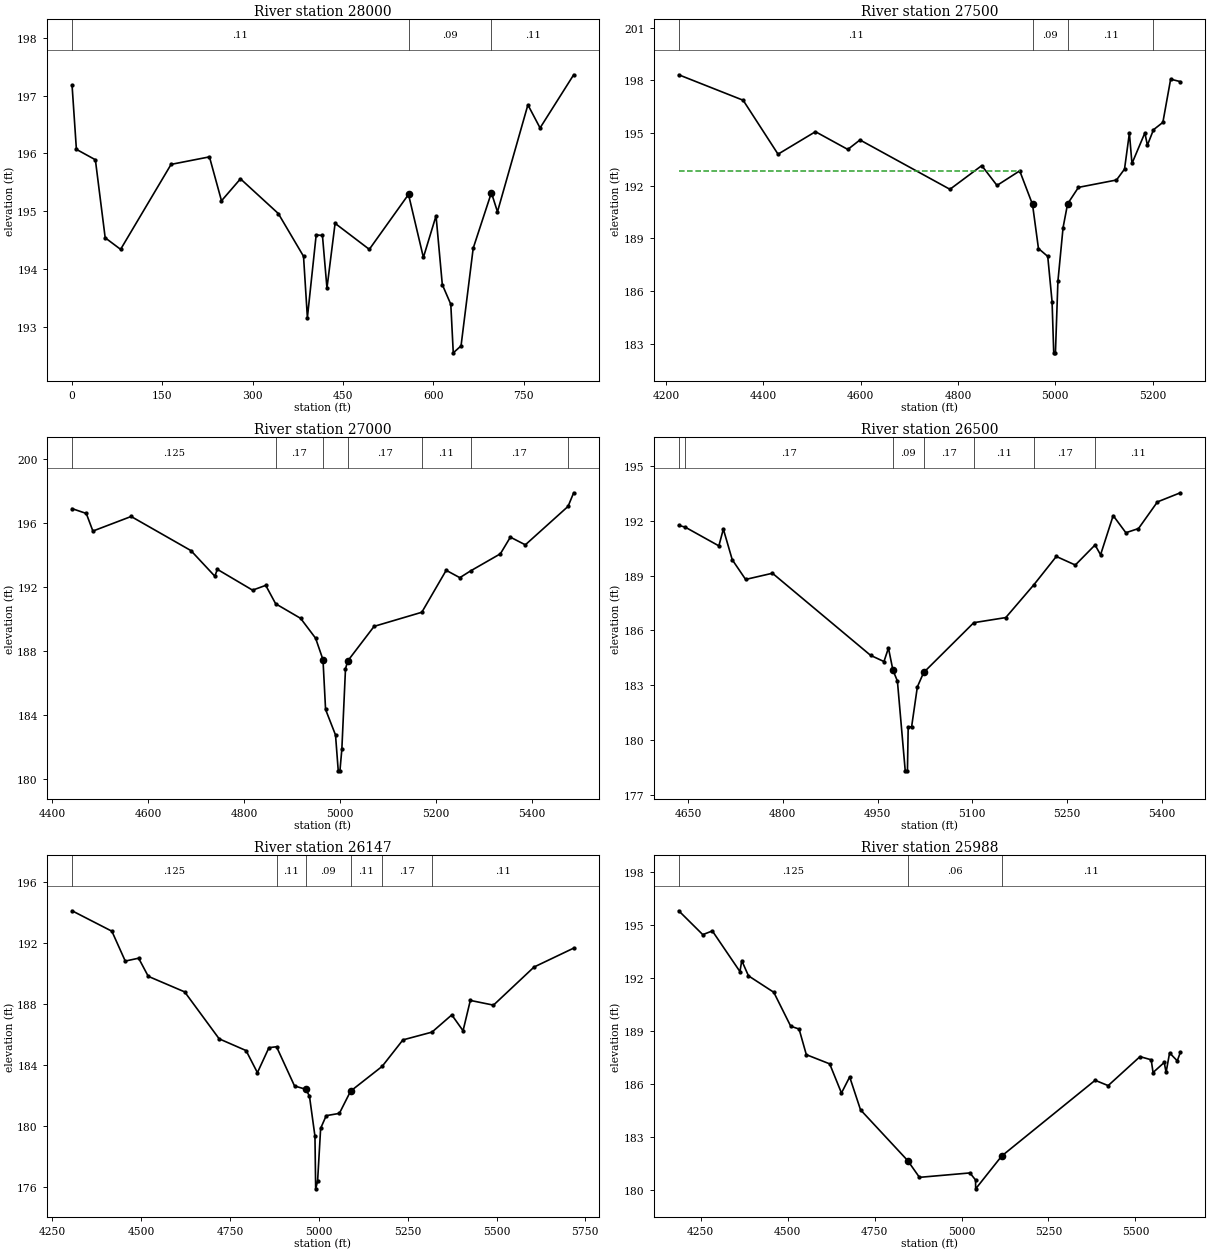
Type RM Length L Ch R = 1 ,28000   ,500,500,500
XS GIS Cut Line= 3
      3836694.77      10107942.6      3836088.18     10107753.66
      3835892.25     10107726.44
#Sta/Elev= 30
       0  197.18     7.2  196.07    38.7  195.89      55  194.54    80.6  194.34
   164.4  195.81   228.1  195.94   248.1  195.18   279.6  195.56   342.4  194.96
   384.3  194.22   390.7  193.16   405.3  194.59   415.7  194.58   423.2  193.67
   436.7  194.79   493.5  194.34   558.6  195.29   583.3   194.2   604.3  194.92
   614.7  193.73   628.8  193.39   632.9  192.55   645.8  192.67     666  194.36
   696.2  195.32   706.3  194.99   756.8  196.84     777  196.44   832.8  197.36
#Mann= 3 , 0 , 0
       0     .11       0   558.6     .09       0   696.2     .11       0
Bank Sta=558.6,696.2
XS Rating Curve= 0 ,0
Exp/Cntr=0.3,0.1

Type RM Length L Ch R = 1 ,27500   ,500,500,500
BEGIN DESCRIPTION:
SILVERDALE CREEK 55.0
END DESCRIPTION:
XS GIS Cut Line= 3
      3837005.04     10107505.09      3836263.02     10107285.24
      3836018.95     10107204.75
#Sta/Elev= 30
  4226.1  198.31  4358.5  196.86  4430.2  193.79  4507.1  195.07  4573.6  194.06
  4598.6   194.6  4783.5  191.79  4848.9  193.14  4880.2  192.01  4926.9  192.84
  4953.2  190.93  4965.4  188.42  4984.5  187.97  4993.4  185.39  4996.8  182.48
  5000.3  182.48  5005.4  186.55    5016  189.61  5025.3  190.96  5047.6   191.9
  5125.8  192.32  5142.3  192.94  5152.3  194.99  5157.6  193.26  5184.1     195
  5189.3   194.3  5201.8  195.18  5221.1   195.6  5237.1  198.06    5257  197.92
#Mann= 4 ,-1 , 0
  4226.1     .11       0  4953.2     .09       0  5025.3     .11       0
  5201.8    .125       0
#XS Ineff= 2 , 0
         4927.23  192.86
Permanent Ineff=
       F       F
Bank Sta=4953.2,5025.3
XS Rating Curve= 0 ,0
Exp/Cntr=0.3,0.1

Type RM Length L Ch R = 1 ,27000   ,500,500,500
BEGIN DESCRIPTION:
SILVERDALE CREEK 54.0
END DESCRIPTION:
XS GIS Cut Line= 3
      3836996.36     10106977.31      3836458.54     10106826.36
      3835991.15     10106691.35
#Sta/Elev= 30
  4441.4   196.9    4471   196.6  4484.8   195.5  4564.5  196.41  4689.1  194.28
  4738.9  192.68  4744.1  193.11  4817.5  191.81  4844.9  192.11  4865.6  190.96
  4917.6  190.05  4948.8  188.81  4964.2  187.47  4969.6  184.36  4990.3  182.77
    4996  180.53  4999.5  180.53  5003.5  181.88  5011.1   186.9 5015.72187.3887
  5070.7  189.55  5170.1  190.43  5220.9  193.05  5249.3  192.59  5271.6  193.01
  5333.8  194.08  5354.6  195.12  5385.8  194.64  5474.8  197.04  5486.5  197.89
#Mann= 7 ,-1 , 0
  4441.4    .125       0  4865.6     .17       0  4964.2     .09       0
 5015.72     .17       0  5170.1     .11       0  5271.6     .17       0
  5474.8     .11       0
Bank Sta=4964.2,5015.72
XS Rating Curve= 0 ,0
Exp/Cntr=0.3,0.1

Type RM Length L Ch R = 1 ,26500   ,353,353,353
BEGIN DESCRIPTION:
SILVERDALE CREEK 53.0
END DESCRIPTION:
XS GIS Cut Line= 3
      3836867.83     10106611.05       3836610.9      10106351.8
      3836181.62     10106373.08
#Sta/Elev= 30
    4635  191.75  4645.1  191.66  4698.6  190.63  4705.7  191.55  4719.8  189.87
    4741  188.79  4783.5  189.13    4939  184.63  4960.2  184.29  4967.3  185.03
  4974.4  183.82  4981.5  183.22  4993.9   178.3  4997.4   178.3  4998.6  180.71
    5004  180.71  5013.1   182.9  5023.1  183.69  5102.5  186.42  5153.2   186.7
    5198  188.51  5233.3  190.05  5263.4  189.58  5294.7  190.68  5303.4  190.14
  5323.4  192.29  5343.5  191.35  5363.5  191.58  5393.5  193.04  5429.8  193.54
#Mann= 7 ,-1 , 0
    4635    .125       0  4645.1     .17       0  4974.4     .09       0
  5023.1     .17       0  5102.5     .11       0    5198     .17       0
  5294.7     .11       0
Bank Sta=4974.4,5023.1
XS Rating Curve= 0 ,0
Exp/Cntr=0.3,0.1

Type RM Length L Ch R = 1 ,26147   ,159,159,159
BEGIN DESCRIPTION:
SILVERDALE CREEK 52.0
END DESCRIPTION:
XS GIS Cut Line= 4
      3837354.89     10106221.24      3836696.01     10106013.77
      3836244.58     10105862.85      3836041.34     10105998.83
#Sta/Elev= 30
  4305.8  194.09  4417.8  192.75  4455.5  190.79  4493.1  190.98  4520.2  189.79
  4622.6  188.77  4719.7  185.69  4795.4  184.92  4827.3  183.47  4859.7  185.11
  4881.1  185.17  4931.7   182.6  4963.2  182.38  4973.7  181.94  4989.2   179.3
  4991.2  175.85  4996.6  176.35  5005.2  179.82  5020.9  180.65  5057.9   180.8
  5089.5  182.26  5178.1  183.88  5236.7  185.62  5318.4  186.13  5374.2  187.26
  5405.9  186.22  5426.3  188.21  5491.5   187.9  5605.6   190.4  5717.1  191.64
#Mann= 6 ,-1 , 0
  4305.8    .125       0  4881.1     .11       0  4963.2     .09       0
  5089.5     .11       0  5178.1     .17       0  5318.4     .11       0
Bank Sta=4963.2,5089.5
XS Rating Curve= 0 ,0
Exp/Cntr=0.3,0.1

Type RM Length L Ch R = 1 ,25988   ,982,982,982
BEGIN DESCRIPTION:
SILVERDALE CREEK 51.0
END DESCRIPTION:
XS GIS Cut Line= 3
      3837430.87     10106084.53      3836643.06     10105860.99
      3836048.42     10105672.18
#Sta/Elev= 30
  4186.5  195.82  4255.7  194.47  4283.2  194.68  4362.6  192.38  4367.8     193
  4387.1  192.14  4459.9  191.21  4508.6  189.29  4532.7  189.13  4553.5  187.68
  4620.7  187.16  4654.6  185.51  4678.2  186.42  4709.4  184.56    4845  181.69
  4878.9  180.74  5024.1  180.99  5040.3  180.59  5040.6  180.09  5115.7  181.95
  5384.2  186.23  5421.7  185.93  5513.3  187.57  5545.5  187.39  5550.8  186.67
    5583  187.24  5588.3  186.68  5598.4  187.78  5620.5  187.33  5629.3  187.81
#Mann= 3 , 0 , 0
  4186.5    .125       0    4845     .06       0  5115.7     .11       0
Bank Sta=4845,5115.7
XS Rating Curve= 0 ,0
Exp/Cntr=0.3,0.1

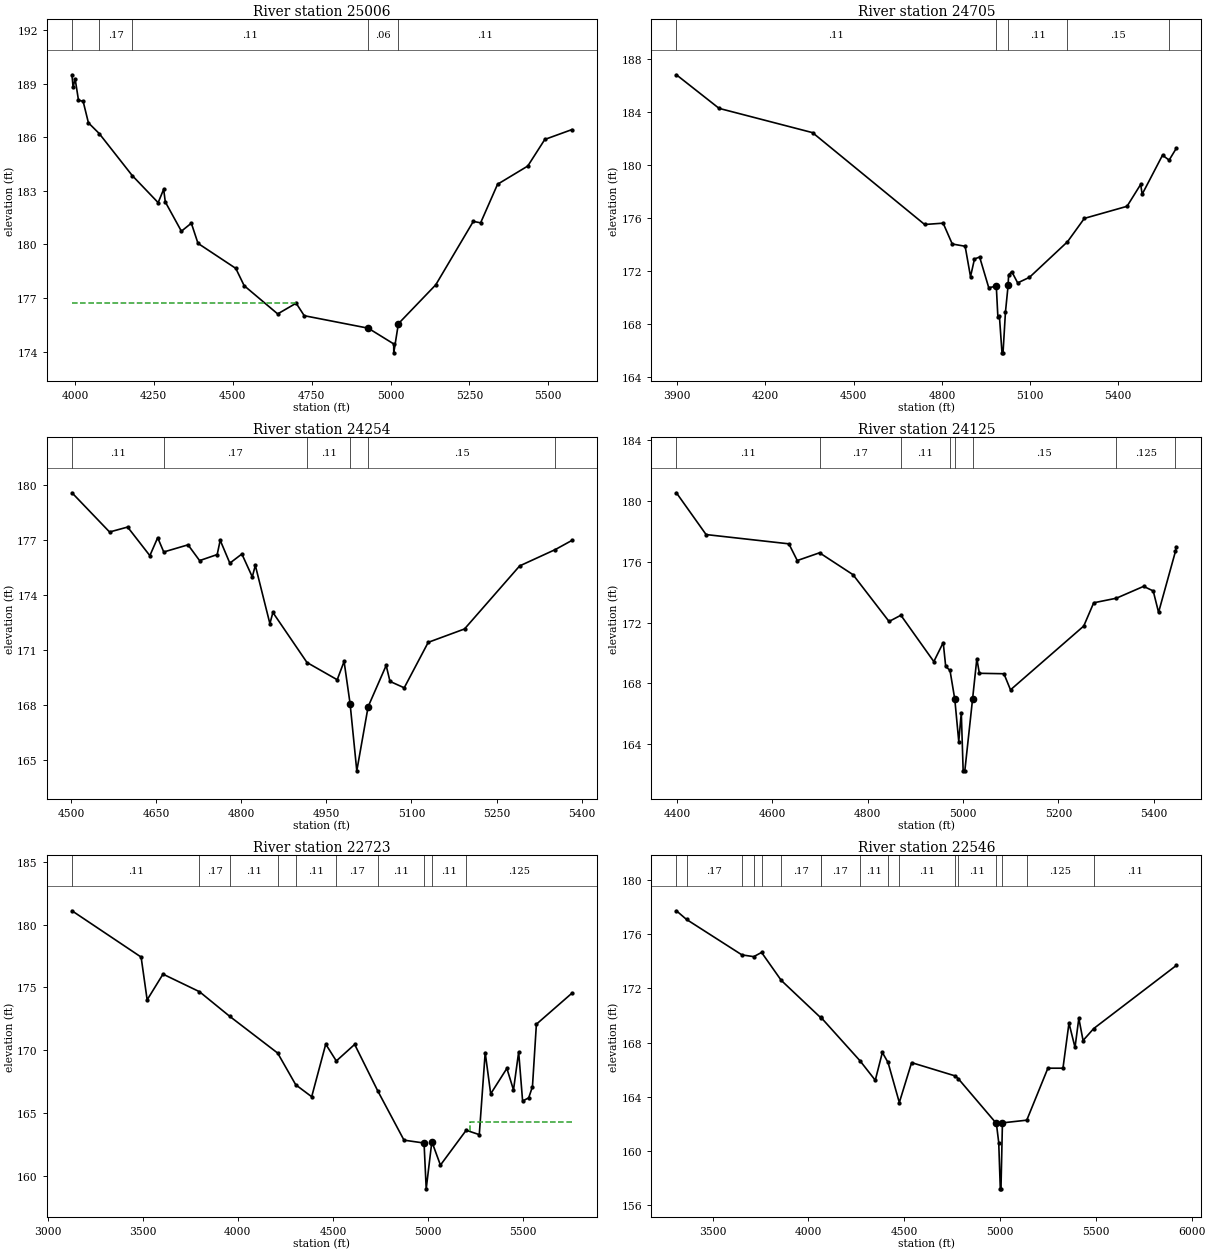
Type RM Length L Ch R = 1 ,25006   ,301,301,301
BEGIN DESCRIPTION:
SILVERDALE CREEK 50.0
END DESCRIPTION:
XS GIS Cut Line= 3
      3837117.42     10105336.73      3836192.11     10105034.65
      3835962.93     10105600.64
#Sta/Elev= 30
  3990.7   189.5  3994.2  188.81  4000.8  189.26  4011.3  188.08  4026.1  188.01
  4042.8  186.81    4077  186.21  4181.5  183.86  4263.8  182.34  4281.2  183.09
  4286.4  182.38  4337.4  180.74  4368.9  181.19    4390  180.06  4509.7  178.66
  4536.3  177.69  4642.5  176.11    4701  176.71  4726.6  176.01  4929.5  175.31
  5010.1  174.43  5010.3  173.93  5024.9  175.56  5143.4  177.74  5262.3  181.29
  5285.5  181.21  5339.2  183.37  5434.9  184.39  5488.9  185.88  5574.7  186.43
#Mann= 5 ,-1 , 0
  3990.7     .11       0    4077     .17       0  4181.5     .11       0
  4929.5     .06       0  5024.9     .11       0
#XS Ineff= 2 , 0
         4700.77  176.71
Permanent Ineff=
       F       F
Bank Sta=4929.5,5024.9
XS Rating Curve= 0 ,0
Exp/Cntr=0.3,0.1

Type RM Length L Ch R = 1 ,24705   ,451,451,451
BEGIN DESCRIPTION:
SILVERDALE CREEK 49.0
END DESCRIPTION:
XS GIS Cut Line= 3
      3837094.89     10105187.43       3836023.7     10104812.43
       3835461.2     10104753.59
#Sta/Elev= 30
  3896.9  186.79  4042.1  184.26  4360.1  182.43  4741.4  175.51  4804.3  175.61
  4835.3  174.04  4879.1  173.87  4897.4  171.58  4910.9  172.91  4928.4  173.06
  4959.4  170.75  4985.1  170.86  4990.5  168.54  4995.7   168.6  5004.5  165.84
    5008  165.84  5016.2   168.9 5025.26170.9163    5027  171.72  5037.7  171.96
  5057.8  171.11    5098  171.53  5227.3  174.21  5284.6  175.97  5429.8  176.88
  5476.2  178.53  5481.3  177.79  5550.5  180.73    5573  180.36  5597.4  181.25
#Mann= 5 ,-1 , 0
  3896.9     .11       0  4985.1     .09       0 5025.26     .11       0
  5227.3     .15       0    5573    .125       0
Bank Sta=4985.1,5025.26
XS Rating Curve= 0 ,0
Exp/Cntr=0.3,0.1

Type RM Length L Ch R = 1 ,24254   ,129,129,129
BEGIN DESCRIPTION:
SILVERDALE CREEK 48.0
END DESCRIPTION:
XS GIS Cut Line= 3
      3836380.42     10104582.26      3835770.23     10104367.99
      3835535.88     10104357.57
#Sta/Elev= 30
  4501.5  179.59  4567.8  177.45  4599.6  177.72  4638.8  176.16  4652.6  177.14
  4663.3  176.36  4706.1  176.75  4726.5  175.89  4757.5  176.22  4762.8     177
  4779.8  175.75    4801  176.25  4819.4     175  4824.7  175.63  4850.4  172.45
  4855.7  173.06  4915.8  170.33  4969.1  169.39  4981.2  170.39  4991.8  168.08
  5003.6  164.42  5023.6  167.92  5055.4  170.17  5062.1   169.3  5087.2  168.95
  5129.5  171.43  5193.5  172.16  5290.7   175.6  5353.4  176.49  5382.8  176.99
#Mann= 6 ,-1 , 0
  4501.5     .11       0  4663.3     .17       0  4915.8     .11       0
  4991.8     .09       0  5023.6     .15       0  5353.4    .125       0
Bank Sta=4991.8,5023.6
XS Rating Curve= 0 ,0
Exp/Cntr=0.3,0.1

Type RM Length L Ch R = 1 ,24125   ,1402,1402,1402
BEGIN DESCRIPTION:
SILVERDALE CREEK 47.0
END DESCRIPTION:
XS GIS Cut Line= 3
      3836436.55     10104505.01      3835923.56     10104321.43
      3835442.33     10104173.16
#Sta/Elev= 30
  4398.7  180.54    4461  177.79  4634.6  177.18  4652.2  176.08  4698.9  176.59
  4769.1  175.15  4844.7  172.07  4869.5  172.48  4938.6  169.43  4958.3  170.68
  4963.5  169.11  4972.5  168.85 4982.57166.9522  4990.9  164.17  4996.2  166.07
  5000.1  162.24  5003.6  162.24 5019.75166.9373  5028.8  169.62  5034.1  168.66
  5085.6  168.63  5099.4  167.57    5253  171.77  5273.9   173.3  5321.3   173.6
  5378.5  174.38  5398.7  174.08  5409.9  172.67  5445.3  176.68  5447.1  176.99
#Mann= 8 ,-1 , 0
  4398.7     .11       0  4698.9     .17       0  4869.5     .11       0
  4972.5     .15       0 4982.57     .09       0 5019.75     .15       0
  5321.3    .125       0  5445.3     .15       0
#XS Ineff= 2 , 0
                          5028.8          169.62
Permanent Ineff=
       F       F
Bank Sta=4982.57,5019.75
XS Rating Curve= 0 ,0
Exp/Cntr=0.3,0.1

Type RM Length L Ch R = 1 ,22723   ,177,177,177
BEGIN DESCRIPTION:
SILVERDALE CREEK 46.0
END DESCRIPTION:
XS GIS Cut Line= 3
      3837552.44     10103620.18      3835773.82     10103021.23
      3835047.56       10102826.
#Sta/Elev= 30
  3127.8  181.11  3491.4  177.42  3523.1  174.01  3606.4  176.06  3798.3  174.66
  3957.1   172.7  4209.4  169.77  4304.6  167.24  4388.3  166.29  4462.2  170.48
  4517.8  169.14  4614.3  170.46  4735.9  166.75  4873.7  162.83  4979.2   162.6
  4990.5  158.95  5020.2  162.71  5065.3  160.84  5200.8  163.62  5269.6  163.27
  5300.7  169.81  5329.6  166.52  5414.7  168.55  5449.5  166.83  5476.7  169.86
  5497.4  165.95  5529.4   166.2  5549.2  167.09  5569.9  172.07  5756.6  174.54
#Mann= 10 ,-1 , 0
  3127.8     .11       0  3798.3     .17       0  3957.1     .11       0
  4209.4     .17       0  4304.6     .11       0  4517.8     .17       0
  4735.9     .11       0  4979.2     .09       0  5020.2     .11       0
  5200.8    .125       0
#XS Ineff= 2 , 0
                         5219.59          164.31
Permanent Ineff=
       F       F
Bank Sta=4979.2,5020.2
XS Rating Curve= 0 ,0
Exp/Cntr=0.3,0.1

Type RM Length L Ch R = 1 ,22546   ,468,468,468
BEGIN DESCRIPTION:
SILVERDALE CREEK 45.0
END DESCRIPTION:
XS GIS Cut Line= 3
       3837443.1     10103396.23      3835851.95     10102864.98
      3834963.92     10102583.73
#Sta/Elev= 30
    3311  177.71  3364.1  177.07  3652.9  174.46  3714.7  174.33  3755.6  174.64
  3858.3  172.58  4063.7  169.84  4065.2  169.86  4269.1  166.66    4349  165.22
  4385.9  167.27  4415.7  166.53  4474.5  163.58  4538.6  166.52  4766.3  165.54
  4782.6  165.33    4981  162.04  4993.3  160.63  5001.5  157.22    5005  157.22
 5012.63162.0814  5139.6  162.28  5249.8  166.11  5328.5  166.11  5359.9  169.43
  5391.4  167.64  5411.3  169.79  5433.4  168.15  5488.9  169.03    5920  173.68
#Mann= 17 ,-1 , 0
    3311     .11       0  3364.1     .17       0  3652.9     .11       0
  3714.7     .17       0  3755.6     .11       0  3858.3     .17       0
  4063.7     .11       0  4065.2     .17       0  4269.1     .11       0
  4415.7     .17       0  4474.5     .11       0  4766.3     .17       0
  4782.6     .11       0    4981     .09       0 5012.63     .11       0
  5139.6    .125       0  5488.9     .11       0
#XS Ineff= 2 , 0
         4538.37  166.49
Permanent Ineff=
       F       F
Bank Sta=4981,5012.63
XS Rating Curve= 0 ,0
Exp/Cntr=0.3,0.1

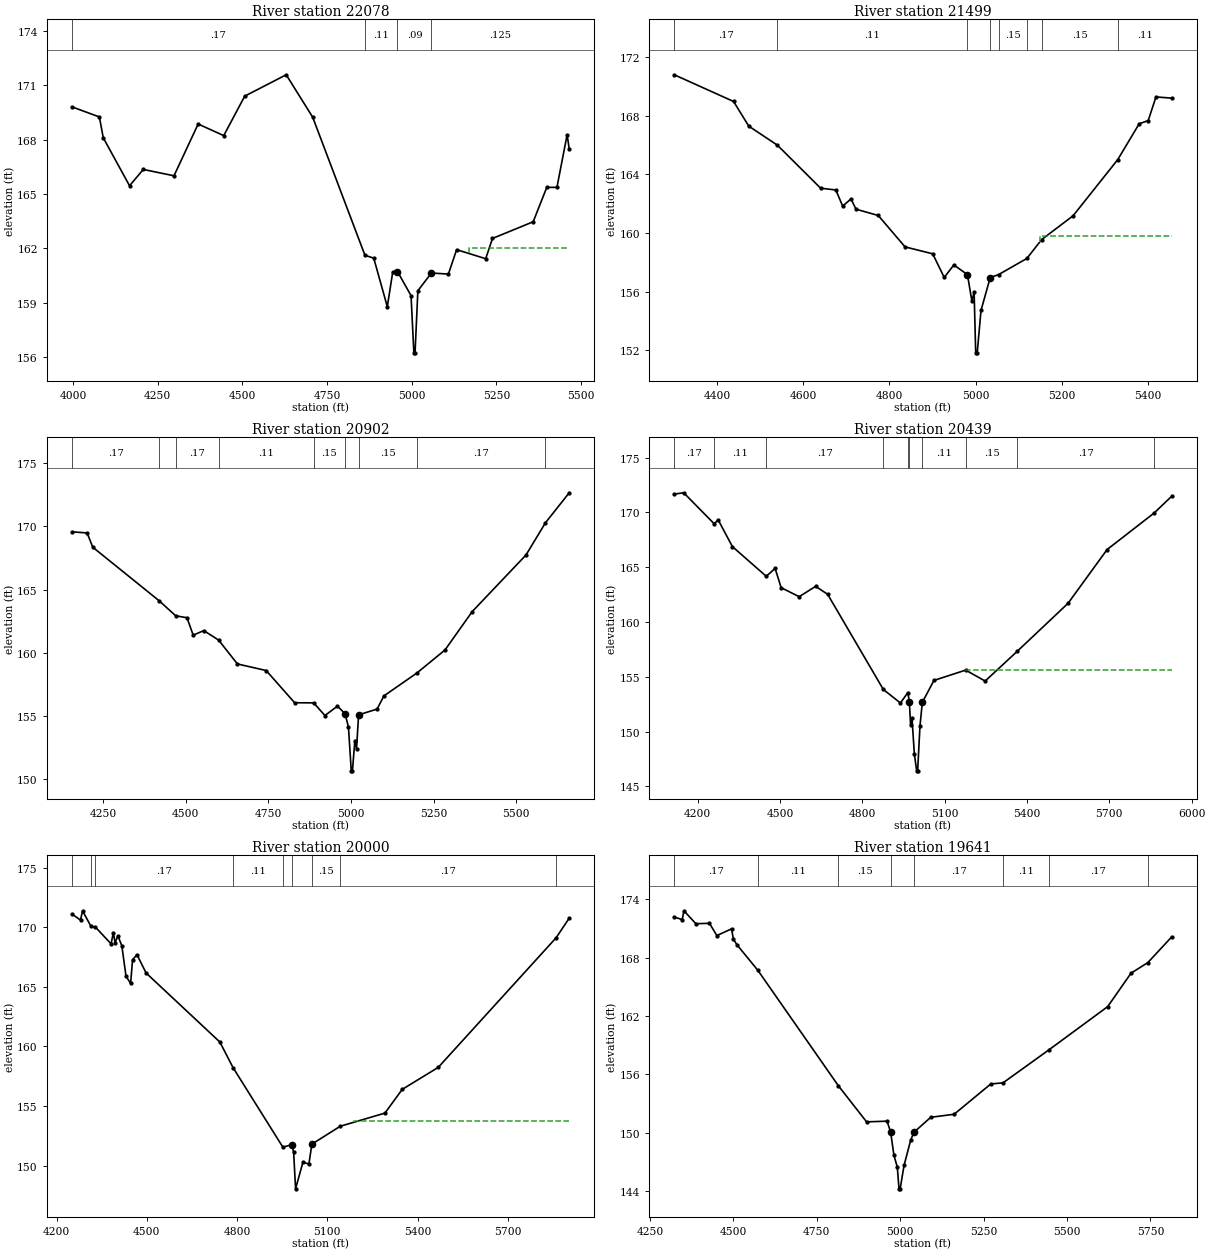
Type RM Length L Ch R = 1 ,22078   ,579,579,579
BEGIN DESCRIPTION:
SILVERDALE CREEK 44.0
END DESCRIPTION:
XS GIS Cut Line= 3
       3836575.9     10103026.42      3836338.92      10102443.1
      3835501.64     10102398.25
#Sta/Elev= 30
  3996.8  169.82  4078.1  169.26  4089.5  168.11  4167.1  165.46  4207.7  166.36
  4298.3  166.01  4369.6  168.87  4445.1  168.23  4507.1  170.41  4629.5  171.59
  4707.6  169.25  4861.9  161.62  4887.9  161.46  4927.9  158.78  4943.9  160.69
    4958  160.72    4998  159.39  5006.3  156.23  5009.8  156.23  5018.1  159.66
  5058.1  160.64  5108.2  160.58  5132.5  161.93  5218.3  161.43  5238.4  162.55
  5358.5  163.47  5398.6  165.37  5428.6  165.37  5458.7  168.28  5464.9  167.48
#Mann= 4 ,-1 , 0
  3996.8     .17       0  4861.9     .11       0    4958     .09       0
  5058.1    .125       0
#XS Ineff= 2 , 0
                         5167.85          162.03
Permanent Ineff=
       F       F
Bank Sta=4958,5058.1
XS Rating Curve= 0 ,0
Exp/Cntr=0.3,0.1

Type RM Length L Ch R = 1 ,21499   ,597,597,597
BEGIN DESCRIPTION:
SILVERDALE CREEK 43.0
END DESCRIPTION:
XS GIS Cut Line= 3
      3836367.58     10102419.71      3836245.17     10101950.92
      3835605.94     10101745.63
#Sta/Elev= 30
  4299.9  170.78  4437.7  168.96    4473  167.28  4539.6  165.98    4640  163.05
  4675.3  162.93  4691.2  161.83  4710.6  162.32  4722.2  161.62  4773.9  161.19
  4836.2  159.05  4900.4  158.58  4927.2  156.97  4949.6  157.82  4981.2  157.16
  4991.4  155.38  4996.7  155.95  5000.4  151.83  5003.9  151.83  5012.7  154.72
  5034.1  156.96  5053.4  157.16  5119.2  158.26  5153.7  159.55  5226.7  161.17
  5330.5     165  5380.3  167.44  5401.3  167.66  5419.3  169.27  5455.8  169.19
#Mann= 8 ,-1 , 0
  4299.9     .17       0  4539.6     .11       0  4981.2     .09       0
  5034.1     .11       0  5053.4     .15       0  5119.2     .11       0
  5153.7     .15       0  5330.5     .11       0
#XS Ineff= 2 , 0
                         5149.24          159.79
Permanent Ineff=
       F       F
Bank Sta=4981.2,5034.1
XS Rating Curve= 0 ,0
Exp/Cntr=0.3,0.1

Type RM Length L Ch R = 1 ,20902   ,463,463,463
BEGIN DESCRIPTION:
SILVERDALE CREEK 42.0
END DESCRIPTION:
XS GIS Cut Line= 3
      3836391.01     10102383.24      3836224.34     10101492.58
      3835641.95     10101357.38
#Sta/Elev= 30
    4156  169.57  4202.2  169.48  4219.3  168.35  4420.5   164.1  4470.1  162.92
  4504.1  162.77    4523  161.39    4555  161.75  4599.8     161  4656.7  159.11
  4743.6  158.59  4829.7  156.04  4887.2  156.03  4921.2  155.03  4959.2  155.77
  4982.3  155.17  4992.4  154.11  5000.9  150.65  5004.4  150.65  5011.8  153.05
  5016.9  152.38    5023  155.08    5079  155.54  5099.6  156.58  5199.7   158.4
  5284.4  160.22  5366.5  163.25  5529.4  167.74  5588.2  170.29    5660  172.66
#Mann= 9 ,-1 , 0
    4156     .17       0  4420.5     .11       0  4470.1     .17       0
  4599.8     .11       0  4887.2     .15       0  4982.3     .09       0
    5023     .15       0  5199.7     .17       0  5588.2     .11       0
Bank Sta=4982.3,5023
XS Rating Curve= 0 ,0
Exp/Cntr=0.3,0.1

Type RM Length L Ch R = 1 ,20439   ,439,439,439
BEGIN DESCRIPTION:
SILVERDALE CREEK 41.0
END DESCRIPTION:
XS GIS Cut Line= 3
      3837078.51     10101987.37      3836742.57     10101364.98
      3835656.65     10101159.25
#Sta/Elev= 30
  4114.7  171.67    4149  171.79  4260.2  168.96  4274.6  169.32  4326.4  166.88
  4449.8  164.17  4482.2  164.89  4504.1  163.13  4569.7  162.31  4629.7  163.25
  4673.5  162.53  4876.3  153.85  4938.7  152.61  4965.9  153.56 4971.36152.7139
  4975.8  150.61  4980.9  151.21  4989.6  147.95    4998  146.42  5001.5  146.42
    5010  150.51 5018.59152.6702  5060.9  154.67  5176.6  155.61  5247.5  154.61
  5364.6  157.33  5549.4   161.7  5691.9  166.61  5863.1  169.94  5927.2  171.47
#Mann= 10 ,-1 , 0
  4114.7     .17       0  4260.2     .11       0  4449.8     .17       0
  4876.3     .15       0  4965.9     .11       0 4971.36     .06       0
 5018.59     .11       0  5176.6     .15       0  5364.6     .17       0
  5863.1     .11       0
#XS Ineff= 2 , 0
                         5172.79          155.65
Permanent Ineff=
       F       F
Bank Sta=4971.36,5018.59
XS Rating Curve= 0 ,0
Exp/Cntr=0.3,0.1

Type RM Length L Ch R = 1 ,20000   ,359,359,359
BEGIN DESCRIPTION:
SILVERDALE CREEK 40.0
END DESCRIPTION:
XS GIS Cut Line= 3
      3837217.86     10100611.07      3836586.78     10101014.85
       3835682.8     10100987.38
#Sta/Elev= 30
  4250.8  171.11  4279.6   170.6  4286.4  171.38  4314.4  170.07  4328.8  170.02
  4381.4   168.6  4388.6  169.55  4394.6  168.71  4403.9  169.28    4417  168.44
  4430.9  165.89  4446.2  165.29  4452.6  167.27  4467.3   167.7  4497.7  166.16
    4743  160.37  4786.6  158.23  4952.5  151.55  4982.3  151.77  4988.2  151.13
  4994.6  148.06  5018.9  150.28  5038.9  150.15  5048.9  151.81  5143.2  153.31
  5291.6  154.41  5349.1   156.4  5469.1  158.25  5860.6  169.11  5904.4  170.76
#Mann= 9 ,-1 , 0
  4250.8     .17       0  4314.4     .11       0  4328.8     .17       0
  4786.6     .11       0  4952.5     .15       0  4982.3     .09       0
  5048.9     .15       0  5143.2     .17       0  5860.6     .11       0
#XS Ineff= 2 , 0
                          5188.9          153.76
Permanent Ineff=
       F       F
Bank Sta=4982.3,5048.9
XS Rating Curve= 0 ,0
Exp/Cntr=0.3,0.1

Type RM Length L Ch R = 1 ,19641   ,615,615,615
BEGIN DESCRIPTION:
SILVERDALE CREEK 39.0
END DESCRIPTION:
XS GIS Cut Line= 3
      3837141.01     10100549.87      3836479.55      10100693.1
      3835666.04      10100706.1
#Sta/Elev= 30
  4323.3  172.19    4347  171.92  4352.3  172.83  4387.9   171.5  4428.8  171.54
  4450.8  170.28  4494.8  170.97  4500.5  169.92  4510.7  169.35  4573.6  166.71
    4815  154.83  4899.5  151.12  4960.9  151.19  4971.6  150.07  4981.4  147.69
  4991.6  146.46  4996.6  144.23  5000.1  144.23  5011.8  146.64  5031.8  149.26
  5041.8  150.06  5091.8  151.59  5161.8   151.9  5271.8  155.02  5308.3  155.13
  5446.1  158.53  5621.9  162.97  5691.9  166.41  5742.3   167.5  5813.7  170.14
#Mann= 8 ,-1 , 0
  4323.3     .17       0  4573.6     .11       0    4815     .15       0
  4971.6     .09       0  5041.8     .17       0  5308.3     .11       0
  5446.1     .17       0  5742.3     .11       0
Bank Sta=4971.6,5041.8
XS Rating Curve= 0 ,0
Exp/Cntr=0.3,0.1

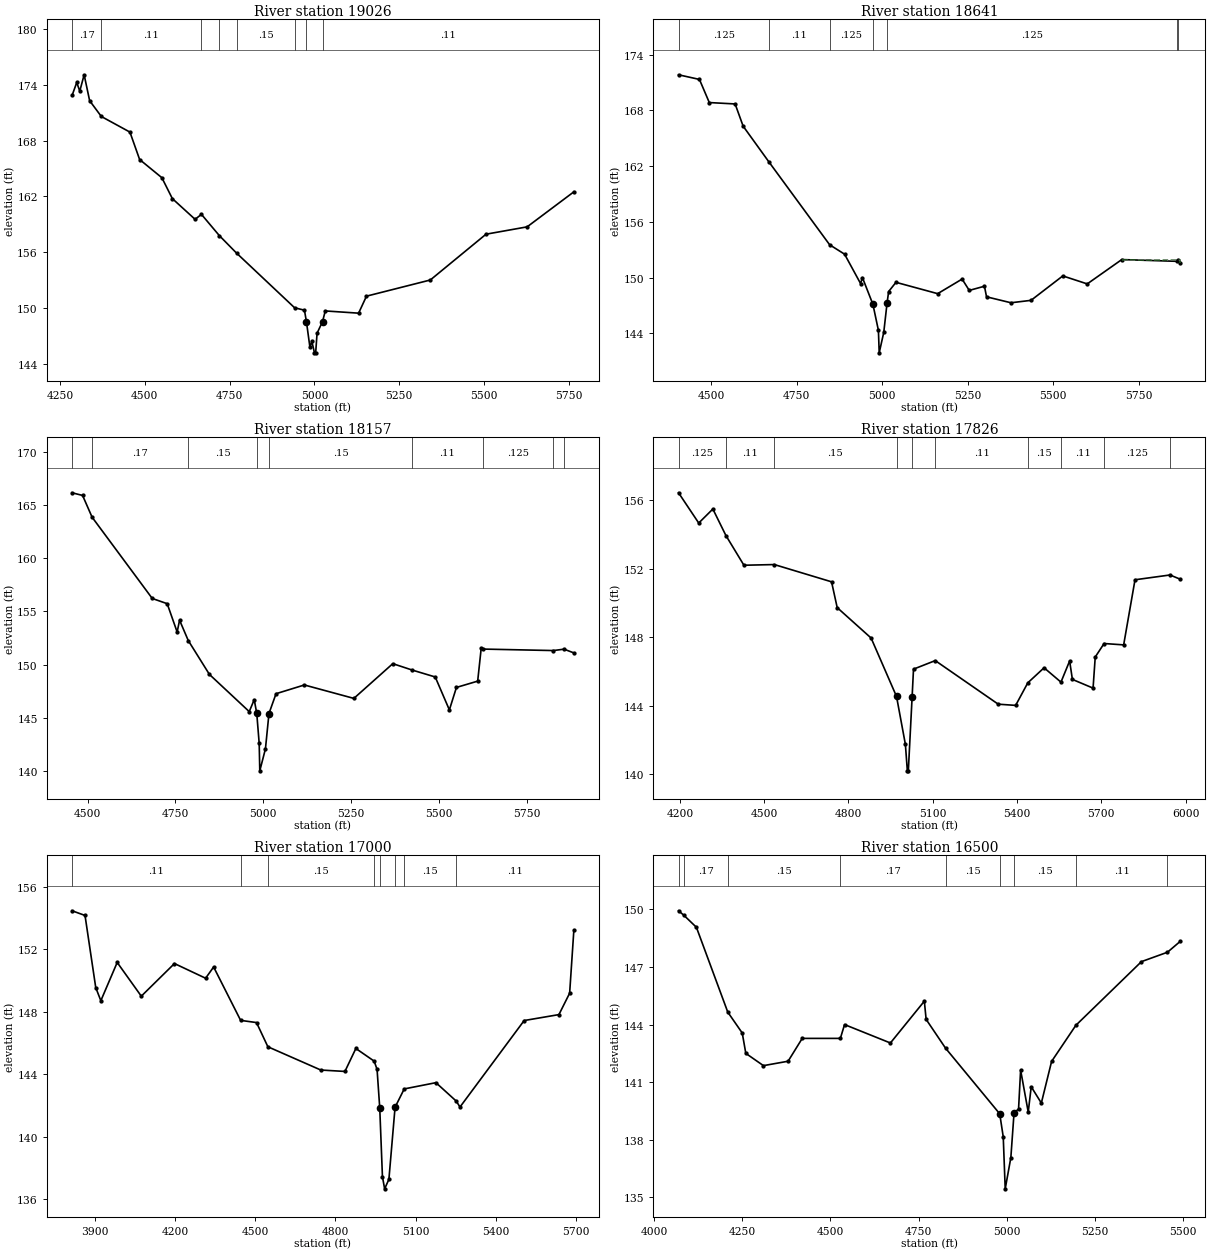
Type RM Length L Ch R = 1 ,19026   ,385,385,385
BEGIN DESCRIPTION:
SILVERDALE CREEK 38.0
END DESCRIPTION:
XS GIS Cut Line= 3
      3837067.84     10100511.07      3836432.46     10100166.84
      3835741.44     10099857.83
#Sta/Elev= 30
  4285.4  172.85  4299.2  174.25  4308.1  173.32    4321  175.08  4337.2  172.29
  4371.7  170.59    4456  168.91  4484.6  165.96  4550.2     164  4581.1  161.75
  4648.2  159.52  4666.8  160.06  4719.6  157.77  4770.3  155.89  4941.6     150
  4970.6  149.74  4976.5148.4914  4986.8  145.74  4992.4  146.38  5000.2  145.15
  5003.7  145.15  5007.8  147.26    5024  148.52    5032  149.66  5130.3  149.42
  5153.5  151.25  5341.7  152.99    5506  157.92  5627.2  158.71    5765  162.48
#Mann= 8 ,-1 , 0
  4285.4     .17       0  4371.7     .11       0  4666.8     .15       0
  4719.6     .11       0  4770.3     .15       0  4941.6     .11       0
  4976.5     .09       0    5024     .11       0
#XS Ineff= 2 , 0
                          5153.5          151.25
Permanent Ineff=
       F       F
Bank Sta=4976.5,5024
XS Rating Curve= 0 ,0
Exp/Cntr=0.3,0.1

Type RM Length L Ch R = 1 ,18641   ,484,484,484
BEGIN DESCRIPTION:
SILVERDALE CREEK 37.0
END DESCRIPTION:
XS GIS Cut Line= 3
      3837117.89     10100061.09       3836575.9     10099822.79
      3835861.28     10099318.66
#Sta/Elev= 30
  4404.9  171.83    4466  171.33  4494.8  168.84  4570.3  168.69  4593.7   166.3
  4668.3  162.49  4846.6  153.53  4890.2  152.52  4936.9  149.36  4942.4     150
    4973  147.12  4989.1  144.32  4991.4   141.9  5004.7   144.1 5014.37147.2579
    5019   148.5  5040.4  149.49  5162.3  148.27  5233.7  149.84  5254.6  148.62
    5299  149.07  5305.1  147.93  5376.5  147.29  5435.1  147.55    5528  150.18
  5599.4  149.32  5700.4  151.94  5862.1  151.75  5865.5  151.94  5871.5   151.6
#Mann= 7 ,-1 , 0
  4404.9    .125       0  4668.3     .11       0  4846.6    .125       0
    4973     .09       0 5014.37    .125       0  5862.1     .11       0
  5865.5    .125       0
#XS Ineff= 2 , 0
       0                  5700.4       0  151.94
Permanent Ineff=
       F       F
Bank Sta=4973,5014.37
XS Rating Curve= 0 ,0
Exp/Cntr=0.3,0.1

Type RM Length L Ch R = 1 ,18157   ,331,331,331
BEGIN DESCRIPTION:
SILVERDALE CREEK 36.0
END DESCRIPTION:
XS GIS Cut Line= 3
      3837098.89     10099752.46      3836710.45     10099381.38
      3835825.88     10099285.99
#Sta/Elev= 30
  4456.1  166.13    4486  165.88    4513  163.84  4684.1  156.21  4726.6  155.72
  4754.9  153.06  4761.8  154.17  4786.5  152.26  4846.7  149.08  4959.9  145.59
  4974.1  146.71  4981.3  145.42  4988.2   142.6  4989.9  140.03    5006   142.1
    5016  145.41  5036.1  147.27  5116.6  148.09  5257.4  146.83  5368.1  150.09
  5423.3  149.49  5488.8  148.84    5529  145.75  5549.1  147.86  5609.5  148.45
  5619.5  151.53    5624  151.46  5824.7  151.32  5855.1  151.45    5883   151.1
#Mann= 9 ,-1 , 0
  4456.1     .11       0    4513     .17       0  4786.5     .15       0
  4981.3     .09       0    5016     .15       0  5423.3     .11       0
    5624    .125       0  5824.7     .11       0  5855.1    .125       0
Bank Sta=4981.3,5016
XS Rating Curve= 0 ,0
Exp/Cntr=0.3,0.1

Type RM Length L Ch R = 1 ,17826   ,826,826,826
BEGIN DESCRIPTION:
SILVERDALE CREEK 35.0
END DESCRIPTION:
XS GIS Cut Line= 3
      3837639.32     10099222.97       3836721.3     10099123.14
      3835868.41     10099253.35
#Sta/Elev= 30
  4195.2  156.45  4267.1  154.68  4317.4   155.5  4363.8  153.95    4428  152.21
  4536.1  152.25  4739.9  151.24    4760  149.73  4880.7  147.95  4971.2  144.53
  5002.7  141.73  5009.7  140.18  5013.2  140.18  5026.6144.4815  5031.6  146.13
    5109  146.63  5333.2  144.08  5395.2  144.01  5438.5  145.33  5496.4  146.21
  5556.5  145.37  5587.4  146.61  5597.2  145.53  5670.8  145.02  5678.5  146.84
    5710  147.63  5779.7  147.55  5820.1  151.36  5944.7  151.64  5981.4  151.39
#Mann= 10 ,-1 , 0
  4195.2    .125       0  4363.8     .11       0  4536.1     .15       0
  4971.2     .09       0  5026.6     .15       0    5109     .11       0
  5438.5     .15       0  5556.5     .11       0    5710    .125       0
  5944.7     .11       0
Bank Sta=4971.2,5026.6
XS Rating Curve= 0 ,0
Exp/Cntr=0.3,0.1

Type RM Length L Ch R = 1 ,17000   ,500,500,500
BEGIN DESCRIPTION:
SILVERDALE CREEK 34.0
END DESCRIPTION:
XS GIS Cut Line= 3
      3837626.24     10098934.34      3836443.69     10098846.61
      3835752.01     10098873.54
#Sta/Elev= 30
  3814.2  154.48  3862.7  154.18  3902.8  149.56  3921.9  148.72  3983.1  151.17
  4073.3  149.01  4197.4   151.1    4314  150.16    4344  150.88  4445.1  147.46
  4504.5  147.32    4547  145.77  4745.1  144.28  4835.4  144.19  4876.3  145.66
  4944.8  144.85  4955.7  144.32  4965.7  141.85  4975.8  137.45    4984  136.67
    5000  137.28 5023.05141.8954  5057.3  143.07    5176  143.47    5252  142.29
    5266  141.91  5506.2  147.45  5636.3  147.83  5676.4   149.2  5692.2  153.24
#Mann= 8 ,-1 , 0
  3814.2     .11       0  4445.1     .17       0    4547     .15       0
  4944.8     .17       0  4965.7     .09       0 5023.05     .17       0
  5057.3     .15       0    5252     .11       0
Bank Sta=4965.7,5023.05
XS Rating Curve= 0 ,0
Exp/Cntr=0.3,0.1

Type RM Length L Ch R = 1 ,16500   ,348,348,348
BEGIN DESCRIPTION:
SILVERDALE CREEK 33.0
END DESCRIPTION:
XS GIS Cut Line= 3
      3837068.55     10098543.91      3836138.19     10098506.82
      3835711.79     10098753.87
#Sta/Elev= 30
  4068.9  149.93  4083.8   149.7  4119.6  149.07  4208.6  144.65  4249.7  143.56
  4259.8   142.5  4309.8  141.86  4379.8  142.09  4419.9  143.28  4528.1  143.28
    4540     144  4670.1  143.04  4766.4  145.22  4771.5  144.27  4826.6  142.77
  4980.3  139.35  4990.3  138.15  4995.9  135.44  5011.9  137.07  5020.9139.3869
  5033.8  139.61  5039.6  141.63  5061.2  139.44  5069.7  140.76  5098.4  139.91
  5127.5  142.08  5196.3  143.96  5382.5  147.28  5456.3  147.77  5492.8  148.34
#Mann= 9 ,-1 , 0
  4068.9     .11       0  4083.8     .17       0  4208.6     .15       0
  4528.1     .17       0  4826.6     .15       0  4980.3     .09       0
  5020.9     .15       0  5196.3     .11       0  5456.3    .125       0
Bank Sta=4980.3,5020.9
XS Rating Curve= 0 ,0
Exp/Cntr=0.3,0.1