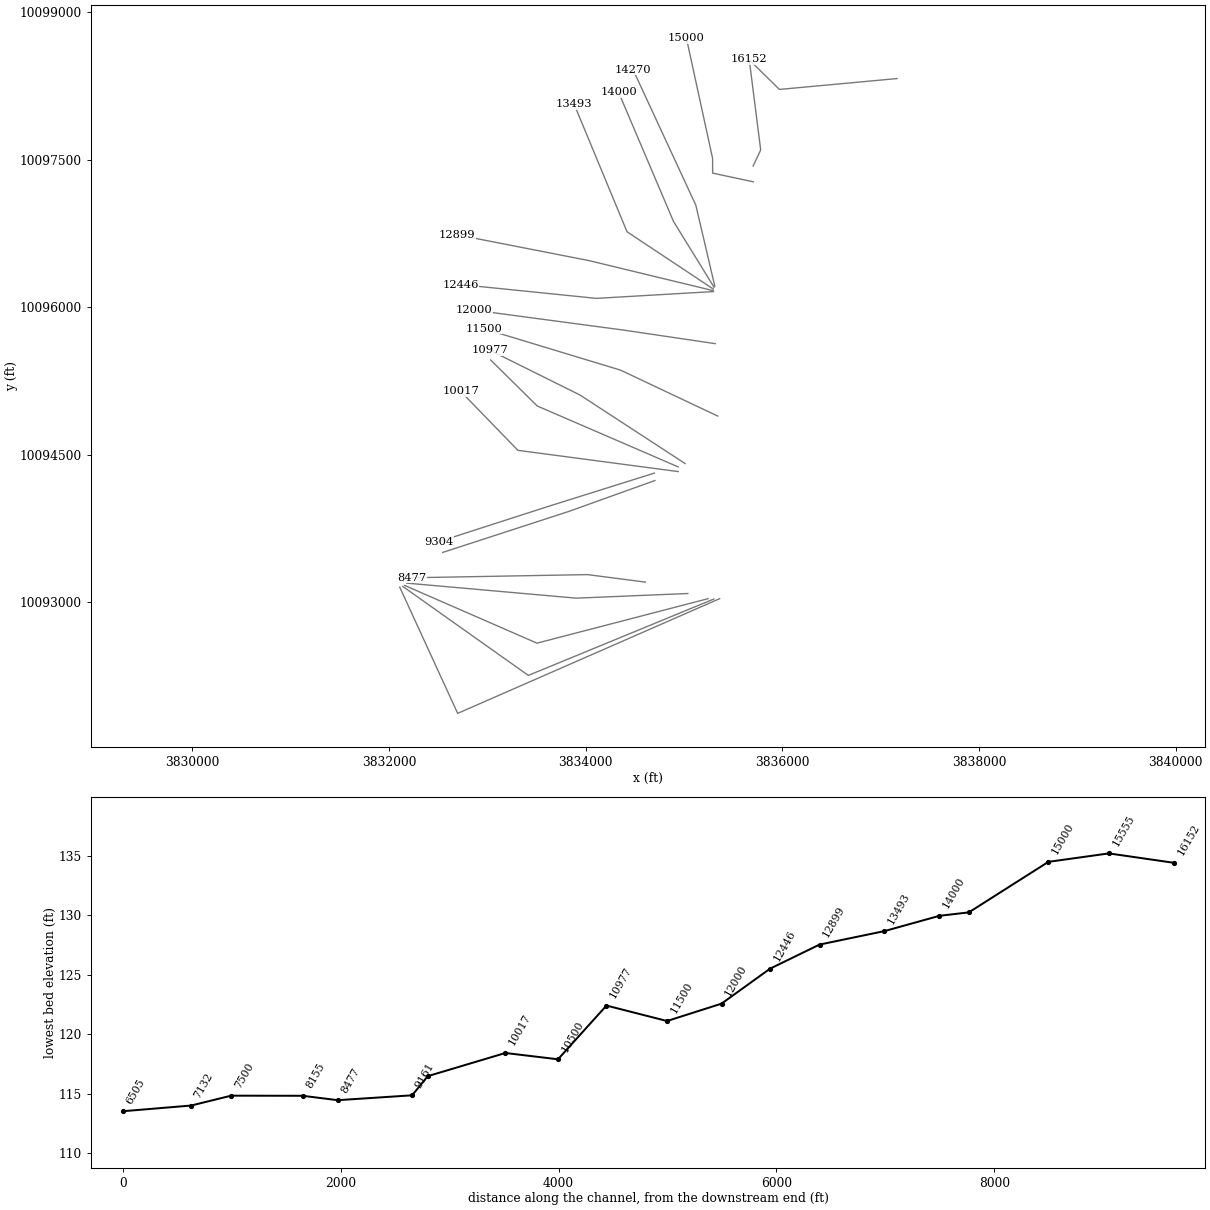
HEC-RAS study SILVERDALE CREEK.prj: SILVERDALE CREEK Base Level Engineering

--- SILVERDALE CREEK.g01 (geometry) --- (continued)

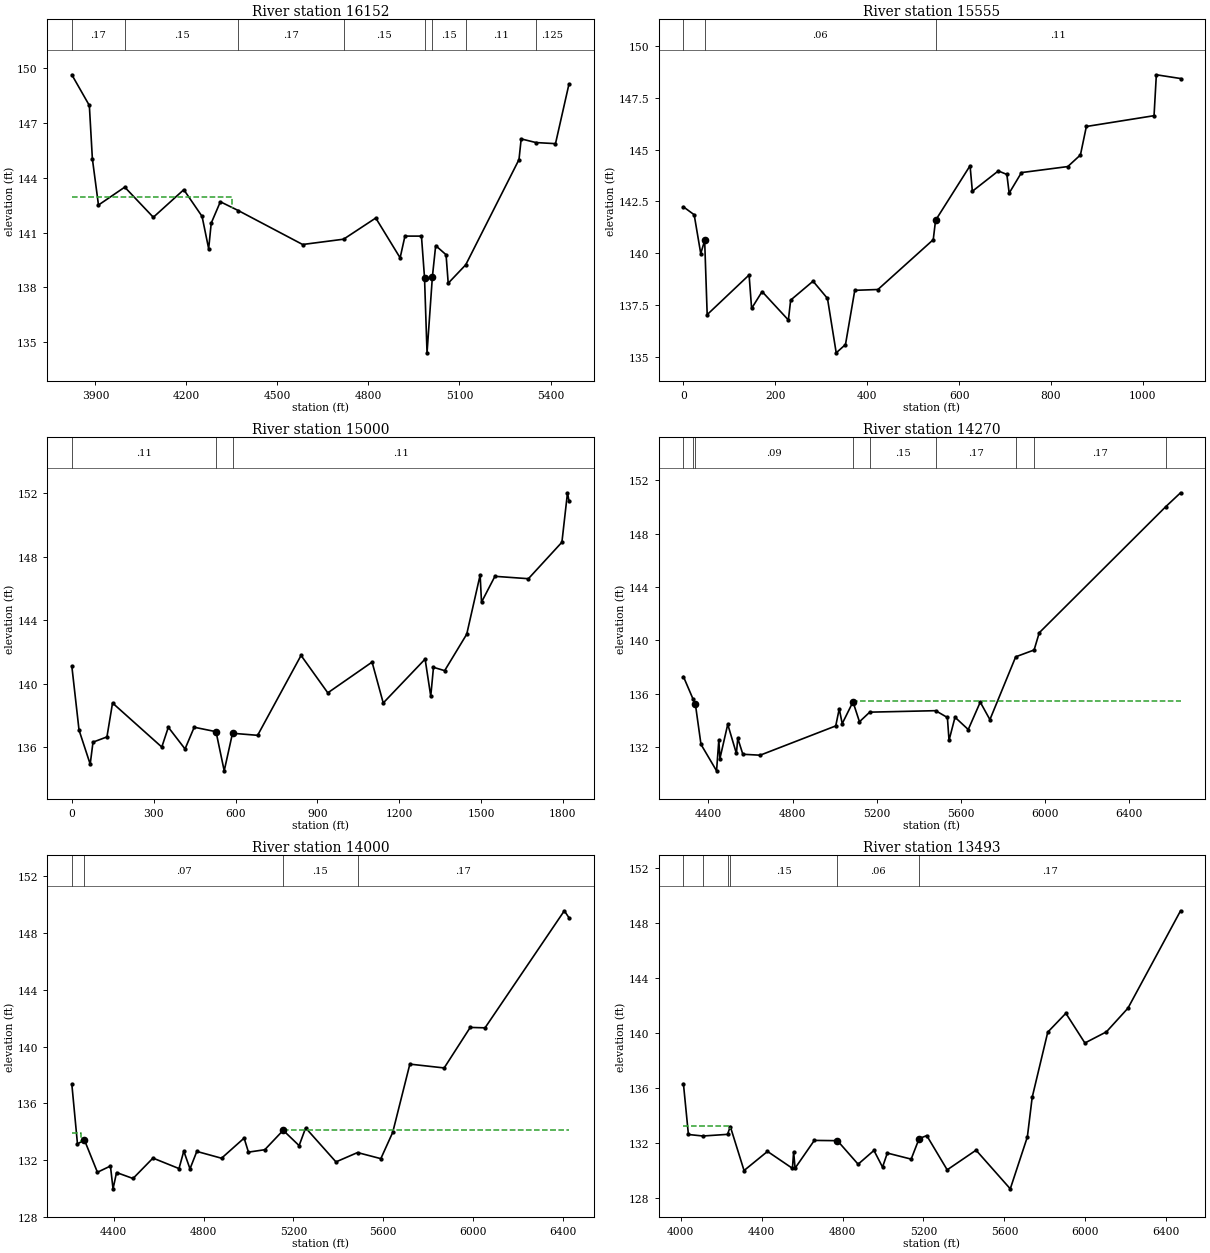
Type RM Length L Ch R = 1 ,16152   ,597,597,597
BEGIN DESCRIPTION:
SILVERDALE CREEK 32.0
END DESCRIPTION:
XS GIS Cut Line= 3
      3837165.27     10098327.33      3835969.57     10098216.66
      3835657.05     10098523.09
#Sta/Elev= 30
  3822.3  149.64    3880  147.96    3890  145.04  3910.1  142.51  3996.7  143.49
  4090.9  141.84  4191.3  143.35  4251.5  141.89  4273.3  140.12  4281.7  141.52
  4311.8  142.69  4370.7  142.21    4583  140.35  4717.9  140.64    4824   141.8
  4904.3  139.62  4920.2  140.81  4974.6  140.81  4984.7  138.54    4993  134.42
  5010.6138.5761  5021.5  140.29  5055.7  139.79  5062.8  138.23  5120.6  139.24
  5296.1     145  5303.3  146.13    5352  145.93  5416.4  145.87  5460.8  149.13
#Mann= 8 ,-1 , 0
  3822.3     .17       0  3996.7     .15       0  4370.7     .17       0
  4717.9     .15       0  4984.7     .09       0  5010.6     .15       0
  5120.6     .11       0    5352    .125       0
#XS Ineff= 2 , 0
         4351.56  142.95
Permanent Ineff=
       F       F
Bank Sta=4984.7,5010.6
XS Rating Curve= 0 ,0
Exp/Cntr=0.3,0.1

Type RM Length L Ch R = 1 ,15555   ,555,555,555
XS GIS Cut Line= 3
      3835701.85     10097437.01      3835779.03     10097600.68
      3835665.75     10098494.43
#Sta/Elev= 30
       0  142.24    23.4  141.86    37.7  139.99    46.2  140.62    51.7  137.05
   142.9  138.96   148.4  137.35   171.2  138.16   228.4  136.79   233.4  137.75
   282.1  138.66   313.5  137.83   332.5  135.21   352.7  135.61   372.9  138.22
   423.3  138.26   543.7  140.66   548.7  141.59   623.8  144.22   628.8  142.99
   685.3  143.97   703.9   143.8   708.9   142.9   735.7  143.89   836.5  144.18
     864  144.74   876.9  146.11  1024.2  146.63  1029.2   148.6  1081.9  148.42
#Mann= 3 , 0 , 0
       0     .11       0    46.2     .06       0   548.7     .11       0
Bank Sta=46.2,548.7
XS Rating Curve= 0 ,0
Exp/Cntr=0.3,0.1

Type RM Length L Ch R = 1 ,15000   ,730,730,730
XS GIS Cut Line= 4
      3835703.71      10097276.8      3835290.42     10097365.12
      3835290.02     10097514.68      3835023.93     10098736.64
#Sta/Elev= 30
       0   141.1    26.4  137.07    67.3  134.92    77.6  136.31   128.7  136.64
   149.2  138.78   329.8     136   353.7  137.25     415  135.88   448.6  137.25
   528.6  136.97   558.6   134.5     589  136.87   681.1  136.74   840.3  141.78
   938.4  139.42  1100.7  141.36  1141.6  138.78  1295.1  141.55  1315.8  139.21
  1325.8  141.03  1366.8  140.82  1447.7  143.12  1496.8  146.85  1501.9  145.14
    1551  146.77  1673.8  146.62  1796.6  148.92  1817.1  152.04  1822.5  151.53
#Mann= 3 , 0 , 0
       0     .11       0   528.6     .09       0     589     .11       0
Bank Sta=528.6,589
XS Rating Curve= 0 ,0
Exp/Cntr=0.3,0.1

Type RM Length L Ch R = 1 ,14270   ,270,270,270
BEGIN DESCRIPTION:
SILVERDALE CREEK 29.0
END DESCRIPTION:
XS GIS Cut Line= 3
      3835312.13     10096215.79      3835119.42     10097038.73
       3834481.2     10098417.48
#Sta/Elev= 30
  4280.8   137.3  4327.3  135.59  4337.6  135.24  4364.3  132.23  4438.4  130.25
  4449.2  132.56  4454.4  131.17  4491.6  133.73  4532.7  131.55  4539.3  132.68
  4563.5  131.49  4645.7  131.42  5005.2  133.61  5021.9  134.89    5036  133.78
  5087.3  135.41  5118.1  133.92  5166.9  134.64  5480.3  134.75  5536.3  134.24
  5544.1  132.53  5572.5  134.26  5635.5  133.34  5692.6  135.39  5738.5  134.08
  5861.2  138.78  5948.7  139.29  5973.2  140.58  6574.2     150  6645.3  151.05
#Mann= 9 ,-1 , 0
  4280.8    .125       0  4327.3     .12       0  4337.6     .09       0
  5087.3     .11       0  5166.9     .15       0  5480.3     .17       0
  5861.2     .11       0  5948.7     .17       0  6574.2     .11       0
#XS Ineff= 2 , 0
                         5087.52          135.44
Permanent Ineff=
       F       F
Bank Sta=4337.6,5087.3
XS Rating Curve= 0 ,0
Exp/Cntr=0.3,0.1

Type RM Length L Ch R = 1 ,14000   ,507,507,507
BEGIN DESCRIPTION:
SILVERDALE CREEK 28.0
END DESCRIPTION:
XS GIS Cut Line= 3
       3835305.2     10096203.34      3834892.66     10096872.73
      3834334.91     10098185.56
#Sta/Elev= 30
  4213.7  137.34  4238.8  133.13  4269.6  133.41  4327.6  131.13  4385.5  131.57
  4397.1  129.96  4412.7  131.11    4486  130.69  4574.8  132.13  4690.7  131.39
    4712  132.62  4739.6  131.37    4770   132.6    4880  132.12  4980.5  133.54
  4999.8  132.55  5072.5  132.72  5154.4  134.09  5225.3  133.01  5254.4  134.26
  5389.3  131.86  5485.3  132.52    5589  132.09  5641.8  133.94  5718.2  138.76
  5870.9  138.49  5986.9  141.35  6052.8  141.32  6405.7  149.58  6426.4  149.09
#Mann= 4 ,-1 , 0
  4213.7    .125       0  4269.6     .07       0  5154.4     .15       0
  5485.3     .17       0
#XS Ineff= 2 , 0
         4254.27  133.88 5154.73          134.09
Permanent Ineff=
       F       F
Bank Sta=4269.6,5154.4
XS Rating Curve= 0 ,0
Exp/Cntr=0.3,0.1

Type RM Length L Ch R = 1 ,13493   ,594,594,594
BEGIN DESCRIPTION:
SILVERDALE CREEK 27.0
END DESCRIPTION:
XS GIS Cut Line= 3
      3835297.39     10096185.13      3834419.76     10096768.47
      3833882.66      10098064.8
#Sta/Elev= 30
  4013.5  136.31  4038.1  132.62  4109.9  132.51  4231.4  132.63  4245.2   133.2
  4313.1     130    4429  131.39  4552.2  130.16  4558.2  131.36  4565.3  130.17
  4660.4  132.19  4774.7  132.17  4876.9  130.46  4955.1  131.46  4997.6  130.25
  5021.2  131.27    5139  130.83  5178.4  132.32  5216.1  132.54  5317.1  130.05
  5459.8  131.48  5628.9  128.67  5713.3  132.44  5737.2  135.32  5814.2  140.06
  5903.6  141.43  5997.7  139.27    6104  140.08  6210.4   141.8  6470.5  148.88
#Mann= 6 ,-1 , 0
  4013.5    .125       0  4109.9     .11       0  4231.4     .17       0
  4245.2     .15       0  4774.7     .06       0  5178.4     .17       0
#XS Ineff= 2 , 0
         4241.61  133.27
Permanent Ineff=
       F       F
Bank Sta=4774.7,5178.4
XS Rating Curve= 0 ,0
Exp/Cntr=0.3,0.1

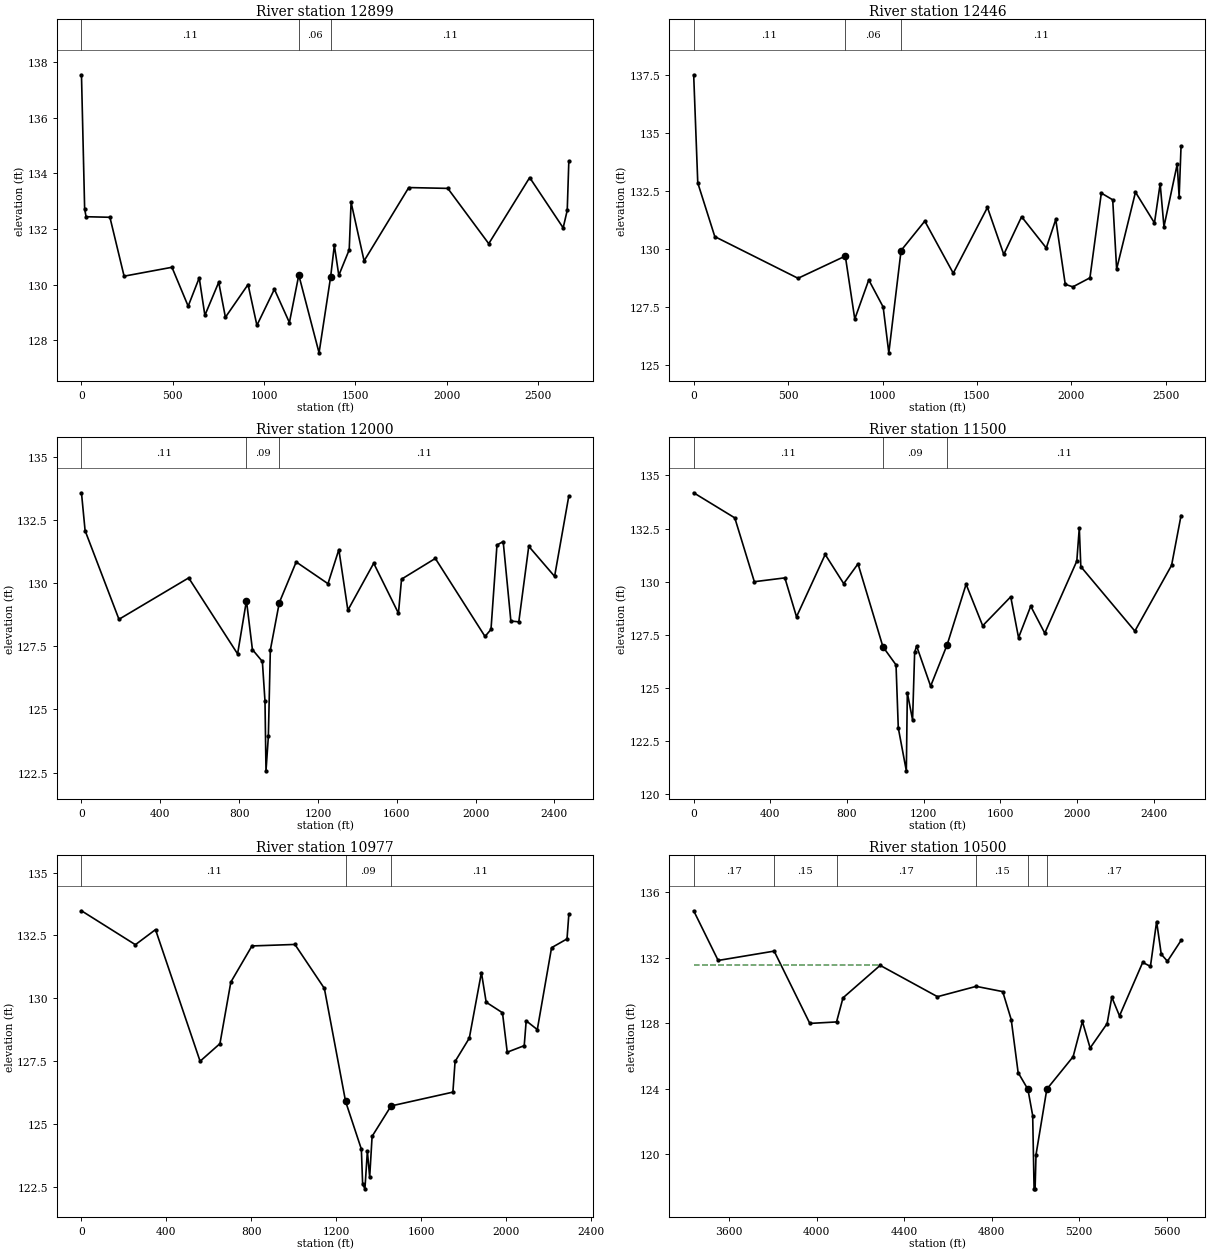
Type RM Length L Ch R = 1 ,12899   ,453,453,453
XS GIS Cut Line= 3
      3835294.76     10096169.51      3834034.35     10096474.64
       3832687.3      10096738.4
#Sta/Elev= 30
       0  137.55    17.4  132.72    25.2  132.44   155.8  132.42   233.5   130.3
   495.6  130.62   584.4  129.22     645  130.24   675.9  128.89   751.7  130.08
   788.4  128.82   912.5     130   960.9  128.53  1056.6  129.83  1138.9  128.63
  1190.3  130.34  1301.3  127.54  1364.6  130.27    1385  131.41  1409.4  130.33
  1466.5  131.25  1476.7  132.96    1548  130.85  1792.6  133.49  2006.5  133.46
  2230.7  131.47  2454.9  133.85  2638.3  132.04  2660.6  132.67  2669.4  134.45
#Mann= 3 , 0 , 0
       0     .11       0  1190.3     .06       0  1364.6     .11       0
Bank Sta=1190.3,1364.6
XS Rating Curve= 0 ,0
Exp/Cntr=0.3,0.1

Type RM Length L Ch R = 1 ,12446   ,447,447,447
XS GIS Cut Line= 3
      3835299.54     10096159.97      3834108.13     10096090.52
       3832727.8     10096231.05
#Sta/Elev= 30
       0  137.53    21.7  132.86   111.9  130.54   552.6  128.74     803   129.7
   853.1  126.98   927.2  128.67  1003.4   127.5  1033.4  125.52  1098.3  129.94
  1223.9  131.21  1374.6  128.96  1555.6   131.8  1642.1  129.77  1736.5   131.4
  1867.2  130.05  1917.4  131.28  1967.7  128.48  2007.9  128.37  2098.4  128.76
  2158.7  132.42    2219  132.13  2239.8  129.14  2339.6  132.46  2440.1  131.13
  2470.3  132.82  2490.4  130.97  2560.7  133.67  2570.8  132.25  2580.9  134.45
#Mann= 3 , 0 , 0
       0     .11       0     803     .06       0  1098.3     .11       0
Bank Sta=803,1098.3
XS Rating Curve= 0 ,0
Exp/Cntr=0.3,0.1

Type RM Length L Ch R = 1 ,12000   ,500,500,500
XS GIS Cut Line= 3
       3835316.1     10095629.96      3834386.48     10095767.56
      3832866.28     10095970.69
#Sta/Elev= 30
       0  133.58    18.4  132.08   190.3  128.57   544.1  130.21   792.4   127.2
   837.3  129.31   867.6  127.37   918.1   126.9   931.4  125.33   936.5  122.57
   948.5  123.93   958.5  127.35    1004  129.23  1089.7  130.84  1251.1  129.98
  1306.3  131.33    1352  128.93  1483.2  130.79  1608.7  128.81  1624.4  130.16
  1795.9  130.98  2048.1  127.89  2078.4  128.17  2108.7  131.51  2140.3  131.65
  2179.3   128.5  2219.6  128.47  2270.1  131.46  2401.2  130.27  2473.5  133.46
#Mann= 3 , 0 , 0
       0     .11       0   837.3     .09       0    1004     .11       0
Bank Sta=837.3,1004
XS Rating Curve= 0 ,0
Exp/Cntr=0.3,0.1

Type RM Length L Ch R = 1 ,11500   ,556,556,556
XS GIS Cut Line= 3
      3835342.94      10094892.6      3834353.37     10095360.58
      3832967.36     10095780.93
#Sta/Elev= 30
       0  134.18   214.5     133   316.5     130   475.8  130.18   536.6  128.35
   686.2  131.28   782.8  129.91   857.4  130.84   987.6  126.94  1055.8  126.09
  1067.6  123.13  1109.6  121.11  1114.8  124.78  1142.2   123.5    1153  126.68
  1163.1  126.98  1236.3  125.09  1322.7  127.04  1421.4  129.88    1508  127.93
  1654.3  129.29  1695.1  127.37  1758.7  128.85  1831.9  127.58  1999.1  130.97
  2012.1  132.53    2020  130.71  2302.1  127.68  2493.6  130.77    2543  133.11
#Mann= 3 , 0 , 0
       0     .11       0   987.6     .09       0  1322.7     .11       0
Bank Sta=987.6,1322.7
XS Rating Curve= 0 ,0
Exp/Cntr=0.3,0.1

Type RM Length L Ch R = 1 ,10977   ,445,445,445
XS GIS Cut Line= 3
      3835009.96     10094410.19      3833941.03     10095107.45
      3833027.97     10095561.31
#Sta/Elev= 30
       0  133.48     254  132.13   348.8  132.73   558.8  127.49   652.3  128.19
   703.6  130.64   803.1  132.08  1005.4  132.14  1144.2  130.39  1244.2  125.89
  1318.5  123.99  1324.5   122.6  1335.3  122.41  1346.8  123.91  1357.7  122.88
  1369.1   124.5  1458.5  125.71  1749.7  126.26    1760  127.48    1827  128.41
  1884.1  131.02  1906.5  129.84  1983.3  129.42  2005.7  127.85  2085.7  128.11
    2095   129.1  2147.3  128.75  2214.5  132.01  2287.3  132.36  2295.9  133.34
#Mann= 3 , 0 , 0
       0     .11       0  1244.2     .09       0  1458.5     .11       0
Bank Sta=1244.2,1458.5
XS Rating Curve= 0 ,0
Exp/Cntr=0.3,0.1

Type RM Length L Ch R = 1 ,10500   ,483,483,483
BEGIN DESCRIPTION:
SILVERDALE CREEK 21.0
END DESCRIPTION:
XS GIS Cut Line= 3
      3834940.55     10094375.45       3833506.7     10094995.57
       3833032.7     10095463.84
#Sta/Elev= 30
  3437.8  134.85  3549.7  131.82  3805.8  132.39  3968.8  127.98  4091.1  128.07
  4120.6  129.54  4290.5  131.52  4552.6  129.61  4729.6  130.24  4850.9  129.92
  4889.8  128.21  4921.4  124.98  4966.1  123.96  4987.9  122.36  4994.3  117.89
  4998.9  117.89  5003.1  119.97  5052.6  123.97  5172.8  125.95  5215.2   128.1
  5250.6  126.48  5328.3  127.97  5349.6  129.58  5384.9  128.44  5490.9   131.7
  5526.3  131.46  5554.6  134.19  5575.8   132.2  5604.1  131.77  5666.3  133.04
#Mann= 6 ,-1 , 0
  3437.8     .17       0  3805.8     .15       0  4091.1     .17       0
  4729.6     .15       0  4966.1     .09       0  5052.6     .17       0
#XS Ineff= 2 , 0
         4291.07  131.55
Permanent Ineff=
       F       F
Bank Sta=4966.1,5052.6
XS Rating Curve= 0 ,0
Exp/Cntr=0.3,0.1

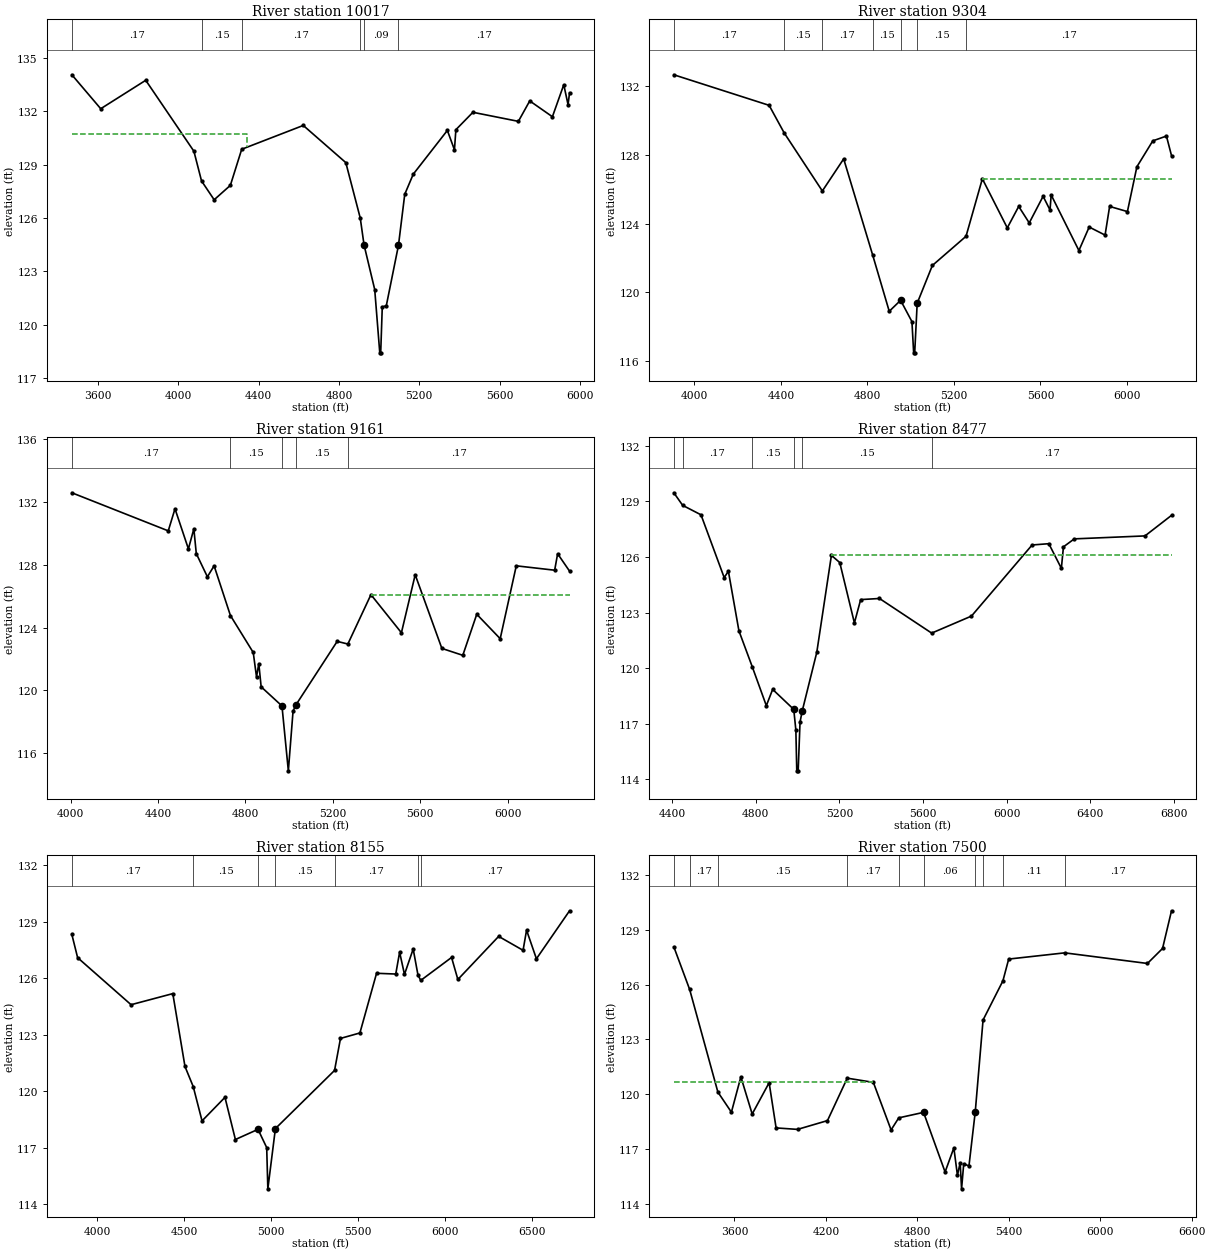
Type RM Length L Ch R = 1 ,10017   ,713,713,713
BEGIN DESCRIPTION:
SILVERDALE CREEK 20.0
END DESCRIPTION:
XS GIS Cut Line= 3
      3834940.39      10094328.1      3833310.17     10094544.24
      3832729.41     10095143.23
#Sta/Elev= 30
  3469.6  134.06  3613.4  132.15  3837.5  133.75  4077.4  129.76  4115.4  128.09
  4178.3  127.03    4259  127.84  4315.5  129.87  4622.1  131.21    4834  129.12
    4906     126  4924.8  124.49    4978  121.98  5003.2  118.42  5007.8  118.42
  5015.6     121  5035.7  121.07  5096.3  124.47  5127.6  127.34    5170  128.47
  5339.8  130.93  5375.1  129.84  5382.2  130.97  5467.1  131.95  5693.5  131.44
  5750.1  132.59    5863   131.7  5919.6   133.5  5940.9  132.38  5948.4  133.05
#Mann= 6 ,-1 , 0
  3469.6     .17       0  4115.4     .15       0  4315.5     .17       0
    4906     .15       0  4924.8     .09       0  5096.3     .17       0
#XS Ineff= 2 , 0
         4342.24  130.73
Permanent Ineff=
       F       F
Bank Sta=4924.8,5096.3
XS Rating Curve= 0 ,0
Exp/Cntr=0.3,0.1

Type RM Length L Ch R = 1 ,9304    ,143,143,143
BEGIN DESCRIPTION:
SILVERDALE CREEK 19.0
END DESCRIPTION:
XS GIS Cut Line= 3
      3834698.19     10094312.47      3833627.88     10093976.53
       3832505.5     10093614.56
#Sta/Elev= 30
  3904.8  132.67  4345.4  130.89  4415.2  129.28  4591.5   125.9  4690.1  127.77
  4823.9  122.18  4900.8  118.89  4953.3  119.53  5005.7  118.29  5013.7  116.47
  5018.5  116.47    5030  119.36  5100.2  121.56  5255.8  123.26  5331.3  126.61
  5446.6  123.75  5499.4     125  5548.1  124.04  5612.2  125.59  5644.2  124.79
  5649.5  125.67  5777.7  122.43  5825.2   123.8  5898.7  123.33  5919.7     125
    6002   124.7  6045.8  127.31  6119.4  128.82  6182.4   129.1  6205.9  127.96
#Mann= 7 ,-1 , 0
  3904.8     .17       0  4415.2     .15       0  4591.5     .17       0
  4823.9     .15       0  4953.3     .09       0    5030     .15       0
  5255.8     .17       0
#XS Ineff= 2 , 0
                         5330.66          126.61
Permanent Ineff=
       F       F
Bank Sta=4953.3,5030
XS Rating Curve= 0 ,0
Exp/Cntr=0.3,0.1

Type RM Length L Ch R = 1 ,9161    ,684,684,684
BEGIN DESCRIPTION:
SILVERDALE CREEK 18.0
END DESCRIPTION:
XS GIS Cut Line= 3
       3834703.4     10094236.95       3833825.8     10093921.85
      3832545.93     10093505.63
#Sta/Elev= 30
  4005.5   132.6  4446.8  130.17  4477.6  131.58    4539  129.02  4563.9   130.3
  4575.1  128.72  4625.9  127.24  4656.7  127.94  4731.3  124.77  4835.8  122.41
  4850.8  120.85  4861.2   121.7    4872  120.22  4967.3     119  4996.5  114.86
    5018  118.66  5030.4  119.05  5220.1  123.12  5268.9  122.95  5374.6   126.1
  5514.1  123.67  5577.2  127.37  5699.3  122.67  5795.1  122.23    5859  124.85
  5966.3  123.29  6039.9  127.94  6215.6  127.66  6229.2  128.71  6283.8   127.6
#Mann= 5 ,-1 , 0
  4005.5     .17       0  4731.3     .15       0  4967.3     .09       0
  5030.4     .15       0  5268.9     .17       0
#XS Ineff= 2 , 0
                         5372.94           126.1
Permanent Ineff=
       F       F
Bank Sta=4967.3,5030.4
XS Rating Curve= 0 ,0
Exp/Cntr=0.3,0.1

Type RM Length L Ch R = 1 ,8477    ,322,322,322
BEGIN DESCRIPTION:
SILVERDALE CREEK 17.0
END DESCRIPTION:
XS GIS Cut Line= 3
      3834606.76     10093203.36      3834017.38     10093279.75
      3832230.98     10093247.66
#Sta/Elev= 30
  4407.6  129.47    4450  128.79  4537.6  128.28  4648.5  124.89  4668.7  125.23
  4719.1  122.01  4782.9  120.07  4850.2  117.97  4880.4  118.85  4981.3  117.77
  4991.4  116.66  4995.8  114.45  5002.5  114.45  5011.4  117.08  5021.4  117.66
  5091.5  120.85  5161.5  126.09  5201.5   125.7  5271.5  122.44  5301.5   123.7
  5391.5  123.76  5641.2  121.89  5831.6  122.81  6121.6  126.65  6201.6  126.72
  6261.6  125.39  6271.6  126.55  6323.4  126.98  6661.7  127.14  6788.6  128.25
#Mann= 6 ,-1 , 0
  4407.6     .11       0    4450     .17       0  4782.9     .15       0
  4981.3     .09       0  5021.4     .15       0  5641.2     .17       0
#XS Ineff= 2 , 0
                         5161.46          126.13
Permanent Ineff=
       F       F
Bank Sta=4981.3,5021.4
XS Rating Curve= 0 ,0
Exp/Cntr=0.3,0.1

Type RM Length L Ch R = 1 ,8155    ,655,655,655
BEGIN DESCRIPTION:
SILVERDALE CREEK 16.0
END DESCRIPTION:
XS GIS Cut Line= 3
      3835038.38     10093087.35      3833902.18     10093040.08
      3832181.32      10093192.8
#Sta/Elev= 30
  3853.8  128.33  3886.9   127.1  4194.6   124.6  4434.8  125.19  4504.9  121.32
  4552.4  120.25  4603.1  118.43  4735.1  119.68  4795.1  117.44  4925.3  117.98
  4975.3  117.01  4981.9  114.82  5025.4  118.02  5365.9  121.11    5400  122.81
  5511.8   123.1  5607.7  126.27  5718.2  126.23  5740.4  127.39  5768.4  126.21
  5818.5  127.56  5845.8  126.19  5861.8  125.89  6039.4  127.11  6075.7  125.94
  6310.5  128.23    6451  127.49  6471.1  128.56  6527.9  127.04  6718.6  129.59
#Mann= 7 ,-1 , 0
  3853.8     .17       0  4552.4     .15       0  4925.3     .09       0
  5025.4     .15       0  5365.9     .17       0  5845.8     .11       0
  5861.8     .17       0
Bank Sta=4925.3,5025.4
XS Rating Curve= 0 ,0
Exp/Cntr=0.3,0.1

Type RM Length L Ch R = 1 ,7500    ,368,368,368
BEGIN DESCRIPTION:
SILVERDALE CREEK 15.0
END DESCRIPTION:
XS GIS Cut Line= 3
      3835243.44     10093034.74      3833504.07      10092582.1
      3832158.83     10093169.52
#Sta/Elev= 30
  3202.7  128.06  3306.5  125.73  3491.7  120.12  3580.5  119.02  3642.5  120.95
  3716.8  118.92    3828  120.63  3873.7  118.16  4014.4  118.08  4210.8  118.56
  4340.5  120.88  4511.7  120.65  4628.1  118.05  4678.4  118.71  4841.1  119.01
  4982.4  115.75  5039.9  117.07  5063.4  115.57  5081.3  116.26  5090.5  114.83
  5104.7   116.2    5139  116.08  5180.4  119.05  5231.5  124.06  5361.8   126.2
  5399.6  127.39  5767.3  127.73    6310  127.15  6409.1  127.97  6467.9  130.03
#Mann= 10 ,-1 , 0
  3202.7     .11       0  3306.5     .17       0  3491.7     .15       0
  4340.5     .17       0  4678.4     .15       0  4841.1     .06       0
  5180.4     .15       0  5231.5     .17       0  5361.8     .11       0
  5767.3     .17       0
#XS Ineff= 2 , 0
         4511.78  120.66
Permanent Ineff=
       F       F
Bank Sta=4841.1,5180.4
XS Rating Curve= 0 ,0
Exp/Cntr=0.3,0.1

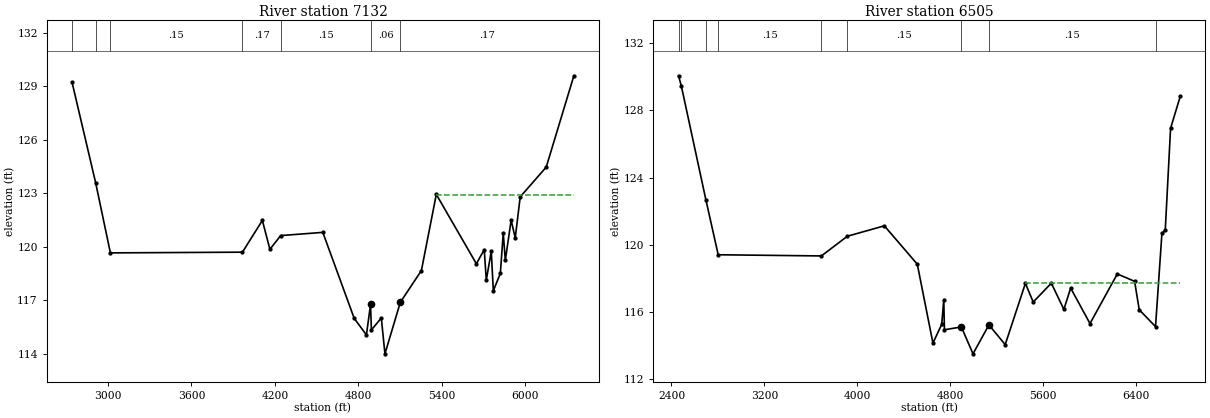
Type RM Length L Ch R = 1 ,7132    ,627,627,627
BEGIN DESCRIPTION:
SILVERDALE CREEK 14.0
END DESCRIPTION:
XS GIS Cut Line= 3
      3835302.01     10093030.82      3833416.19     10092253.93
      3832139.32     10093159.72
#Sta/Elev= 30
  2742.6  129.22  2912.9  123.56  3017.9  119.66  3966.5   119.7  4109.8  121.48
  4163.9  119.86  4241.4  120.63  4544.1  120.81  4769.6  115.99  4857.4  115.06
    4887  116.77  4893.1  115.34  4964.4  116.01  4990.4     114    5101  116.89
  5252.4  118.67  5359.4  122.94  5647.3  119.05  5703.9  119.84  5718.6  118.13
  5754.3  119.75  5769.1  117.54  5819.5  118.51  5840.4  120.77  5855.2  119.24
    5897  121.49  5926.5   120.5  5962.2   122.8  6149.2  124.47  6347.7  129.59
#Mann= 7 ,-1 , 0
  2742.6     .11       0  2912.9     .17       0  3017.9     .15       0
  3966.5     .17       0  4241.4     .15       0    4887     .06       0
    5101     .17       0
#XS Ineff= 2 , 0
                         5358.44          122.93
Permanent Ineff=
       F       F
Bank Sta=4887,5101
XS Rating Curve= 0 ,0
Exp/Cntr=0.3,0.1

Type RM Length L Ch R = 1 ,6505    ,505,505,505
BEGIN DESCRIPTION:
SILVERDALE CREEK 13.0
END DESCRIPTION:
XS GIS Cut Line= 3
      3835361.49     10093034.74      3832697.88     10091867.65
      3832108.05     10093152.77
#Sta/Elev= 30
    2461  130.05  2484.9  129.45  2696.8  122.67  2802.7  119.41  3691.8  119.34
  3914.6  120.51  4233.7  121.13  4517.5  118.85  4652.2  114.16  4727.8  115.27
  4745.7  116.73  4751.2  114.95  4896.9  115.12  4997.4  113.52 5134.24115.2388
  5274.8  114.07  5448.7  117.71  5515.9   116.6  5672.1  117.72    5780  116.16
  5838.6  117.43    6005  115.32  6240.4  118.27  6389.3  117.83  6429.1  116.14
  6569.5  115.14  6624.7  120.69  6653.2  120.86  6699.2  126.93  6783.1  128.84
#Mann= 9 ,-1 , 0
    2461    .125       0  2484.9     .11       0  2696.8     .17       0
  2802.7     .15       0  3691.8     .17       0  3914.6     .15       0
  4896.9     .06       0 5134.24     .15       0  6569.5     .17       0
#XS Ineff= 2 , 0
                          5449.2          117.72
Permanent Ineff=
       F       F
Bank Sta=4896.9,5134.24
XS Rating Curve= 0 ,0
Exp/Cntr=0.3,0.1