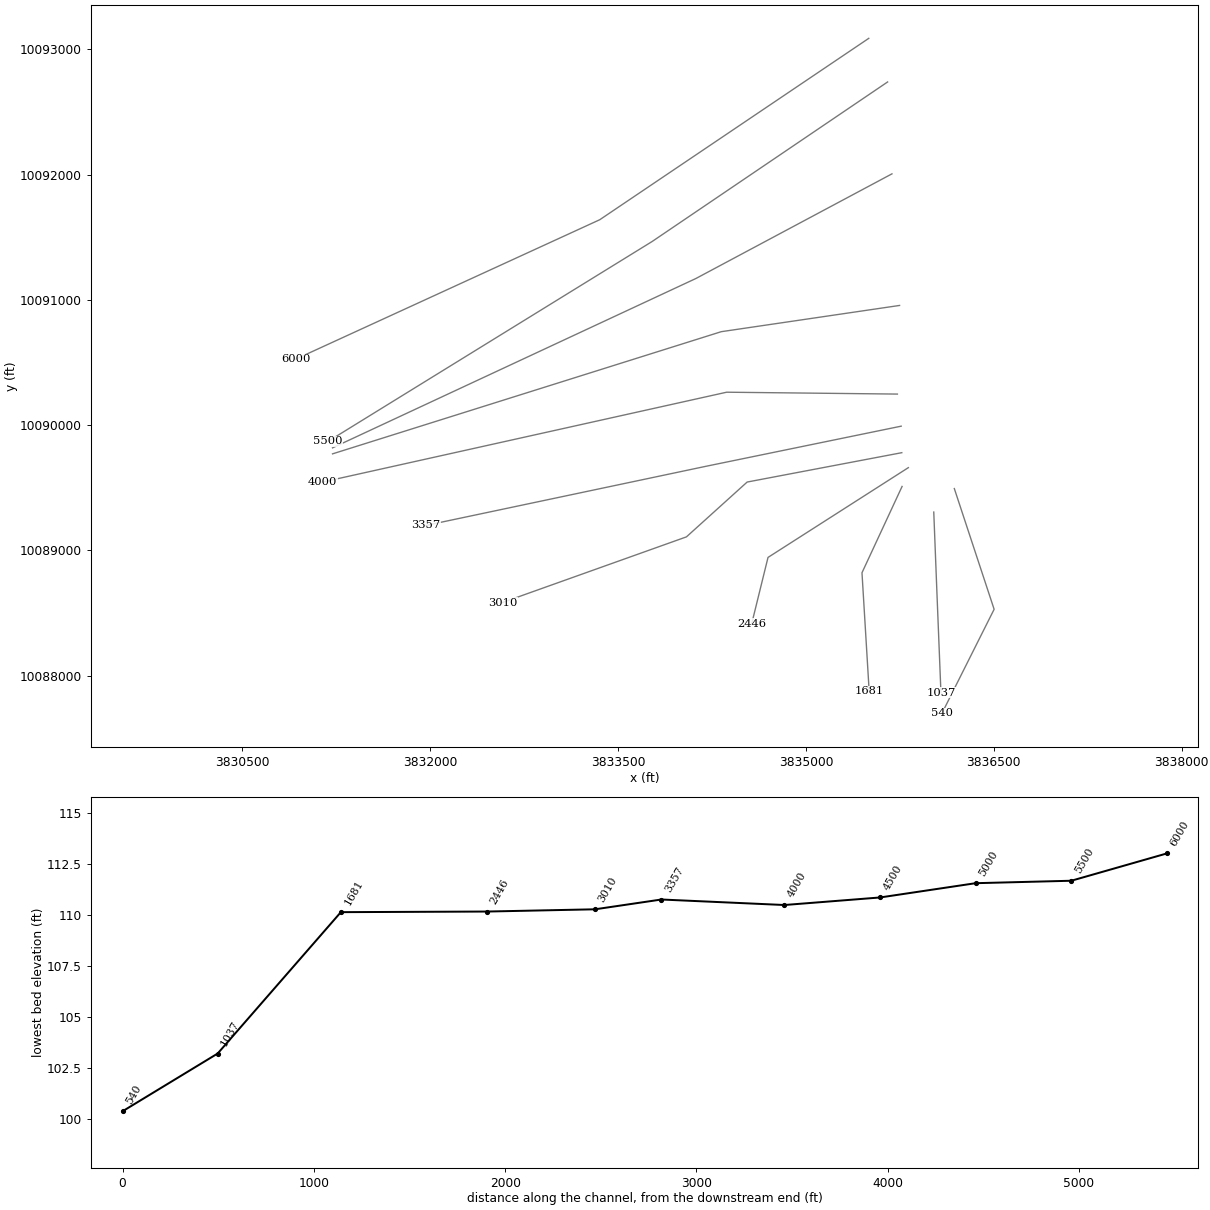
HEC-RAS study SILVERDALE CREEK.prj: SILVERDALE CREEK Base Level Engineering

--- SILVERDALE CREEK.g01 (geometry) --- (continued)

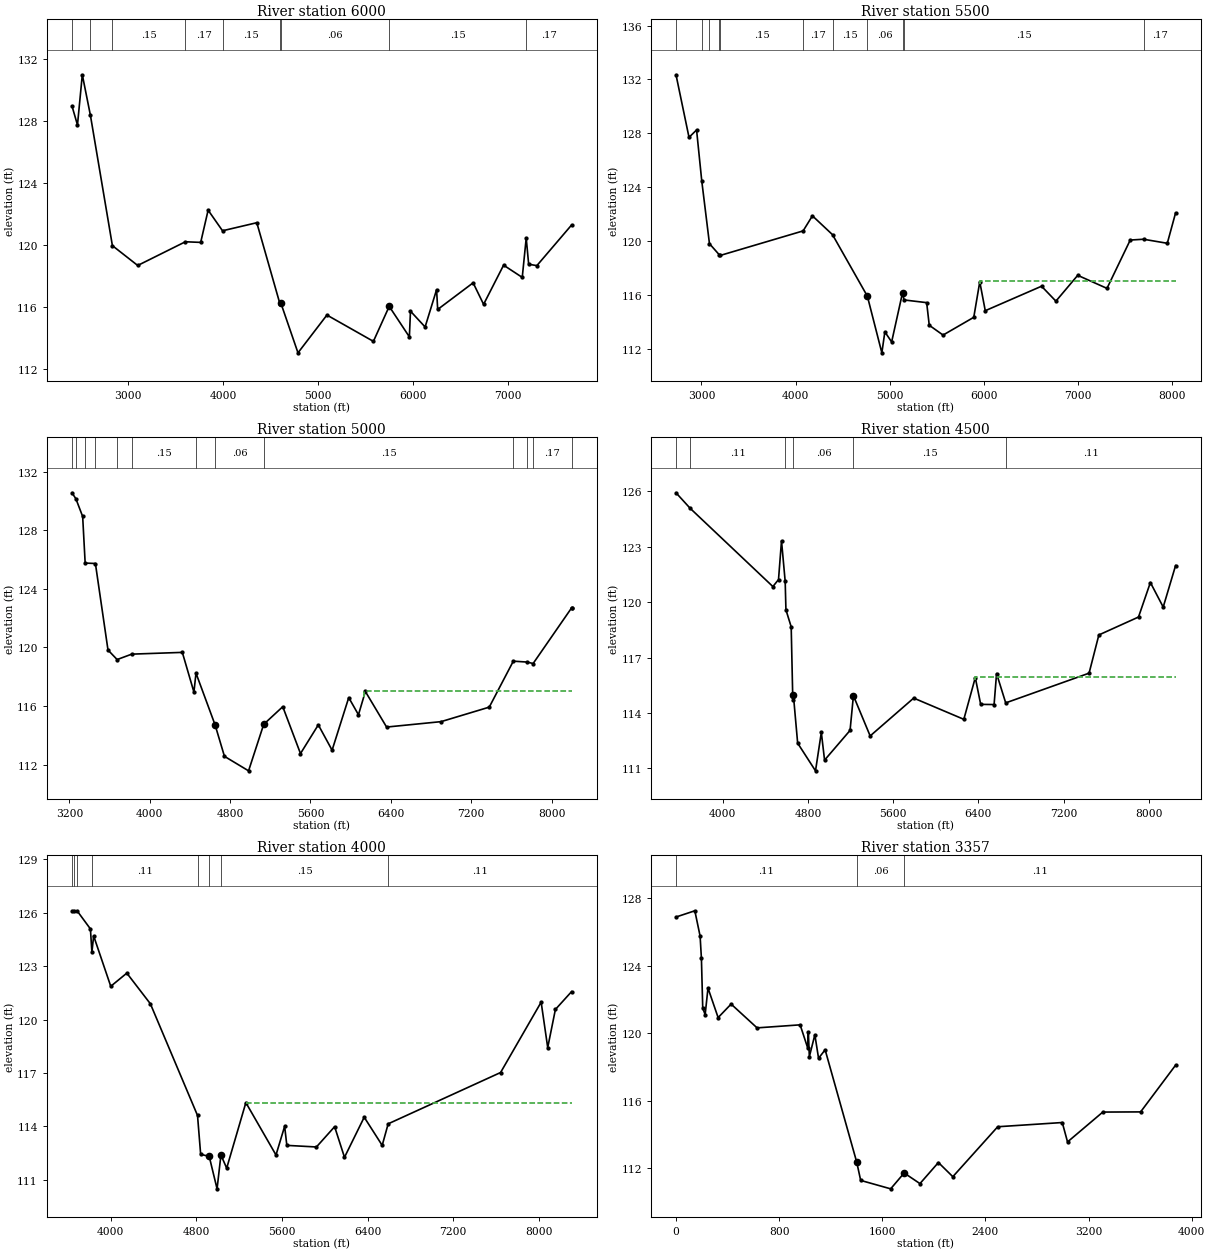
Type RM Length L Ch R = 1 ,6000    ,500,500,500
BEGIN DESCRIPTION:
SILVERDALE CREEK 12.0
END DESCRIPTION:
XS GIS Cut Line= 3
      3835502.11     10093087.77      3833354.95      10091640.1
      3830925.81      10090526.1
#Sta/Elev= 30
  2410.4  128.97  2468.5  127.74  2519.4  130.98  2604.3  128.38  2836.3  119.95
    3103  118.67    3605   120.2  3766.3  120.16  3844.6  122.24  3996.3  120.91
  4357.3  121.43  4600.2  116.21  4609.1  116.27    4791  113.03  5095.8  115.47
  5585.4  113.77  5751.9  116.03  5964.3  114.06  5975.9  115.72    6130   114.7
    6251  117.11  6262.3  115.83  6635.7  117.55    6746  116.16  6956.7  118.69
  7153.1   117.9  7194.9  120.44  7220.6  118.75  7307.1  118.66  7672.4  121.28
#Mann= 9 ,-1 , 0
  2410.4    .125       0  2604.3     .11       0  2836.3     .15       0
    3605     .17       0  3996.3     .15       0  4600.2     .08       0
  4609.1     .06       0  5751.9     .15       0  7194.9     .17       0
Bank Sta=4609.1,5751.9
XS Rating Curve= 0 ,0
Exp/Cntr=0.3,0.1

Type RM Length L Ch R = 1 ,5500    ,500,500,500
BEGIN DESCRIPTION:
SILVERDALE CREEK 11.0
END DESCRIPTION:
XS GIS Cut Line= 3
      3835652.39     10092739.64      3833773.14     10091466.33
      3831186.25     10089870.73
#Sta/Elev= 30
    2730  132.35  2868.3   127.7  2948.6  128.25  3003.4  124.48  3085.5   119.8
  3189.2  118.98  3201.6  118.93  4080.9  120.75  4179.7  121.87  4393.2  120.47
  4763.7   115.9  4917.7  111.69  4949.5  113.25  5021.7   112.5  5137.6  116.16
    5153  115.62  5393.9  115.42  5421.4  113.74  5568.1  113.01  5894.5  114.33
  5958.3  116.97  6016.6  114.82  6614.8  116.64  6767.4  115.53  6999.2  117.45
  7310.2  116.48  7557.3  120.07  7698.5  120.13  7951.2  119.83  8039.4  122.09
#Mann= 11 ,-1 , 0
    2730    .125       0  3003.4     .11       0  3085.5     .15       0
  3189.2     .11       0  3201.6     .15       0  4080.9     .17       0
  4393.2     .15       0  4763.7     .06       0  5137.6     .08       0
    5153     .15       0  7698.5     .17       0
#XS Ineff= 2 , 0
                         5963.62          117.05
Permanent Ineff=
       F       F
Bank Sta=4763.7,5137.6
XS Rating Curve= 0 ,0
Exp/Cntr=0.3,0.1

Type RM Length L Ch R = 1 ,5000    ,500,500,500
BEGIN DESCRIPTION:
SILVERDALE CREEK 10.0
END DESCRIPTION:
XS GIS Cut Line= 3
      3835687.16     10092006.17       3834121.8     10091170.63
      3831221.89     10089819.07
#Sta/Elev= 30
  3225.6  130.56  3264.8  130.15  3332.2  128.94    3357  125.76    3459  125.73
  3584.4  119.82  3675.3  119.17    3821  119.54  4324.4  119.66  4439.8  116.95
  4460.5  118.24  4650.6114.7069  4743.8  112.56  4983.9  111.57 5134.57114.7466
  5324.3  115.95  5500.8  112.75  5678.2  114.71  5815.5  112.98  5981.1  116.57
    6078   115.4  6146.6  116.99    6358  114.56  6900.5  114.93    7380  115.92
  7619.6  119.06  7755.2     119  7816.9   118.9  8199.1  122.69  8199.4   122.7
#Mann= 13 ,-1 , 0
  3225.6    .125       0  3264.8     .15       0    3357    .125       0
    3459     .11       0  3675.3     .17       0    3821     .15       0
  4460.5     .17       0  4650.6     .06       0 5134.57     .15       0
  7619.6     .17       0  7755.2     .15       0  7816.9     .17       0
  8199.1     .11       0
#XS Ineff= 2 , 0
                         6131.32          117.05
Permanent Ineff=
       F       F
Bank Sta=4650.6,5134.57
XS Rating Curve= 0 ,0
Exp/Cntr=0.3,0.1

Type RM Length L Ch R = 1 ,4500    ,500,500,500
BEGIN DESCRIPTION:
SILVERDALE CREEK 9.0
END DESCRIPTION:
XS GIS Cut Line= 3
      3835747.85     10090955.79      3834324.78     10090746.37
      3831221.91      10089771.2
#Sta/Elev= 30
  3561.6  125.93  3694.3  125.09  4471.3  120.85  4524.1  121.23  4552.2  123.33
  4586.7  121.13  4593.8  119.59  4643.1  118.67  4658.4  114.68  4663.5  114.99
  4703.8  112.37  4871.5  110.87  4926.1  112.95  4956.5  111.45  5195.9  113.06
  5227.4  114.94  5384.6  112.76  5793.4  114.81  6264.1  113.66  6371.8  115.92
  6422.4  114.47  6548.2  114.46  6571.5  116.14  6657.3  114.55  7440.1  116.16
    7532  118.23  7904.2   119.2  8015.7  121.07  8136.2  119.74  8252.5  121.99
#Mann= 6 ,-1 , 0
  3561.6    .125       0  3694.3     .11       0  4586.7     .17       0
  4663.5     .06       0  5227.4     .15       0  6657.3     .11       0
#XS Ineff= 2 , 0
                         6366.69          115.94
Permanent Ineff=
       F       F
Bank Sta=4663.5,5227.4
XS Rating Curve= 0 ,0
Exp/Cntr=0.3,0.1

Type RM Length L Ch R = 1 ,4000    ,643,643,643
BEGIN DESCRIPTION:
SILVERDALE CREEK 8.0
END DESCRIPTION:
XS GIS Cut Line= 3
      3835730.48     10090248.33      3834367.56     10090263.26
      3831140.49     10089545.65
#Sta/Elev= 30
    3637  126.08  3659.9  126.09  3684.8  126.11  3809.6  125.09  3823.4  123.78
  3839.6   124.7  3999.6  121.87  4149.7  122.61  4369.7  120.89  4810.4  114.62
  4839.7  112.44  4919.7  112.32  4993.1   110.5  5029.2   112.4    5083  111.66
  5262.2  115.34  5543.8   112.4  5624.6  114.01  5645.1  112.94  5921.7  112.85
  6091.7  113.99  6183.9  112.27  6368.2  114.52  6536.3  112.94  6592.2  114.15
  7642.7  117.03  8021.8  120.98  8083.2  118.43  8154.9  120.57  8305.9  121.57
#Mann= 8 ,-1 , 0
    3637    .125       0  3659.9     .15       0  3684.8    .125       0
  3823.4     .11       0  4810.4     .15       0  4919.7     .06       0
  5029.2     .15       0  6592.2     .11       0
#XS Ineff= 2 , 0
                         5264.92          115.34
Permanent Ineff=
       F       F
Bank Sta=4919.7,5029.2
XS Rating Curve= 0 ,0
Exp/Cntr=0.3,0.1

Type RM Length L Ch R = 1 ,3357    ,347,347,347
XS GIS Cut Line= 3
      3835760.91     10089992.26      3834198.41     10089671.08
      3831967.79     10089199.93
#Sta/Elev= 30
       0  126.88     146  127.25   186.9  125.75   197.1  124.43   207.3  121.49
     226  121.09   248.1  122.67   326.7  120.92   427.4  121.72   628.8  120.31
   962.8  120.49  1021.5  119.12  1026.6  120.05  1034.2   118.6  1076.9   119.9
  1105.7  118.51  1156.7  119.01  1401.8  112.35  1432.4  111.27    1665  110.77
  1769.6  111.71  1892.1  111.08  2035.2  112.33  2147.1  111.49  2495.3  114.45
    2996   114.7  3036.8  113.55  3310.4  115.32  3603.7  115.33    3875   118.1
#Mann= 3 , 0 , 0
       0     .11       0  1401.8     .06       0  1769.6     .11       0
Bank Sta=1401.8,1769.6
XS Rating Curve= 0 ,0
Exp/Cntr=0.3,0.1

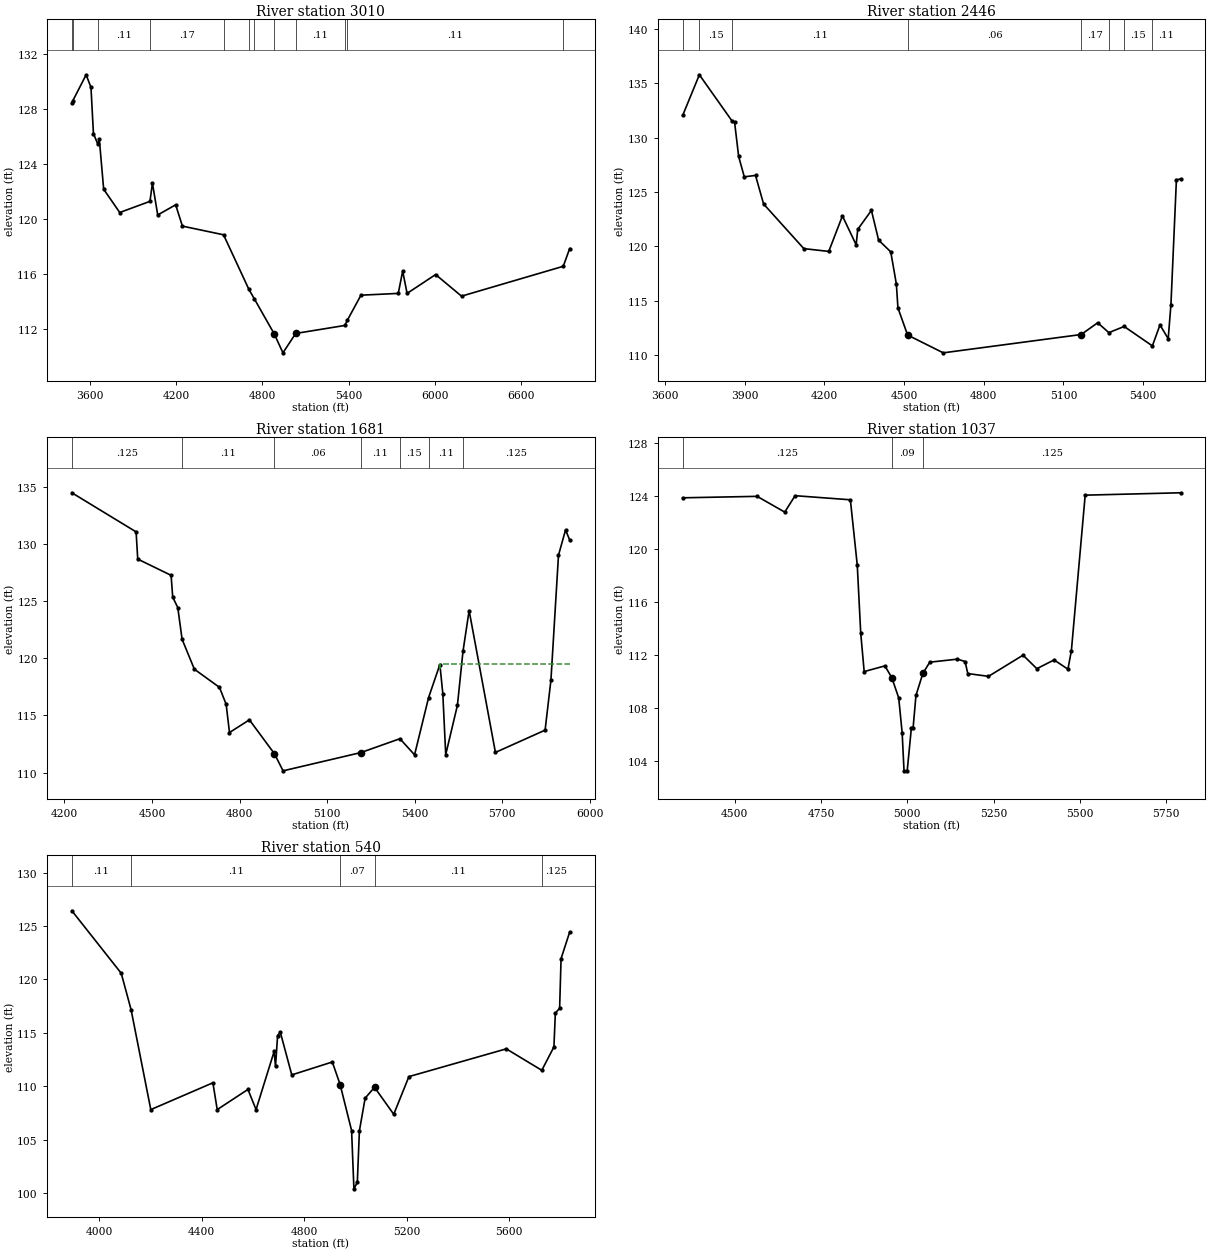
Type RM Length L Ch R = 1 ,3010    ,564,564,564
BEGIN DESCRIPTION:
SILVERDALE CREEK 6.0
END DESCRIPTION:
XS GIS Cut Line= 4
      3835765.55     10089780.53      3834531.16     10089546.15
      3834046.79     10089108.65      3832578.03     10088584.56
#Sta/Elev= 30
    3472  128.44  3478.4  128.61  3571.4   130.5  3605.1  129.58  3622.3  126.23
  3653.4  125.44    3663  125.84  3693.6  122.18  3805.5  120.49  4016.1   121.3
  4033.3  122.63  4070.2  120.31  4195.1  121.05  4242.3   119.5  4528.8  118.87
  4705.5   114.9  4743.6  114.21  4882.8  111.65  4942.6  110.29  5031.5   111.7
    5374  112.28    5392  112.67  5486.2  114.48  5746.1  114.61  5776.9  116.23
  5807.7  114.61  6006.4  115.98  6186.9  114.41  6895.8  116.58  6940.6  117.87
#Mann= 12 ,-1 , 0
    3472    .125       0  3478.4     .15       0  3653.4     .11       0
  4016.1     .17       0  4528.8     .11       0  4705.5     .17       0
  4743.6     .11       0  4882.8     .06       0  5031.5     .11       0
    5374     .15       0    5392     .11       0  6895.8     .15       0
Bank Sta=4882.8,5031.5
XS Rating Curve= 0 ,0
Exp/Cntr=0.3,0.1

Type RM Length L Ch R = 1 ,2446    ,765,765,765
BEGIN DESCRIPTION:
SILVERDALE CREEK 5.0
END DESCRIPTION:
XS GIS Cut Line= 3
      3835817.89      10089661.1      3834697.83     10088944.59
      3834567.64     10088416.02
#Sta/Elev= 30
  3666.9  132.05  3729.6  135.79  3852.2  131.55  3862.3   131.4  3877.5  128.27
  3898.7  126.39    3941  126.52  3971.4  123.89  4122.8  119.78  4216.7  119.52
  4268.2  122.79  4319.8  120.13  4325.8  121.55  4377.3   123.3  4404.4  120.56
  4450.1  119.48  4471.2  116.52  4477.1  114.32  4513.5  111.82  4647.7  110.18
 5167.06111.8685  5229.1  112.95  5271.2  112.04  5328.7  112.61  5434.9  110.82
  5463.6  112.75  5494.5  111.48  5504.8  114.62  5525.4  126.11  5540.9   126.2
#Mann= 8 ,-1 , 0
  3666.9    .125       0  3729.6     .15       0  3852.2     .11       0
  4513.5     .06       0 5167.06     .17       0  5271.2     .11       0
  5328.7     .15       0  5434.9     .11       0
Bank Sta=4513.5,5167.06
XS Rating Curve= 0 ,0
Exp/Cntr=0.3,0.1

Type RM Length L Ch R = 1 ,1681    ,644,644,644
BEGIN DESCRIPTION:
SILVERDALE CREEK 4.0
END DESCRIPTION:
XS GIS Cut Line= 3
      3835767.85     10089511.06      3835447.83     10088822.19
      3835505.12      10087876.9
#Sta/Elev= 30
  4225.3  134.47  4445.5  131.05  4451.1  128.67  4565.5  127.25    4571  125.34
  4588.4  124.43  4603.1  121.66  4645.2  119.04  4731.3  117.45  4754.2  115.97
  4765.6   113.5  4833.9  114.61  4919.9  111.64  4949.3  110.15  5216.4  111.75
  5349.9  112.96  5400.1  111.55  5448.2  116.56  5486.9  119.45  5496.9  116.91
  5506.9  111.57    5547  115.88  5566.1   120.6  5587.1  124.17  5677.3  111.76
  5847.6  113.71  5867.6  118.09  5893.5  129.01  5917.7  131.22  5931.9  130.34
#Mann= 7 ,-1 , 0
  4225.3    .125       0  4603.1     .11       0  4919.9     .06       0
  5216.4     .11       0  5349.9     .15       0  5448.2     .11       0
  5566.1    .125       0
#XS Ineff= 2 , 0
                         5488.35          119.46
Permanent Ineff=
       F       F
Bank Sta=4919.9,5216.4
XS Rating Curve= 0 ,0
Exp/Cntr=0.3,0.1

Type RM Length L Ch R = 1 ,1037    ,497,497,497
BEGIN DESCRIPTION:
SILVERDALE CREEK 2.0
END DESCRIPTION:
XS GIS Cut Line= 3
      3836020.75     10089306.56      3836046.79      10088642.5
      3836077.99     10087864.99
#Sta/Elev= 30
  4348.9  123.85  4564.6  123.96  4644.6  122.77  4674.6  124.01  4834.8   123.7
  4854.8  118.76  4864.8  113.63  4874.8  110.72  4934.8  111.15  4954.9  110.26
  4974.9  108.73  4984.9  106.09  4990.3  103.22  4999.5  103.22  5011.7  106.49
  5016.7  106.49  5024.9  108.92  5044.9  110.58  5064.9  111.43    5145  111.66
  5167.3  111.48    5175  110.57  5235.1  110.36  5335.2  111.96  5375.2  110.94
  5425.2   111.6  5465.3   110.9  5475.3   112.3  5515.3  124.05  5791.6  124.23
#Mann= 3 , 0 , 0
  4348.9    .125       0  4954.9     .09       0  5044.9    .125       0
Bank Sta=4954.9,5044.9
XS Rating Curve= 0 ,0
Exp/Cntr=0.3,0.1

Type RM Length L Ch R = 1 ,540     ,0,0,0
BEGIN DESCRIPTION:
SILVERDALE CREEK 1.0
END DESCRIPTION:
XS GIS Cut Line= 3
       3836184.8      10089494.1      3836502.52     10088530.52
      3836085.84     10087699.77
#Sta/Elev= 30
  3892.8  126.43  4085.5  120.58    4124  117.17    4201  107.81  4443.5  110.32
  4460.4  107.81  4580.4   109.7    4612  107.81  4682.7  113.26    4688  111.85
  4696.2  114.75  4706.8  115.06  4751.5  111.06  4909.9  112.27  4940.4  110.15
  4985.1  105.85  4994.2  100.39  5007.5     101  5015.6  105.82    5038  108.88
  5074.6   109.9  5149.7  107.37  5208.9   110.9  5589.2   113.5  5727.8  111.49
  5775.2  113.68  5780.8  116.84  5797.5  117.31  5803.1  121.95  5836.8  124.44
#Mann= 5 ,-1 , 0
  3892.8     .11       0    4124     .11       0  4940.4     .07       0
  5074.6     .11       0  5727.8    .125       0
Bank Sta=4940.4,5074.6
XS Rating Curve= 0 ,0
Exp/Cntr=0.3,0.1

Chan Stop Cuts=-1
Use User Specified Reach Order=0
Composite Channel Slope=5

--- SILVERDALE CREEK.g10 (geometry) ---

Geom Title=Existing Conditions
Program Version=4.10

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
River Reach=SILVERDALE CREEK,Reach-1

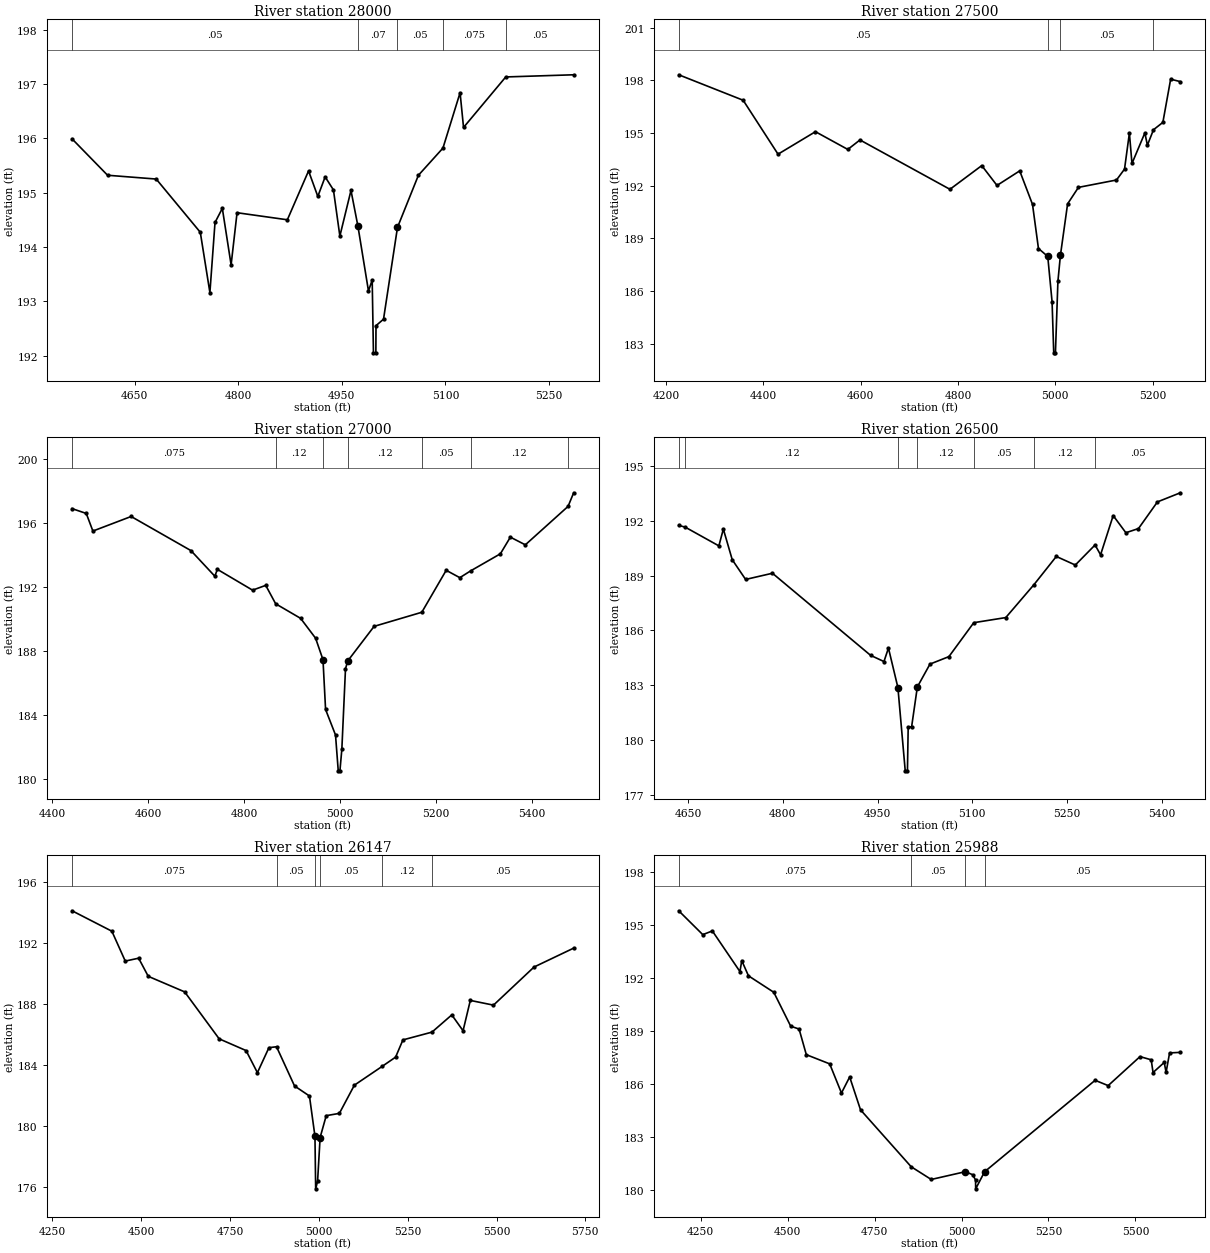
Type RM Length L Ch R = 1 ,28000   ,500,500,500
BEGIN DESCRIPTION:
SILVERDALE CREEK 56.0
END DESCRIPTION:
XS GIS Cut Line= 3
      3836502.48     10107903.02      3836088.18     10107753.66
      3835805.38     10107713.77
#Sta/Elev= 30
  4559.6  195.99    4611  195.32  4681.4  195.25  4745.2  194.27  4759.1  193.16
  4766.5  194.45  4777.1  194.71  4789.8  193.67  4798.4  194.63  4871.2   194.5
  4901.9   195.4  4915.3  194.93  4925.9  195.29  4937.9  195.05  4947.2   194.2
  4963.3  195.04 4973.34 194.383  4988.6  193.19    4994  193.39  4995.8  192.05
  4999.3  192.05  4999.5  192.55  5010.4  192.67  5030.6  194.36  5060.9  195.32
  5096.4  195.82  5121.2  196.84  5126.2   196.2  5187.3  197.13  5285.6  197.17
#Mann= 5 ,-1 , 0
  4559.6     .05       0 4973.34     .07       0  5030.6     .05       0
  5096.4    .075       0  5187.3     .05       0
Bank Sta=4973.34,5030.6
XS Rating Curve= 0 ,0
Exp/Cntr=0.3,0.1

Type RM Length L Ch R = 1 ,27500   ,500,500,500
BEGIN DESCRIPTION:
SILVERDALE CREEK 55.0
END DESCRIPTION:
XS GIS Cut Line= 3
      3837005.04     10107505.09      3836263.02     10107285.24
      3836018.95     10107204.75
#Sta/Elev= 30
  4226.1  198.31  4358.5  196.86  4430.2  193.79  4507.1  195.07  4573.6  194.06
  4598.6   194.6  4783.5  191.79  4848.9  193.14  4880.2  192.01  4926.9  192.84
  4953.2  190.93  4965.4  188.42  4984.5  187.97  4993.4  185.39  4996.8  182.48
  5000.3  182.48  5005.4  186.55  5010.5 188.022  5025.3  190.96  5047.6   191.9
  5125.8  192.32  5142.3  192.94  5152.3  194.99  5157.6  193.26  5184.1     195
  5189.3   194.3  5201.8  195.18  5221.1   195.6  5237.1  198.06    5257  197.92
#Mann= 4 ,-1 , 0
  4226.1     .05       0  4984.5     .07       0  5010.5     .05       0
  5201.8    .075       0
Bank Sta=4984.5,5010.5
XS Rating Curve= 0 ,0
Exp/Cntr=0.3,0.1

Type RM Length L Ch R = 1 ,27000   ,500,500,500
BEGIN DESCRIPTION:
SILVERDALE CREEK 54.0
END DESCRIPTION:
XS GIS Cut Line= 3
      3836996.36     10106977.31      3836458.54     10106826.36
      3835991.15     10106691.35
#Sta/Elev= 30
  4441.4   196.9    4471   196.6  4484.8   195.5  4564.5  196.41  4689.1  194.28
  4738.9  192.68  4744.1  193.11  4817.5  191.81  4844.9  192.11  4865.6  190.96
  4917.6  190.05  4948.8  188.81  4964.2  187.47  4969.6  184.36  4990.3  182.77
    4996  180.53  4999.5  180.53  5003.5  181.88  5011.1   186.9 5015.72 187.389
  5070.7  189.55  5170.1  190.43  5220.9  193.05  5249.3  192.59  5271.6  193.01
  5333.8  194.08  5354.6  195.12  5385.8  194.64  5474.8  197.04  5486.5  197.89
#Mann= 7 ,-1 , 0
  4441.4    .075       0  4865.6     .12       0  4964.2     .07       0
 5015.72     .12       0  5170.1     .05       0  5271.6     .12       0
  5474.8     .05       0
Bank Sta=4964.2,5015.72
XS Rating Curve= 0 ,0
Exp/Cntr=0.3,0.1

Type RM Length L Ch R = 1 ,26500   ,353,353,353
BEGIN DESCRIPTION:
SILVERDALE CREEK 53.0
END DESCRIPTION:
XS GIS Cut Line= 3
      3836867.83     10106611.05       3836610.9      10106351.8
      3836181.62     10106373.08
#Sta/Elev= 30
    4635  191.75  4645.1  191.66  4698.6  190.63  4705.7  191.55  4719.8  189.87
    4741  188.79  4783.5  189.13    4939  184.63  4960.2  184.29  4967.3  185.03
 4982.28 182.866  4993.9   178.3  4997.4   178.3  4998.6  180.71    5004  180.71
  5013.1   182.9  5033.1  184.15  5063.1  184.56  5102.5  186.42  5153.2   186.7
    5198  188.51  5233.3  190.05  5263.4  189.58  5294.7  190.68  5303.4  190.14
  5323.4  192.29  5343.5  191.35  5363.5  191.58  5393.5  193.04  5429.8  193.54
#Mann= 7 ,-1 , 0
    4635    .075       0  4645.1     .12       0 4982.28     .07       0
  5013.1     .12       0  5102.5     .05       0    5198     .12       0
  5294.7     .05       0
Bank Sta=4982.28,5013.1
XS Rating Curve= 0 ,0
Exp/Cntr=0.3,0.1

Type RM Length L Ch R = 1 ,26147   ,159,159,159
BEGIN DESCRIPTION:
SILVERDALE CREEK 52.0
END DESCRIPTION:
XS GIS Cut Line= 4
      3837354.89     10106221.24      3836696.01     10106013.77
      3836244.58     10105862.85      3836041.34     10105998.83
#Sta/Elev= 30
  4305.8  194.09  4417.8  192.75  4455.5  190.79  4493.1  190.98  4520.2  189.79
  4622.6  188.77  4719.7  185.69  4795.4  184.92  4827.3  183.47  4859.7  185.11
  4881.1  185.17  4931.7   182.6  4973.7  181.94  4989.2   179.3  4991.2  175.85
  4996.6  176.35  5003.7 179.215  5020.9  180.65  5057.9   180.8  5100.1  182.65
  5178.1  183.88  5216.1  184.49  5236.7  185.62  5318.4  186.13  5374.2  187.26
  5405.9  186.22  5426.3  188.21  5491.5   187.9  5605.6   190.4  5717.1  191.64
#Mann= 6 ,-1 , 0
  4305.8    .075       0  4881.1     .05       0  4989.2     .07       0
  5003.7     .05       0  5178.1     .12       0  5318.4     .05       0
Bank Sta=4989.2,5003.7
XS Rating Curve= 0 ,0
Exp/Cntr=0.3,0.1

Type RM Length L Ch R = 1 ,25988   ,982,982,982
BEGIN DESCRIPTION:
SILVERDALE CREEK 51.0
END DESCRIPTION:
XS GIS Cut Line= 3
      3837430.87     10106084.53      3836643.06     10105860.99
      3836048.42     10105672.18
#Sta/Elev= 30
  4186.5  195.82  4255.7  194.47  4283.2  194.68  4362.6  192.38  4367.8     193
  4387.1  192.14  4459.9  191.21  4508.6  189.29  4532.7  189.13  4553.5  187.68
  4620.7  187.16  4654.6  185.51  4678.2  186.42  4709.4  184.56  4855.1  181.34
  4912.8  180.62  5010.9  181.06  5031.9  180.89  5040.3  180.59  5040.6  180.09
 5066.29 181.057  5384.2  186.23  5421.7  185.93  5513.3  187.57  5545.5  187.39
  5550.8  186.67    5583  187.24  5588.3  186.68  5598.4  187.78  5629.3  187.81
#Mann= 4 ,-1 , 0
  4186.5    .075       0  4855.1     .05       0  5010.9     .03       0
 5066.29     .05       0
Bank Sta=5010.9,5066.29
XS Rating Curve= 0 ,0
Exp/Cntr=0.3,0.1

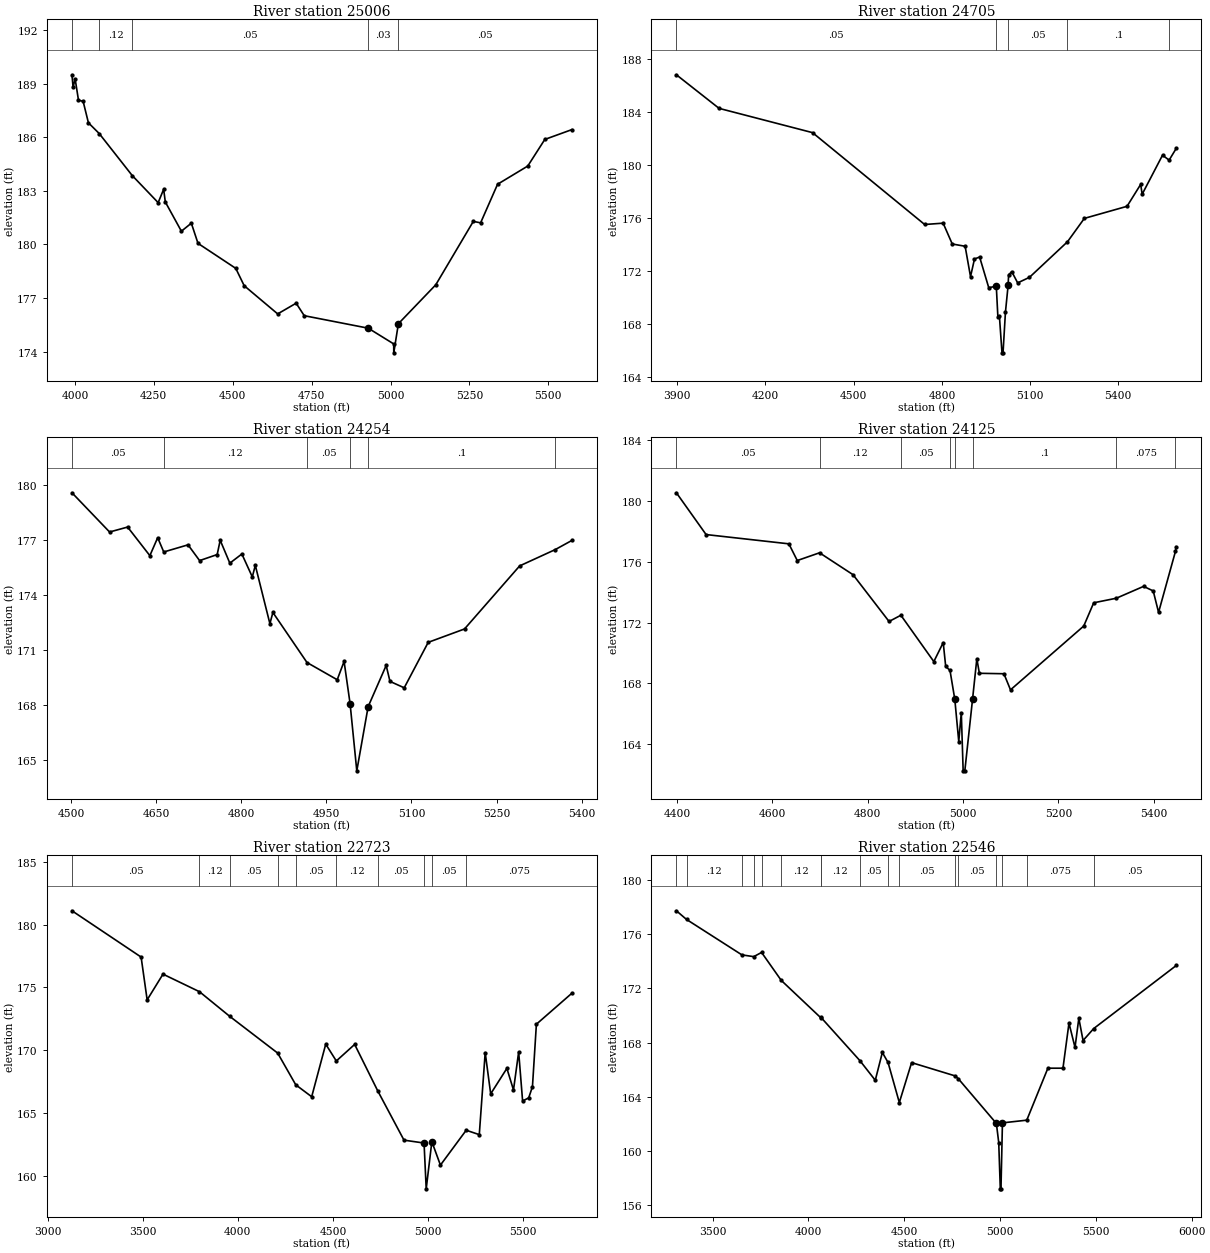
Type RM Length L Ch R = 1 ,25006   ,301,301,301
BEGIN DESCRIPTION:
SILVERDALE CREEK 50.0
END DESCRIPTION:
XS GIS Cut Line= 3
      3837117.42     10105336.73      3836192.11     10105034.65
      3835962.93     10105600.64
#Sta/Elev= 30
  3990.7   189.5  3994.2  188.81  4000.8  189.26  4011.3  188.08  4026.1  188.01
  4042.8  186.81    4077  186.21  4181.5  183.86  4263.8  182.34  4281.2  183.09
  4286.4  182.38  4337.4  180.74  4368.9  181.19    4390  180.06  4509.7  178.66
  4536.3  177.69  4642.5  176.11    4701  176.71  4726.6  176.01  4929.5  175.31
  5010.1  174.43  5010.3  173.93  5024.9  175.56  5143.4  177.74  5262.3  181.29
  5285.5  181.21  5339.2  183.37  5434.9  184.39  5488.9  185.88  5574.7  186.43
#Mann= 5 ,-1 , 0
  3990.7     .05       0    4077     .12       0  4181.5     .05       0
  4929.5     .03       0  5024.9     .05       0
Bank Sta=4929.5,5024.9
XS Rating Curve= 0 ,0
Exp/Cntr=0.3,0.1

Type RM Length L Ch R = 1 ,24705   ,451,451,451
BEGIN DESCRIPTION:
SILVERDALE CREEK 49.0
END DESCRIPTION:
XS GIS Cut Line= 3
      3837094.89     10105187.43       3836023.7     10104812.43
       3835461.2     10104753.59
#Sta/Elev= 30
  3896.9  186.79  4042.1  184.26  4360.1  182.43  4741.4  175.51  4804.3  175.61
  4835.3  174.04  4879.1  173.87  4897.4  171.58  4910.9  172.91  4928.4  173.06
  4959.4  170.75  4985.1  170.86  4990.5  168.54  4995.7   168.6  5004.5  165.84
    5008  165.84  5016.2   168.9 5025.26 170.916    5027  171.72  5037.7  171.96
  5057.8  171.11    5098  171.53  5227.3  174.21  5284.6  175.97  5429.8  176.88
  5476.2  178.53  5481.3  177.79  5550.5  180.73    5573  180.36  5597.4  181.25
#Mann= 5 ,-1 , 0
  3896.9     .05       0  4985.1     .07       0 5025.26     .05       0
  5227.3      .1       0    5573    .075       0
Bank Sta=4985.1,5025.26
XS Rating Curve= 0 ,0
Exp/Cntr=0.3,0.1

Type RM Length L Ch R = 1 ,24254   ,129,129,129
BEGIN DESCRIPTION:
SILVERDALE CREEK 48.0
END DESCRIPTION:
XS GIS Cut Line= 3
      3836380.42     10104582.26      3835770.23     10104367.99
      3835535.88     10104357.57
#Sta/Elev= 30
  4501.5  179.59  4567.8  177.45  4599.6  177.72  4638.8  176.16  4652.6  177.14
  4663.3  176.36  4706.1  176.75  4726.5  175.89  4757.5  176.22  4762.8     177
  4779.8  175.75    4801  176.25  4819.4     175  4824.7  175.63  4850.4  172.45
  4855.7  173.06  4915.8  170.33  4969.1  169.39  4981.2  170.39  4991.8  168.08
  5003.6  164.42  5023.6  167.92  5055.4  170.17  5062.1   169.3  5087.2  168.95
  5129.5  171.43  5193.5  172.16  5290.7   175.6  5353.4  176.49  5382.8  176.99
#Mann= 6 ,-1 , 0
  4501.5     .05       0  4663.3     .12       0  4915.8     .05       0
  4991.8     .07       0  5023.6      .1       0  5353.4    .075       0
Bank Sta=4991.8,5023.6
XS Rating Curve= 0 ,0
Exp/Cntr=0.3,0.1

Type RM Length L Ch R = 1 ,24125   ,1402,1402,1402
BEGIN DESCRIPTION:
SILVERDALE CREEK 47.0
END DESCRIPTION:
XS GIS Cut Line= 3
      3836436.55     10104505.01      3835923.56     10104321.43
      3835442.33     10104173.16
#Sta/Elev= 30
  4398.7  180.54    4461  177.79  4634.6  177.18  4652.2  176.08  4698.9  176.59
  4769.1  175.15  4844.7  172.07  4869.5  172.48  4938.6  169.43  4958.3  170.68
  4963.5  169.11  4972.5  168.85 4982.57 166.952  4990.9  164.17  4996.2  166.07
  5000.1  162.24  5003.6  162.24 5019.75 166.937  5028.8  169.62  5034.1  168.66
  5085.6  168.63  5099.4  167.57    5253  171.77  5273.9   173.3  5321.3   173.6
  5378.5  174.38  5398.7  174.08  5409.9  172.67  5445.3  176.68  5447.1  176.99
#Mann= 8 ,-1 , 0
  4398.7     .05       0  4698.9     .12       0  4869.5     .05       0
  4972.5      .1       0 4982.57     .07       0 5019.75      .1       0
  5321.3    .075       0  5445.3      .1       0
Bank Sta=4982.57,5019.75
XS Rating Curve= 0 ,0
Exp/Cntr=0.3,0.1

Type RM Length L Ch R = 1 ,22723   ,177,177,177
BEGIN DESCRIPTION:
SILVERDALE CREEK 46.0
END DESCRIPTION:
XS GIS Cut Line= 3
      3837552.44     10103620.18      3835773.82     10103021.23
      3835047.56       10102826.
#Sta/Elev= 30
  3127.8  181.11  3491.4  177.42  3523.1  174.01  3606.4  176.06  3798.3  174.66
  3957.1   172.7  4209.4  169.77  4304.6  167.24  4388.3  166.29  4462.2  170.48
  4517.8  169.14  4614.3  170.46  4735.9  166.75  4873.7  162.83  4979.2   162.6
  4990.5  158.95  5020.2  162.71  5065.3  160.84  5200.8  163.62  5269.6  163.27
  5300.7  169.81  5329.6  166.52  5414.7  168.55  5449.5  166.83  5476.7  169.86
  5497.4  165.95  5529.4   166.2  5549.2  167.09  5569.9  172.07  5756.6  174.54
#Mann= 10 ,-1 , 0
  3127.8     .05       0  3798.3     .12       0  3957.1     .05       0
  4209.4     .12       0  4304.6     .05       0  4517.8     .12       0
  4735.9     .05       0  4979.2     .07       0  5020.2     .05       0
  5200.8    .075       0
Bank Sta=4979.2,5020.2
XS Rating Curve= 0 ,0
Exp/Cntr=0.3,0.1

Type RM Length L Ch R = 1 ,22546   ,468,468,468
BEGIN DESCRIPTION:
SILVERDALE CREEK 45.0
END DESCRIPTION:
XS GIS Cut Line= 3
       3837443.1     10103396.23      3835851.95     10102864.98
      3834963.92     10102583.73
#Sta/Elev= 30
    3311  177.71  3364.1  177.07  3652.9  174.46  3714.7  174.33  3755.6  174.64
  3858.3  172.58  4063.7  169.84  4065.2  169.86  4269.1  166.66    4349  165.22
  4385.9  167.27  4415.7  166.53  4474.5  163.58  4538.6  166.52  4766.3  165.54
  4782.6  165.33    4981  162.04  4993.3  160.63  5001.5  157.22    5005  157.22
 5012.63 162.081  5139.6  162.28  5249.8  166.11  5328.5  166.11  5359.9  169.43
  5391.4  167.64  5411.3  169.79  5433.4  168.15  5488.9  169.03    5920  173.68
#Mann= 17 ,-1 , 0
    3311     .05       0  3364.1     .12       0  3652.9     .05       0
  3714.7     .12       0  3755.6     .05       0  3858.3     .12       0
  4063.7     .05       0  4065.2     .12       0  4269.1     .05       0
  4415.7     .12       0  4474.5     .05       0  4766.3     .12       0
  4782.6     .05       0    4981     .07       0 5012.63     .05       0
  5139.6    .075       0  5488.9     .05       0
Bank Sta=4981,5012.63
XS Rating Curve= 0 ,0
Exp/Cntr=0.3,0.1

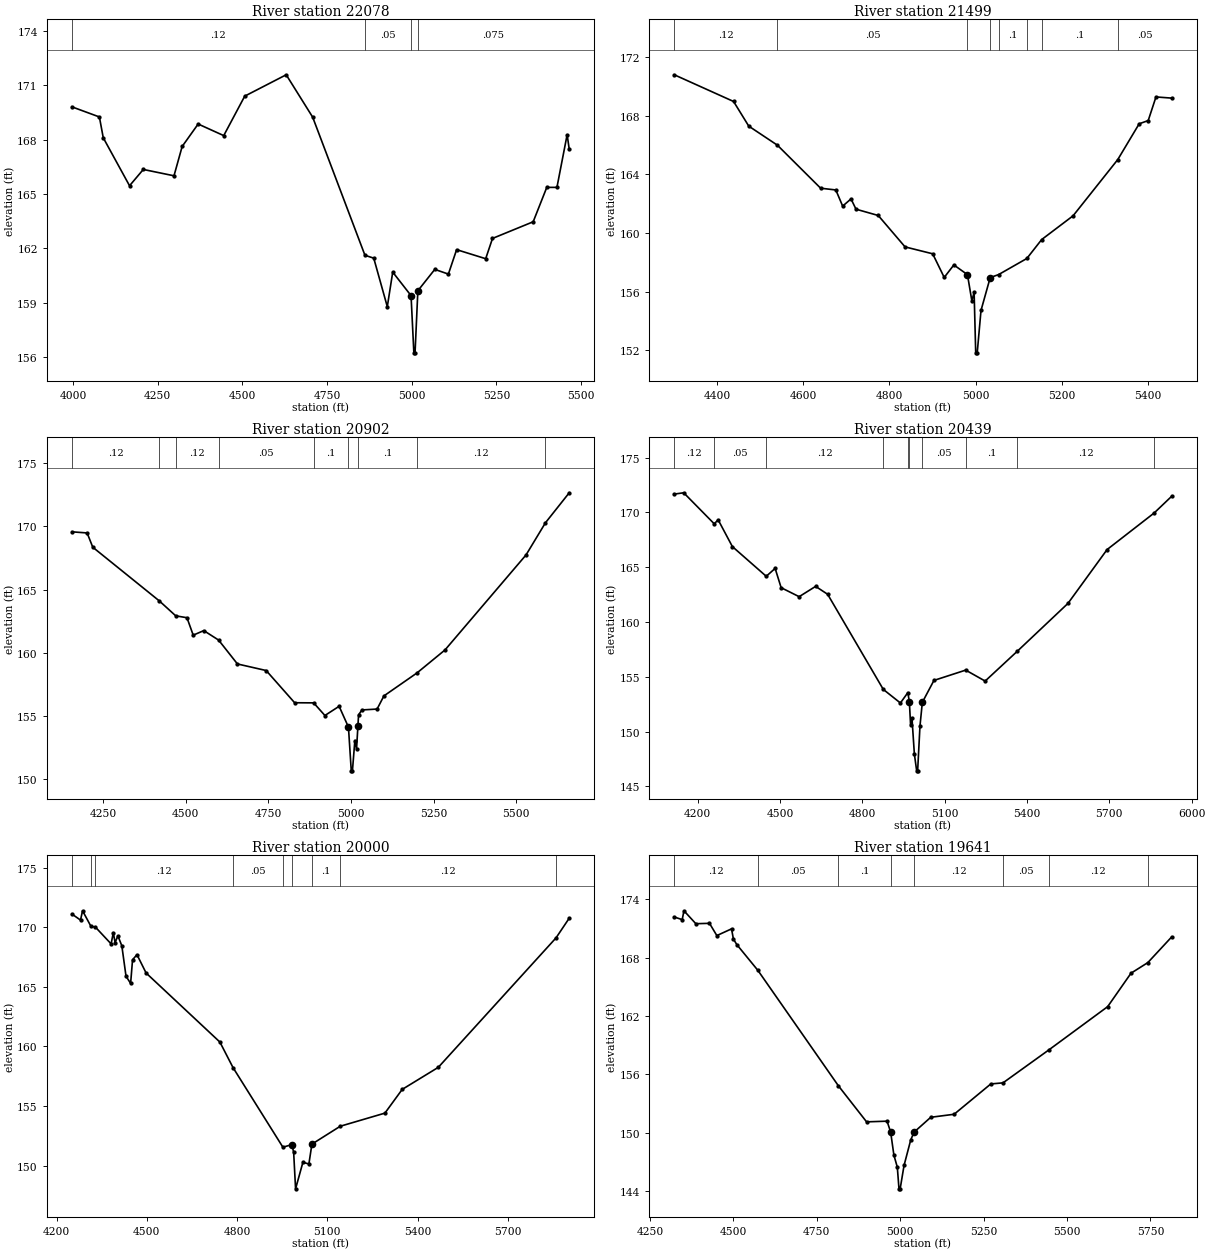
Type RM Length L Ch R = 1 ,22078   ,579,579,579
BEGIN DESCRIPTION:
SILVERDALE CREEK 44.0
END DESCRIPTION:
XS GIS Cut Line= 3
       3836575.9     10103026.42      3836338.92      10102443.1
      3835501.64     10102398.25
#Sta/Elev= 30
  3996.8  169.82  4078.1  169.26  4089.5  168.11  4167.1  165.46  4207.7  166.36
  4298.3  166.01  4322.4  167.63  4369.6  168.87  4445.1  168.23  4507.1  170.41
  4629.5  171.59  4707.6  169.25  4861.9  161.62  4887.9  161.46  4927.9  158.78
  4943.9  160.69    4998  159.39  5006.3  156.23  5009.8  156.23  5018.1  159.66
  5068.1  160.84  5108.2  160.58  5132.5  161.93  5218.3  161.43  5238.4  162.55
  5358.5  163.47  5398.6  165.37  5428.6  165.37  5458.7  168.28  5464.9  167.48
#Mann= 4 ,-1 , 0
  3996.8     .12       0  4861.9     .05       0    4998     .07       0
  5018.1    .075       0
Bank Sta=4998,5018.1
XS Rating Curve= 0 ,0
Exp/Cntr=0.3,0.1

Type RM Length L Ch R = 1 ,21499   ,597,597,597
BEGIN DESCRIPTION:
SILVERDALE CREEK 43.0
END DESCRIPTION:
XS GIS Cut Line= 3
      3836367.58     10102419.71      3836245.17     10101950.92
      3835605.94     10101745.63
#Sta/Elev= 30
  4299.9  170.78  4437.7  168.96    4473  167.28  4539.6  165.98    4640  163.05
  4675.3  162.93  4691.2  161.83  4710.6  162.32  4722.2  161.62  4773.9  161.19
  4836.2  159.05  4900.4  158.58  4927.2  156.97  4949.6  157.82  4981.2  157.16
  4991.4  155.38  4996.7  155.95  5000.4  151.83  5003.9  151.83  5012.7  154.72
  5034.1  156.96  5053.4  157.16  5119.2  158.26  5153.7  159.55  5226.7  161.17
  5330.5     165  5380.3  167.44  5401.3  167.66  5419.3  169.27  5455.8  169.19
#Mann= 8 ,-1 , 0
  4299.9     .12       0  4539.6     .05       0  4981.2     .07       0
  5034.1     .05       0  5053.4      .1       0  5119.2     .05       0
  5153.7      .1       0  5330.5     .05       0
Bank Sta=4981.2,5034.1
XS Rating Curve= 0 ,0
Exp/Cntr=0.3,0.1

Type RM Length L Ch R = 1 ,20902   ,463,463,463
BEGIN DESCRIPTION:
SILVERDALE CREEK 42.0
END DESCRIPTION:
XS GIS Cut Line= 3
      3836391.01     10102383.24      3836224.34     10101492.58
      3835641.95     10101357.38
#Sta/Elev= 30
    4156  169.57  4202.2  169.48  4219.3  168.35  4420.5   164.1  4470.1  162.92
  4504.1  162.77    4523  161.39    4555  161.75  4599.8     161  4656.7  159.11
  4743.6  158.59  4829.7  156.04  4887.2  156.03  4921.2  155.03  4964.2  155.76
  4992.4  154.11  5000.9  150.65  5004.4  150.65  5011.8  153.05  5016.9  152.38
    5021 154.195    5023  155.08  5033.1  155.47    5079  155.54  5099.6  156.58
  5199.7   158.4  5284.4  160.22  5529.4  167.74  5588.2  170.29    5660  172.66
#Mann= 9 ,-1 , 0
    4156     .12       0  4420.5     .05       0  4470.1     .12       0
  4599.8     .05       0  4887.2      .1       0  4992.4     .07       0
    5021      .1       0  5199.7     .12       0  5588.2     .05       0
Bank Sta=4992.4,5021
XS Rating Curve= 0 ,0
Exp/Cntr=0.3,0.1

Type RM Length L Ch R = 1 ,20439   ,439,439,439
BEGIN DESCRIPTION:
SILVERDALE CREEK 41.0
END DESCRIPTION:
XS GIS Cut Line= 3
      3837078.51     10101987.37      3836742.57     10101364.98
      3835656.65     10101159.25
#Sta/Elev= 30
  4114.7  171.67    4149  171.79  4260.2  168.96  4274.6  169.32  4326.4  166.88
  4449.8  164.17  4482.2  164.89  4504.1  163.13  4569.7  162.31  4629.7  163.25
  4673.5  162.53  4876.3  153.85  4938.7  152.61  4965.9  153.56 4971.36 152.714
  4975.8  150.61  4980.9  151.21  4989.6  147.95    4998  146.42  5001.5  146.42
    5010  150.51 5018.59  152.67  5060.9  154.67  5176.6  155.61  5247.5  154.61
  5364.6  157.33  5549.4   161.7  5691.9  166.61  5863.1  169.94  5927.2  171.47
#Mann= 10 ,-1 , 0
  4114.7     .12       0  4260.2     .05       0  4449.8     .12       0
  4876.3      .1       0  4965.9     .05       0 4971.36     .03       0
 5018.59     .05       0  5176.6      .1       0  5364.6     .12       0
  5863.1     .05       0
Bank Sta=4971.36,5018.59
XS Rating Curve= 0 ,0
Exp/Cntr=0.3,0.1

Type RM Length L Ch R = 1 ,20000   ,359,359,359
BEGIN DESCRIPTION:
SILVERDALE CREEK 40.0
END DESCRIPTION:
XS GIS Cut Line= 3
      3837217.86     10100611.07      3836586.78     10101014.85
       3835682.8     10100987.38
#Sta/Elev= 30
  4250.8  171.11  4279.6   170.6  4286.4  171.38  4314.4  170.07  4328.8  170.02
  4381.4   168.6  4388.6  169.55  4394.6  168.71  4403.9  169.28    4417  168.44
  4430.9  165.89  4446.2  165.29  4452.6  167.27  4467.3   167.7  4497.7  166.16
    4743  160.37  4786.6  158.23  4952.5  151.55  4982.3  151.77  4988.2  151.13
  4994.6  148.06  5018.9  150.28  5038.9  150.15  5048.9  151.81  5143.2  153.31
  5291.6  154.41  5349.1   156.4  5469.1  158.25  5860.6  169.11  5904.4  170.76
#Mann= 9 ,-1 , 0
  4250.8     .12       0  4314.4     .05       0  4328.8     .12       0
  4786.6     .05       0  4952.5      .1       0  4982.3     .07       0
  5048.9      .1       0  5143.2     .12       0  5860.6     .05       0
Bank Sta=4982.3,5048.9
XS Rating Curve= 0 ,0
Exp/Cntr=0.3,0.1

Type RM Length L Ch R = 1 ,19641   ,615,615,615
BEGIN DESCRIPTION:
SILVERDALE CREEK 39.0
END DESCRIPTION:
XS GIS Cut Line= 3
      3837141.01     10100549.87      3836479.55      10100693.1
      3835666.04      10100706.1
#Sta/Elev= 30
  4323.3  172.19    4347  171.92  4352.3  172.83  4387.9   171.5  4428.8  171.54
  4450.8  170.28  4494.8  170.97  4500.5  169.92  4510.7  169.35  4573.6  166.71
    4815  154.83  4899.5  151.12  4960.9  151.19  4971.6  150.07  4981.4  147.69
  4991.6  146.46  4996.6  144.23  5000.1  144.23  5011.8  146.64  5031.8  149.26
  5041.8  150.06  5091.8  151.59  5161.8   151.9  5271.8  155.02  5308.3  155.13
  5446.1  158.53  5621.9  162.97  5691.9  166.41  5742.3   167.5  5813.7  170.14
#Mann= 8 ,-1 , 0
  4323.3     .12       0  4573.6     .05       0    4815      .1       0
  4971.6     .07       0  5041.8     .12       0  5308.3     .05       0
  5446.1     .12       0  5742.3     .05       0
Bank Sta=4971.6,5041.8
XS Rating Curve= 0 ,0
Exp/Cntr=0.3,0.1