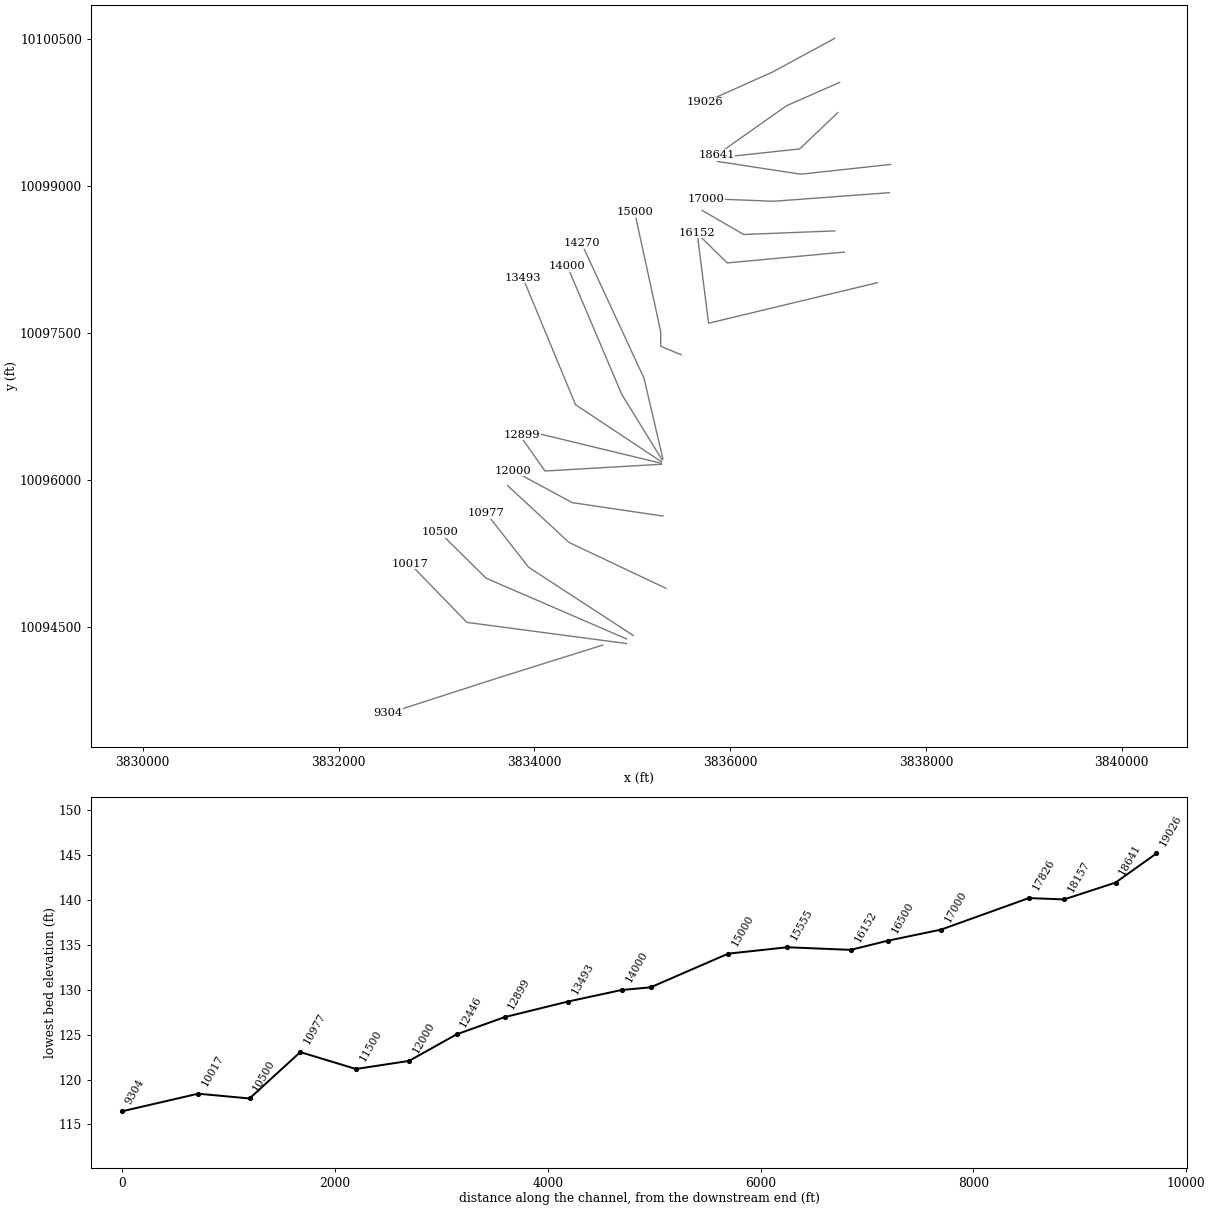
HEC-RAS study SILVERDALE CREEK.prj: SILVERDALE CREEK Base Level Engineering

--- SILVERDALE CREEK.g10 (geometry) --- (continued)

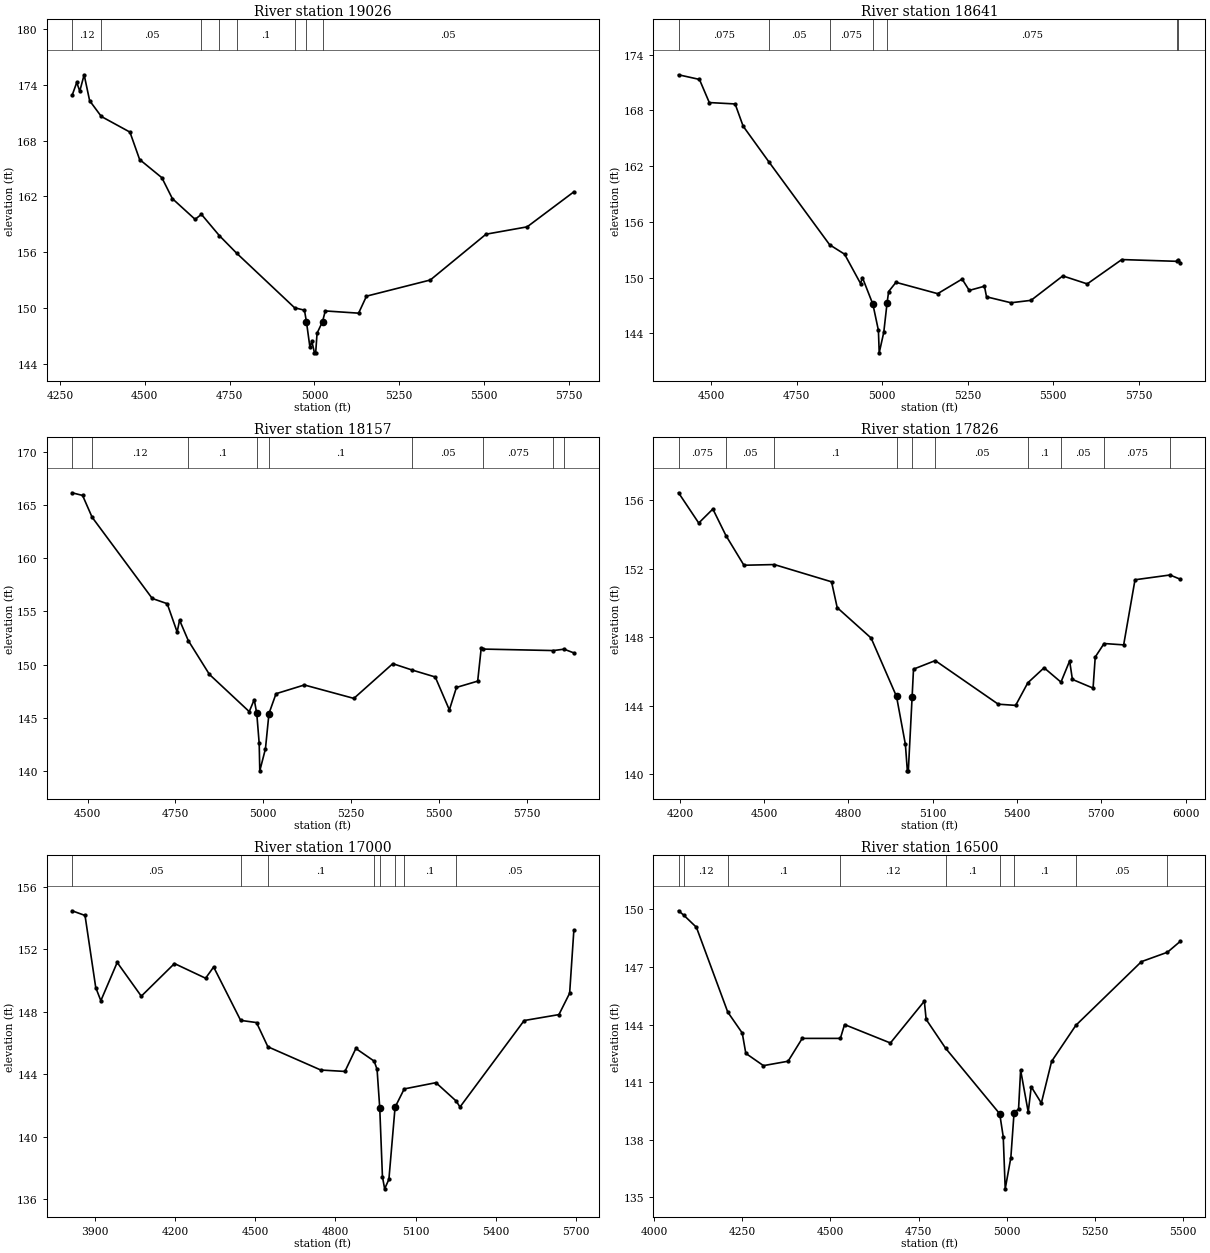
Type RM Length L Ch R = 1 ,19026   ,385,385,385
BEGIN DESCRIPTION:
SILVERDALE CREEK 38.0
END DESCRIPTION:
XS GIS Cut Line= 3
      3837067.84     10100511.07      3836432.46     10100166.84
      3835741.44     10099857.83
#Sta/Elev= 30
  4285.4  172.85  4299.2  174.25  4308.1  173.32    4321  175.08  4337.2  172.29
  4371.7  170.59    4456  168.91  4484.6  165.96  4550.2     164  4581.1  161.75
  4648.2  159.52  4666.8  160.06  4719.6  157.77  4770.3  155.89  4941.6     150
  4970.6  149.74  4976.5 148.491  4986.8  145.74  4992.4  146.38  5000.2  145.15
  5003.7  145.15  5007.8  147.26    5024  148.52    5032  149.66  5130.3  149.42
  5153.5  151.25  5341.7  152.99    5506  157.92  5627.2  158.71    5765  162.48
#Mann= 8 ,-1 , 0
  4285.4     .12       0  4371.7     .05       0  4666.8      .1       0
  4719.6     .05       0  4770.3      .1       0  4941.6     .05       0
  4976.5     .07       0    5024     .05       0
Bank Sta=4976.5,5024
XS Rating Curve= 0 ,0
Exp/Cntr=0.3,0.1

Type RM Length L Ch R = 1 ,18641   ,484,484,484
BEGIN DESCRIPTION:
SILVERDALE CREEK 37.0
END DESCRIPTION:
XS GIS Cut Line= 3
      3837117.89     10100061.09       3836575.9     10099822.79
      3835861.28     10099318.66
#Sta/Elev= 30
  4404.9  171.83    4466  171.33  4494.8  168.84  4570.3  168.69  4593.7   166.3
  4668.3  162.49  4846.6  153.53  4890.2  152.52  4936.9  149.36  4942.4     150
    4973  147.12  4989.1  144.32  4991.4   141.9  5004.7   144.1 5014.37 147.258
    5019   148.5  5040.4  149.49  5162.3  148.27  5233.7  149.84  5254.6  148.62
    5299  149.07  5305.1  147.93  5376.5  147.29  5435.1  147.55    5528  150.18
  5599.4  149.32  5700.4  151.94  5862.1  151.75  5865.5  151.94  5871.5   151.6
#Mann= 7 ,-1 , 0
  4404.9    .075       0  4668.3     .05       0  4846.6    .075       0
    4973     .07       0 5014.37    .075       0  5862.1     .05       0
  5865.5    .075       0
Bank Sta=4973,5014.37
XS Rating Curve= 0 ,0
Exp/Cntr=0.3,0.1

Type RM Length L Ch R = 1 ,18157   ,331,331,331
BEGIN DESCRIPTION:
SILVERDALE CREEK 36.0
END DESCRIPTION:
XS GIS Cut Line= 3
      3837098.89     10099752.46      3836710.45     10099381.38
      3835825.88     10099285.99
#Sta/Elev= 30
  4456.1  166.13    4486  165.88    4513  163.84  4684.1  156.21  4726.6  155.72
  4754.9  153.06  4761.8  154.17  4786.5  152.26  4846.7  149.08  4959.9  145.59
  4974.1  146.71  4981.3  145.42  4988.2   142.6  4989.9  140.03    5006   142.1
    5016  145.41  5036.1  147.27  5116.6  148.09  5257.4  146.83  5368.1  150.09
  5423.3  149.49  5488.8  148.84    5529  145.75  5549.1  147.86  5609.5  148.45
  5619.5  151.53    5624  151.46  5824.7  151.32  5855.1  151.45    5883   151.1
#Mann= 9 ,-1 , 0
  4456.1     .05       0    4513     .12       0  4786.5      .1       0
  4981.3     .07       0    5016      .1       0  5423.3     .05       0
    5624    .075       0  5824.7     .05       0  5855.1    .075       0
Bank Sta=4981.3,5016
XS Rating Curve= 0 ,0
Exp/Cntr=0.3,0.1

Type RM Length L Ch R = 1 ,17826   ,826,826,826
BEGIN DESCRIPTION:
SILVERDALE CREEK 35.0
END DESCRIPTION:
XS GIS Cut Line= 3
      3837639.32     10099222.97       3836721.3     10099123.14
      3835868.41     10099253.35
#Sta/Elev= 30
  4195.2  156.45  4267.1  154.68  4317.4   155.5  4363.8  153.95    4428  152.21
  4536.1  152.25  4739.9  151.24    4760  149.73  4880.7  147.95  4971.2  144.53
  5002.7  141.73  5009.7  140.18  5013.2  140.18  5026.6 144.482  5031.6  146.13
    5109  146.63  5333.2  144.08  5395.2  144.01  5438.5  145.33  5496.4  146.21
  5556.5  145.37  5587.4  146.61  5597.2  145.53  5670.8  145.02  5678.5  146.84
    5710  147.63  5779.7  147.55  5820.1  151.36  5944.7  151.64  5981.4  151.39
#Mann= 10 ,-1 , 0
  4195.2    .075       0  4363.8     .05       0  4536.1      .1       0
  4971.2     .07       0  5026.6      .1       0    5109     .05       0
  5438.5      .1       0  5556.5     .05       0    5710    .075       0
  5944.7     .05       0
Bank Sta=4971.2,5026.6
XS Rating Curve= 0 ,0
Exp/Cntr=0.3,0.1

Type RM Length L Ch R = 1 ,17000   ,500,500,500
BEGIN DESCRIPTION:
SILVERDALE CREEK 34.0
END DESCRIPTION:
XS GIS Cut Line= 3
      3837626.24     10098934.34      3836443.69     10098846.61
      3835752.01     10098873.54
#Sta/Elev= 30
  3814.2  154.48  3862.7  154.18  3902.8  149.56  3921.9  148.72  3983.1  151.17
  4073.3  149.01  4197.4   151.1    4314  150.16    4344  150.88  4445.1  147.46
  4504.5  147.32    4547  145.77  4745.1  144.28  4835.4  144.19  4876.3  145.66
  4944.8  144.85  4955.7  144.32  4965.7  141.85  4975.8  137.45    4984  136.67
    5000  137.28 5023.05 141.895  5057.3  143.07    5176  143.47    5252  142.29
    5266  141.91  5506.2  147.45  5636.3  147.83  5676.4   149.2  5692.2  153.24
#Mann= 8 ,-1 , 0
  3814.2     .05       0  4445.1     .12       0    4547      .1       0
  4944.8     .12       0  4965.7     .07       0 5023.05     .12       0
  5057.3      .1       0    5252     .05       0
Bank Sta=4965.7,5023.05
XS Rating Curve= 0 ,0
Exp/Cntr=0.3,0.1

Type RM Length L Ch R = 1 ,16500   ,348,348,348
BEGIN DESCRIPTION:
SILVERDALE CREEK 33.0
END DESCRIPTION:
XS GIS Cut Line= 3
      3837068.55     10098543.91      3836138.19     10098506.82
      3835711.79     10098753.87
#Sta/Elev= 30
  4068.9  149.93  4083.8   149.7  4119.6  149.07  4208.6  144.65  4249.7  143.56
  4259.8   142.5  4309.8  141.86  4379.8  142.09  4419.9  143.28  4528.1  143.28
    4540     144  4670.1  143.04  4766.4  145.22  4771.5  144.27  4826.6  142.77
  4980.3  139.35  4990.3  138.15  4995.9  135.44  5011.9  137.07  5020.9 139.387
  5033.8  139.61  5039.6  141.63  5061.2  139.44  5069.7  140.76  5098.4  139.91
  5127.5  142.08  5196.3  143.96  5382.5  147.28  5456.3  147.77  5492.8  148.34
#Mann= 9 ,-1 , 0
  4068.9     .05       0  4083.8     .12       0  4208.6      .1       0
  4528.1     .12       0  4826.6      .1       0  4980.3     .07       0
  5020.9      .1       0  5196.3     .05       0  5456.3    .075       0
Bank Sta=4980.3,5020.9
XS Rating Curve= 0 ,0
Exp/Cntr=0.3,0.1

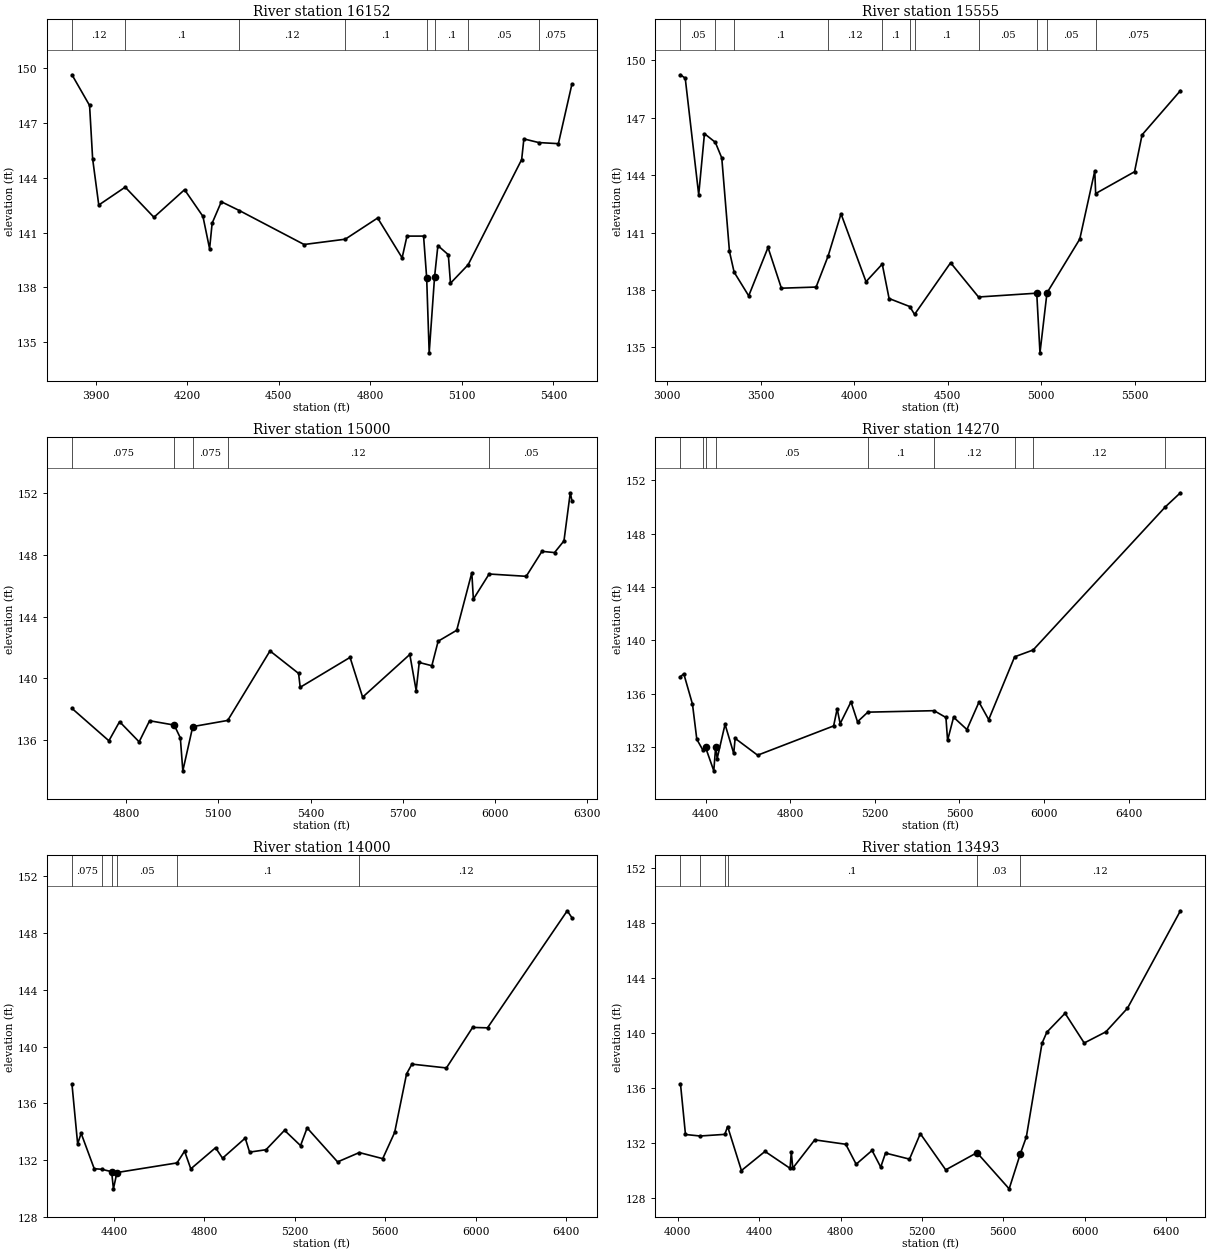
Type RM Length L Ch R = 1 ,16152   ,597,597,597
BEGIN DESCRIPTION:
SILVERDALE CREEK 32.0
END DESCRIPTION:
XS GIS Cut Line= 3
      3837165.27     10098327.33      3835969.57     10098216.66
      3835657.05     10098523.09
#Sta/Elev= 30
  3822.3  149.64    3880  147.96    3890  145.04  3910.1  142.51  3996.7  143.49
  4090.9  141.84  4191.3  143.35  4251.5  141.89  4273.3  140.12  4281.7  141.52
  4311.8  142.69  4370.7  142.21    4583  140.35  4717.9  140.64    4824   141.8
  4904.3  139.62  4920.2  140.81  4974.6  140.81  4984.7  138.54    4993  134.42
  5010.6 138.576  5021.5  140.29  5055.7  139.79  5062.8  138.23  5120.6  139.24
  5296.1     145  5303.3  146.13    5352  145.93  5416.4  145.87  5460.8  149.13
#Mann= 8 ,-1 , 0
  3822.3     .12       0  3996.7      .1       0  4370.7     .12       0
  4717.9      .1       0  4984.7     .07       0  5010.6      .1       0
  5120.6     .05       0    5352    .075       0
Bank Sta=4984.7,5010.6
XS Rating Curve= 0 ,0
Exp/Cntr=0.3,0.1

Type RM Length L Ch R = 1 ,15555   ,555,555,555
BEGIN DESCRIPTION:
SILVERDALE CREEK 31.0
END DESCRIPTION:
XS GIS Cut Line= 3
      3837502.66      10098014.2      3835779.03     10097600.68
      3835665.75      10098494.4
#Sta/Elev= 30
  3070.4  149.25  3095.9  149.07  3167.9  142.98  3198.7  146.17  3256.7  145.72
  3291.3   144.9  3332.4  140.01  3357.3  138.93  3435.3  137.69  3538.6  140.22
  3610.1  138.09  3795.7  138.15  3859.9  139.77  3928.9  141.98  4062.6  138.43
  4149.4  139.35    4186  137.55  4296.6  137.13  4322.2  136.72  4514.9  139.42
  4664.2  137.63  4975.5  137.83  4992.8  134.71 5030.23 137.845  5205.7  140.66
  5285.8  144.22  5290.6  143.04  5498.5  144.18  5538.8  146.11  5743.8  148.42
#Mann= 11 ,-1 , 0
  3070.4     .05       0  3256.7     .12       0  3357.3      .1       0
  3859.9     .12       0  4149.4      .1       0  4296.6     .12       0
  4322.2      .1       0  4664.2     .05       0  4975.5     .07       0
 5030.23     .05       0  5290.6    .075       0
Bank Sta=4975.5,5030.23
XS Rating Curve= 0 ,0
Exp/Cntr=0.3,0.1

Type RM Length L Ch R = 1 ,15000   ,730,730,730
BEGIN DESCRIPTION:
SILVERDALE CREEK 30.0
END DESCRIPTION:
XS GIS Cut Line= 4
      3835499.66      10097278.3      3835290.42     10097365.12
      3835290.02     10097514.68      3835023.99     10098736.35
#Sta/Elev= 30
  4623.9  138.05    4744  135.95  4778.7  137.19  4842.4  135.88  4876.4  137.25
  4956.4  136.97  4976.4  136.14  4984.5     134  5016.8  136.87  5130.5  137.27
  5268.1  141.78  5361.1  140.32  5366.3  139.42  5528.5  141.36  5569.4  138.78
  5722.9  141.55  5743.6  139.21  5753.6  141.03  5794.6  140.82  5815.1  142.41
  5875.5  143.12  5924.6  146.85  5929.7  145.14  5980.9  146.77  6101.6  146.62
  6152.8  148.24  6193.7  148.16  6224.4  148.92  6244.9  152.04  6250.3  151.53
#Mann= 5 ,-1 , 0
  4623.9    .075       0  4956.4     .07       0  5016.8    .075       0
  5130.5     .12       0  5980.9     .05       0
Bank Sta=4956.4,5016.8
XS Rating Curve= 0 ,0
Exp/Cntr=0.3,0.1

Type RM Length L Ch R = 1 ,14270   ,270,270,270
BEGIN DESCRIPTION:
SILVERDALE CREEK 29.0
END DESCRIPTION:
XS GIS Cut Line= 3
      3835312.13     10096215.79      3835119.42     10097038.73
       3834481.2     10098417.48
#Sta/Elev= 30
  4280.8   137.3  4296.5  137.51  4337.6  135.24  4358.1  132.61  4385.4  131.84
  4399.2  132.02  4438.4  130.25 4447.31 132.049  4454.4  131.17  4491.6  133.73
  4532.7  131.55  4539.3  132.68  4645.7  131.42  5005.2  133.61  5021.9  134.89
    5036  133.78  5087.3  135.41  5118.1  133.92  5166.9  134.64  5480.3  134.75
  5536.3  134.24  5544.1  132.53  5572.5  134.26  5635.5  133.34  5692.6  135.39
  5738.5  134.08  5861.2  138.78  5948.7  139.29  6574.2     150  6645.3  151.05
#Mann= 9 ,-1 , 0
  4280.8    .075       0  4385.4     .05       0  4399.2     .07       0
 4447.31     .05       0  5166.9      .1       0  5480.3     .12       0
  5861.2     .05       0  5948.7     .12       0  6574.2     .05       0
Bank Sta=4399.2,4447.31
XS Rating Curve= 0 ,0
Exp/Cntr=0.3,0.1

Type RM Length L Ch R = 1 ,14000   ,507,507,507
BEGIN DESCRIPTION:
SILVERDALE CREEK 28.0
END DESCRIPTION:
XS GIS Cut Line= 3
       3835305.2     10096203.34      3834892.66     10096872.73
      3834334.91     10098185.56
#Sta/Elev= 30
  4213.7  137.34  4238.8  133.13  4254.2  133.88  4312.2  131.38  4345.7  131.34
  4389.2 131.169  4397.1  129.96  4412.7  131.11  4678.7  131.79    4712  132.62
  4739.6  131.37  4849.2  132.86    4880  132.12  4980.5  133.54  4999.8  132.55
  5072.5  132.72  5154.4  134.09  5225.3  133.01  5254.4  134.26  5389.3  131.86
  5485.3  132.52    5589  132.09  5641.8  133.94  5694.5  138.07  5718.2  138.76
  5870.9  138.49  5986.9  141.35  6052.8  141.32  6405.7  149.58  6426.4  149.09
#Mann= 6 ,-1 , 0
  4213.7    .075       0  4345.7     .05       0  4389.2     .03       0
  4412.7     .05       0  4678.7      .1       0  5485.3     .12       0
Bank Sta=4389.2,4412.7
XS Rating Curve= 0 ,0
Exp/Cntr=0.3,0.1

Type RM Length L Ch R = 1 ,13493   ,594,594,594
BEGIN DESCRIPTION:
SILVERDALE CREEK 27.0
END DESCRIPTION:
XS GIS Cut Line= 3
      3835297.39     10096185.13      3834419.76     10096768.47
      3833882.66      10098064.8
#Sta/Elev= 30
  4013.5  136.31  4038.1  132.62  4109.9  132.51  4231.4  132.63  4245.2   133.2
  4313.1     130    4429  131.39  4552.2  130.16  4558.2  131.36  4565.3  130.17
  4673.4  132.23  4825.8  131.91  4876.9  130.46  4955.1  131.46  4997.6  130.25
  5021.2  131.27    5139  130.83  5192.2  132.68  5317.1  130.05  5470.6   131.3
  5628.9  128.67    5684  131.23  5713.3  132.44  5790.3  139.25  5814.2  140.06
  5903.6  141.43  5997.7  139.27    6104  140.08  6210.4   141.8  6470.5  148.88
#Mann= 6 ,-1 , 0
  4013.5    .075       0  4109.9     .05       0  4231.4     .12       0
  4245.2      .1       0  5470.6     .03       0    5684     .12       0
Bank Sta=5470.6,5684
XS Rating Curve= 0 ,0
Exp/Cntr=0.3,0.1

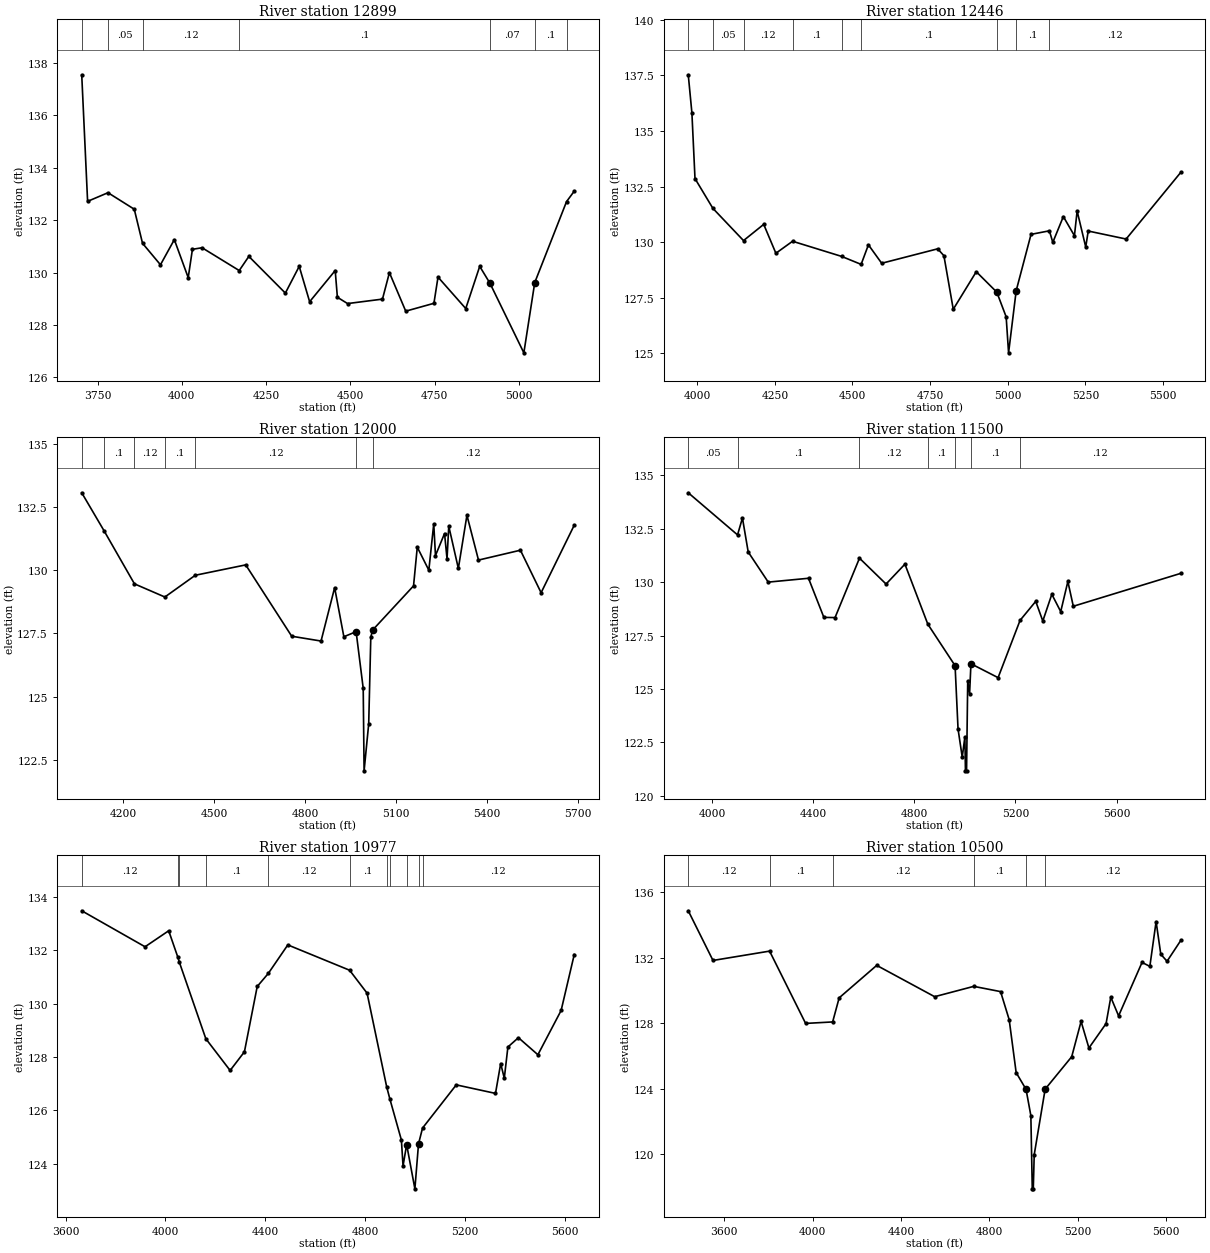
Type RM Length L Ch R = 1 ,12899   ,453,453,453
BEGIN DESCRIPTION:
SILVERDALE CREEK 26.0
END DESCRIPTION:
XS GIS Cut Line= 3
      3835294.75     10096169.52      3834034.35     10096474.64
      3833871.15      10096459.6
#Sta/Elev= 30
  3703.1  137.55  3720.5  132.72    3781  133.05  3858.9  132.42  3883.4  131.12
  3936.6   130.3  3977.7  131.26  4018.9  129.81  4031.4  130.89    4060  130.95
  4170.2  130.08  4198.7  130.62    4307  129.22  4348.1  130.24    4379  128.89
  4454.8  130.08  4461.3  129.06  4491.5  128.82    4595  128.99  4615.6     130
    4664  128.53  4747.6  128.83  4759.7  129.83    4842  128.63  4883.4  130.24
    4914  129.59  5014.3  126.94  5046.6  129.62  5140.9  132.71  5163.8  133.11
#Mann= 7 ,-1 , 0
  3703.1    .075       0    3781     .05       0  3883.4     .12       0
  4170.2      .1       0    4914     .07       0  5046.6      .1       0
  5140.9     .12       0
Bank Sta=4914,5046.6
XS Rating Curve= 0 ,0
Exp/Cntr=0.3,0.1

Type RM Length L Ch R = 1 ,12446   ,446,446,446
BEGIN DESCRIPTION:
SILVERDALE CREEK 25.0
END DESCRIPTION:
XS GIS Cut Line= 3
      3835299.49     10096159.96      3834108.13     10096090.52
      3833882.63     10096411.43
#Sta/Elev= 30
  3971.3  137.53    3983  135.82    3993  132.86  4050.6  131.52  4149.2  130.07
  4214.2   130.8  4253.4   129.5  4307.1  130.04  4464.7  129.36  4527.8     129
  4551.3  129.88    4594  129.05  4774.3   129.7  4794.3  129.39  4824.4  126.98
  4898.5  128.67  4964.6  127.75  4994.7  126.64  5002.5  125.02 5027.04 127.818
  5074.8  130.35  5133.9  130.51  5144.9  129.99  5178.8  131.15  5214.5  130.29
  5223.2   131.4  5250.9  129.78  5258.9   130.5  5380.9  130.14  5556.9  133.14
#Mann= 9 ,-1 , 0
  3971.3    .075       0  4050.6     .05       0  4149.2     .12       0
  4307.1      .1       0  4464.7     .12       0  4527.8      .1       0
  4964.6     .07       0 5027.04      .1       0  5133.9     .12       0
Bank Sta=4964.6,5027.04
XS Rating Curve= 0 ,0
Exp/Cntr=0.3,0.1

Type RM Length L Ch R = 1 ,12000   ,500,500,500
BEGIN DESCRIPTION:
SILVERDALE CREEK 24.0
END DESCRIPTION:
XS GIS Cut Line= 3
      3835312.59     10095630.45      3834386.48     10095767.56
      3833781.65     10096094.21
#Sta/Elev= 30
  4063.8  133.06  4137.3  131.56  4237.6  129.46  4337.9  128.94  4438.2   129.8
  4604.4  130.21    4756  127.39  4852.7   127.2  4897.5  129.31  4927.9  127.37
  4968.3  127.57  4991.7  125.33  4994.6  122.07  5009.8  123.93  5016.7  127.35
  5022.4  127.63  5157.6  129.38  5169.9  130.91    5208     130  5224.2  131.83
  5229.9  130.58  5259.8  131.45    5268  130.45  5273.7  131.74  5305.3  130.07
  5333.6  132.17  5371.7   130.4  5509.9  130.79  5578.1  129.11  5687.4  131.78
#Mann= 7 ,-1 , 0
  4063.8    .075       0  4137.3      .1       0  4237.6     .12       0
  4337.9      .1       0  4438.2     .12       0  4968.3     .07       0
  5022.4     .12       0
Bank Sta=4968.3,5022.4
XS Rating Curve= 0 ,0
Exp/Cntr=0.3,0.1

Type RM Length L Ch R = 1 ,11500   ,523,523,523
BEGIN DESCRIPTION:
SILVERDALE CREEK 23.0
END DESCRIPTION:
XS GIS Cut Line= 3
       3835342.9     10094892.62      3834353.37     10095360.58
      3833726.95     10095941.46
#Sta/Elev= 30
  3905.4  134.18  4100.4  132.21  4119.8     133  4142.6  131.41  4221.9     130
  4381.2  130.18    4442  128.35  4486.2  128.34  4582.9  131.12  4688.1  129.91
  4762.7  130.84  4853.4  128.03  4961.2  126.09  4972.9  123.13  4989.5  121.81
    5000  122.76  5002.2  121.17  5006.6  121.17  5011.2  125.38  5018.6  124.78
 5023.95 126.181  5131.4  125.53  5218.3  128.21  5280.3   129.1  5308.3  128.18
    5344  129.43  5379.2  128.62  5407.5  130.03    5429  128.87  5854.3  130.41
#Mann= 7 ,-1 , 0
  3905.4     .05       0  4100.4      .1       0  4582.9     .12       0
  4853.4      .1       0  4961.2     .07       0 5023.95      .1       0
  5218.3     .12       0
Bank Sta=4961.2,5023.95
XS Rating Curve= 0 ,0
Exp/Cntr=0.3,0.1

Type RM Length L Ch R = 1 ,10977   ,477,477,477
BEGIN DESCRIPTION:
SILVERDALE CREEK 22.0
END DESCRIPTION:
XS GIS Cut Line= 3
      3835009.94      10094410.2      3833941.03     10095107.45
       3833510.2     10095657.36
#Sta/Elev= 30
  3664.2  133.48  3918.1  132.13  4012.9  132.73  4049.9  131.73    4056  131.54
  4161.8  128.68  4259.2  127.49  4316.5  128.19  4367.8  130.64  4412.3  131.13
  4490.5   132.2  4738.2  131.25  4808.3  130.39  4886.8  126.88  4899.7  126.42
  4945.9  124.88  4952.5  123.91    4967  124.71    5000  123.05 5014.56 124.738
  5030.7  125.33  5165.9  126.95  5323.2  126.63    5344  127.75  5358.5   127.2
  5372.9  128.37  5415.1  128.72  5493.2  128.08  5586.3  129.74    5639  131.84
#Mann= 11 ,-1 , 0
  3664.2     .12       0  4049.9      .1       0    4056     .12       0
  4161.8      .1       0  4412.3     .12       0  4738.2      .1       0
  4886.8     .12       0  4899.7      .1       0    4967     .03       0
 5014.56      .1       0  5030.7     .12       0
Bank Sta=4967,5014.56
XS Rating Curve= 0 ,0
Exp/Cntr=0.3,0.1

Type RM Length L Ch R = 1 ,10500   ,483,483,483
BEGIN DESCRIPTION:
SILVERDALE CREEK 21.0
END DESCRIPTION:
XS GIS Cut Line= 3
      3834940.55     10094375.45       3833506.7     10094995.57
       3833032.7     10095463.84
#Sta/Elev= 30
  3437.8  134.85  3549.7  131.82  3805.8  132.39  3968.8  127.98  4091.1  128.07
  4120.6  129.54  4290.5  131.52  4552.6  129.61  4729.6  130.24  4850.9  129.92
  4889.8  128.21  4921.4  124.98  4966.1  123.96  4987.9  122.36  4994.3  117.89
  4998.9  117.89  5003.1  119.97  5052.6  123.97  5172.8  125.95  5215.2   128.1
  5250.6  126.48  5328.3  127.97  5349.6  129.58  5384.9  128.44  5490.9   131.7
  5526.3  131.46  5554.6  134.19  5575.8   132.2  5604.1  131.77  5666.3  133.04
#Mann= 6 ,-1 , 0
  3437.8     .12       0  3805.8      .1       0  4091.1     .12       0
  4729.6      .1       0  4966.1     .07       0  5052.6     .12       0
Bank Sta=4966.1,5052.6
XS Rating Curve= 0 ,0
Exp/Cntr=0.3,0.1

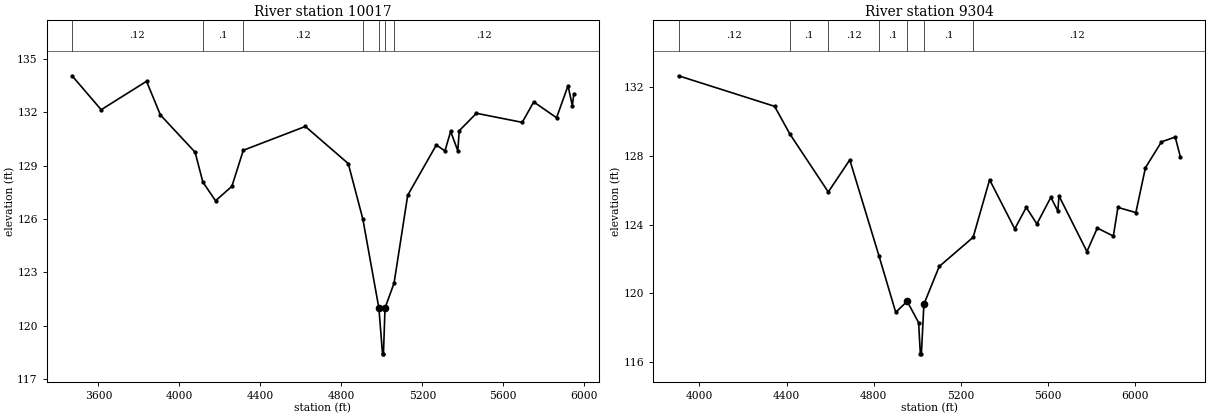
Type RM Length L Ch R = 1 ,10017   ,713,713,713
BEGIN DESCRIPTION:
SILVERDALE CREEK 20.0
END DESCRIPTION:
XS GIS Cut Line= 3
      3834940.39      10094328.1      3833310.17     10094544.24
      3832729.41     10095143.23
#Sta/Elev= 30
  3469.6  134.06  3613.4  132.15  3837.5  133.75  3905.8  131.86  4077.4  129.76
  4115.4  128.09  4178.3  127.03    4259  127.84  4315.5  129.87  4622.1  131.21
    4834  129.12    4906     126  4985.3  120.99  5003.2  118.42  5007.8  118.42
  5015.6     121  5060.3   122.4  5127.6  127.34  5269.1  130.17  5311.5  129.83
  5339.8  130.93  5375.1  129.84  5382.2  130.97  5467.1  131.95  5693.5  131.44
  5750.1  132.59    5863   131.7  5919.6   133.5  5940.9  132.38  5948.4  133.05
#Mann= 7 ,-1 , 0
  3469.6     .12       0  4115.4      .1       0  4315.5     .12       0
    4906      .1       0  4985.3     .07       0  5015.6      .1       0
  5060.3     .12       0
Bank Sta=4985.3,5015.6
XS Rating Curve= 0 ,0
Exp/Cntr=0.3,0.1

Type RM Length L Ch R = 1 ,9304    ,143,143,143
BEGIN DESCRIPTION:
SILVERDALE CREEK 19.0
END DESCRIPTION:
XS GIS Cut Line= 3
      3834698.19     10094312.47      3833627.88     10093976.53
       3832505.5     10093614.56
#Sta/Elev= 30
  3904.8  132.67  4345.4  130.89  4415.2  129.28  4591.5   125.9  4690.1  127.77
  4823.9  122.18  4900.8  118.89  4953.3  119.53  5005.7  118.29  5013.7  116.47
  5018.5  116.47    5030  119.36  5100.2  121.56  5255.8  123.26  5331.3  126.61
  5446.6  123.75  5499.4     125  5548.1  124.04  5612.2  125.59  5644.2  124.79
  5649.5  125.67  5777.7  122.43  5825.2   123.8  5898.7  123.33  5919.7     125
    6002   124.7  6045.8  127.31  6119.4  128.82  6182.4   129.1  6205.9  127.96
#Mann= 7 ,-1 , 0
  3904.8     .12       0  4415.2      .1       0  4591.5     .12       0
  4823.9      .1       0  4953.3     .07       0    5030      .1       0
  5255.8     .12       0
Bank Sta=4953.3,5030
XS Rating Curve= 0 ,0
Exp/Cntr=0.3,0.1