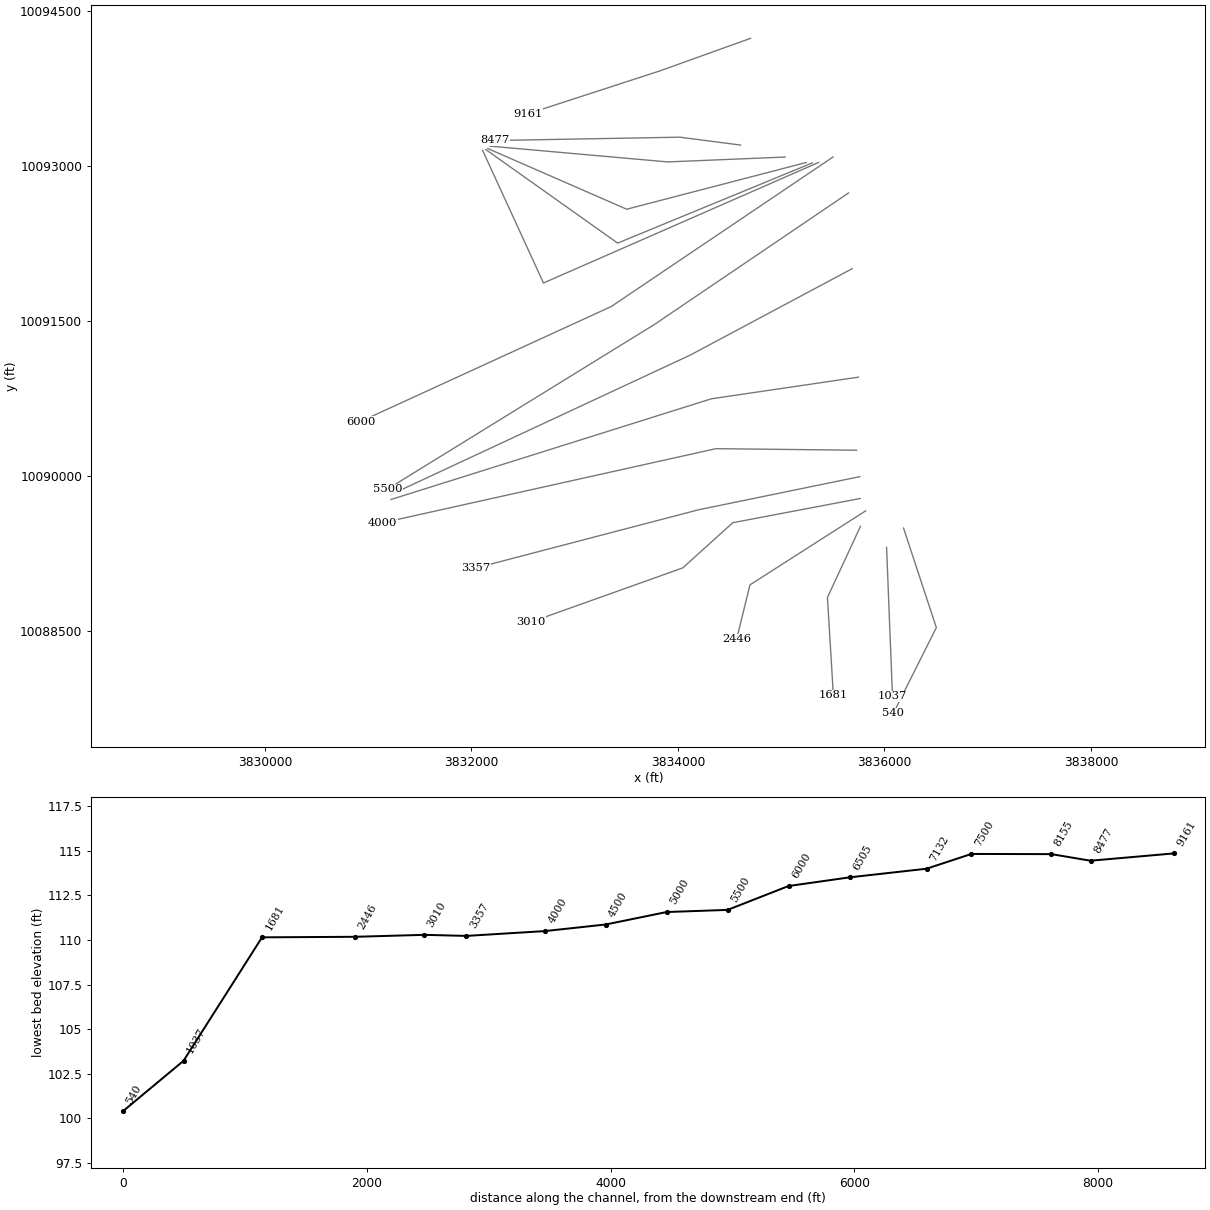
HEC-RAS study SILVERDALE CREEK.prj: SILVERDALE CREEK Base Level Engineering

--- SILVERDALE CREEK.g10 (geometry) --- (continued)

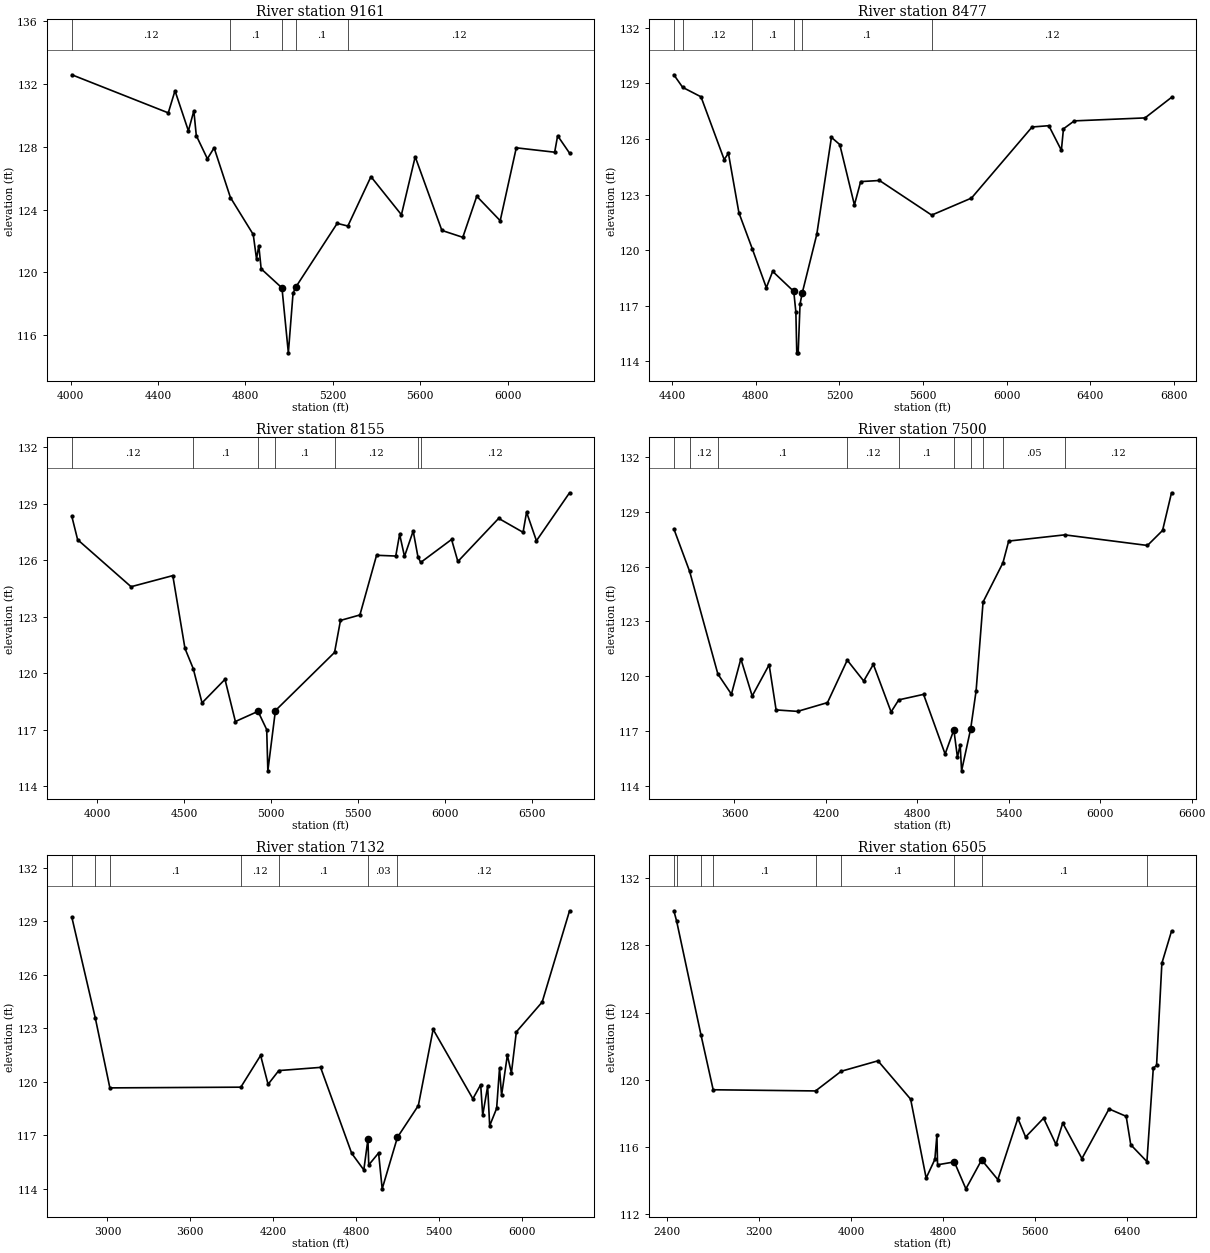
Type RM Length L Ch R = 1 ,9161    ,684,684,684
BEGIN DESCRIPTION:
SILVERDALE CREEK 18.0
END DESCRIPTION:
XS GIS Cut Line= 3
       3834703.4     10094236.95       3833825.8     10093921.85
      3832545.93     10093505.63
#Sta/Elev= 30
  4005.5   132.6  4446.8  130.17  4477.6  131.58    4539  129.02  4563.9   130.3
  4575.1  128.72  4625.9  127.24  4656.7  127.94  4731.3  124.77  4835.8  122.41
  4850.8  120.85  4861.2   121.7    4872  120.22  4967.3     119  4996.5  114.86
    5018  118.66  5030.4  119.05  5220.1  123.12  5268.9  122.95  5374.6   126.1
  5514.1  123.67  5577.2  127.37  5699.3  122.67  5795.1  122.23    5859  124.85
  5966.3  123.29  6039.9  127.94  6215.6  127.66  6229.2  128.71  6283.8   127.6
#Mann= 5 ,-1 , 0
  4005.5     .12       0  4731.3      .1       0  4967.3     .07       0
  5030.4      .1       0  5268.9     .12       0
Bank Sta=4967.3,5030.4
XS Rating Curve= 0 ,0
Exp/Cntr=0.3,0.1

Type RM Length L Ch R = 1 ,8477    ,322,322,322
BEGIN DESCRIPTION:
SILVERDALE CREEK 17.0
END DESCRIPTION:
XS GIS Cut Line= 3
      3834606.76     10093203.36      3834017.38     10093279.75
      3832230.98     10093247.66
#Sta/Elev= 30
  4407.6  129.47    4450  128.79  4537.6  128.28  4648.5  124.89  4668.7  125.23
  4719.1  122.01  4782.9  120.07  4850.2  117.97  4880.4  118.85  4981.3  117.77
  4991.4  116.66  4995.8  114.45  5002.5  114.45  5011.4  117.08  5021.4  117.66
  5091.5  120.85  5161.5  126.09  5201.5   125.7  5271.5  122.44  5301.5   123.7
  5391.5  123.76  5641.2  121.89  5831.6  122.81  6121.6  126.65  6201.6  126.72
  6261.6  125.39  6271.6  126.55  6323.4  126.98  6661.7  127.14  6788.6  128.25
#Mann= 6 ,-1 , 0
  4407.6     .05       0    4450     .12       0  4782.9      .1       0
  4981.3     .07       0  5021.4      .1       0  5641.2     .12       0
Bank Sta=4981.3,5021.4
XS Rating Curve= 0 ,0
Exp/Cntr=0.3,0.1

Type RM Length L Ch R = 1 ,8155    ,655,655,655
BEGIN DESCRIPTION:
SILVERDALE CREEK 16.0
END DESCRIPTION:
XS GIS Cut Line= 3
      3835038.38     10093087.35      3833902.18     10093040.08
      3832181.32      10093192.8
#Sta/Elev= 30
  3853.8  128.33  3886.9   127.1  4194.6   124.6  4434.8  125.19  4504.9  121.32
  4552.4  120.25  4603.1  118.43  4735.1  119.68  4795.1  117.44  4925.3  117.98
  4975.3  117.01  4981.9  114.82  5025.4  118.02  5365.9  121.11    5400  122.81
  5511.8   123.1  5607.7  126.27  5718.2  126.23  5740.4  127.39  5768.4  126.21
  5818.5  127.56  5845.8  126.19  5861.8  125.89  6039.4  127.11  6075.7  125.94
  6310.5  128.23    6451  127.49  6471.1  128.56  6527.9  127.04  6718.6  129.59
#Mann= 7 ,-1 , 0
  3853.8     .12       0  4552.4      .1       0  4925.3     .07       0
  5025.4      .1       0  5365.9     .12       0  5845.8     .05       0
  5861.8     .12       0
Bank Sta=4925.3,5025.4
XS Rating Curve= 0 ,0
Exp/Cntr=0.3,0.1

Type RM Length L Ch R = 1 ,7500    ,368,368,368
BEGIN DESCRIPTION:
SILVERDALE CREEK 15.0
END DESCRIPTION:
XS GIS Cut Line= 3
      3835243.44     10093034.74      3833504.07      10092582.1
      3832158.83     10093169.52
#Sta/Elev= 30
  3202.7  128.06  3306.5  125.73  3491.7  120.12  3580.5  119.02  3642.5  120.95
  3716.8  118.92    3828  120.63  3873.7  118.16  4014.4  118.08  4210.8  118.56
  4340.5  120.88  4448.4  119.74  4511.7  120.65  4628.1  118.05  4678.4  118.71
  4841.1  119.01  4982.4  115.75  5039.9  117.07  5063.4  115.57  5081.3  116.26
  5090.5  114.83  5149.7 117.103  5185.8   119.2  5231.5  124.06  5361.8   126.2
  5399.6  127.39  5767.3  127.73    6310  127.15  6409.1  127.97  6467.9  130.03
#Mann= 10 ,-1 , 0
  3202.7     .05       0  3306.5     .12       0  3491.7      .1       0
  4340.5     .12       0  4678.4      .1       0  5039.9     .03       0
  5149.7      .1       0  5231.5     .12       0  5361.8     .05       0
  5767.3     .12       0
Bank Sta=5039.9,5149.7
XS Rating Curve= 0 ,0
Exp/Cntr=0.3,0.1

Type RM Length L Ch R = 1 ,7132    ,627,627,627
BEGIN DESCRIPTION:
SILVERDALE CREEK 14.0
END DESCRIPTION:
XS GIS Cut Line= 3
      3835302.01     10093030.82      3833416.19     10092253.93
      3832139.32     10093159.72
#Sta/Elev= 30
  2742.6  129.22  2912.9  123.56  3017.9  119.66  3966.5   119.7  4109.8  121.48
  4163.9  119.86  4241.4  120.63  4544.1  120.81  4769.6  115.99  4857.4  115.06
    4887  116.77  4893.1  115.34  4964.4  116.01  4990.4     114    5101  116.89
  5252.4  118.67  5359.4  122.94  5647.3  119.05  5703.9  119.84  5718.6  118.13
  5754.3  119.75  5769.1  117.54  5819.5  118.51  5840.4  120.77  5855.2  119.24
    5897  121.49  5926.5   120.5  5962.2   122.8  6149.2  124.47  6347.7  129.59
#Mann= 7 ,-1 , 0
  2742.6     .05       0  2912.9     .12       0  3017.9      .1       0
  3966.5     .12       0  4241.4      .1       0    4887     .03       0
    5101     .12       0
Bank Sta=4887,5101
XS Rating Curve= 0 ,0
Exp/Cntr=0.3,0.1

Type RM Length L Ch R = 1 ,6505    ,505,505,505
BEGIN DESCRIPTION:
SILVERDALE CREEK 13.0
END DESCRIPTION:
XS GIS Cut Line= 3
      3835361.49     10093034.74      3832697.88     10091867.65
      3832108.05     10093152.77
#Sta/Elev= 30
    2461  130.05  2484.9  129.45  2696.8  122.67  2802.7  119.41  3691.8  119.34
  3914.6  120.51  4233.7  121.13  4517.5  118.85  4652.2  114.16  4727.8  115.27
  4745.7  116.73  4751.2  114.95  4896.9  115.12  4997.4  113.52 5134.24 115.239
  5274.8  114.07  5448.7  117.71  5515.9   116.6  5672.1  117.72    5780  116.16
  5838.6  117.43    6005  115.32  6240.4  118.27  6389.3  117.83  6429.1  116.14
  6569.5  115.14  6624.7  120.69  6653.2  120.86  6699.2  126.93  6783.1  128.84
#Mann= 9 ,-1 , 0
    2461    .075       0  2484.9     .05       0  2696.8     .12       0
  2802.7      .1       0  3691.8     .12       0  3914.6      .1       0
  4896.9     .03       0 5134.24      .1       0  6569.5     .12       0
Bank Sta=4896.9,5134.24
XS Rating Curve= 0 ,0
Exp/Cntr=0.3,0.1

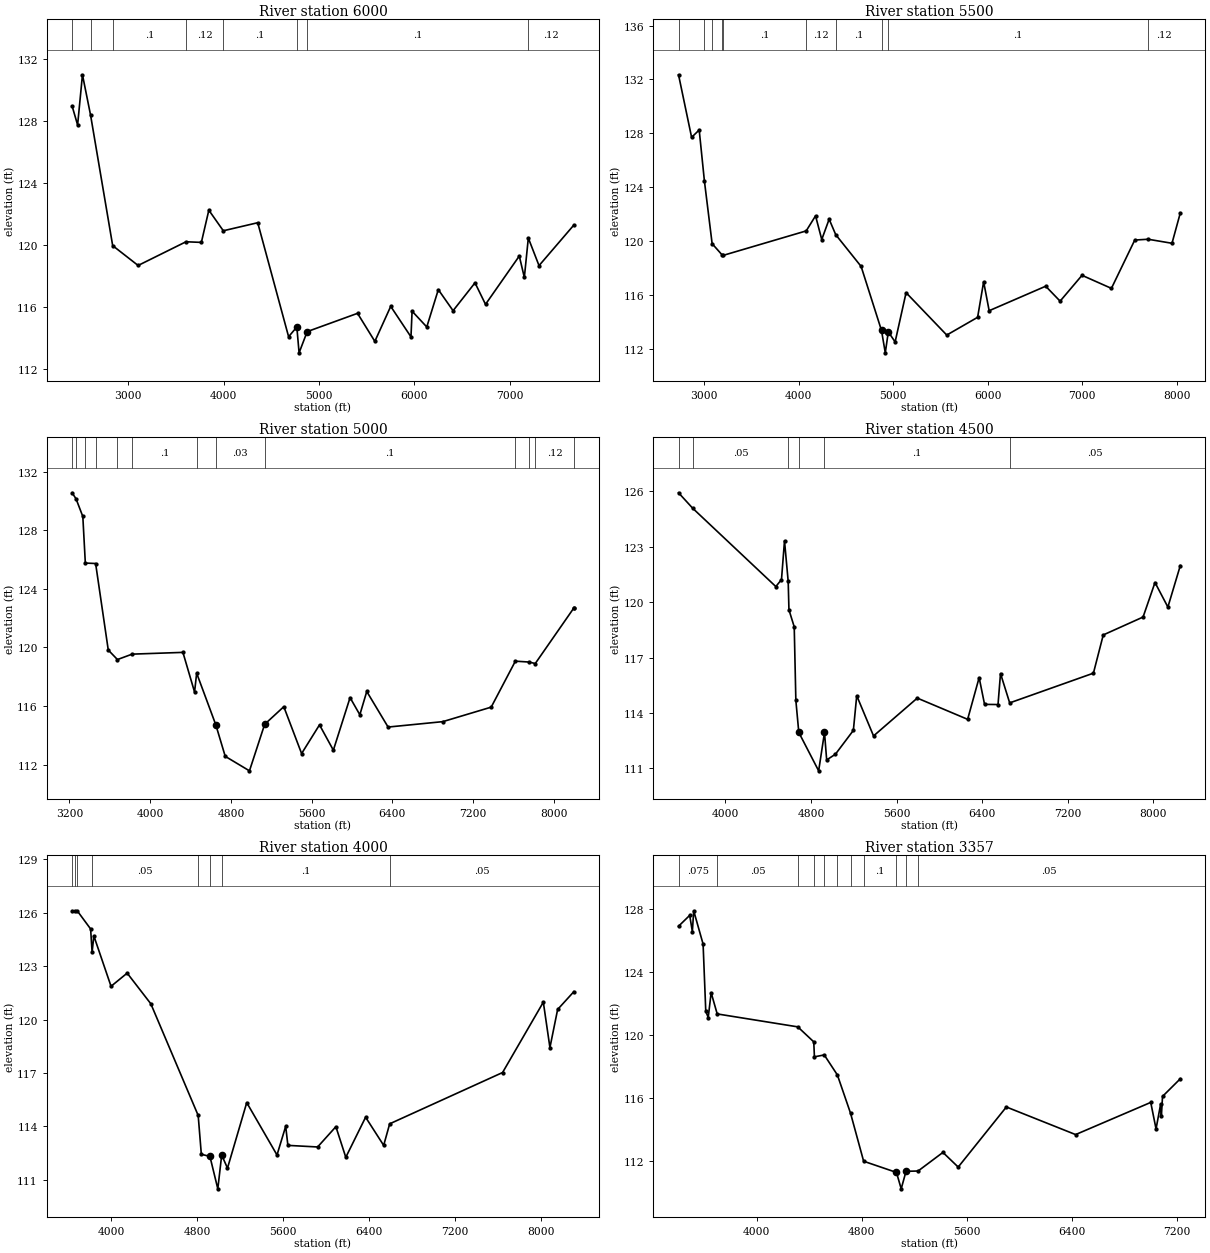
Type RM Length L Ch R = 1 ,6000    ,500,500,500
BEGIN DESCRIPTION:
SILVERDALE CREEK 12.0
END DESCRIPTION:
XS GIS Cut Line= 3
      3835502.11     10093087.77      3833354.95      10091640.1
      3830925.81      10090526.1
#Sta/Elev= 30
  2410.4  128.97  2468.5  127.74  2519.4  130.98  2604.3  128.38  2836.3  119.95
    3103  118.67    3605   120.2  3766.3  120.16  3844.6  122.24  3996.3  120.91
  4357.3  121.43  4681.1  114.07  4767.4   114.7    4791  113.03  4875.9   114.4
  5403.9  115.58  5585.4  113.77  5751.9  116.03  5964.3  114.06  5975.9  115.72
    6130   114.7    6251  117.11  6405.8  115.75  6635.7  117.55    6746  116.16
  7100.2  119.28  7153.1   117.9  7194.9  120.44  7307.1  118.66  7672.4  121.28
#Mann= 8 ,-1 , 0
  2410.4    .075       0  2604.3     .05       0  2836.3      .1       0
    3605     .12       0  3996.3      .1       0  4767.4     .03       0
  4875.9      .1       0  7194.9     .12       0
Bank Sta=4767.4,4875.9
XS Rating Curve= 0 ,0
Exp/Cntr=0.3,0.1

Type RM Length L Ch R = 1 ,5500    ,500,500,500
BEGIN DESCRIPTION:
SILVERDALE CREEK 11.0
END DESCRIPTION:
XS GIS Cut Line= 3
      3835652.39     10092739.64      3833773.14     10091466.33
      3831186.25     10089870.73
#Sta/Elev= 30
    2730  132.35  2868.3   127.7  2948.6  128.25  3003.4  124.48  3085.5   119.8
  3189.2  118.98  3201.6  118.93  4080.9  120.75  4179.7  121.87  4245.4  120.11
  4323.5  121.62  4393.2  120.47  4661.9  118.11  4877.6  113.35  4917.7  111.69
  4949.5  113.25  5021.7   112.5  5137.6  116.16  5568.1  113.01  5894.5  114.33
  5958.3  116.97  6016.6  114.82  6614.8  116.64  6767.4  115.53  6999.2  117.45
  7310.2  116.48  7557.3  120.07  7698.5  120.13  7951.2  119.83  8039.4  122.09
#Mann= 10 ,-1 , 0
    2730    .075       0  3003.4     .05       0  3085.5      .1       0
  3189.2     .05       0  3201.6      .1       0  4080.9     .12       0
  4393.2      .1       0  4877.6     .03       0  4949.5      .1       0
  7698.5     .12       0
Bank Sta=4877.6,4949.5
XS Rating Curve= 0 ,0
Exp/Cntr=0.3,0.1

Type RM Length L Ch R = 1 ,5000    ,500,500,500
BEGIN DESCRIPTION:
SILVERDALE CREEK 10.0
END DESCRIPTION:
XS GIS Cut Line= 3
      3835687.16     10092006.17       3834121.8     10091170.63
      3831221.89     10089819.07
#Sta/Elev= 30
  3225.6  130.56  3264.8  130.15  3332.2  128.94    3357  125.76    3459  125.73
  3584.4  119.82  3675.3  119.17    3821  119.54  4324.4  119.66  4439.8  116.95
  4460.5  118.24  4650.6 114.707  4743.8  112.56  4983.9  111.57 5134.57 114.747
  5324.3  115.95  5500.8  112.75  5678.2  114.71  5815.5  112.98  5981.1  116.57
    6078   115.4  6146.6  116.99    6358  114.56  6900.5  114.93    7380  115.92
  7619.6  119.06  7755.2     119  7816.9   118.9  8199.1  122.69  8199.4   122.7
#Mann= 13 ,-1 , 0
  3225.6    .075       0  3264.8      .1       0    3357    .075       0
    3459     .05       0  3675.3     .12       0    3821      .1       0
  4460.5     .12       0  4650.6     .03       0 5134.57      .1       0
  7619.6     .12       0  7755.2      .1       0  7816.9     .12       0
  8199.1     .05       0
Bank Sta=4650.6,5134.57
XS Rating Curve= 0 ,0
Exp/Cntr=0.3,0.1

Type RM Length L Ch R = 1 ,4500    ,500,500,500
BEGIN DESCRIPTION:
SILVERDALE CREEK 9.0
END DESCRIPTION:
XS GIS Cut Line= 3
      3835747.85     10090955.79      3834324.78     10090746.37
      3831221.91      10089771.2
#Sta/Elev= 30
  3561.6  125.93  3694.3  125.09  4471.3  120.85  4524.1  121.23  4552.2  123.33
  4586.7  121.13  4593.8  119.59  4643.1  118.67  4658.4  114.68  4685.9  112.95
  4871.5  110.87  4926.1  112.95  4946.4  111.46  5028.2  111.77  5195.9  113.06
  5227.4  114.94  5384.6  112.76  5793.4  114.81  6264.1  113.66  6371.8  115.92
  6422.4  114.47  6548.2  114.46  6571.5  116.14  6657.3  114.55  7440.1  116.16
    7532  118.23  7904.2   119.2  8015.7  121.07  8136.2  119.74  8252.5  121.99
#Mann= 6 ,-1 , 0
  3561.6    .075       0  3694.3     .05       0  4586.7     .12       0
  4685.9     .03       0  4926.1      .1       0  6657.3     .05       0
Bank Sta=4685.9,4926.1
XS Rating Curve= 0 ,0
Exp/Cntr=0.3,0.1

Type RM Length L Ch R = 1 ,4000    ,643,643,643
BEGIN DESCRIPTION:
SILVERDALE CREEK 8.0
END DESCRIPTION:
XS GIS Cut Line= 3
      3835730.48     10090248.33      3834367.56     10090263.26
      3831140.49     10089545.65
#Sta/Elev= 30
    3637  126.08  3659.9  126.09  3684.8  126.11  3809.6  125.09  3823.4  123.78
  3839.6   124.7  3999.6  121.87  4149.7  122.61  4369.7  120.89  4810.4  114.62
  4839.7  112.44  4919.7  112.32  4993.1   110.5  5029.2   112.4    5083  111.66
  5262.2  115.34  5543.8   112.4  5624.6  114.01  5645.1  112.94  5921.7  112.85
  6091.7  113.99  6183.9  112.27  6368.2  114.52  6536.3  112.94  6592.2  114.15
  7642.7  117.03  8021.8  120.98  8083.2  118.43  8154.9  120.57  8305.9  121.57
#Mann= 8 ,-1 , 0
    3637    .075       0  3659.9      .1       0  3684.8    .075       0
  3823.4     .05       0  4810.4      .1       0  4919.7     .03       0
  5029.2      .1       0  6592.2     .05       0
Bank Sta=4919.7,5029.2
XS Rating Curve= 0 ,0
Exp/Cntr=0.3,0.1

Type RM Length L Ch R = 1 ,3357    ,347,347,347
BEGIN DESCRIPTION:
SILVERDALE CREEK 7.0
END DESCRIPTION:
XS GIS Cut Line= 3
      3835760.88     10089992.25      3834198.41     10089671.08
      3832046.75     10089108.64
#Sta/Elev= 30
  3405.2  126.88  3490.3  127.57  3510.4  126.54  3520.6  127.86  3592.1  125.75
  3612.5  121.49  3631.2  121.09  3653.3  122.67  3699.5  121.32  4312.7   120.5
  4434.4  119.55  4439.4   118.6  4514.3  118.72  4614.2  117.45  4714.1  115.03
    4814  111.98  5063.9  111.27  5099.9  110.23 5136.67 111.342  5228.3  111.36
  5417.5  112.54  5533.7  111.61  5900.2  115.42  6427.3  113.67  6999.1  115.71
  7039.5  114.03  7074.8  115.62    7080  114.82  7088.8  116.09  7224.3  117.21
#Mann= 11 ,-1 , 0
  3405.2    .075       0  3699.5     .05       0  4312.7     .12       0
  4434.4     .05       0  4514.3     .12       0  4614.2     .05       0
  4714.1     .12       0    4814      .1       0  5063.9     .03       0
 5136.67      .1       0  5228.3     .05       0
Bank Sta=5063.9,5136.67
XS Rating Curve= 0 ,0
Exp/Cntr=0.3,0.1

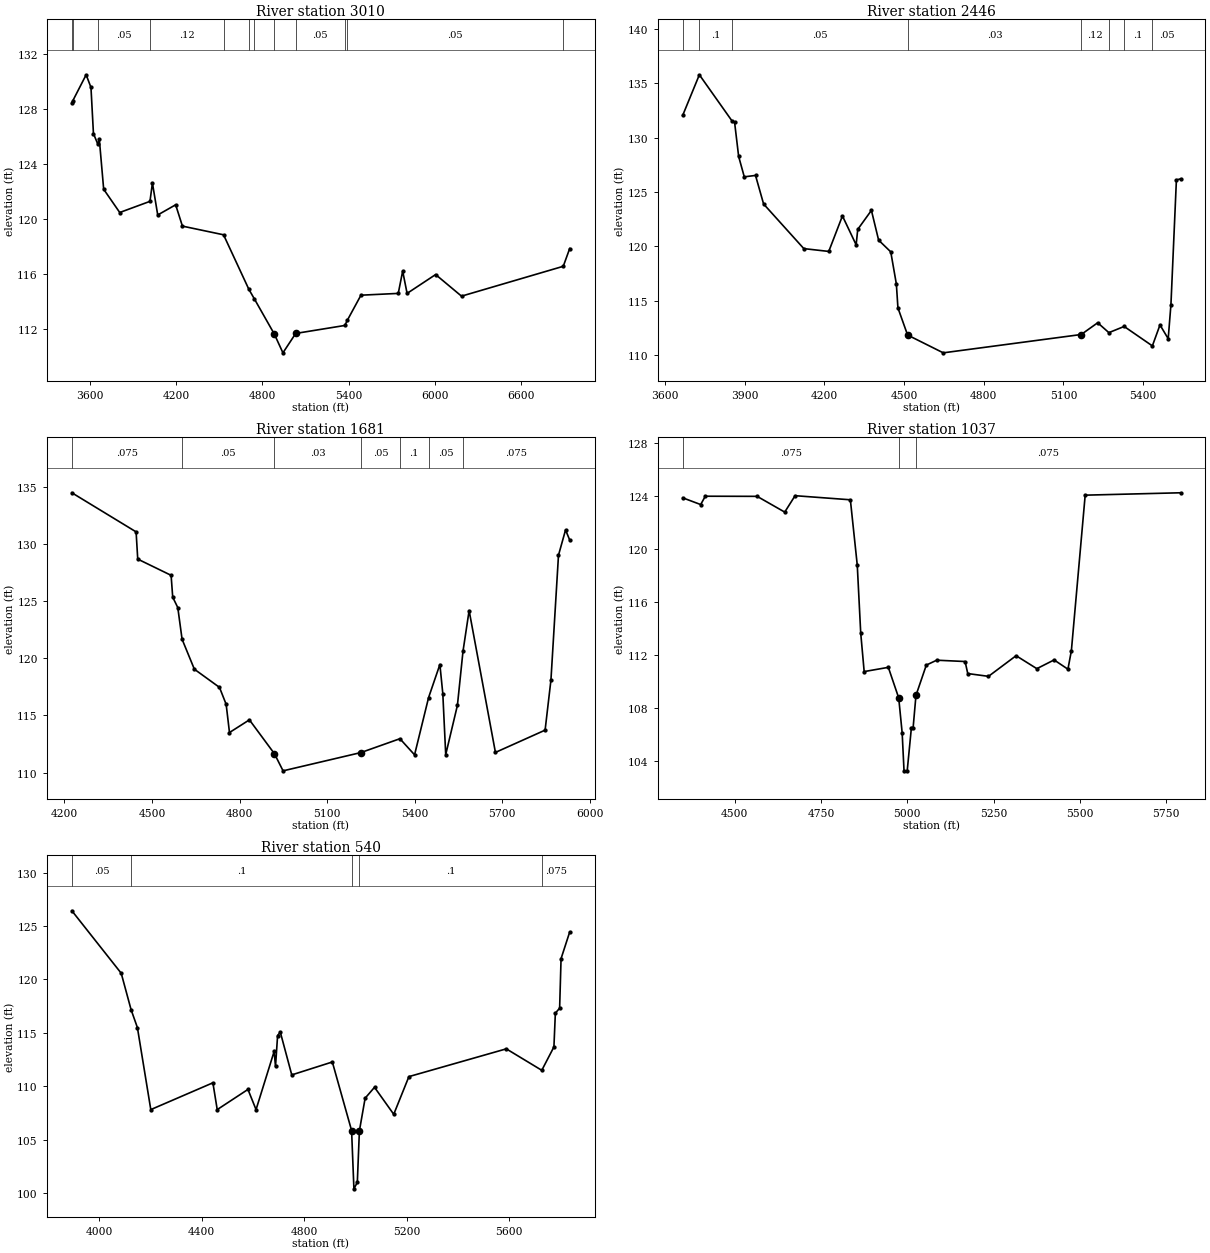
Type RM Length L Ch R = 1 ,3010    ,564,564,564
BEGIN DESCRIPTION:
SILVERDALE CREEK 6.0
END DESCRIPTION:
XS GIS Cut Line= 4
      3835765.55     10089780.53      3834531.16     10089546.15
      3834046.79     10089108.65      3832578.03     10088584.56
#Sta/Elev= 30
    3472  128.44  3478.4  128.61  3571.4   130.5  3605.1  129.58  3622.3  126.23
  3653.4  125.44    3663  125.84  3693.6  122.18  3805.5  120.49  4016.1   121.3
  4033.3  122.63  4070.2  120.31  4195.1  121.05  4242.3   119.5  4528.8  118.87
  4705.5   114.9  4743.6  114.21  4882.8  111.65  4942.6  110.29  5031.5   111.7
    5374  112.28    5392  112.67  5486.2  114.48  5746.1  114.61  5776.9  116.23
  5807.7  114.61  6006.4  115.98  6186.9  114.41  6895.8  116.58  6940.6  117.87
#Mann= 12 ,-1 , 0
    3472    .075       0  3478.4      .1       0  3653.4     .05       0
  4016.1     .12       0  4528.8     .05       0  4705.5     .12       0
  4743.6     .05       0  4882.8     .03       0  5031.5     .05       0
    5374      .1       0    5392     .05       0  6895.8      .1       0
Bank Sta=4882.8,5031.5
XS Rating Curve= 0 ,0
Exp/Cntr=0.3,0.1

Type RM Length L Ch R = 1 ,2446    ,765,765,765
BEGIN DESCRIPTION:
SILVERDALE CREEK 5.0
END DESCRIPTION:
XS GIS Cut Line= 3
      3835817.89      10089661.1      3834697.83     10088944.59
      3834567.64     10088416.02
#Sta/Elev= 30
  3666.9  132.05  3729.6  135.79  3852.2  131.55  3862.3   131.4  3877.5  128.27
  3898.7  126.39    3941  126.52  3971.4  123.89  4122.8  119.78  4216.7  119.52
  4268.2  122.79  4319.8  120.13  4325.8  121.55  4377.3   123.3  4404.4  120.56
  4450.1  119.48  4471.2  116.52  4477.1  114.32  4513.5  111.82  4647.7  110.18
 5167.06 111.869  5229.1  112.95  5271.2  112.04  5328.7  112.61  5434.9  110.82
  5463.6  112.75  5494.5  111.48  5504.8  114.62  5525.4  126.11  5540.9   126.2
#Mann= 8 ,-1 , 0
  3666.9    .075       0  3729.6      .1       0  3852.2     .05       0
  4513.5     .03       0 5167.06     .12       0  5271.2     .05       0
  5328.7      .1       0  5434.9     .05       0
Bank Sta=4513.5,5167.06
XS Rating Curve= 0 ,0
Exp/Cntr=0.3,0.1

Type RM Length L Ch R = 1 ,1681    ,644,644,644
BEGIN DESCRIPTION:
SILVERDALE CREEK 4.0
END DESCRIPTION:
XS GIS Cut Line= 3
      3835767.85     10089511.06      3835447.83     10088822.19
      3835505.12      10087876.9
#Sta/Elev= 30
  4225.3  134.47  4445.5  131.05  4451.1  128.67  4565.5  127.25    4571  125.34
  4588.4  124.43  4603.1  121.66  4645.2  119.04  4731.3  117.45  4754.2  115.97
  4765.6   113.5  4833.9  114.61  4919.9  111.64  4949.3  110.15  5216.4  111.75
  5349.9  112.96  5400.1  111.55  5448.2  116.56  5486.9  119.45  5496.9  116.91
  5506.9  111.57    5547  115.88  5566.1   120.6  5587.1  124.17  5677.3  111.76
  5847.6  113.71  5867.6  118.09  5893.5  129.01  5917.7  131.22  5931.9  130.34
#Mann= 7 ,-1 , 0
  4225.3    .075       0  4603.1     .05       0  4919.9     .03       0
  5216.4     .05       0  5349.9      .1       0  5448.2     .05       0
  5566.1    .075       0
Bank Sta=4919.9,5216.4
XS Rating Curve= 0 ,0
Exp/Cntr=0.3,0.1

Type RM Length L Ch R = 1 ,1037    ,497,497,497
BEGIN DESCRIPTION:
SILVERDALE CREEK 2.0
END DESCRIPTION:
XS GIS Cut Line= 3
      3836020.75     10089306.56      3836046.79      10088642.5
      3836077.99     10087864.99
#Sta/Elev= 30
  4348.9  123.85    4401  123.34  4414.4  123.97  4564.6  123.96  4644.6  122.77
  4674.6  124.01  4834.8   123.7  4854.8  118.76  4864.8  113.63  4874.8  110.72
  4944.8  111.04  4974.9  108.73  4984.9  106.09  4990.3  103.22  4999.5  103.22
  5011.7  106.49  5016.7  106.49  5024.9  108.92  5054.9  111.21    5085  111.58
  5167.3  111.48    5175  110.57  5235.1  110.36  5315.1  111.92  5375.2  110.94
  5425.2   111.6  5465.3   110.9  5475.3   112.3  5515.3  124.05  5791.6  124.23
#Mann= 3 , 0 , 0
  4348.9    .075       0  4974.9     .07       0  5024.9    .075       0
Bank Sta=4974.9,5024.9
XS Rating Curve= 0 ,0
Exp/Cntr=0.3,0.1

Type RM Length L Ch R = 1 ,540     ,0,0,0
BEGIN DESCRIPTION:
SILVERDALE CREEK 1.0
END DESCRIPTION:
XS GIS Cut Line= 3
       3836184.8      10089494.1      3836502.52     10088530.52
      3836085.84     10087699.77
#Sta/Elev= 30
  3892.8  126.43  4085.5  120.58    4124  117.17  4148.7  115.49    4201  107.81
  4443.5  110.32  4460.4  107.81  4580.4   109.7    4612  107.81  4682.7  113.26
    4688  111.85  4696.2  114.75  4706.8  115.06  4751.5  111.06  4909.9  112.27
  4985.1  105.85  4994.2  100.39  5007.5     101  5015.6  105.82    5038  108.88
  5074.6   109.9  5149.7  107.37  5208.9   110.9  5589.2   113.5  5727.8  111.49
  5775.2  113.68  5780.8  116.84  5797.5  117.31  5803.1  121.95  5836.8  124.44
#Mann= 5 ,-1 , 0
  3892.8     .05       0    4124      .1       0  4985.1     .07       0
  5015.6      .1       0  5727.8    .075       0
Bank Sta=4985.1,5015.6
XS Rating Curve= 0 ,0
Exp/Cntr=0.3,0.1