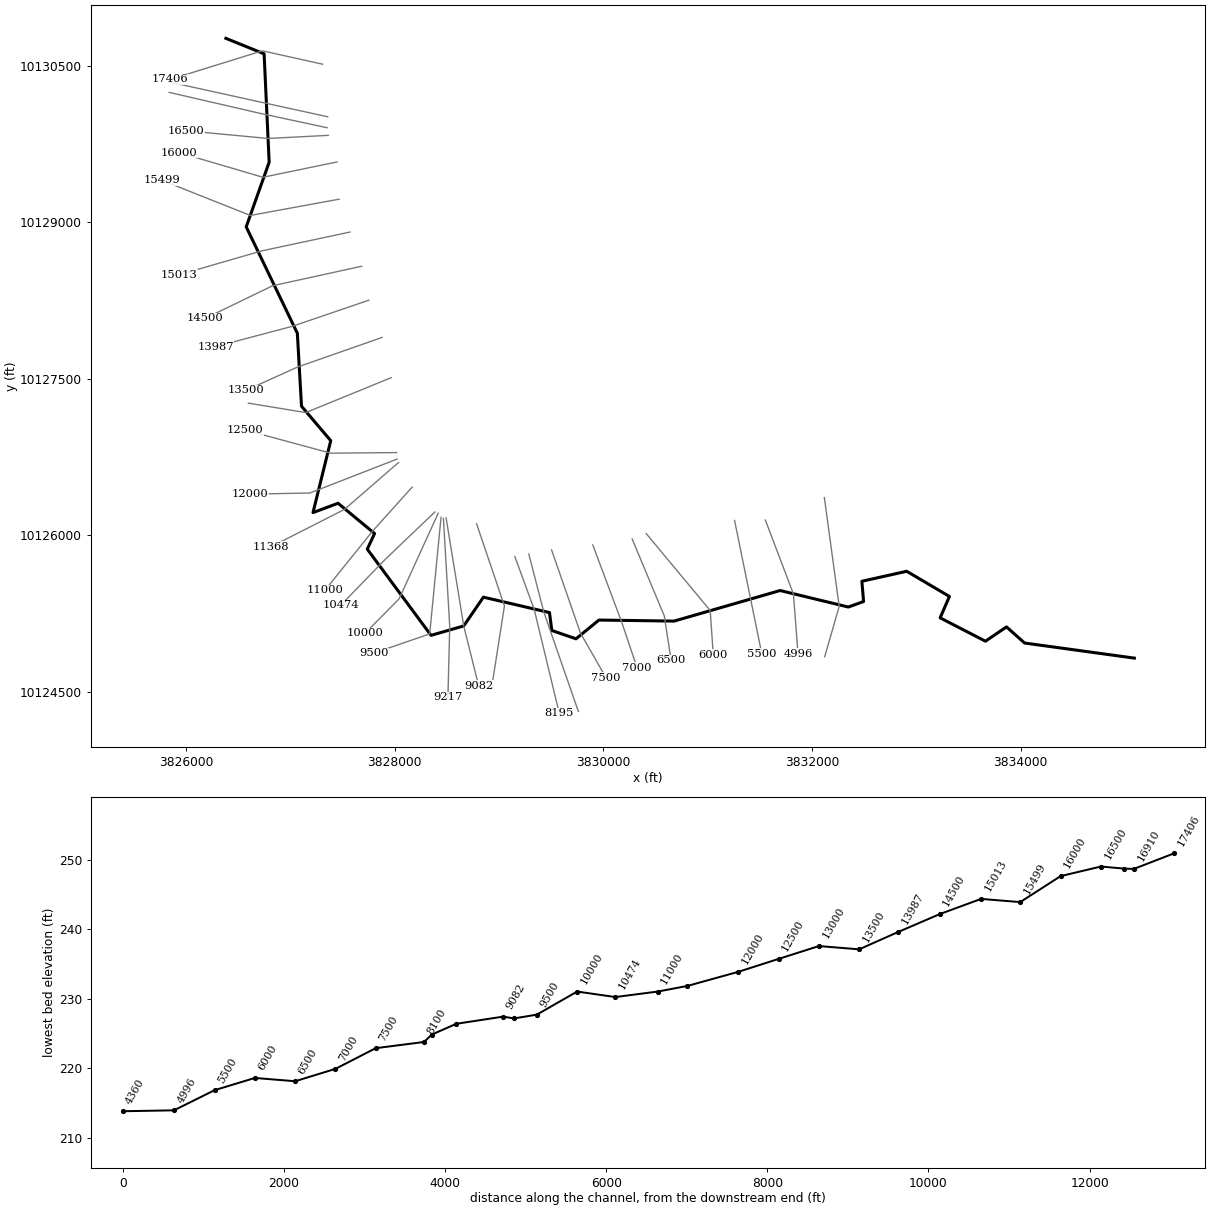
--- STEWARTS CREEK TRIBUTARY NO 1.prj (project) ---

Proj Title=STEWARTS CREEK TRIBUTARY NO 1 Base Level Engineering
Current Plan=p01
Default Exp/Contr=0.3,0.1
English Units
Geom File=g01
Flow File=f01
Plan File=p01
Y Axis Title=Elevation
X Axis Title(PF)=Main Channel Distance
X Axis Title(XS)=Station
BEGIN DESCRIPTION:
STEWARTS CREEK TRIBUTARY NO 1
END DESCRIPTION:
DSS Export Rating Curves= 0
DSS Export Rating Curve Sorted= 0
DSS Export Volume Flow Curves= 0
DXF OffsetX= 0
DXF OffsetY= 0
DXF ScaleX= 1
DXF ScaleY= 10

--- STEWARTS CREEK TRIBUTARY NO 1.p01 (plan) ---

Plan Title=Multiple Run
Short Identifier=Multiple
Geom File=g01
Flow File=f01
Subcritical Flow
K Sum by GR= 0
Std Step Tol= 0.01
Critical Tol= 0.01
Num of Std Step Trials= 20
Max Error Tol= 0.3
Flow Tol Ratio= 0.001
Split Flow NTrial= 30
Split Flow Tol= 0.02
Split Flow Ratio= 0.02
Log Output Level= 0
Friction Slope Method= 1
Unsteady Friction Slope Method= 2
Unsteady Bridges Friction Slope Method= 1
Parabolic Critical Depth
Global Vel Dist=  1 , 1 , 1
Global Log Level= 0
CheckData=True
Encroach Param= -1, 0, 0, 0
BEGIN DESCRIPTION:
Multiple Run
END DESCRIPTION:

--- STEWARTS CREEK TRIBUTARY NO 1.f01 (steady flow) ---

Flow Title=Multiple
Program Version=4.10
Number of Profiles= 7
Profile Names=10-year,25-year,50-year,1pct_min,100-year,1pct_plu,500-year
River Rch & RM=STEWARTS CREEK T,Reach-1         ,17406
     632     845    1130     498    1503    4539    2743
River Rch & RM=STEWARTS CREEK T,Reach-1         ,13000
     982    1339    1818     810    2445    7384    4575
River Rch & RM=STEWARTS CREEK T,Reach-1         ,2668
     936    1267    1710     757    2287    6907    4229
Boundary for River Rch & Prof#=STEWARTS CREEK T,Reach-1         , 1
Up Type= 0
Dn Type= 3
Dn Slope=0.009
Boundary for River Rch & Prof#=STEWARTS CREEK T,Reach-1         , 2
Up Type= 0
Dn Type= 3
Dn Slope=0.009
Boundary for River Rch & Prof#=STEWARTS CREEK T,Reach-1         , 3
Up Type= 0
Dn Type= 3
Dn Slope=0.009
Boundary for River Rch & Prof#=STEWARTS CREEK T,Reach-1         , 4
Up Type= 0
Dn Type= 3
Dn Slope=0.009
Boundary for River Rch & Prof#=STEWARTS CREEK T,Reach-1         , 5
Up Type= 0
Dn Type= 3
Dn Slope=0.009
Boundary for River Rch & Prof#=STEWARTS CREEK T,Reach-1         , 6
Up Type= 0
Dn Type= 3
Dn Slope=0.009
Boundary for River Rch & Prof#=STEWARTS CREEK T,Reach-1         , 7
Up Type= 0
Dn Type= 3
Dn Slope=0.009
DSS Import GetInterval= 0
DSS Import GetPeak= 0
DSS Import FillOption= 0

--- STEWARTS CREEK TRIBUTARY NO 1.g01 (geometry) ---

Geom Title=Existing Conditions
Program Version=4.10

River Reach=STEWARTS CREEK T,Reach-1
Reach XY= 30
       3826383.4     10130764.62      3826749.72     10130616.18
      3826798.24     10129576.86      3826578.24     10128956.86
      3827068.24     10127936.86      3827108.24     10127236.86
      3827388.24     10126906.86      3827218.24     10126216.86
      3827458.24     10126306.86      3827808.24     10126016.86
      3827738.24     10125866.86      3828349.19     10125040.11
      3828662.68     10125130.54      3828851.08     10125406.35
      3829484.09     10125258.65       3829506.7     10125086.83
      3829738.24     10125006.86      3829958.24     10125186.86
      3830678.24     10125176.86      3831694.26     10125470.06
      3832347.88     10125311.69      3832493.84     10125364.61
      3832477.47     10125558.69      3832907.15     10125654.54
      3833316.31     10125413.03      3833227.41     10125207.93
      3833661.57     10124984.06      3833863.23     10125121.19
      3834036.63     10124966.54       3835088.3     10124821.85

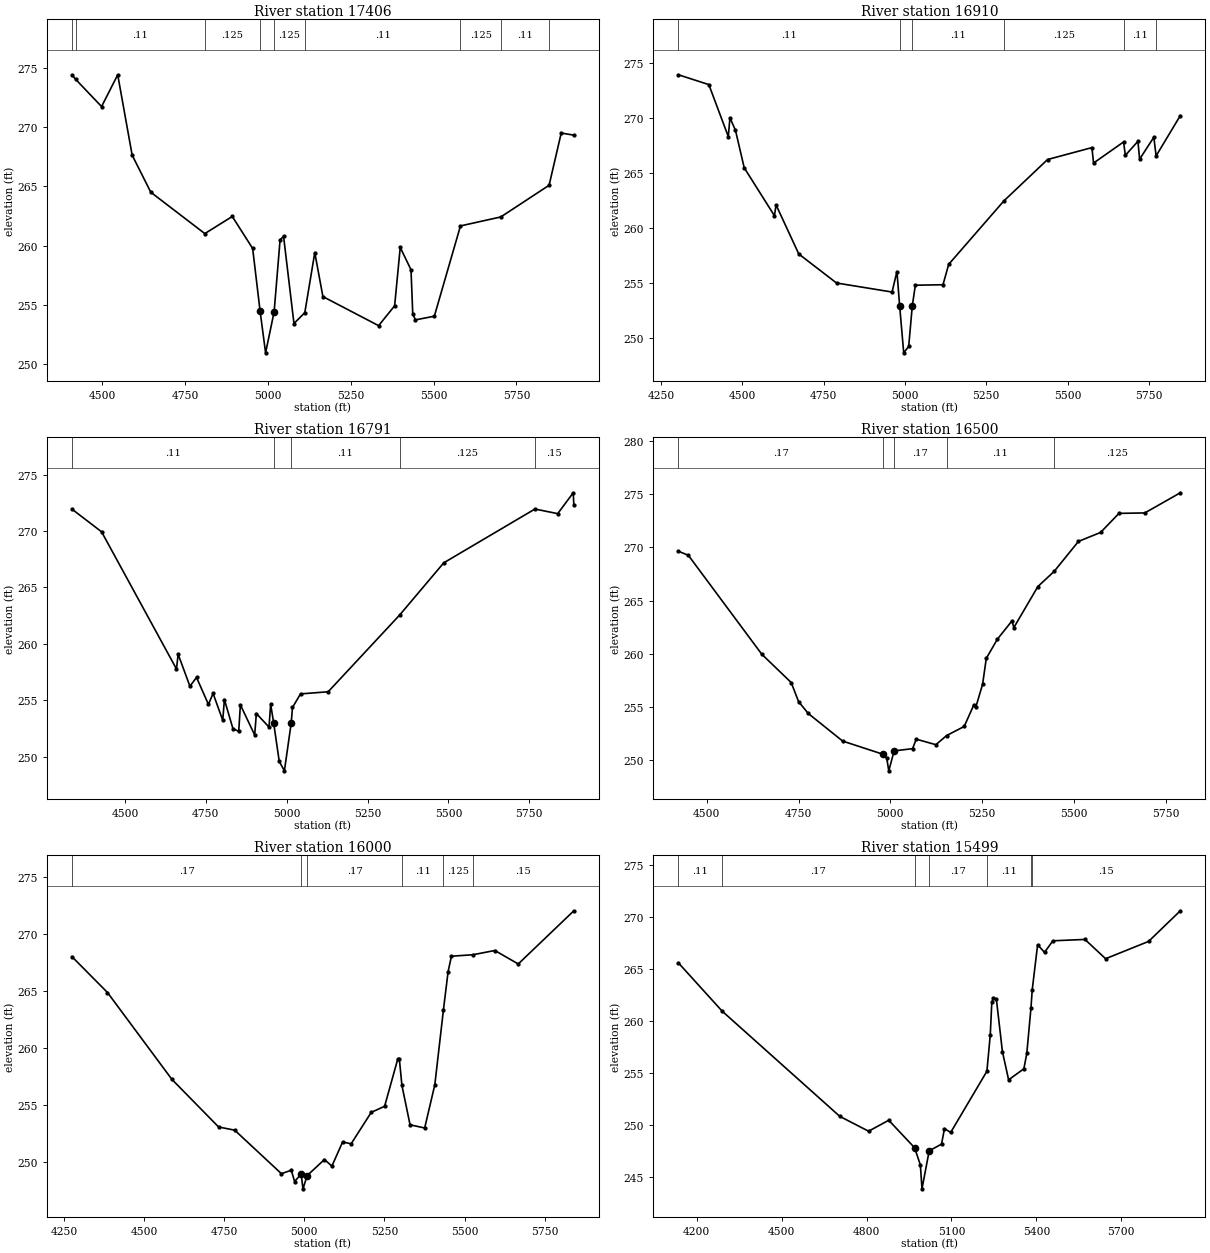
Type RM Length L Ch R = 1 ,17406   ,496,496,496
BEGIN DESCRIPTION:
STEWARTS CREEK TRIBUTARY NO 1 33.0
END DESCRIPTION:
XS GIS Cut Line= 3
      3827310.07     10130516.67      3826733.23     10130644.83
      3825851.43     10130371.14
#Sta/Elev= 30
  4409.1  274.45  4420.1  274.07  4498.5  271.76  4547.2  274.45  4590.7  267.65
    4647  264.51    4810  261.01  4892.8  262.46  4954.3  259.75 4976.78254.4323
  4993.3  250.92 5019.02254.3849    5037  260.47  5047.5  260.79  5078.9   253.4
  5111.6  254.32  5141.7   259.4  5166.2  255.68  5334.3  253.22  5382.6   254.9
  5399.5  259.84    5432  257.95  5437.3  254.21  5445.4  253.71  5502.4  254.02
  5581.2  261.66    5703  262.42  5848.6   265.1  5885.2  269.52  5923.3  269.34
#Mann= 9 ,-1 , 0
  4409.1    .125       0  4420.1     .11       0    4810    .125       0
 4976.78     .09       0 5019.02    .125       0  5111.6     .11       0
  5581.2    .125       0    5703     .11       0  5848.6    .125       0
Bank Sta=4976.78,5019.02
XS Rating Curve= 0 ,0
Exp/Cntr=0.3,0.1

Type RM Length L Ch R = 1 ,16910   ,119,119,119
BEGIN DESCRIPTION:
STEWARTS CREEK TRIBUTARY NO 1 32.0
END DESCRIPTION:
XS GIS Cut Line= 3
      3827359.23     10130012.59      3826679.41     10130161.32
      3825852.63     10130343.43
#Sta/Elev= 30
  4304.1  273.89  4397.6     273  4457.4  268.29  4462.5     270  4479.5  268.85
  4506.3  265.46  4599.2  261.12  4604.3  262.09    4674  257.65    4790  255.02
  4960.7   254.2  4975.7  256.06    4984252.9528  4996.5  248.69  5011.8  249.27
  5022.9252.9566  5032.3  254.82  5117.2  254.86  5134.7  256.71  5304.4  262.46
  5438.6  266.21  5574.9  267.29    5580  265.89  5672.1   267.8  5677.7  266.59
  5716.3  267.86  5721.5  266.24  5765.2  268.23  5772.2  266.54  5846.6  270.19
#Mann= 6 ,-1 , 0
  4304.1     .11       0    4984     .09       0  5022.9     .11       0
  5304.4    .125       0  5672.1     .11       0  5772.2    .125       0
Bank Sta=4984,5022.9
XS Rating Curve= 0 ,0
Exp/Cntr=0.3,0.1

Type RM Length L Ch R = 1 ,16791   ,291,291,291
BEGIN DESCRIPTION:
STEWARTS CREEK TRIBUTARY NO 1 31.5
END DESCRIPTION:
XS GIS Cut Line= 3
       3827354.4     10129907.28       3826705.2      10130046.7
      3825840.36     10130246.42
#Sta/Elev= 30
    4336  271.93  4427.6  269.92  4659.1  257.76  4664.3  259.06  4700.7  256.23
  4721.1  257.01  4757.9  254.62  4772.3  255.59  4802.2  253.21  4807.3  255.05
  4833.6  252.48  4851.6  252.23  4856.7  254.58  4900.9  251.91  4906.1  253.81
  4945.2  252.61  4950.3  254.63 4959.48252.9908  4976.8  249.57  4992.8  248.73
 5013.75252.9581  5017.8  254.35  5042.6  255.55  5128.1  255.74  5349.3  262.55
  5485.4  267.17  5767.3  271.94  5837.7  271.53  5885.6  273.38  5887.6   272.3
#Mann= 5 ,-1 , 0
    4336     .11       0 4959.48     .09       0 5013.75     .11       0
  5349.3    .125       0  5767.3     .15       0
Bank Sta=4959.48,5013.75
XS Rating Curve= 0 ,0
Exp/Cntr=0.3,0.1

Type RM Length L Ch R = 1 ,16500   ,500,500,500
BEGIN DESCRIPTION:
STEWARTS CREEK TRIBUTARY NO 1 31.0
END DESCRIPTION:
XS GIS Cut Line= 3
      3827364.77     10129834.37      3826788.24     10129804.61
       3826001.5     10129878.52
#Sta/Elev= 30
  4422.7  269.62  4449.7  269.24  4649.9  259.96    4730  257.31  4750.1  255.52
  4776.4  254.41  4870.2  251.82  4980.4  250.58  4990.4  250.21  4995.9  249.03
  5010.4   250.9  5060.7  251.11  5070.7     252  5124.2  251.48  5153.5  252.34
  5201.3  253.19  5227.9  255.24  5232.9  254.99  5251.5  257.15  5261.5  259.57
  5291.7  261.37  5331.6  263.09  5336.6  262.46  5402.1  266.31  5446.5  267.73
  5512.6  270.54  5572.9  271.38  5623.1  273.17  5693.4  273.21  5790.2   275.1
#Mann= 5 ,-1 , 0
  4422.7     .17       0  4980.4     .06       0  5010.4     .17       0
  5153.5     .11       0  5446.5    .125       0
Bank Sta=4980.4,5010.4
XS Rating Curve= 0 ,0
Exp/Cntr=0.3,0.1

Type RM Length L Ch R = 1 ,16000   ,501,501,501
BEGIN DESCRIPTION:
STEWARTS CREEK TRIBUTARY NO 1 30.0
END DESCRIPTION:
XS GIS Cut Line= 3
      3827448.06     10129579.16      3826738.24      10129432.6
       3825931.4     10129669.86
#Sta/Elev= 30
  4275.2  267.99    4386  264.85    4587  257.24  4732.7  253.07  4782.9  252.79
  4928.6  248.98  4959.5  249.28  4969.8  248.29  4990.2  248.95  4995.9  247.65
    5009  248.81  5062.9  250.22  5086.1  249.64  5119.5  251.75  5146.3   251.6
  5208.9  254.35  5250.6  254.88  5291.5  259.01  5296.7  258.99  5304.6  256.71
    5330  253.26  5375.6  252.98  5407.2  256.76  5434.2  263.35  5448.6  266.66
    5459  268.03  5526.4  268.16  5594.5  268.53  5667.5  267.35    5841  272.01
#Mann= 6 ,-1 , 0
  4275.2     .17       0  4990.2     .06       0    5009     .17       0
  5304.6     .11       0  5434.2    .125       0  5526.4     .15       0
Bank Sta=4990.2,5009
XS Rating Curve= 0 ,0
Exp/Cntr=0.3,0.1

Type RM Length L Ch R = 1 ,15499   ,486,486,486
BEGIN DESCRIPTION:
STEWARTS CREEK TRIBUTARY NO 1 29.0
END DESCRIPTION:
XS GIS Cut Line= 3
      3827468.94      10129222.4      3826618.24     10129066.36
      3825773.61     10129402.09
#Sta/Elev= 30
  4135.1  265.59  4289.7  260.96  4705.6  250.86  4807.2  249.44  4878.4  250.49
  4969.9  247.85  4990.2   246.2  4995.9  243.91  5021.4  247.56    5065   248.2
  5075.4  249.69  5097.3  249.32  5225.3  255.19  5237.2  258.67  5242.7  261.81
  5248.1   262.2  5258.7  262.14  5280.2  257.07  5302.1  254.37    5356  255.43
  5366.3   256.9  5381.1  261.28  5385.5  263.01  5404.6  267.33  5428.9   266.6
  5458.6  267.71  5571.9  267.84  5644.8  265.99  5796.7  267.65  5908.9  270.59
#Mann= 7 ,-1 , 0
  4135.1     .11       0  4289.7     .17       0  4969.9     .09       0
  5021.4     .17       0  5225.3     .11       0  5381.1    .125       0
  5385.5     .15       0
Bank Sta=4969.9,5021.4
XS Rating Curve= 0 ,0
Exp/Cntr=0.3,0.1

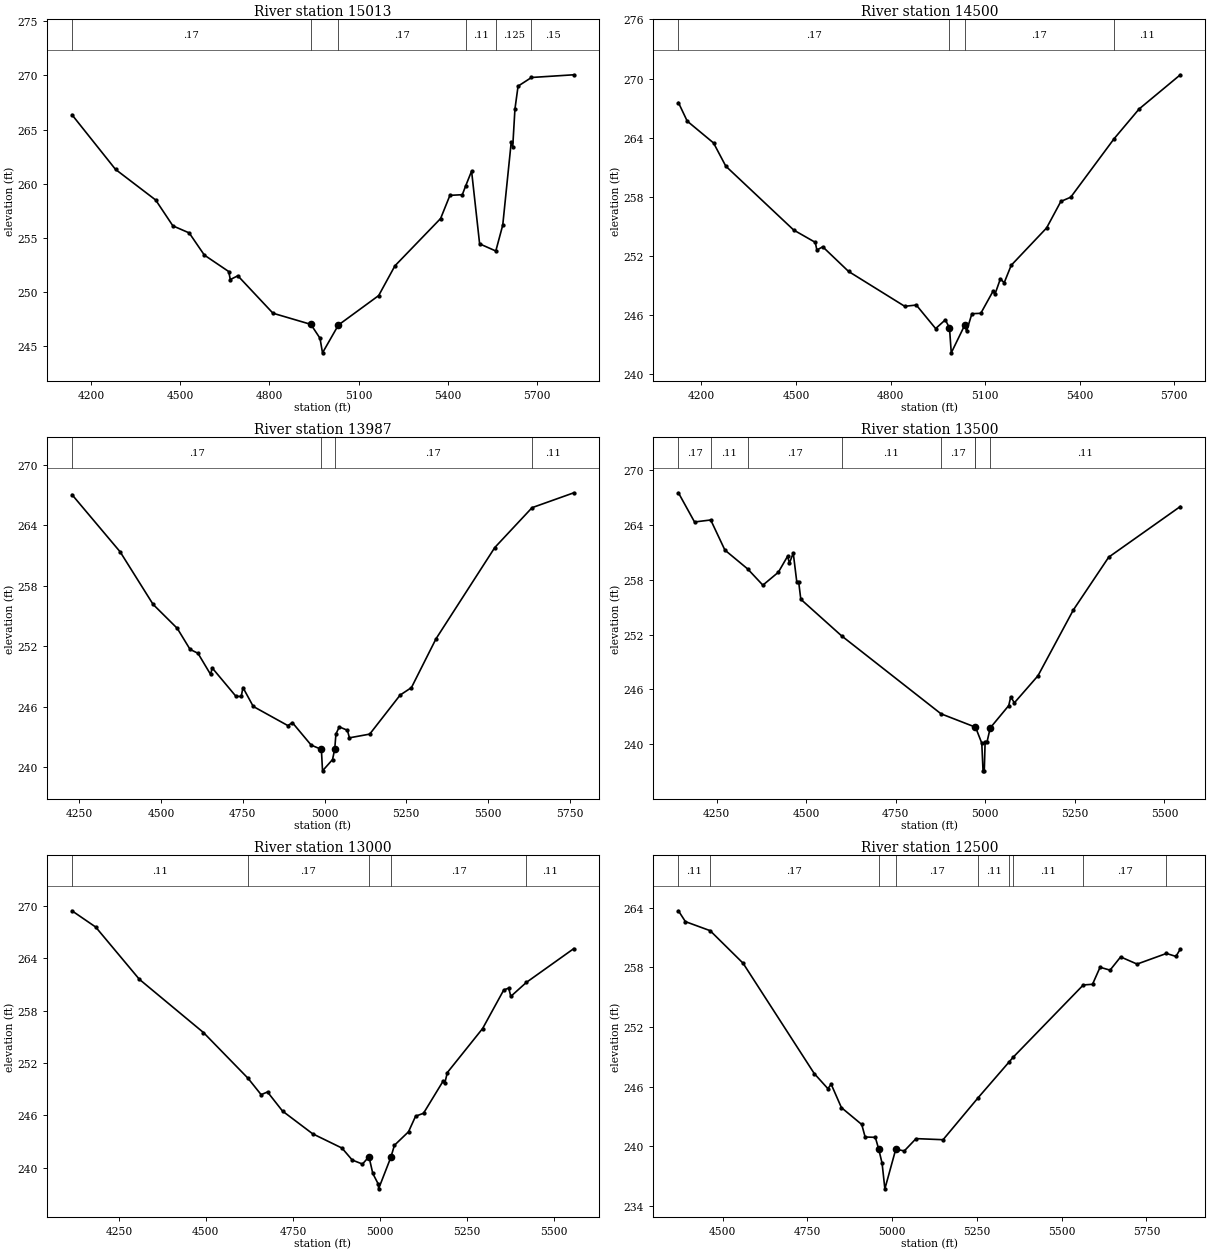
Type RM Length L Ch R = 1 ,15013   ,513,513,513
BEGIN DESCRIPTION:
STEWARTS CREEK TRIBUTARY NO 1 28.0
END DESCRIPTION:
XS GIS Cut Line= 3
      3827573.09     10128907.29      3826728.24     10128726.86
      3825937.68     10128498.43
#Sta/Elev= 30
  4136.1  266.37  4282.5  261.32  4417.5  258.49  4475.4   256.1  4530.1  255.45
  4581.1   253.4    4663  251.88  4668.3  251.14  4693.6  251.49  4811.7  248.03
    4939     247  4969.7  245.72  4978.2  244.37  5031.6  246.94  5166.9  249.66
  5221.6  252.41  5375.1  256.78  5406.4  258.92    5448  258.98    5459  259.77
  5479.2  261.16  5506.2  254.44  5560.6  253.78  5583.9  256.17  5612.3  263.81
  5617.5  263.42  5624.9  266.89  5635.4  269.01  5680.5  269.81  5822.9  270.06
#Mann= 6 ,-1 , 0
  4136.1     .17       0    4939     .09       0  5031.6     .17       0
    5459     .11       0  5560.6    .125       0  5680.5     .15       0
Bank Sta=4939,5031.6
XS Rating Curve= 0 ,0
Exp/Cntr=0.3,0.1

Type RM Length L Ch R = 1 ,14500   ,513,513,513
BEGIN DESCRIPTION:
STEWARTS CREEK TRIBUTARY NO 1 27.0
END DESCRIPTION:
XS GIS Cut Line= 3
      3827685.07     10128579.16      3826832.29     10128392.81
      3826185.08     10128079.17
#Sta/Elev= 30
  4127.1  267.57    4155  265.69  4238.6  263.47  4277.4  261.12  4492.7  254.64
  4561.2  253.39  4566.3  252.61  4584.9  252.94  4666.8  250.44    4845   246.9
  4881.7  247.03  4943.1  244.64  4973.8  245.53    4987   244.7  4992.6  242.18
  5035.5     245  5041.1  244.38  5058.1  246.15  5086.3  246.19  5125.9  248.48
  5131.4  248.14  5148.4  249.69  5160.5  249.29  5182.7  251.06    5295  254.85
  5340.2  257.54  5371.6  257.97  5509.3  263.91  5588.5  266.92  5719.2  270.39
#Mann= 4 ,-1 , 0
  4127.1     .17       0    4987     .09       0  5035.5     .17       0
  5509.3     .11       0
Bank Sta=4987,5035.5
XS Rating Curve= 0 ,0
Exp/Cntr=0.3,0.1

Type RM Length L Ch R = 1 ,13987   ,487,487,487
BEGIN DESCRIPTION:
STEWARTS CREEK TRIBUTARY NO 1 26.0
END DESCRIPTION:
XS GIS Cut Line= 3
      3827752.77     10128253.64      3827021.41     10128003.69
      3826284.05     10127808.33
#Sta/Elev= 30
  4227.1  267.07  4374.6  261.38  4475.4  256.16  4549.3  253.78  4588.5  251.69
  4612.7   251.3  4651.1  249.21  4656.4  249.84    4729  247.02  4745.1  247.01
  4750.3   247.9  4781.8  246.02  4887.5  244.12  4901.6  244.41    4959  242.18
  4990.3  241.75  4993.8  239.62  5024.4  240.74 5031.13241.7767  5034.8  243.28
  5045.1  243.99  5069.9  243.65  5076.1   242.9  5138.2  243.27  5231.3  247.15
  5265.8  247.89    5341  252.74  5520.9  261.81  5634.9  265.77  5762.8  267.25
#Mann= 4 ,-1 , 0
  4227.1     .17       0  4990.3     .09       0 5031.13     .17       0
  5634.9     .11       0
Bank Sta=4990.3,5031.13
XS Rating Curve= 0 ,0
Exp/Cntr=0.3,0.1

Type RM Length L Ch R = 1 ,13500   ,500,500,500
BEGIN DESCRIPTION:
STEWARTS CREEK TRIBUTARY NO 1 25.0
END DESCRIPTION:
XS GIS Cut Line= 3
      3827880.36     10127896.86       3827071.7      10127613.4
      3826575.68     10127389.05
#Sta/Elev= 30
  4143.1  267.48  4188.1  264.29  4233.3  264.51  4272.9  261.22  4336.5  259.16
  4378.9  257.39  4422.1   258.8  4447.8  260.54  4453.1   259.8  4463.7   260.9
  4473.5  257.77  4478.8  257.77  4484.8  255.85  4598.5  251.86  4876.2  243.34
    4971   241.9  4972.3  241.91  4990.1  240.13  4993.6  237.11  4997.1  237.11
  4999.4   240.3  5004.9   240.3  5013.7   241.8  5065.4  244.24  5070.9  245.19
  5081.1  244.54  5146.9  247.49  5245.7  254.68  5344.5  260.45  5544.4  265.98
#Mann= 8 ,-1 , 0
  4143.1     .17       0  4233.3     .11       0  4336.5     .17       0
  4598.5     .11       0  4876.2     .17       0    4971     .11       0
  4972.3     .09       0  5013.7     .11       0
Bank Sta=4972.3,5013.7
XS Rating Curve= 0 ,0
Exp/Cntr=0.3,0.1

Type RM Length L Ch R = 1 ,13000   ,500,500,500
BEGIN DESCRIPTION:
STEWARTS CREEK TRIBUTARY NO 1 24.0
END DESCRIPTION:
XS GIS Cut Line= 3
      3827967.83     10127511.06      3827148.98     10127176.12
      3826599.19     10127266.66
#Sta/Elev= 30
  4115.3  269.44  4183.4  267.58  4308.9  261.59  4493.1  255.49  4621.1  250.25
  4658.8  248.37  4677.1  248.68  4720.3  246.49  4806.7  243.89  4891.1  242.25
  4920.5  240.88  4949.9  240.42  4968.6  241.26  4979.6  239.34  4995.9  238.08
  4996.2  237.58  5031.5   241.2  5041.7  242.57  5082.2  244.12  5102.5   245.9
  5125.3  246.24  5181.4  249.91  5186.5   249.7  5193.7   250.9  5295.1  255.95
  5355.9  260.37    5370  260.58  5376.1  259.63    5421  261.24  5557.2  265.11
#Mann= 5 ,-1 , 0
  4115.3     .11       0  4621.1     .17       0  4968.6     .09       0
  5031.5     .17       0    5421     .11       0
Bank Sta=4968.6,5031.5
XS Rating Curve= 0 ,0
Exp/Cntr=0.3,0.1

Type RM Length L Ch R = 1 ,12500   ,500,500,500
BEGIN DESCRIPTION:
STEWARTS CREEK TRIBUTARY NO 1 23.0
END DESCRIPTION:
XS GIS Cut Line= 3
      3828018.41     10126792.71      3827388.24     10126786.94
      3826567.92     10127008.85
#Sta/Elev= 30
  4369.8  263.69  4390.4   262.6  4463.3  261.69  4560.4  258.42  4770.4  247.32
  4810.4  245.81  4820.4  246.24  4850.4   243.9  4910.4   242.2  4920.4  240.94
  4950.4  240.91  4960.4  239.73  4970.4   238.3  4978.6  235.73  5010.8  239.72
  5035.8  239.54  5070.5  240.78  5150.2  240.67  5253.8   244.9  5344.2  248.46
  5357.1  248.97  5563.7  256.23  5590.9   256.3  5613.1  258.01  5642.6  257.72
  5673.8  259.05  5722.3  258.33  5808.9   259.4  5836.8   259.1  5849.8  259.84
#Mann= 9 ,-1 , 0
  4369.8     .11       0  4463.3     .17       0  4960.4     .09       0
  5010.8     .17       0  5253.8     .11       0  5344.2     .17       0
  5357.1     .11       0  5563.7     .17       0  5808.9     .11       0
Bank Sta=4960.4,5010.8
XS Rating Curve= 0 ,0
Exp/Cntr=0.3,0.1

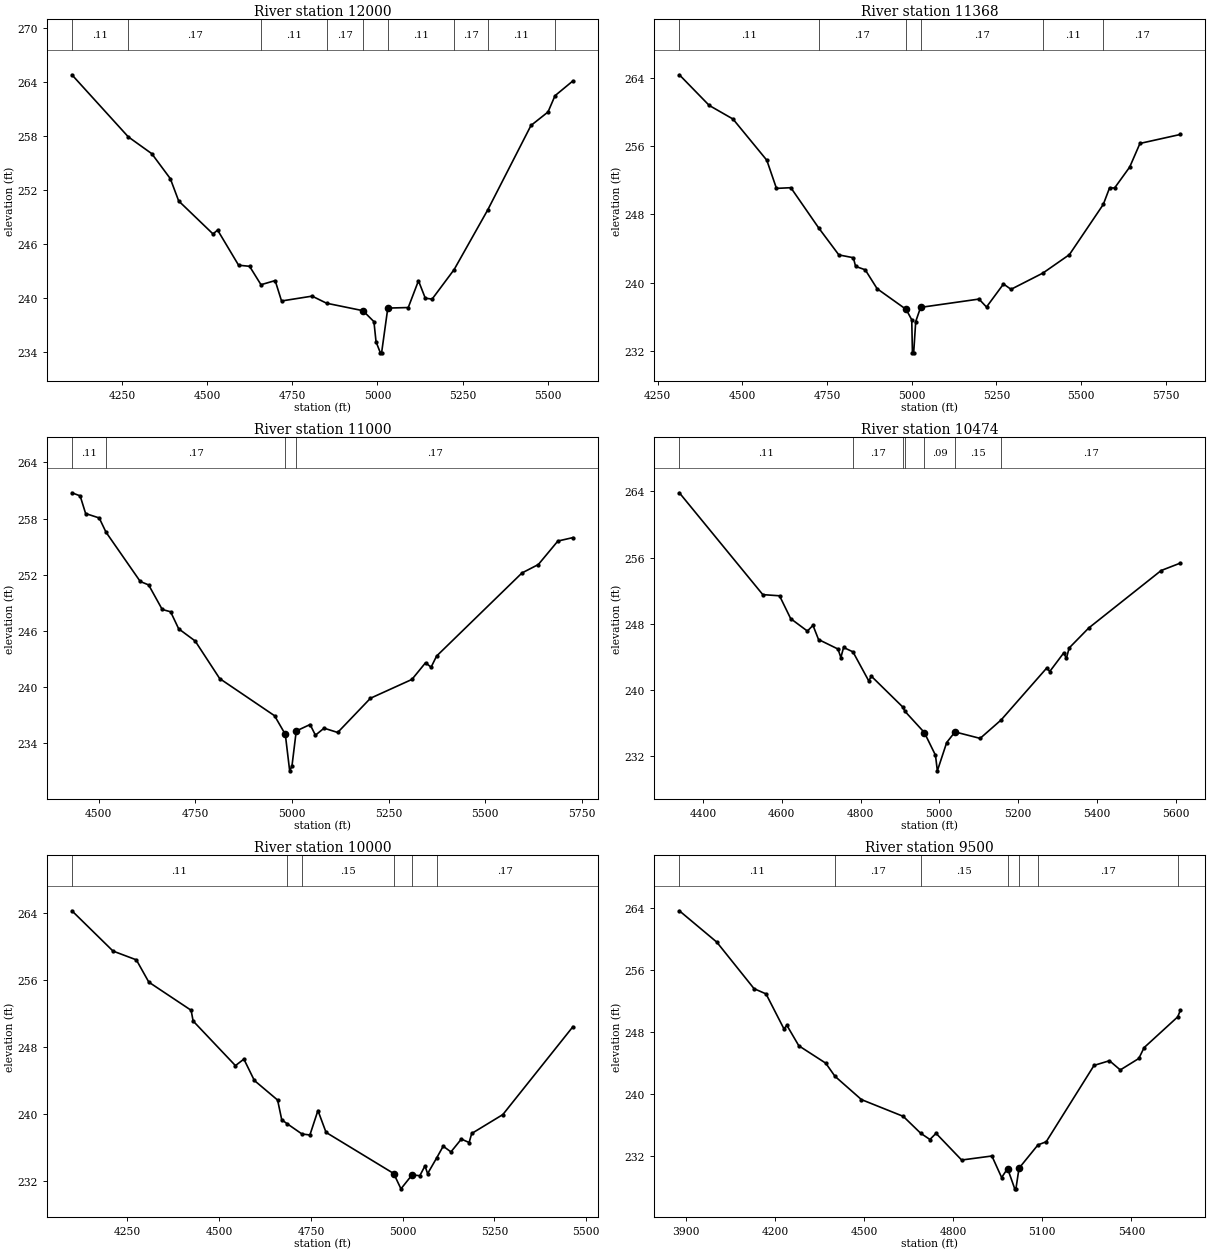
Type RM Length L Ch R = 1 ,12000   ,632,632,632
BEGIN DESCRIPTION:
STEWARTS CREEK TRIBUTARY NO 1 22.0
END DESCRIPTION:
XS GIS Cut Line= 3
      3828023.64     10126730.21      3827188.24     10126404.93
      3826614.73     10126394.27
#Sta/Elev= 30
  4103.5  264.81    4269   257.9  4337.9  256.03  4392.3  253.25  4416.8  250.77
  4517.5   247.1    4531  247.53  4592.6  243.62  4624.8   243.5  4658.3  241.45
  4699.9  241.91  4718.6  239.64  4808.3  240.18  4850.8  239.39  4957.5  238.56
  4989.7  237.34  4995.9   235.1  5008.6  233.87  5012.2  233.87  5030.4  238.85
  5090.4  238.91  5120.4  241.89  5140.4  239.95  5160.4  239.85  5225.1  243.14
  5323.7  249.78  5450.5  259.17  5500.5  260.67    5521  262.48  5573.6  264.13
#Mann= 9 ,-1 , 0
  4103.5     .11       0    4269     .17       0  4658.3     .11       0
  4850.8     .17       0  4957.5     .09       0  5030.4     .11       0
  5225.1     .17       0  5323.7     .11       0    5521    .125       0
Bank Sta=4957.5,5030.4
XS Rating Curve= 0 ,0
Exp/Cntr=0.3,0.1

Type RM Length L Ch R = 1 ,11368   ,368,368,368
BEGIN DESCRIPTION:
STEWARTS CREEK TRIBUTARY NO 1 21.0
END DESCRIPTION:
XS GIS Cut Line= 3
      3828036.61     10126696.33      3827518.24     10126246.86
       3826811.5     10125887.18
#Sta/Elev= 30
  4313.9  264.32  4402.1  260.74  4472.3  259.15  4572.1  254.34  4600.6  251.05
  4643.1  251.13  4725.1  246.44  4784.8  243.28  4827.6  242.95  4834.2  241.94
  4862.7  241.54  4897.8  239.33  4983.3  236.92    5000   235.7    5002  231.84
  5005.7  231.84  5011.7  235.49  5026.1  237.15  5198.5  238.12  5220.7  237.19
  5270.8  239.88  5293.1  239.26  5387.3  241.16  5465.4  243.31  5565.5  249.18
  5583.9   251.1  5598.9   251.1  5643.4  253.54  5673.7   256.3    5793  257.35
#Mann= 6 ,-1 , 0
  4313.9     .11       0  4725.1     .17       0  4983.3     .09       0
  5026.1     .17       0  5387.3     .11       0  5565.5     .17       0
Bank Sta=4983.3,5026.1
XS Rating Curve= 0 ,0
Exp/Cntr=0.3,0.1

Type RM Length L Ch R = 1 ,11000   ,526,526,526
BEGIN DESCRIPTION:
STEWARTS CREEK TRIBUTARY NO 1 20.0
END DESCRIPTION:
XS GIS Cut Line= 3
      3828167.85     10126461.07      3827787.51     10126037.59
      3827331.91     10125471.32
#Sta/Elev= 30
  4430.8  260.75  4452.1  260.42  4466.3  258.53  4501.4  258.06    4519  256.54
  4607.6  251.27  4629.3   250.9  4664.4  248.28  4686.1  248.03    4707  246.21
  4749.6  244.91  4813.1  240.89    4955  236.92  4982.8  234.93  4994.1  231.03
    5000  231.53  5011.1  235.29  5046.9  235.98  5060.7  234.84  5083.1  235.59
  5118.3  235.13  5203.1  238.79  5310.3   240.8  5345.5  242.58  5359.9  242.11
  5374.2   243.3    5595  252.18  5637.3  253.08  5687.8  255.59  5726.8  255.96
#Mann= 4 ,-1 , 0
  4430.8     .11       0    4519     .17       0  4982.8     .09       0
  5011.1     .17       0
Bank Sta=4982.8,5011.1
XS Rating Curve= 0 ,0
Exp/Cntr=0.3,0.1

Type RM Length L Ch R = 1 ,10474   ,474,474,474
BEGIN DESCRIPTION:
STEWARTS CREEK TRIBUTARY NO 1 19.0
END DESCRIPTION:
XS GIS Cut Line= 3
       3828385.7     10126222.81      3827908.24     10125766.86
      3827482.46     10125327.39
#Sta/Elev= 30
  4339.8  263.82  4551.7  251.52  4594.2  251.38  4622.5  248.62  4664.9  247.12
  4679.1  247.81  4693.2   246.1  4742.6  244.95  4749.9  243.92  4756.8  245.14
  4780.6  244.61  4820.6  241.11  4827.5  241.66  4907.9  237.91  4912.2  237.45
  4961.8  234.87  4990.1  232.13  4994.9  230.24  5018.6  233.66  5039.7  234.94
  5103.5  234.16  5156.7  236.38    5273  242.68  5280.2  242.23  5315.4  244.46
  5322.6  243.85  5329.6  245.08  5379.2  247.49  5563.1  254.43  5611.9  255.33
#Mann= 7 ,-1 , 0
  4339.8     .11       0  4780.6     .17       0  4907.9     .11       0
  4912.2     .15       0  4961.8     .09       0  5039.7     .15       0
  5156.7     .17       0
Bank Sta=4961.8,5039.7
XS Rating Curve= 0 ,0
Exp/Cntr=0.3,0.1

Type RM Length L Ch R = 1 ,10000   ,500,500,500
BEGIN DESCRIPTION:
STEWARTS CREEK TRIBUTARY NO 1 18.0
END DESCRIPTION:
XS GIS Cut Line= 3
      3828417.86      10126211.1      3828043.99     10125391.11
      3827717.85     10125061.07
#Sta/Elev= 30
  4098.8  264.23  4210.8  259.42  4274.4  258.37  4308.4  255.71  4423.6  252.35
  4429.1  251.07  4544.4  245.74  4567.4  246.52  4595.9  243.97  4659.3  241.63
  4670.6  239.27  4684.8  238.82  4725.6  237.58  4747.3  237.46  4769.2  240.38
  4791.3  237.77  4975.6  232.86  4995.4  231.03  5025.6  232.69  5046.8   232.6
  5060.9  233.77    5068  232.84  5093.1  234.75  5110.5  236.12  5131.6  235.44
  5159.9  236.97  5181.2  236.56  5188.2  237.64  5273.1   239.9    5464  250.39
#Mann= 6 ,-1 , 0
  4098.8     .11       0  4684.8     .17       0  4725.6     .15       0
  4975.6     .06       0  5025.6     .15       0  5093.1     .17       0
Bank Sta=4975.6,5025.6
XS Rating Curve= 0 ,0
Exp/Cntr=0.3,0.1

Type RM Length L Ch R = 1 ,9500    ,283,283,283
BEGIN DESCRIPTION:
STEWARTS CREEK TRIBUTARY NO 1 17.0
END DESCRIPTION:
XS GIS Cut Line= 3
      3828445.03     10126171.71       3828336.3     10125054.08
       3827802.3     10124869.81
#Sta/Elev= 30
  3877.1  263.61  4003.1  259.57  4128.9  253.55  4169.1  252.88  4229.4  248.37
  4239.4  248.82  4279.6  246.18  4370.1  243.94  4401.4  242.24  4490.6  239.23
  4631.3  237.07  4689.8   234.9  4721.2  234.08  4741.8  234.88  4828.1  231.43
    4930  231.95  4962.8  229.17  4982.9  230.33    5007  227.71  5010.9  227.71
 5021.42230.3745  5085.1  233.38    5113  233.79  5274.2  243.65  5326.1  244.25
  5362.5  243.06  5424.9  244.54  5442.7  245.94  5555.9  249.91  5564.9  250.76
#Mann= 7 ,-1 , 0
  3877.1     .11       0  4401.4     .17       0  4689.8     .15       0
  4982.9     .09       0 5021.42     .15       0  5085.1     .17       0
  5555.9     .11       0
Bank Sta=4982.9,5021.42
XS Rating Curve= 0 ,0
Exp/Cntr=0.3,0.1

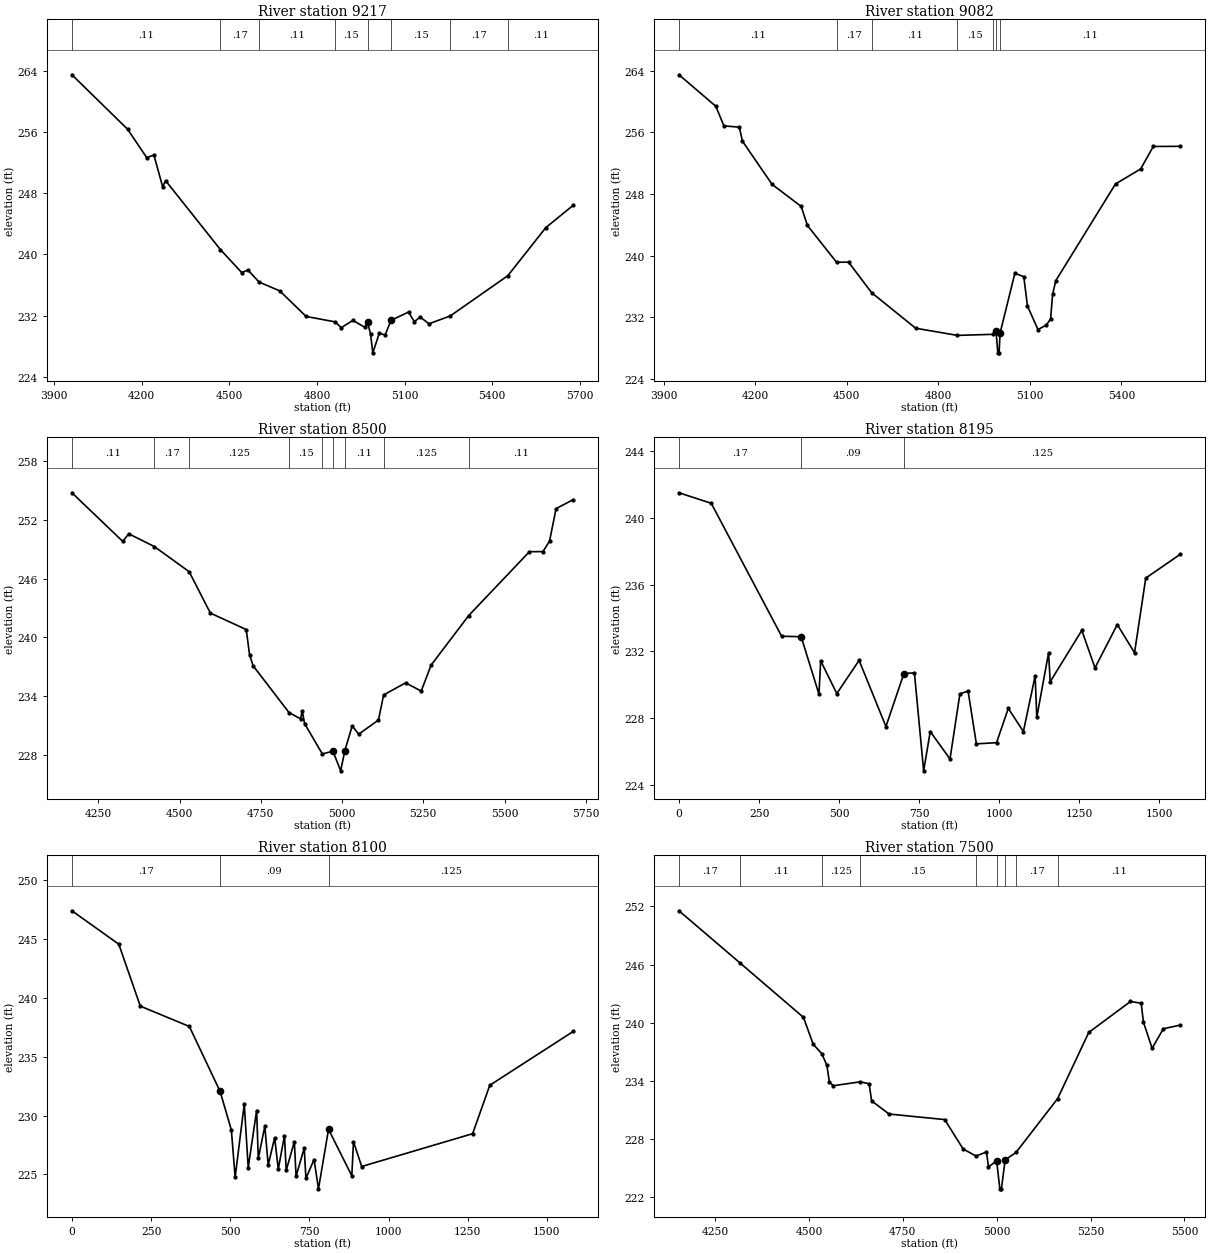
Type RM Length L Ch R = 1 ,9217    ,135,135,135
BEGIN DESCRIPTION:
STEWARTS CREEK TRIBUTARY NO 1 16.0
END DESCRIPTION:
XS GIS Cut Line= 3
      3828467.85     10126161.04      3828528.54     10125124.51
      3828510.94     10124447.44
#Sta/Elev= 30
  3961.7  263.46    4152  256.36  4217.7  252.64  4242.1  252.99  4272.2  248.84
  4282.2  249.64  4469.8  240.64  4542.7  237.64  4564.1  237.97    4602   236.4
  4672.9  235.25    4763  231.91  4862.9   231.2  4883.2  230.44  4923.3   231.4
  4963.4   230.5  4973.4  231.15  4983.4  229.63  4991.4  227.16  5013.4  229.72
  5033.5  229.49  5053.5   231.4  5113.5  232.48  5133.5  231.22  5153.5  231.84
  5183.5  230.95  5256.4  231.98  5453.3  237.23  5583.6  243.52  5677.3  246.43
#Mann= 8 ,-1 , 0
  3961.7     .11       0  4469.8     .17       0    4602     .11       0
  4862.9     .15       0  4973.4     .09       0  5053.5     .15       0
  5256.4     .17       0  5453.3     .11       0
Bank Sta=4973.4,5053.5
XS Rating Curve= 0 ,0
Exp/Cntr=0.3,0.1

Type RM Length L Ch R = 1 ,9082    ,582,582,582
BEGIN DESCRIPTION:
STEWARTS CREEK TRIBUTARY NO 1 16.5
END DESCRIPTION:
XS GIS Cut Line= 3
      3828493.58     10126166.23      3828662.68     10125130.54
      3828805.79     10124554.97
#Sta/Elev= 30
  3950.6  263.45  4071.3  259.37  4097.7  256.83  4148.3  256.66  4158.5  254.85
  4255.6  249.25    4351  246.39  4371.3  243.93  4466.8  239.16  4506.3  239.17
  4581.6  235.22  4725.9  230.61  4862.8  229.68  4978.8  229.82  4989.3  230.19
  4995.2  227.42  4999.2  227.42  5002.7     230    5051  237.73  5080.2  237.29
  5092.2   233.5  5126.6  230.44    5154  231.02    5168  231.82  5174.6  234.99
  5184.9  236.76  5380.7  249.31  5463.2  251.25  5504.4  254.16  5593.1  254.18
#Mann= 7 ,-1 , 0
  3950.6     .11       0  4466.8     .17       0  4581.6     .11       0
  4862.8     .15       0  4978.8     .11       0  4989.3     .09       0
  5002.7     .11       0
Bank Sta=4989.3,5002.7
XS Rating Curve= 0 ,0
Exp/Cntr=0.3,0.1

Type RM Length L Ch R = 1 ,8500    ,305,305,305
BEGIN DESCRIPTION:
STEWARTS CREEK TRIBUTARY NO 1 15.0
END DESCRIPTION:
XS GIS Cut Line= 3
      3828786.09     10126109.27      3829052.64     10125321.76
      3828942.59     10124618.72
#Sta/Elev= 30
  4168.6  254.75  4325.1  249.79  4343.3  250.57  4422.1  249.27  4529.4   246.7
  4594.7  242.48  4705.1   240.8  4715.2  238.25  4726.2  237.11  4836.8  232.33
  4872.3   231.7  4877.6   232.5  4884.6  231.21  4939.3  228.11  4971.9   228.4
  4995.7  226.39  5008.6228.4558  5031.1  230.97  5051.3  230.13    5112  231.57
  5127.8  234.13  5195.4  235.36  5243.6  234.53    5274  237.17  5389.8  242.23
  5576.6  248.74  5618.1  248.75  5638.4   249.8  5658.6  253.13  5711.6  254.06
#Mann= 9 ,-1 , 0
  4168.6     .11       0  4422.1     .17       0  4529.4    .125       0
  4836.8     .15       0  4939.3     .11       0  4971.9     .09       0
  5008.6     .11       0  5127.8    .125       0  5389.8     .11       0
Bank Sta=4971.9,5008.6
XS Rating Curve= 0 ,0
Exp/Cntr=0.3,0.1

Type RM Length L Ch R = 1 ,8195    ,95,95,95
XS GIS Cut Line= 3
      3829152.07     10125795.66      3829337.29     10125290.74
      3829578.45     10124292.03
#Sta/Elev= 30
       0  241.52   100.7  240.89   320.4  232.91   381.4  232.88     437  229.43
   442.4  231.43   492.7  229.47   562.3  231.46   646.1  227.49   702.1  230.67
     735  230.71   763.8  224.83   784.4  227.19   846.1  225.54     877  229.45
   902.5  229.62   928.4  226.45   991.4  226.52  1028.1  228.58  1075.2  227.19
  1111.9  230.53    1117  228.04  1153.8  231.91  1158.9  230.18  1257.6  233.26
  1298.7  231.01  1368.3  233.61  1422.2  231.92  1457.2   236.4  1565.2  237.83
#Mann= 3 , 0 , 0
       0     .17       0   381.4     .09       0   702.1    .125       0
Bank Sta=381.4,702.1
XS Rating Curve= 0 ,0
Exp/Cntr=0.3,0.1

Type RM Length L Ch R = 1 ,8100    ,600,600,600
XS GIS Cut Line= 3
      3829286.09     10125820.21       3829429.2     10125265.68
       3829760.7     10124310.74
#Sta/Elev= 30
       0  247.42     148  244.58     216  239.31   370.9  237.58   468.1  232.05
   503.6  228.77   515.5  224.75   544.3  230.98   556.8  225.58   583.4  230.43
   588.6  226.36   609.2  229.09   619.9   225.8   640.3  228.12   651.7  225.45
   671.4   228.3   676.7  225.33   702.6  227.78   707.9  224.84   733.7  227.24
     739  224.66   764.8  226.26   778.7  223.77   810.5  228.83     884  224.88
   889.3  227.79   915.1  225.67  1265.6  228.46  1319.8  232.58  1583.5  237.16
#Mann= 3 , 0 , 0
       0     .17       0   468.1     .09       0   810.5    .125       0
Bank Sta=468.1,810.5
XS Rating Curve= 0 ,0
Exp/Cntr=0.3,0.1

Type RM Length L Ch R = 1 ,7500    ,500,500,500
BEGIN DESCRIPTION:
STEWARTS CREEK TRIBUTARY NO 1 13.0
END DESCRIPTION:
XS GIS Cut Line= 3
      3829504.15     10125859.49      3829781.68     10125060.31
      3830024.82     10124635.81
#Sta/Elev= 30
    4154  251.54  4316.9  246.15  4485.6  240.55  4511.4  237.78  4534.2  236.82
  4547.8  235.61  4554.6  233.88  4565.2  233.51  4636.9  233.91  4660.4  233.71
    4667  231.95  4713.4  230.59  4861.6  230.02  4910.7  226.99    4945  226.26
  4972.9  226.68  4978.2  225.14    5000  225.76  5008.5  222.88  5012.7  222.88
 5022.57225.8542  5051.5  226.63  5162.4  232.18  5245.3     239  5356.4  242.19
  5384.9  242.01  5390.9  240.06    5414  237.37  5443.9  239.38  5489.2  239.76
#Mann= 9 ,-1 , 0
    4154     .17       0  4316.9     .11       0  4534.2    .125       0
  4636.9     .15       0    4945    .125       0    5000     .09       0
 5022.57    .125       0  5051.5     .17       0  5162.4     .11       0
Bank Sta=5000,5022.57
XS Rating Curve= 0 ,0
Exp/Cntr=0.3,0.1

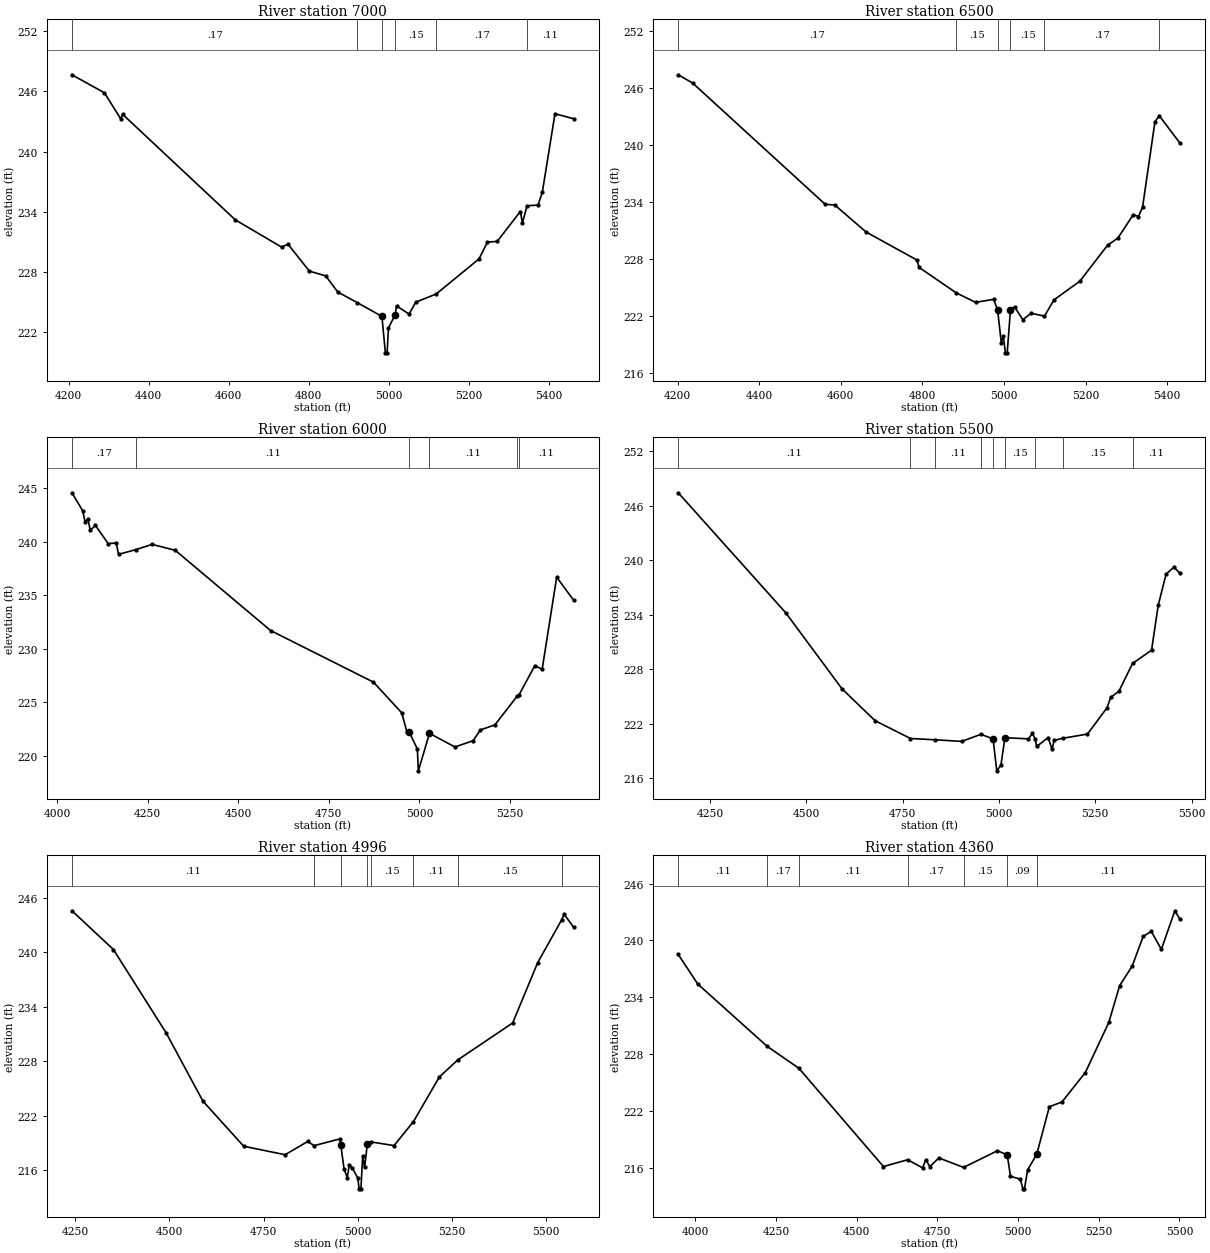
Type RM Length L Ch R = 1 ,7000    ,500,500,500
BEGIN DESCRIPTION:
STEWARTS CREEK TRIBUTARY NO 1 12.0
END DESCRIPTION:
XS GIS Cut Line= 3
      3829899.12     10125907.23      3830176.75     10125165.37
      3830324.46     10124726.68
#Sta/Elev= 30
  4207.9  247.66  4289.2  245.86  4329.6  243.28    4335   243.7  4616.4  233.18
  4732.2  230.46  4748.3  230.75  4801.7  228.06  4842.7  227.58  4872.9  225.97
  4922.1   224.9  4983.2  223.54  4991.9   219.9  4996.2   219.9  4999.6   222.4
 5016.32223.6864  5019.7  224.59  5051.2  223.77  5067.8  224.96  5119.2  225.78
  5226.1  229.28  5247.2  230.95  5271.7  231.03  5329.4  234.01  5334.7  232.87
  5346.2  234.58  5373.8  234.65  5384.4  235.93  5416.1  243.77  5462.9  243.27
#Mann= 6 ,-1 , 0
  4207.9     .17       0  4922.1     .15       0  4983.2     .09       0
 5016.32     .15       0  5119.2     .17       0  5346.2     .11       0
Bank Sta=4983.2,5016.32
XS Rating Curve= 0 ,0
Exp/Cntr=0.3,0.1

Type RM Length L Ch R = 1 ,6500    ,500,500,500
BEGIN DESCRIPTION:
STEWARTS CREEK TRIBUTARY NO 1 11.0
END DESCRIPTION:
XS GIS Cut Line= 3
      3830276.72     10125963.66        3830584.     10125226.86
      3830649.99     10124800.44
#Sta/Elev= 30
  4201.7  247.39    4237  246.52    4562  233.75  4585.2  233.69  4662.1  230.84
  4786.7  227.89  4792.1  227.11  4883.5  224.42  4930.4  223.44  4975.1  223.75
  4984.6  222.58  4993.5  219.19  4998.5  219.85  5003.7  218.12    5008  218.12
    5016  222.66  5026.1  222.95  5046.3  221.61  5066.6  222.28  5099.4  221.99
  5122.8   223.7  5185.8  225.65  5253.9  229.44  5279.1  230.19    5317  232.67
  5329.7  232.47  5339.8  233.46  5370.1  242.44  5380.5  243.09  5431.5  240.19
#Mann= 6 ,-1 , 0
  4201.7     .17       0  4883.5     .15       0  4984.6     .09       0
    5016     .15       0  5099.4     .17       0  5380.5     .11       0
Bank Sta=4984.6,5016
XS Rating Curve= 0 ,0
Exp/Cntr=0.3,0.1

Type RM Length L Ch R = 1 ,6000    ,500,500,500
BEGIN DESCRIPTION:
STEWARTS CREEK TRIBUTARY NO 1 10.0
END DESCRIPTION:
XS GIS Cut Line= 3
      3830411.26     10126015.74      3831024.11     10125278.64
      3831053.51     10124854.26
#Sta/Elev= 30
  4041.4  244.55  4071.1  242.87  4077.6  241.83  4085.4  242.11  4091.9  241.05
  4106.2   241.5  4141.4  239.81  4163.5  239.86    4170   238.8  4218.5  239.25
  4262.5  239.73  4326.3  239.18  4589.3  231.69  4873.1  226.87  4951.2     224
  4965.5  222.19    4972   222.2  4994.2  220.62  4996.9  218.59  5027.6  222.09
  5097.8  220.82  5147.9   221.4    5168  222.41  5208.1  222.88  5269.6  225.57
  5274.9   225.7  5318.3  228.42  5338.4  228.07  5378.5  236.67  5425.4  234.51
#Mann= 6 ,-1 , 0
  4041.4     .17       0  4218.5     .11       0    4972     .09       0
  5027.6     .11       0  5269.6     .15       0  5274.9     .11       0
Bank Sta=4972,5027.6
XS Rating Curve= 0 ,0
Exp/Cntr=0.3,0.1

Type RM Length L Ch R = 1 ,5500    ,504,504,504
BEGIN DESCRIPTION:
STEWARTS CREEK TRIBUTARY NO 1 9.0
END DESCRIPTION:
XS GIS Cut Line= 3
      3831257.63     10126141.58      3831424.17     10125326.12
        3831518.     10124865.78
#Sta/Elev= 30
  4167.7  247.44  4446.3  234.25  4592.7  225.86  4678.5  222.35  4770.4  220.39
  4833.4  220.25  4903.1  220.07  4953.3  220.85  4984.7  220.35  4994.3  216.83
  5005.1  217.45  5015.4  220.48  5076.6  220.35  5086.8  220.95    5094  220.32
  5097.8  219.51  5127.6  220.49  5137.8  219.21  5143.3  220.18  5164.9  220.41
  5229.7  220.88  5280.7  223.79  5289.8  224.91  5311.3  225.59  5346.6  228.65
    5396  230.11  5413.4  235.08  5433.8   238.5  5454.2  239.25  5469.8  238.57
#Mann= 9 ,-1 , 0
  4167.7     .11       0  4770.4     .17       0  4833.4     .11       0
  4953.3     .15       0  4984.7     .09       0  5015.4     .15       0
    5094     .17       0  5164.9     .15       0  5346.6     .11       0
Bank Sta=4984.7,5015.4
XS Rating Curve= 0 ,0
Exp/Cntr=0.3,0.1

Type RM Length L Ch R = 1 ,4996    ,636,636,636
BEGIN DESCRIPTION:
STEWARTS CREEK TRIBUTARY NO 1 8.0
END DESCRIPTION:
XS GIS Cut Line= 3
      3831552.75     10126145.98      3831821.71     10125436.77
      3831865.25     10124865.82
#Sta/Elev= 30
  4241.5  244.59  4351.5  240.32  4491.5  231.12    4589   223.6  4697.1  218.63
    4807  217.69  4867.3  219.16  4883.8  218.69  4952.6  219.44 4954.63 218.814
  4963.3  216.14  4971.8  215.17  4977.2  216.54  4984.7  216.28    5000   215.1
  5003.3  213.93  5008.1  213.93  5012.9  217.57  5017.9  216.29 5025.05218.8423
  5035.1   219.1    5096   218.7  5147.6  221.35  5216.3  226.27  5265.2  228.15
  5410.7  232.22  5477.1  238.87  5540.9  243.61  5547.3   244.2  5572.6  242.77
#Mann= 8 ,-1 , 0
  4241.5     .11       0  4883.8     .17       0 4954.63     .09       0
 5025.05     .17       0  5035.1     .15       0  5147.6     .11       0
  5265.2     .15       0  5540.9     .11       0
Bank Sta=4954.63,5025.05
XS Rating Curve= 0 ,0
Exp/Cntr=0.3,0.1

Type RM Length L Ch R = 1 ,4360    ,679,679,679
BEGIN DESCRIPTION:
STEWARTS CREEK TRIBUTARY NO 1 7.0
END DESCRIPTION:
XS GIS Cut Line= 3
      3832117.85     10126361.08      3832260.08     10125318.03
      3832121.48     10124835.65
#Sta/Elev= 30
  3947.3  238.52  4007.9   235.4  4222.5  228.84  4321.3  226.51  4583.1  216.15
  4658.1  216.87  4704.3  216.01  4714.3  216.87    4727  216.14  4754.7  217.06
  4831.3  216.06  4936.4  217.82  4966.7  217.38  4976.7  215.12  5007.2  214.82
  5015.2   213.8    5020   213.8  5029.7  215.79  5058.2  217.46  5097.1  222.46
  5136.1  222.96  5208.7  226.07  5281.3  231.35    5315  235.24  5353.9   237.3
  5387.7  240.42    5413  240.96  5444.2  239.06  5485.9  243.13  5501.9  242.23
#Mann= 7 ,-1 , 0
  3947.3     .11       0  4222.5     .17       0  4321.3     .11       0
  4658.1     .17       0  4831.3     .15       0  4966.7     .09       0
  5058.2     .11       0
Bank Sta=4966.7,5058.2
XS Rating Curve= 0 ,0
Exp/Cntr=0.3,0.1