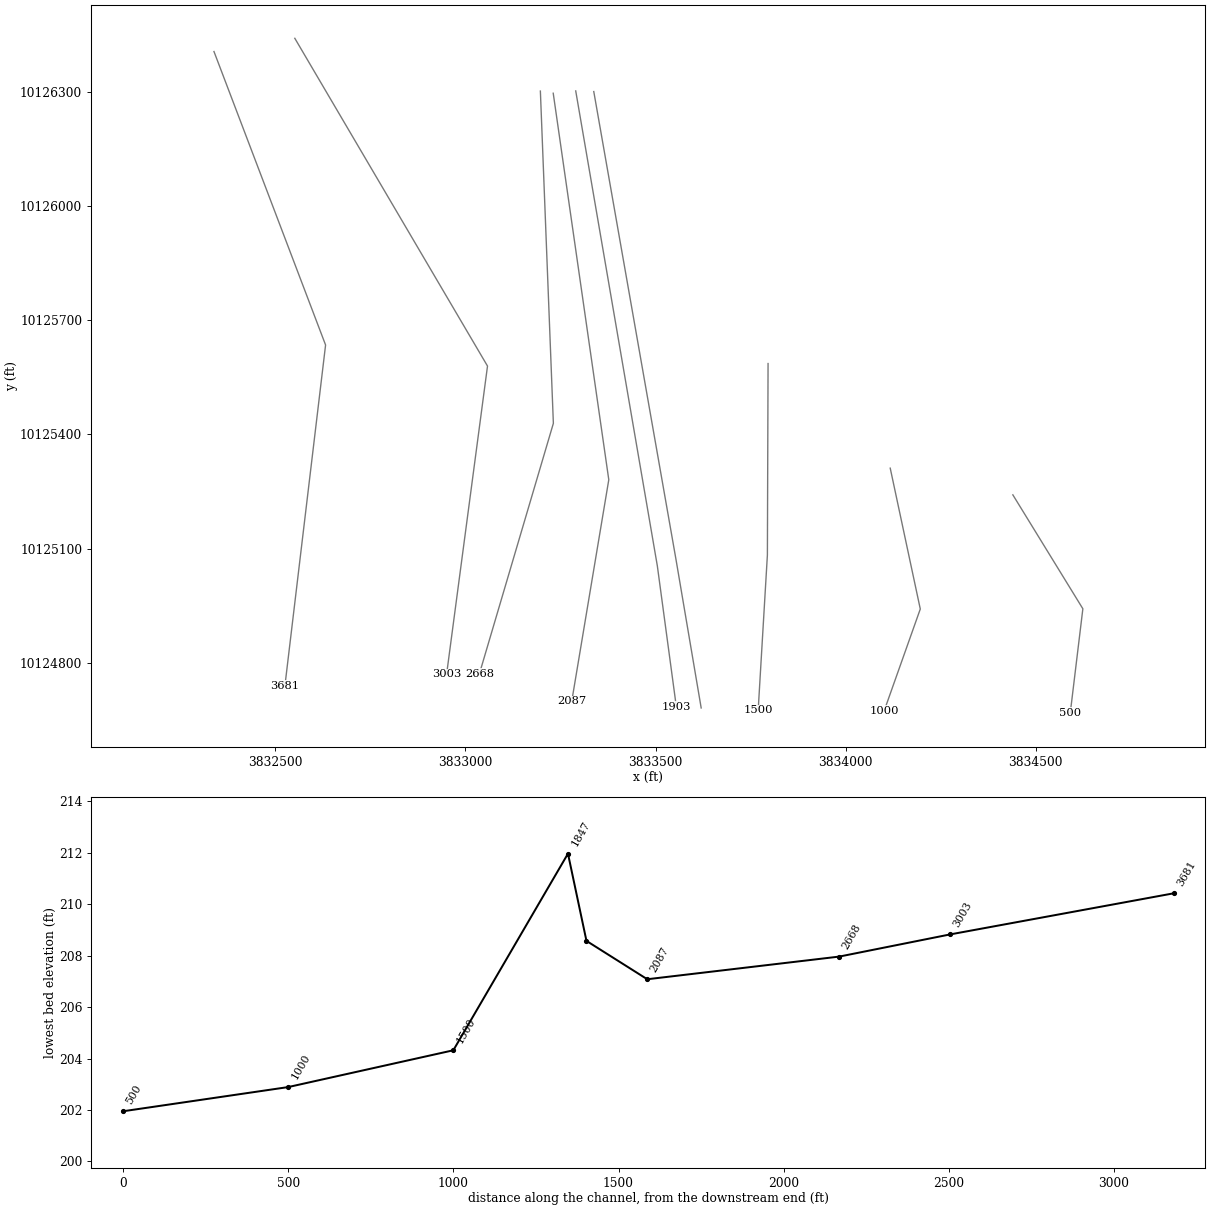
HEC-RAS study STEWARTS CREEK TRIBUTARY NO 1.prj: STEWARTS CREEK TRIBUTARY NO 1 Base Level Engineering

--- STEWARTS CREEK TRIBUTARY NO 1.g01 (geometry) --- (continued)

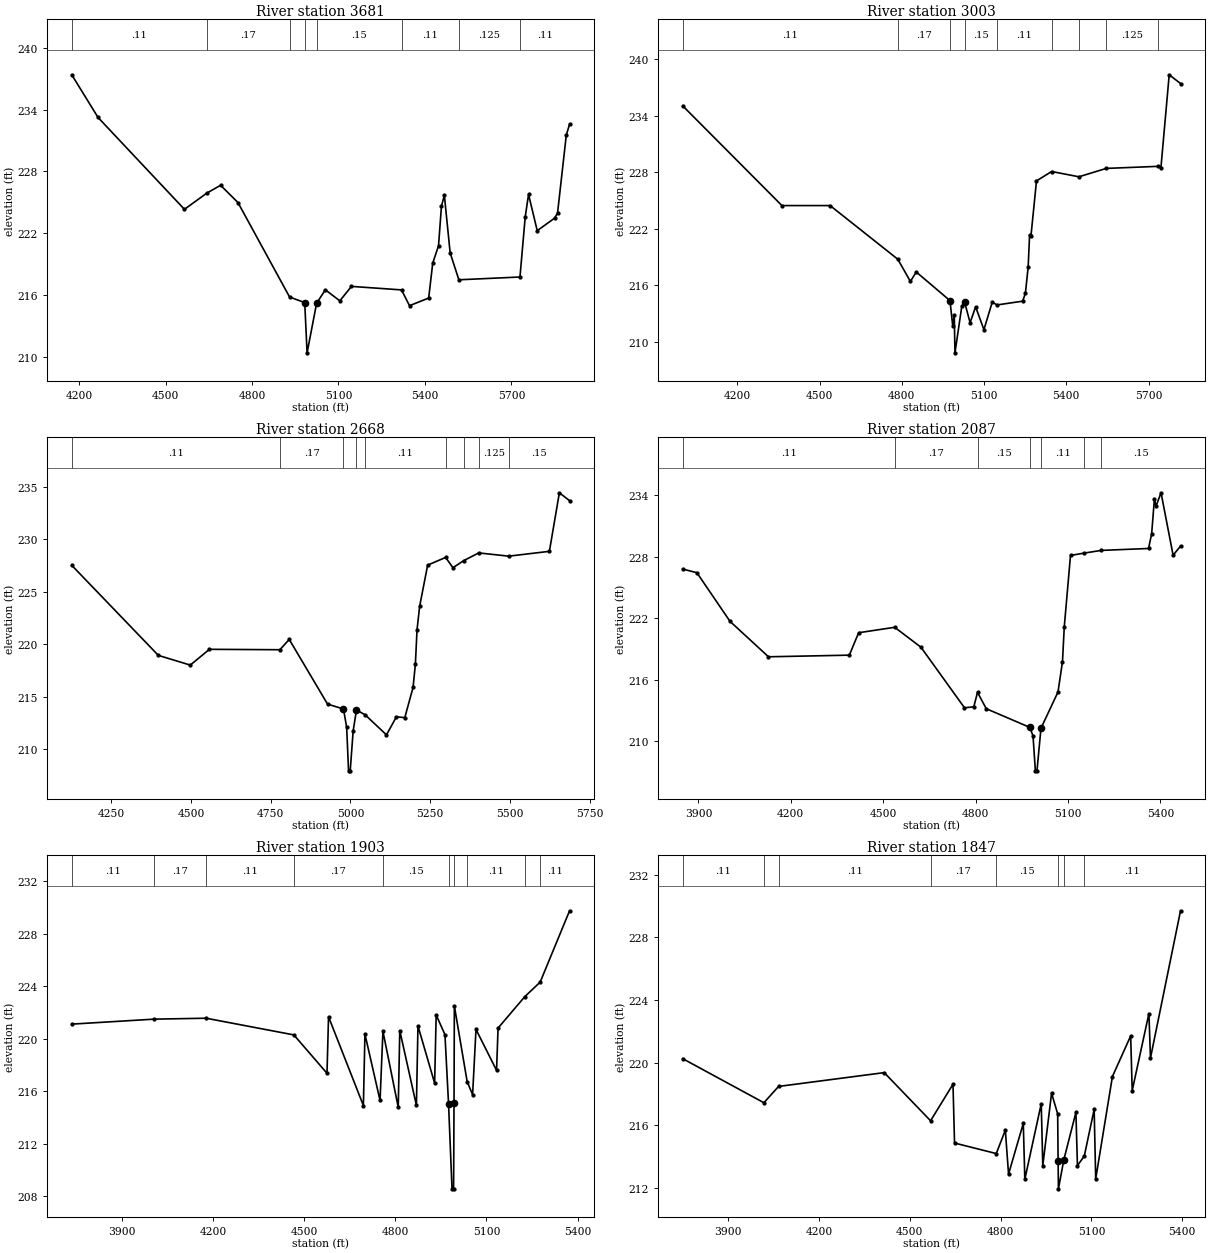
Type RM Length L Ch R = 1 ,3681    ,678,678,678
BEGIN DESCRIPTION:
Mapping XS a0a90d26
END DESCRIPTION:
XS GIS Cut Line= 3
      3832338.35     10126406.36      3832631.95     10125635.05
      3832524.99     10124739.71
#Sta/Elev= 30
  4174.7  237.37    4266  233.23  4565.6  224.33  4643.3   225.9    4691  226.66
  4751.2  224.99  4930.4  215.83  4982.9  215.29  4991.1  210.42  5024.1  215.22
  5054.4  216.53  5104.7  215.46    5145  216.86  5318.7  216.52  5346.4  214.99
  5412.9  215.73    5427  219.12  5447.1   220.8  5457.2  224.63  5467.3  225.69
  5487.4  220.11  5517.6   217.5  5729.6  217.77  5747.7  223.56  5759.3  225.77
  5789.5  222.26    5850  223.48    5860  223.98  5890.3  231.52  5901.7  232.58
#Mann= 8 ,-1 , 0
  4174.7     .11       0  4643.3     .17       0  4930.4     .15       0
  4982.9     .09       0  5024.1     .15       0  5318.7     .11       0
  5517.6    .125       0  5729.6     .11       0
#Block Obstruct= 2 , 0
                         5469.49          225.65
Bank Sta=4982.9,5024.1
XS Rating Curve= 0 ,0
Exp/Cntr=0.3,0.1

Type RM Length L Ch R = 1 ,3003    ,335,335,335
BEGIN DESCRIPTION:
STEWARTS CREEK TRIBUTARY NO 1 6.0
END DESCRIPTION:
XS GIS Cut Line= 3
      3832551.01     10126441.11      3833057.91     10125579.69
      3832950.34     10124770.11
#Sta/Elev= 30
  4000.5  235.07  4362.5  224.47  4538.3  224.47  4785.2  218.77  4831.2  216.41
  4852.7  217.41  4975.6  214.37  4985.5  211.72  4991.3  212.82  4993.8  208.82
  5018.8  213.78  5028.9  214.22    5049  212.02  5069.2  213.71  5099.5  211.28
  5129.8  214.21  5147.1  213.91  5240.7  214.31  5250.8  215.15  5260.9  217.96
  5266.1  221.37  5271.1  221.25  5291.2  227.09  5346.5  228.09  5446.1  227.53
  5545.8  228.42  5735.7  228.64  5745.1  228.46  5775.4  238.37  5816.7  237.44
#Mann= 9 ,-1 , 0
  4000.5     .11       0  4785.2     .17       0  4975.6     .09       0
  5028.9     .15       0  5147.1     .11       0  5346.5    .125       0
  5446.1     .15       0  5545.8    .125       0  5735.7     .15       0
Bank Sta=4975.6,5028.9
XS Rating Curve= 0 ,0
Exp/Cntr=0.3,0.1

Type RM Length L Ch R = 1 ,2668    ,581,581,581
BEGIN DESCRIPTION:
STEWARTS CREEK TRIBUTARY NO 1 5.0
END DESCRIPTION:
XS GIS Cut Line= 3
      3833196.97     10126302.44      3833231.16     10125429.21
       3833036.4      10124770.4
#Sta/Elev= 30
  4126.1  227.51  4397.7  218.94  4497.8  218.02  4557.8  219.52  4778.6  219.48
    4808  220.46  4928.1  214.31  4978.1  213.84  4988.1   212.1    4994  207.96
  4999.2  207.96  5008.5  211.78  5018.9  213.75  5046.4  213.28  5112.8  211.38
  5144.1   213.1  5170.3  213.02  5196.2  215.89  5203.5  218.08  5208.7  221.38
    5217  223.63    5242  227.53  5298.4  228.26  5321.3  227.28  5354.7  227.95
  5402.1  228.69  5496.1  228.38  5623.7  228.84    5655  234.41    5687  233.66
#Mann= 9 ,-1 , 0
  4126.1     .11       0  4778.6     .17       0  4978.1     .09       0
  5018.9     .17       0  5046.4     .11       0  5298.4    .125       0
  5354.7     .15       0  5402.1    .125       0  5496.1     .15       0
Bank Sta=4978.1,5018.9
XS Rating Curve= 0 ,0
Exp/Cntr=0.3,0.1

Type RM Length L Ch R = 1 ,2087    ,184,184,184
BEGIN DESCRIPTION:
Mapping XS e6dbec3b
END DESCRIPTION:
XS GIS Cut Line= 3
      3833230.77      10126296.8      3833376.94     10125280.92
      3833279.49     10124698.66
#Sta/Elev= 30
  3848.9  226.79  3895.1  226.43  4002.6  221.68  4127.5  218.22  4390.1  218.38
  4420.3  220.57  4537.3   221.1  4622.5  219.16    4764  213.24  4794.3  213.33
  4806.3  214.75  4834.7  213.15  4976.5  211.32  4986.6  210.48  4994.2  207.08
  4999.4  207.08 5012.44211.2393  5067.7  214.78  5082.3  217.75    5088  221.12
  5108.3  228.12  5153.1  228.35  5207.6  228.61  5361.8   228.8  5371.9  230.25
  5380.8  233.66  5385.9  232.92  5402.3  234.24  5441.5  228.14  5465.6  229.03
#Mann= 7 ,-1 , 0
  3848.9     .11       0  4537.3     .17       0  4806.3     .15       0
  4976.5     .09       0 5012.44     .11       0  5153.1    .125       0
  5207.6     .15       0
Bank Sta=4976.5,5012.44
XS Rating Curve= 0 ,0
Exp/Cntr=0.3,0.1

Type RM Length L Ch R = 1 ,1903    ,56,56,56
BEGIN DESCRIPTION:
STEWARTS CREEK TRIBUTARY NO 1 4.0
END DESCRIPTION:
XS GIS Cut Line= 3
      3833289.96     10126302.82      3833504.61     10125054.84
      3833554.61      10124684.4
#Sta/Elev= 30
  3733.7  221.11  4005.3  221.49  4176.3  221.56  4465.4  220.29  4574.6  217.37
  4579.7  221.67  4694.5  214.91  4699.6  220.35  4749.4   215.3  4758.9  220.57
  4809.3  214.78  4814.4  220.62  4869.2  214.92  4874.3  220.97  4929.2  216.62
  4934.3  221.81  4963.2  220.31 4975.02215.0648  4986.5  208.57  4991.7  208.57
  4993.1215.1129  4994.2   222.5  5036.3  216.74  5054.3  215.74  5065.5  220.71
  5133.2  217.59  5138.2  220.81  5226.2   223.2  5276.9  224.31  5373.8  229.74
#Mann= 10 ,-1 , 0
  3733.7     .11       0  4005.3     .17       0  4176.3     .11       0
  4465.4     .17       0  4758.9     .15       0 4975.02     .09       0
  4993.1     .15       0  5036.3     .11       0  5226.2     .15       0
  5276.9     .11       0
Bank Sta=4975.02,4993.1
XS Rating Curve= 0 ,0
Exp/Cntr=0.3,0.1

Type RM Length L Ch R = 1 ,1847    ,347,347,347
BEGIN DESCRIPTION:
STEWARTS CREEK TRIBUTARY NO 1 3.5
END DESCRIPTION:
XS GIS Cut Line= 3
      3833337.44     10126301.18      3833553.99     10125069.87
      3833619.99     10124681.14
#Sta/Elev= 30
  3749.8  220.26  4018.1  217.45  4066.5  218.49  4415.5  219.37  4568.6   216.3
  4642.7  218.63  4647.8  214.88  4785.6  214.21  4815.6   215.7  4826.2   212.9
  4874.9  216.13    4880  212.57  4934.2  217.39  4939.3  213.44  4968.3  218.06
  4988.5  216.74 4989.89213.7651    4991  211.96  5008.9  213.82  5048.7  216.83
  5053.8  213.44  5076.4  214.05    5109  217.02  5114.1  212.59  5169.3  219.12
  5229.6  221.71  5234.7  218.23  5289.9  223.14    5295   220.3  5394.3  229.69
#Mann= 8 ,-1 , 0
  3749.8     .11       0  4018.1     .17       0  4066.5     .11       0
  4568.6     .17       0  4785.6     .15       0 4989.89     .09       0
  5008.9     .15       0  5076.4     .11       0
Bank Sta=4989.89,5008.9
XS Rating Curve= 0 ,0
Exp/Cntr=0.3,0.1

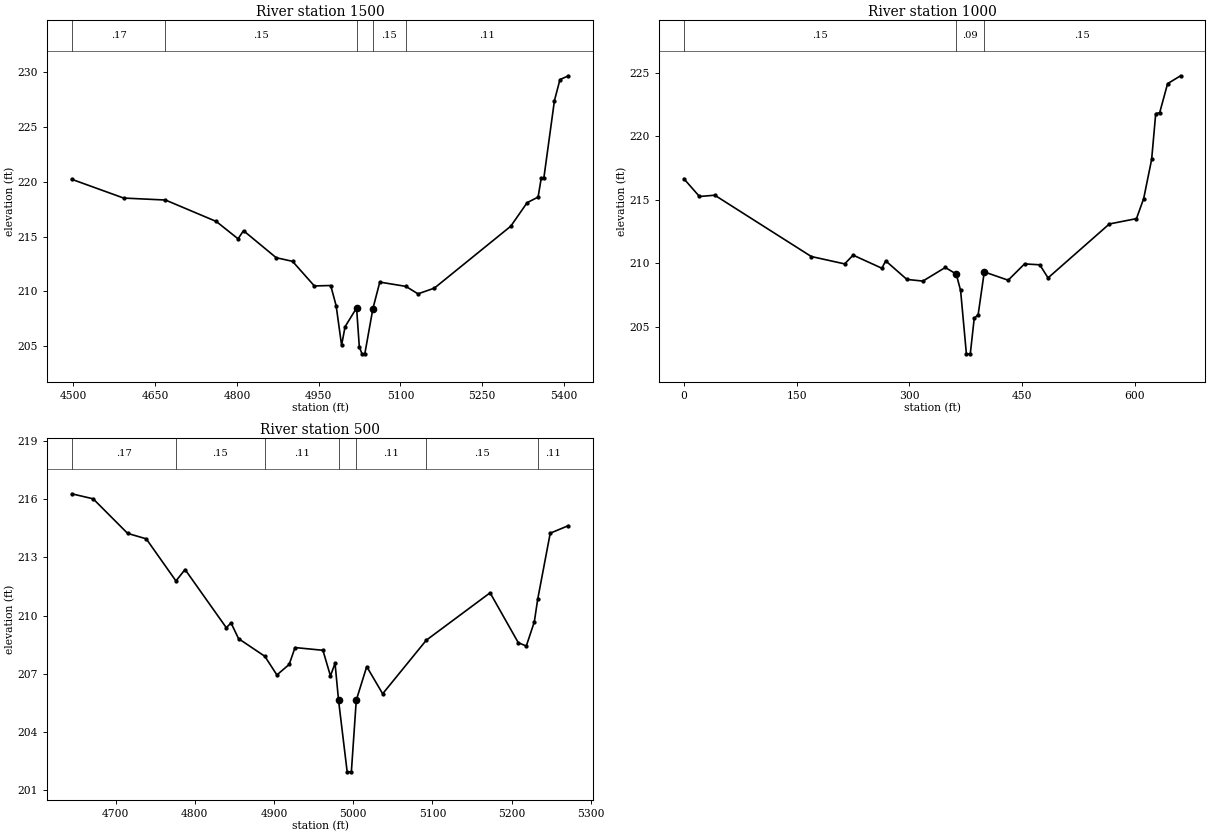
Type RM Length L Ch R = 1 ,1500    ,500,500,500
BEGIN DESCRIPTION:
STEWARTS CREEK TRIBUTARY NO 1 3.0
END DESCRIPTION:
XS GIS Cut Line= 3
      3833795.93     10125586.33      3833794.16     10125083.13
      3833769.92     10124675.45
#Sta/Elev= 30
  4496.8  220.21  4592.1   218.5  4668.9  218.32  4762.1  216.37  4802.1  214.79
  4812.1  215.53  4872.1  213.07  4902.1  212.74  4942.1   210.5  4972.1  210.54
  4982.1   208.7  4992.1   205.1  4998.5  206.79  5019.6   208.5  5024.6  204.97
  5029.5  204.32  5034.7  204.32  5049.6208.4433  5062.2  210.85  5110.1  210.46
  5132.3  209.78  5162.3   210.3  5302.6  215.94  5332.6  218.08  5352.7  218.59
  5358.4  220.29  5363.4  220.37  5382.7  227.37  5392.8  229.28  5408.4  229.63
#Mann= 5 ,-1 , 0
  4496.8     .17       0  4668.9     .15       0  5019.6     .09       0
  5049.6     .15       0  5110.1     .11       0
Bank Sta=5019.6,5049.6
XS Rating Curve= 0 ,0
Exp/Cntr=0.3,0.1

Type RM Length L Ch R = 1 ,1000    ,500,500,500
XS GIS Cut Line= 3
      3834117.27     10125311.38      3834196.36     10124941.17
      3834101.33     10124673.49
#Sta/Elev= 30
       0  216.66    20.8  215.26    41.2  215.36   169.7  210.54   214.1  209.96
   225.3  210.65   263.6  209.62   268.7   210.2   296.9  208.74   318.2  208.61
     348  209.68   362.6  209.16   368.4  207.87   376.1  202.89   381.3  202.89
   386.5  205.67   391.8  205.98   399.9  209.33   431.7  208.68   453.5  209.96
   473.8  209.89   484.8  208.86   566.4   213.1   602.5  213.52   612.1   215.1
   622.7  218.18   628.1  221.77   633.4  221.85   643.9  224.13   661.2  224.75
#Mann= 3 , 0 , 0
       0     .15       0   362.6     .09       0   399.9     .15       0
Bank Sta=362.6,399.9
XS Rating Curve= 0 ,0
Exp/Cntr=0.3,0.1

Type RM Length L Ch R = 1 ,500     ,0,0,0
BEGIN DESCRIPTION:
STEWARTS CREEK TRIBUTARY NO 1 1.0
END DESCRIPTION:
XS GIS Cut Line= 3
      3834439.88     10125241.19      3834624.02     10124941.81
      3834590.92     10124668.28
#Sta/Elev= 30
  4644.7  216.27  4671.8  216.01  4715.3  214.23  4738.8  213.95  4776.3  211.78
  4787.8  212.37  4839.9  209.37  4845.8  209.62  4855.3  208.81  4888.5   207.9
  4903.7  206.94  4919.2  207.48  4926.6  208.35  4961.8  208.21  4971.3  206.89
  4977.1  207.54 4981.54205.6286  4992.4  201.95  4997.7  201.95  5003.9  205.64
  5017.1  207.37  5037.2  205.97  5092.3  208.73  5172.8  211.17  5208.4   208.6
  5218.5  208.43  5228.6  209.67  5232.9  210.84  5248.7  214.24  5271.7  214.63
#Mann= 7 ,-1 , 0
  4644.7     .17       0  4776.3     .15       0  4888.5     .11       0
 4981.54     .09       0  5003.9     .11       0  5092.3     .15       0
  5232.9     .11       0
Bank Sta=4981.54,5003.9
XS Rating Curve= 0 ,0
Exp/Cntr=0.3,0.1

Chan Stop Cuts=-1
Use User Specified Reach Order=0
Composite Channel Slope=5

--- STEWARTS CREEK TRIBUTARY NO 1.g10 (geometry) ---

Geom Title=Existing Conditions
Program Version=4.10

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
River Reach=STEWARTS CREEK T,Reach-1

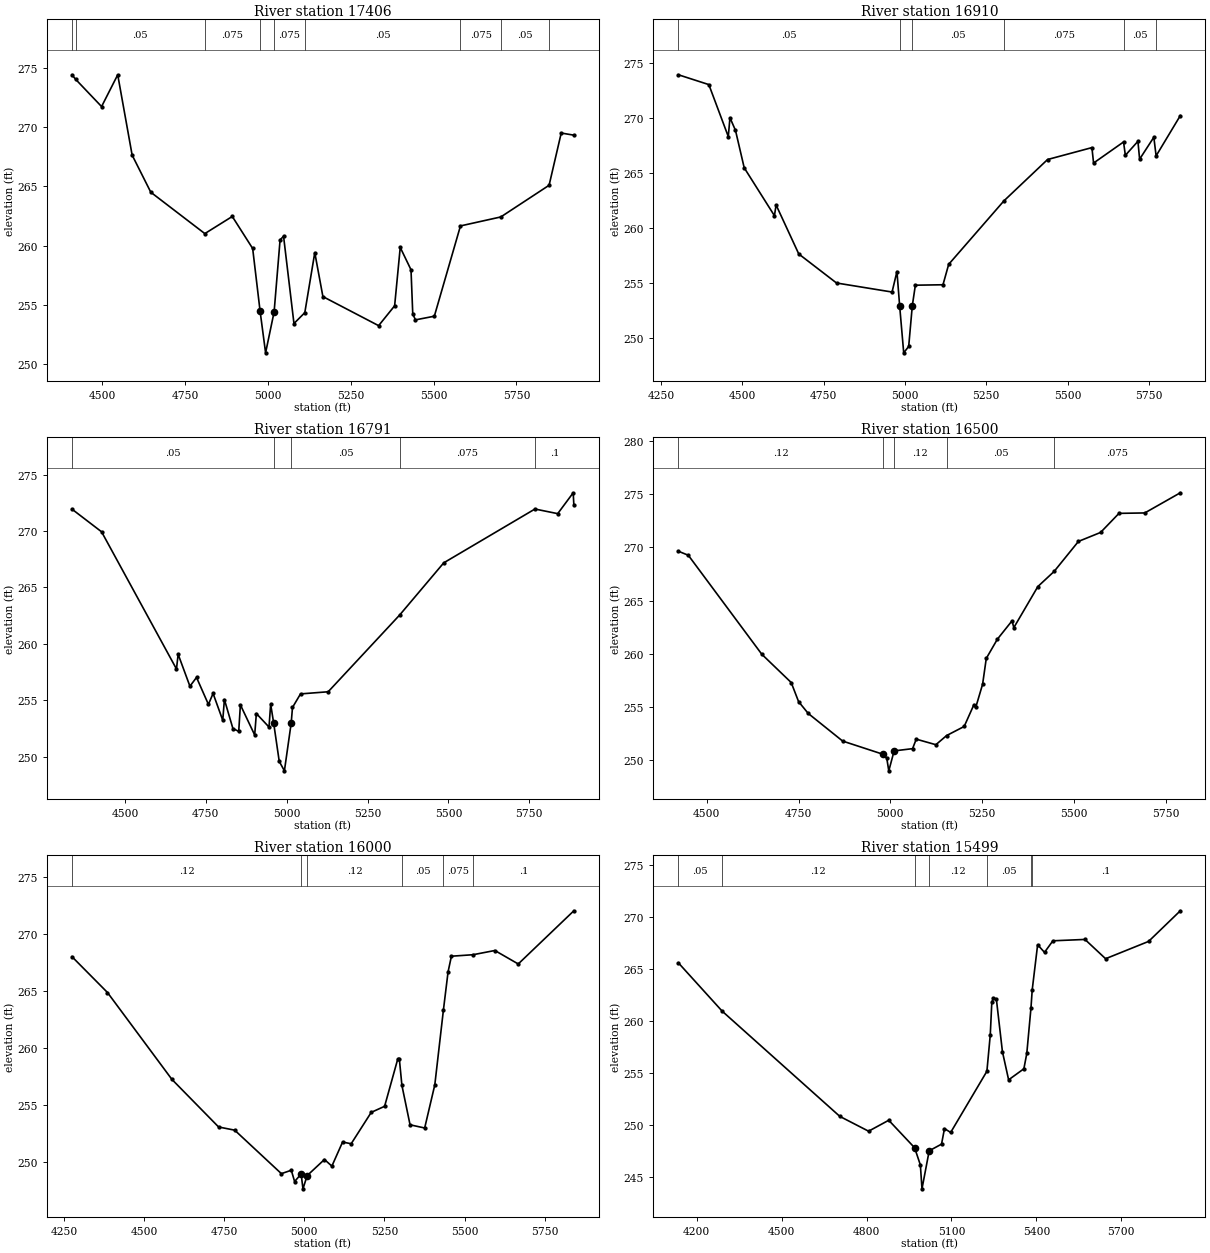
Type RM Length L Ch R = 1 ,17406   ,496,496,496
BEGIN DESCRIPTION:
STEWARTS CREEK TRIBUTARY NO 1 33.0
END DESCRIPTION:
XS GIS Cut Line= 3
      3827310.07     10130516.67      3826733.23     10130644.83
      3825851.43     10130371.14
#Sta/Elev= 30
  4409.1  274.45  4420.1  274.07  4498.5  271.76  4547.2  274.45  4590.7  267.65
    4647  264.51    4810  261.01  4892.8  262.46  4954.3  259.75 4976.78 254.432
  4993.3  250.92 5019.02 254.385    5037  260.47  5047.5  260.79  5078.9   253.4
  5111.6  254.32  5141.7   259.4  5166.2  255.68  5334.3  253.22  5382.6   254.9
  5399.5  259.84    5432  257.95  5437.3  254.21  5445.4  253.71  5502.4  254.02
  5581.2  261.66    5703  262.42  5848.6   265.1  5885.2  269.52  5923.3  269.34
#Mann= 9 ,-1 , 0
  4409.1    .075       0  4420.1     .05       0    4810    .075       0
 4976.78     .07       0 5019.02    .075       0  5111.6     .05       0
  5581.2    .075       0    5703     .05       0  5848.6    .075       0
Bank Sta=4976.78,5019.02
XS Rating Curve= 0 ,0
Exp/Cntr=0.3,0.1

Type RM Length L Ch R = 1 ,16910   ,119,119,119
BEGIN DESCRIPTION:
STEWARTS CREEK TRIBUTARY NO 1 32.0
END DESCRIPTION:
XS GIS Cut Line= 3
      3827359.23     10130012.59      3826679.41     10130161.32
      3825852.63     10130343.43
#Sta/Elev= 30
  4304.1  273.89  4397.6     273  4457.4  268.29  4462.5     270  4479.5  268.85
  4506.3  265.46  4599.2  261.12  4604.3  262.09    4674  257.65    4790  255.02
  4960.7   254.2  4975.7  256.06    4984 252.953  4996.5  248.69  5011.8  249.27
  5022.9 252.957  5032.3  254.82  5117.2  254.86  5134.7  256.71  5304.4  262.46
  5438.6  266.21  5574.9  267.29    5580  265.89  5672.1   267.8  5677.7  266.59
  5716.3  267.86  5721.5  266.24  5765.2  268.23  5772.2  266.54  5846.6  270.19
#Mann= 6 ,-1 , 0
  4304.1     .05       0    4984     .07       0  5022.9     .05       0
  5304.4    .075       0  5672.1     .05       0  5772.2    .075       0
Bank Sta=4984,5022.9
XS Rating Curve= 0 ,0
Exp/Cntr=0.3,0.1

Type RM Length L Ch R = 1 ,16791   ,291,291,291
BEGIN DESCRIPTION:
STEWARTS CREEK TRIBUTARY NO 1 31.5
END DESCRIPTION:
XS GIS Cut Line= 3
       3827354.4     10129907.28       3826705.2      10130046.7
      3825840.36     10130246.42
#Sta/Elev= 30
    4336  271.93  4427.6  269.92  4659.1  257.76  4664.3  259.06  4700.7  256.23
  4721.1  257.01  4757.9  254.62  4772.3  255.59  4802.2  253.21  4807.3  255.05
  4833.6  252.48  4851.6  252.23  4856.7  254.58  4900.9  251.91  4906.1  253.81
  4945.2  252.61  4950.3  254.63 4959.48 252.991  4976.8  249.57  4992.8  248.73
 5013.75 252.958  5017.8  254.35  5042.6  255.55  5128.1  255.74  5349.3  262.55
  5485.4  267.17  5767.3  271.94  5837.7  271.53  5885.6  273.38  5887.6   272.3
#Mann= 5 ,-1 , 0
    4336     .05       0 4959.48     .07       0 5013.75     .05       0
  5349.3    .075       0  5767.3      .1       0
Bank Sta=4959.48,5013.75
XS Rating Curve= 0 ,0
Exp/Cntr=0.3,0.1

Type RM Length L Ch R = 1 ,16500   ,500,500,500
BEGIN DESCRIPTION:
STEWARTS CREEK TRIBUTARY NO 1 31.0
END DESCRIPTION:
XS GIS Cut Line= 3
      3827364.77     10129834.37      3826788.24     10129804.61
       3826001.5     10129878.52
#Sta/Elev= 30
  4422.7  269.62  4449.7  269.24  4649.9  259.96    4730  257.31  4750.1  255.52
  4776.4  254.41  4870.2  251.82  4980.4  250.58  4990.4  250.21  4995.9  249.03
  5010.4   250.9  5060.7  251.11  5070.7     252  5124.2  251.48  5153.5  252.34
  5201.3  253.19  5227.9  255.24  5232.9  254.99  5251.5  257.15  5261.5  259.57
  5291.7  261.37  5331.6  263.09  5336.6  262.46  5402.1  266.31  5446.5  267.73
  5512.6  270.54  5572.9  271.38  5623.1  273.17  5693.4  273.21  5790.2   275.1
#Mann= 5 ,-1 , 0
  4422.7     .12       0  4980.4     .03       0  5010.4     .12       0
  5153.5     .05       0  5446.5    .075       0
Bank Sta=4980.4,5010.4
XS Rating Curve= 0 ,0
Exp/Cntr=0.3,0.1

Type RM Length L Ch R = 1 ,16000   ,501,501,501
BEGIN DESCRIPTION:
STEWARTS CREEK TRIBUTARY NO 1 30.0
END DESCRIPTION:
XS GIS Cut Line= 3
      3827448.06     10129579.16      3826738.24      10129432.6
       3825931.4     10129669.86
#Sta/Elev= 30
  4275.2  267.99    4386  264.85    4587  257.24  4732.7  253.07  4782.9  252.79
  4928.6  248.98  4959.5  249.28  4969.8  248.29  4990.2  248.95  4995.9  247.65
    5009  248.81  5062.9  250.22  5086.1  249.64  5119.5  251.75  5146.3   251.6
  5208.9  254.35  5250.6  254.88  5291.5  259.01  5296.7  258.99  5304.6  256.71
    5330  253.26  5375.6  252.98  5407.2  256.76  5434.2  263.35  5448.6  266.66
    5459  268.03  5526.4  268.16  5594.5  268.53  5667.5  267.35    5841  272.01
#Mann= 6 ,-1 , 0
  4275.2     .12       0  4990.2     .03       0    5009     .12       0
  5304.6     .05       0  5434.2    .075       0  5526.4      .1       0
Bank Sta=4990.2,5009
XS Rating Curve= 0 ,0
Exp/Cntr=0.3,0.1

Type RM Length L Ch R = 1 ,15499   ,486,486,486
BEGIN DESCRIPTION:
STEWARTS CREEK TRIBUTARY NO 1 29.0
END DESCRIPTION:
XS GIS Cut Line= 3
      3827468.94      10129222.4      3826618.24     10129066.36
      3825773.61     10129402.09
#Sta/Elev= 30
  4135.1  265.59  4289.7  260.96  4705.6  250.86  4807.2  249.44  4878.4  250.49
  4969.9  247.85  4990.2   246.2  4995.9  243.91  5021.4  247.56    5065   248.2
  5075.4  249.69  5097.3  249.32  5225.3  255.19  5237.2  258.67  5242.7  261.81
  5248.1   262.2  5258.7  262.14  5280.2  257.07  5302.1  254.37    5356  255.43
  5366.3   256.9  5381.1  261.28  5385.5  263.01  5404.6  267.33  5428.9   266.6
  5458.6  267.71  5571.9  267.84  5644.8  265.99  5796.7  267.65  5908.9  270.59
#Mann= 7 ,-1 , 0
  4135.1     .05       0  4289.7     .12       0  4969.9     .07       0
  5021.4     .12       0  5225.3     .05       0  5381.1    .075       0
  5385.5      .1       0
Bank Sta=4969.9,5021.4
XS Rating Curve= 0 ,0
Exp/Cntr=0.3,0.1

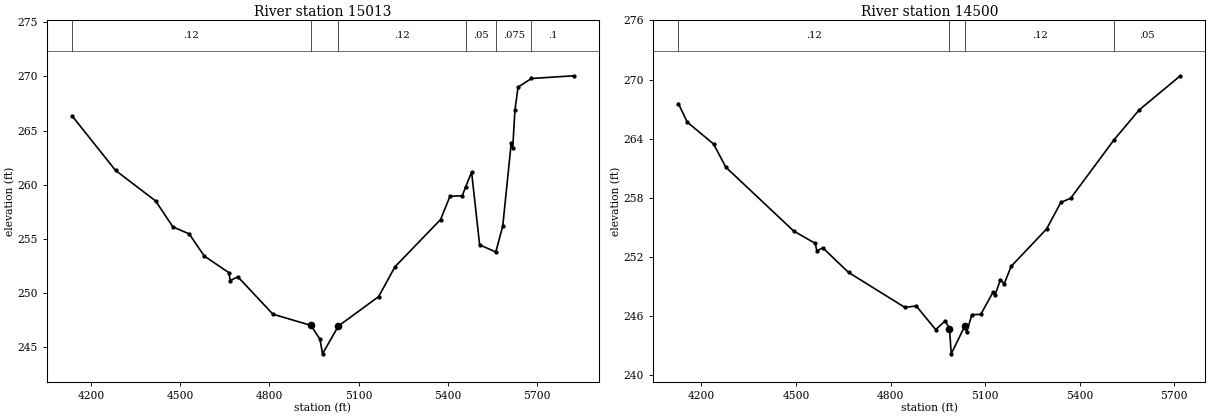
Type RM Length L Ch R = 1 ,15013   ,513,513,513
BEGIN DESCRIPTION:
STEWARTS CREEK TRIBUTARY NO 1 28.0
END DESCRIPTION:
XS GIS Cut Line= 3
      3827573.09     10128907.29      3826728.24     10128726.86
      3825937.68     10128498.43
#Sta/Elev= 30
  4136.1  266.37  4282.5  261.32  4417.5  258.49  4475.4   256.1  4530.1  255.45
  4581.1   253.4    4663  251.88  4668.3  251.14  4693.6  251.49  4811.7  248.03
    4939     247  4969.7  245.72  4978.2  244.37  5031.6  246.94  5166.9  249.66
  5221.6  252.41  5375.1  256.78  5406.4  258.92    5448  258.98    5459  259.77
  5479.2  261.16  5506.2  254.44  5560.6  253.78  5583.9  256.17  5612.3  263.81
  5617.5  263.42  5624.9  266.89  5635.4  269.01  5680.5  269.81  5822.9  270.06
#Mann= 6 ,-1 , 0
  4136.1     .12       0    4939     .07       0  5031.6     .12       0
    5459     .05       0  5560.6    .075       0  5680.5      .1       0
Bank Sta=4939,5031.6
XS Rating Curve= 0 ,0
Exp/Cntr=0.3,0.1

Type RM Length L Ch R = 1 ,14500   ,513,513,513
BEGIN DESCRIPTION:
STEWARTS CREEK TRIBUTARY NO 1 27.0
END DESCRIPTION:
XS GIS Cut Line= 3
      3827685.07     10128579.16      3826832.29     10128392.81
      3826185.08     10128079.17
#Sta/Elev= 30
  4127.1  267.57    4155  265.69  4238.6  263.47  4277.4  261.12  4492.7  254.64
  4561.2  253.39  4566.3  252.61  4584.9  252.94  4666.8  250.44    4845   246.9
  4881.7  247.03  4943.1  244.64  4973.8  245.53    4987   244.7  4992.6  242.18
  5035.5     245  5041.1  244.38  5058.1  246.15  5086.3  246.19  5125.9  248.48
  5131.4  248.14  5148.4  249.69  5160.5  249.29  5182.7  251.06    5295  254.85
  5340.2  257.54  5371.6  257.97  5509.3  263.91  5588.5  266.92  5719.2  270.39
#Mann= 4 ,-1 , 0
  4127.1     .12       0    4987     .07       0  5035.5     .12       0
  5509.3     .05       0
Bank Sta=4987,5035.5
XS Rating Curve= 0 ,0
Exp/Cntr=0.3,0.1