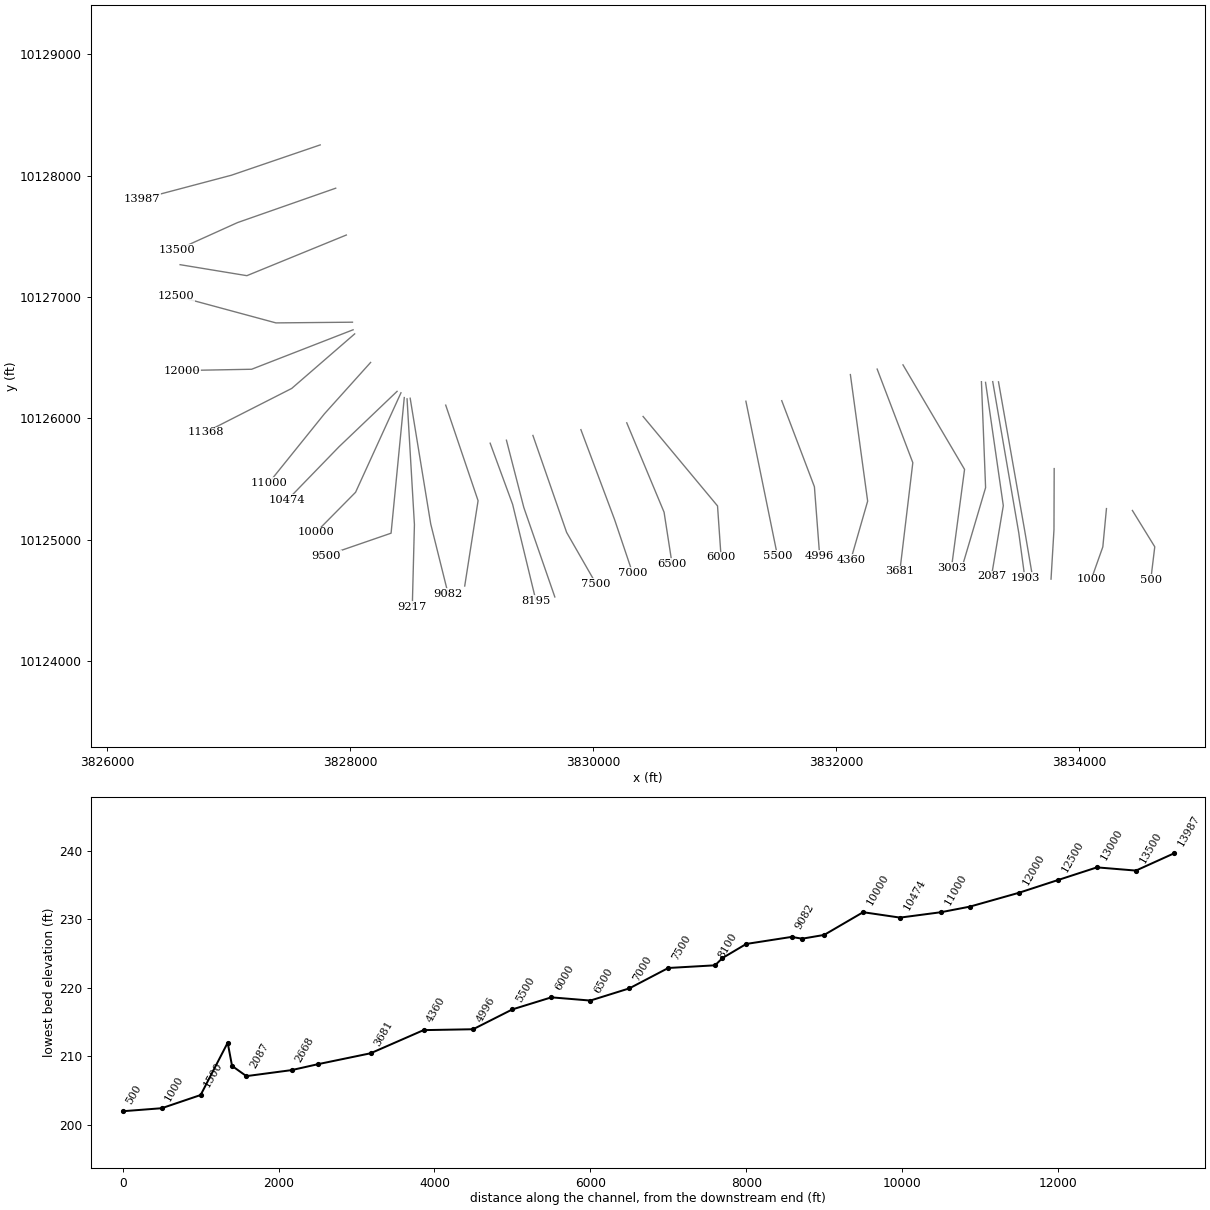
HEC-RAS study STEWARTS CREEK TRIBUTARY NO 1.prj: STEWARTS CREEK TRIBUTARY NO 1 Base Level Engineering

--- STEWARTS CREEK TRIBUTARY NO 1.g10 (geometry) --- (continued)

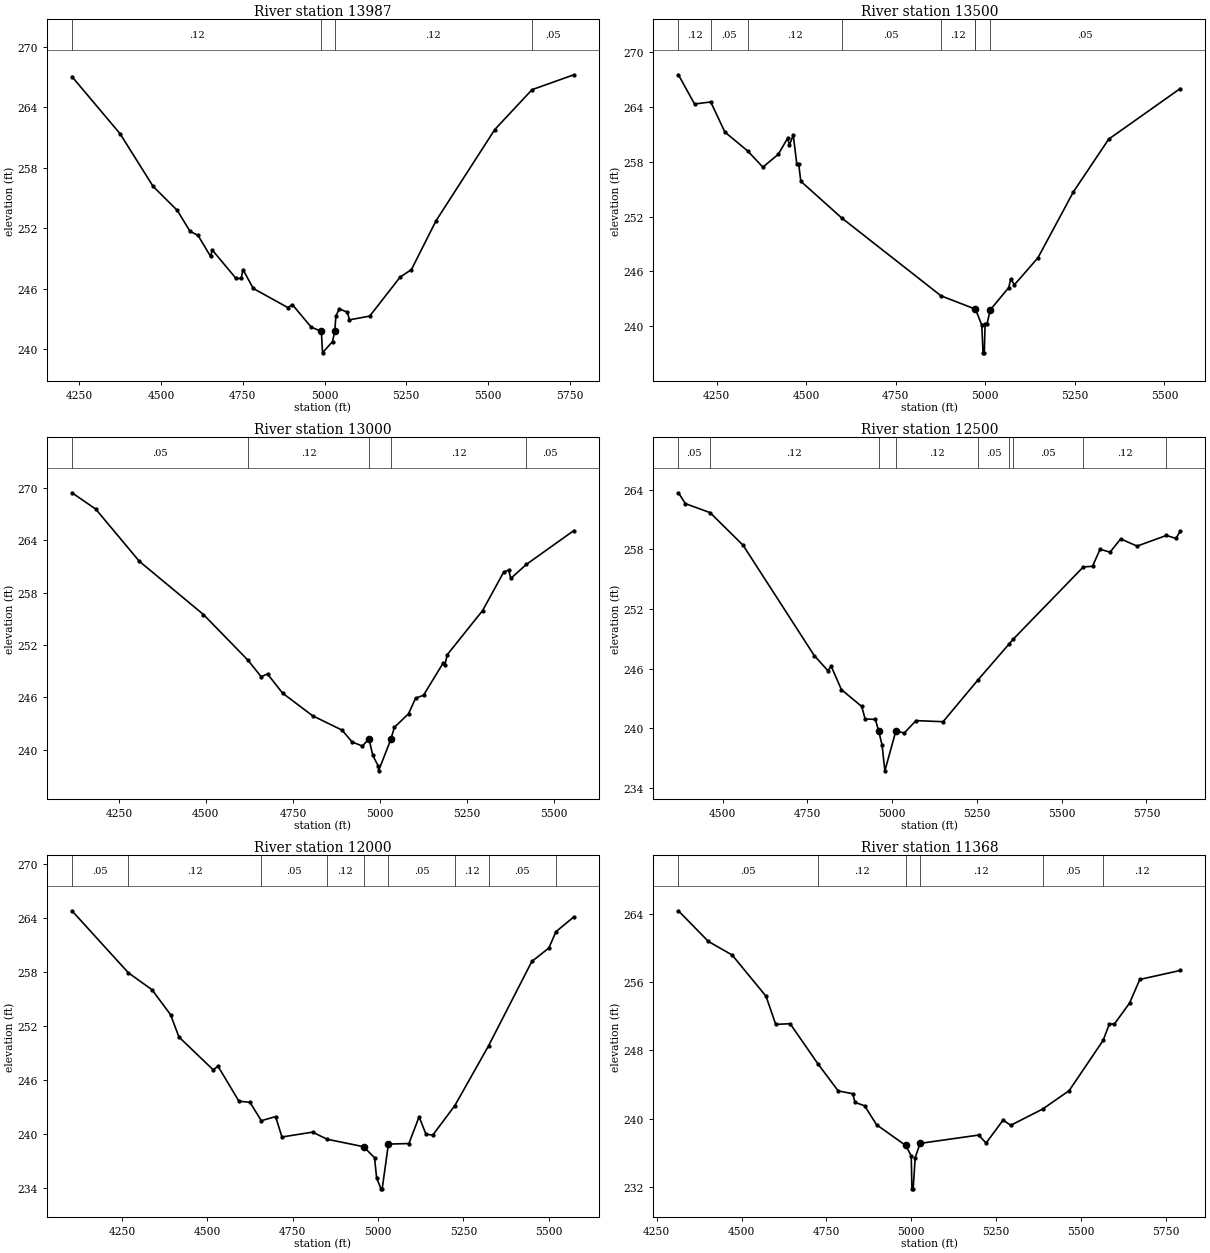
Type RM Length L Ch R = 1 ,13987   ,487,487,487
BEGIN DESCRIPTION:
STEWARTS CREEK TRIBUTARY NO 1 26.0
END DESCRIPTION:
XS GIS Cut Line= 3
      3827752.77     10128253.64      3827021.41     10128003.69
      3826284.05     10127808.33
#Sta/Elev= 30
  4227.1  267.07  4374.6  261.38  4475.4  256.16  4549.3  253.78  4588.5  251.69
  4612.7   251.3  4651.1  249.21  4656.4  249.84    4729  247.02  4745.1  247.01
  4750.3   247.9  4781.8  246.02  4887.5  244.12  4901.6  244.41    4959  242.18
  4990.3  241.75  4993.8  239.62  5024.4  240.74 5031.13 241.777  5034.8  243.28
  5045.1  243.99  5069.9  243.65  5076.1   242.9  5138.2  243.27  5231.3  247.15
  5265.8  247.89    5341  252.74  5520.9  261.81  5634.9  265.77  5762.8  267.25
#Mann= 4 ,-1 , 0
  4227.1     .12       0  4990.3     .07       0 5031.13     .12       0
  5634.9     .05       0
Bank Sta=4990.3,5031.13
XS Rating Curve= 0 ,0
Exp/Cntr=0.3,0.1

Type RM Length L Ch R = 1 ,13500   ,500,500,500
BEGIN DESCRIPTION:
STEWARTS CREEK TRIBUTARY NO 1 25.0
END DESCRIPTION:
XS GIS Cut Line= 3
      3827880.36     10127896.86       3827071.7      10127613.4
      3826575.68     10127389.05
#Sta/Elev= 30
  4143.1  267.48  4188.1  264.29  4233.3  264.51  4272.9  261.22  4336.5  259.16
  4378.9  257.39  4422.1   258.8  4447.8  260.54  4453.1   259.8  4463.7   260.9
  4473.5  257.77  4478.8  257.77  4484.8  255.85  4598.5  251.86  4876.2  243.34
    4971   241.9  4972.3  241.91  4990.1  240.13  4993.6  237.11  4997.1  237.11
  4999.4   240.3  5004.9   240.3  5013.7   241.8  5065.4  244.24  5070.9  245.19
  5081.1  244.54  5146.9  247.49  5245.7  254.68  5344.5  260.45  5544.4  265.98
#Mann= 8 ,-1 , 0
  4143.1     .12       0  4233.3     .05       0  4336.5     .12       0
  4598.5     .05       0  4876.2     .12       0    4971     .05       0
  4972.3     .07       0  5013.7     .05       0
Bank Sta=4972.3,5013.7
XS Rating Curve= 0 ,0
Exp/Cntr=0.3,0.1

Type RM Length L Ch R = 1 ,13000   ,500,500,500
BEGIN DESCRIPTION:
STEWARTS CREEK TRIBUTARY NO 1 24.0
END DESCRIPTION:
XS GIS Cut Line= 3
      3827967.83     10127511.06      3827148.98     10127176.12
      3826599.19     10127266.66
#Sta/Elev= 30
  4115.3  269.44  4183.4  267.58  4308.9  261.59  4493.1  255.49  4621.1  250.25
  4658.8  248.37  4677.1  248.68  4720.3  246.49  4806.7  243.89  4891.1  242.25
  4920.5  240.88  4949.9  240.42  4968.6  241.26  4979.6  239.34  4995.9  238.08
  4996.2  237.58  5031.5   241.2  5041.7  242.57  5082.2  244.12  5102.5   245.9
  5125.3  246.24  5181.4  249.91  5186.5   249.7  5193.7   250.9  5295.1  255.95
  5355.9  260.37    5370  260.58  5376.1  259.63    5421  261.24  5557.2  265.11
#Mann= 5 ,-1 , 0
  4115.3     .05       0  4621.1     .12       0  4968.6     .07       0
  5031.5     .12       0    5421     .05       0
Bank Sta=4968.6,5031.5
XS Rating Curve= 0 ,0
Exp/Cntr=0.3,0.1

Type RM Length L Ch R = 1 ,12500   ,500,500,500
BEGIN DESCRIPTION:
STEWARTS CREEK TRIBUTARY NO 1 23.0
END DESCRIPTION:
XS GIS Cut Line= 3
      3828018.41     10126792.71      3827388.24     10126786.94
      3826567.92     10127008.85
#Sta/Elev= 30
  4369.8  263.69  4390.4   262.6  4463.3  261.69  4560.4  258.42  4770.4  247.32
  4810.4  245.81  4820.4  246.24  4850.4   243.9  4910.4   242.2  4920.4  240.94
  4950.4  240.91  4960.4  239.73  4970.4   238.3  4978.6  235.73  5010.8  239.72
  5035.8  239.54  5070.5  240.78  5150.2  240.67  5253.8   244.9  5344.2  248.46
  5357.1  248.97  5563.7  256.23  5590.9   256.3  5613.1  258.01  5642.6  257.72
  5673.8  259.05  5722.3  258.33  5808.9   259.4  5836.8   259.1  5849.8  259.84
#Mann= 9 ,-1 , 0
  4369.8     .05       0  4463.3     .12       0  4960.4     .07       0
  5010.8     .12       0  5253.8     .05       0  5344.2     .12       0
  5357.1     .05       0  5563.7     .12       0  5808.9     .05       0
Bank Sta=4960.4,5010.8
XS Rating Curve= 0 ,0
Exp/Cntr=0.3,0.1

Type RM Length L Ch R = 1 ,12000   ,632,632,632
BEGIN DESCRIPTION:
STEWARTS CREEK TRIBUTARY NO 1 22.0
END DESCRIPTION:
XS GIS Cut Line= 3
      3828023.64     10126730.21      3827188.24     10126404.93
      3826614.73     10126394.27
#Sta/Elev= 30
  4103.5  264.81    4269   257.9  4337.9  256.03  4392.3  253.25  4416.8  250.77
  4517.5   247.1    4531  247.53  4592.6  243.62  4624.8   243.5  4658.3  241.45
  4699.9  241.91  4718.6  239.64  4808.3  240.18  4850.8  239.39  4957.5  238.56
  4989.7  237.34  4995.9   235.1  5008.6  233.87  5012.2  233.87  5030.4  238.85
  5090.4  238.91  5120.4  241.89  5140.4  239.95  5160.4  239.85  5225.1  243.14
  5323.7  249.78  5450.5  259.17  5500.5  260.67    5521  262.48  5573.6  264.13
#Mann= 9 ,-1 , 0
  4103.5     .05       0    4269     .12       0  4658.3     .05       0
  4850.8     .12       0  4957.5     .07       0  5030.4     .05       0
  5225.1     .12       0  5323.7     .05       0    5521    .075       0
Bank Sta=4957.5,5030.4
XS Rating Curve= 0 ,0
Exp/Cntr=0.3,0.1

Type RM Length L Ch R = 1 ,11368   ,368,368,368
BEGIN DESCRIPTION:
STEWARTS CREEK TRIBUTARY NO 1 21.0
END DESCRIPTION:
XS GIS Cut Line= 3
      3828036.61     10126696.33      3827518.24     10126246.86
       3826811.5     10125887.18
#Sta/Elev= 30
  4313.9  264.32  4402.1  260.74  4472.3  259.15  4572.1  254.34  4600.6  251.05
  4643.1  251.13  4725.1  246.44  4784.8  243.28  4827.6  242.95  4834.2  241.94
  4862.7  241.54  4897.8  239.33  4983.3  236.92    5000   235.7    5002  231.84
  5005.7  231.84  5011.7  235.49  5026.1  237.15  5198.5  238.12  5220.7  237.19
  5270.8  239.88  5293.1  239.26  5387.3  241.16  5465.4  243.31  5565.5  249.18
  5583.9   251.1  5598.9   251.1  5643.4  253.54  5673.7   256.3    5793  257.35
#Mann= 6 ,-1 , 0
  4313.9     .05       0  4725.1     .12       0  4983.3     .07       0
  5026.1     .12       0  5387.3     .05       0  5565.5     .12       0
Bank Sta=4983.3,5026.1
XS Rating Curve= 0 ,0
Exp/Cntr=0.3,0.1

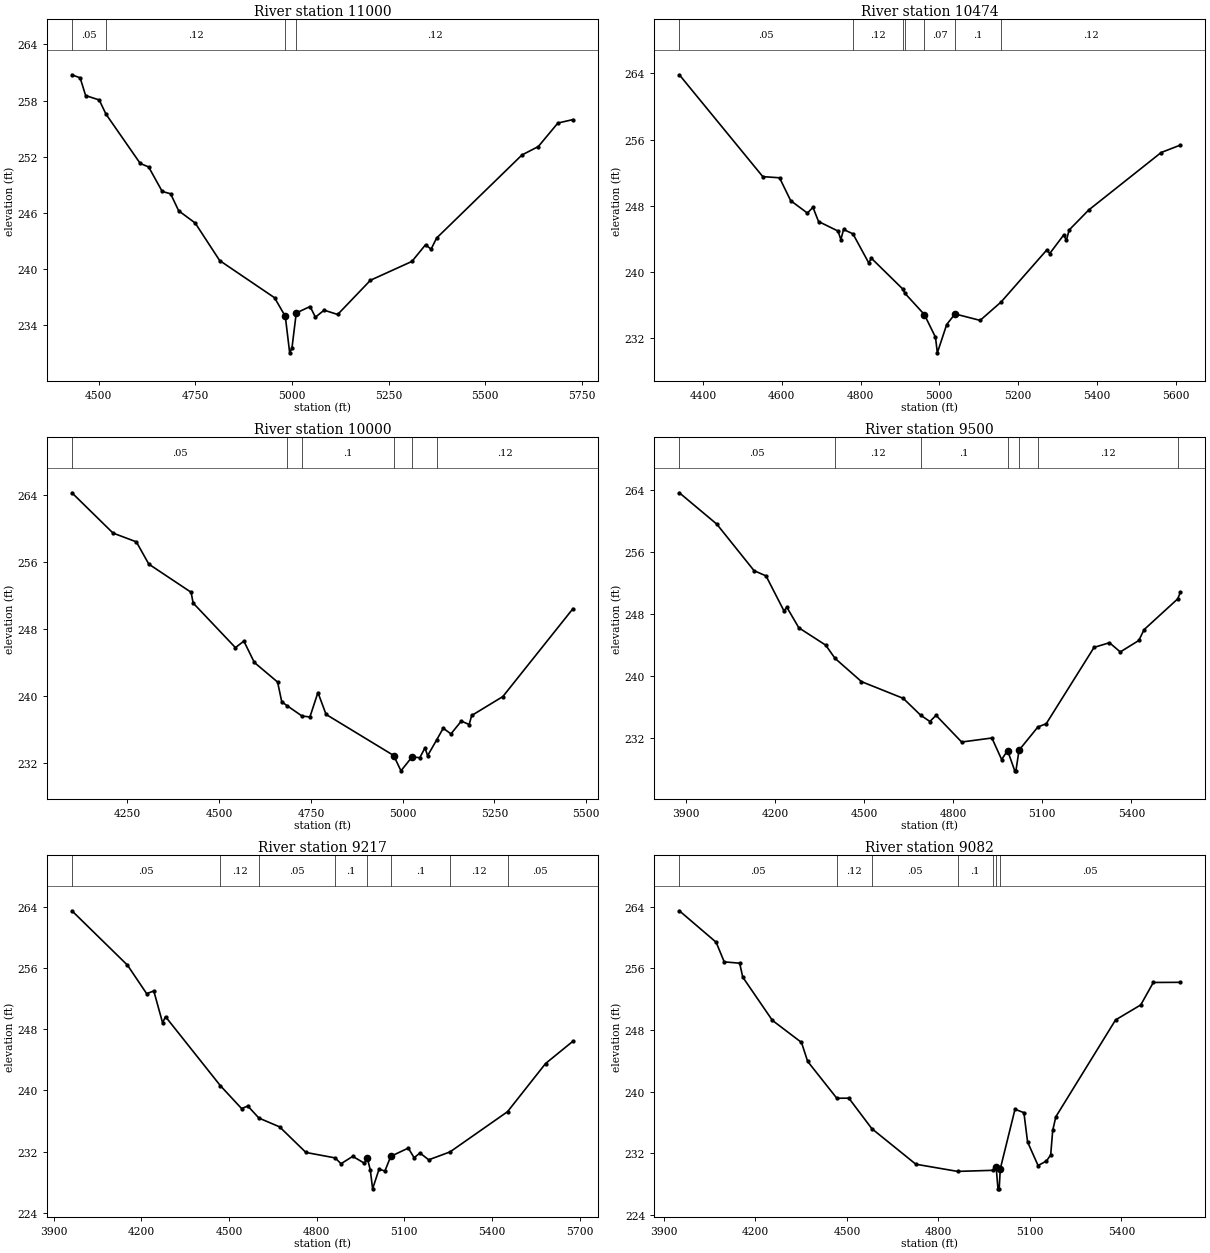
Type RM Length L Ch R = 1 ,11000   ,526,526,526
BEGIN DESCRIPTION:
STEWARTS CREEK TRIBUTARY NO 1 20.0
END DESCRIPTION:
XS GIS Cut Line= 3
      3828167.85     10126461.07      3827787.51     10126037.59
      3827331.91     10125471.32
#Sta/Elev= 30
  4430.8  260.75  4452.1  260.42  4466.3  258.53  4501.4  258.06    4519  256.54
  4607.6  251.27  4629.3   250.9  4664.4  248.28  4686.1  248.03    4707  246.21
  4749.6  244.91  4813.1  240.89    4955  236.92  4982.8  234.93  4994.1  231.03
    5000  231.53  5011.1  235.29  5046.9  235.98  5060.7  234.84  5083.1  235.59
  5118.3  235.13  5203.1  238.79  5310.3   240.8  5345.5  242.58  5359.9  242.11
  5374.2   243.3    5595  252.18  5637.3  253.08  5687.8  255.59  5726.8  255.96
#Mann= 4 ,-1 , 0
  4430.8     .05       0    4519     .12       0  4982.8     .07       0
  5011.1     .12       0
Bank Sta=4982.8,5011.1
XS Rating Curve= 0 ,0
Exp/Cntr=0.3,0.1

Type RM Length L Ch R = 1 ,10474   ,474,474,474
BEGIN DESCRIPTION:
STEWARTS CREEK TRIBUTARY NO 1 19.0
END DESCRIPTION:
XS GIS Cut Line= 3
       3828385.7     10126222.81      3827908.24     10125766.86
      3827482.46     10125327.39
#Sta/Elev= 30
  4339.8  263.82  4551.7  251.52  4594.2  251.38  4622.5  248.62  4664.9  247.12
  4679.1  247.81  4693.2   246.1  4742.6  244.95  4749.9  243.92  4756.8  245.14
  4780.6  244.61  4820.6  241.11  4827.5  241.66  4907.9  237.91  4912.2  237.45
  4961.8  234.87  4990.1  232.13  4994.9  230.24  5018.6  233.66  5039.7  234.94
  5103.5  234.16  5156.7  236.38    5273  242.68  5280.2  242.23  5315.4  244.46
  5322.6  243.85  5329.6  245.08  5379.2  247.49  5563.1  254.43  5611.9  255.33
#Mann= 7 ,-1 , 0
  4339.8     .05       0  4780.6     .12       0  4907.9     .05       0
  4912.2      .1       0  4961.8     .07       0  5039.7      .1       0
  5156.7     .12       0
Bank Sta=4961.8,5039.7
XS Rating Curve= 0 ,0
Exp/Cntr=0.3,0.1

Type RM Length L Ch R = 1 ,10000   ,500,500,500
BEGIN DESCRIPTION:
STEWARTS CREEK TRIBUTARY NO 1 18.0
END DESCRIPTION:
XS GIS Cut Line= 3
      3828417.86      10126211.1      3828043.99     10125391.11
      3827717.85     10125061.07
#Sta/Elev= 30
  4098.8  264.23  4210.8  259.42  4274.4  258.37  4308.4  255.71  4423.6  252.35
  4429.1  251.07  4544.4  245.74  4567.4  246.52  4595.9  243.97  4659.3  241.63
  4670.6  239.27  4684.8  238.82  4725.6  237.58  4747.3  237.46  4769.2  240.38
  4791.3  237.77  4975.6  232.86  4995.4  231.03  5025.6  232.69  5046.8   232.6
  5060.9  233.77    5068  232.84  5093.1  234.75  5110.5  236.12  5131.6  235.44
  5159.9  236.97  5181.2  236.56  5188.2  237.64  5273.1   239.9    5464  250.39
#Mann= 6 ,-1 , 0
  4098.8     .05       0  4684.8     .12       0  4725.6      .1       0
  4975.6     .03       0  5025.6      .1       0  5093.1     .12       0
Bank Sta=4975.6,5025.6
XS Rating Curve= 0 ,0
Exp/Cntr=0.3,0.1

Type RM Length L Ch R = 1 ,9500    ,283,283,283
BEGIN DESCRIPTION:
STEWARTS CREEK TRIBUTARY NO 1 17.0
END DESCRIPTION:
XS GIS Cut Line= 3
      3828445.03     10126171.71       3828336.3     10125054.08
       3827802.3     10124869.81
#Sta/Elev= 30
  3877.1  263.61  4003.1  259.57  4128.9  253.55  4169.1  252.88  4229.4  248.37
  4239.4  248.82  4279.6  246.18  4370.1  243.94  4401.4  242.24  4490.6  239.23
  4631.3  237.07  4689.8   234.9  4721.2  234.08  4741.8  234.88  4828.1  231.43
    4930  231.95  4962.8  229.17  4982.9  230.33    5007  227.71  5010.9  227.71
 5021.42 230.375  5085.1  233.38    5113  233.79  5274.2  243.65  5326.1  244.25
  5362.5  243.06  5424.9  244.54  5442.7  245.94  5555.9  249.91  5564.9  250.76
#Mann= 7 ,-1 , 0
  3877.1     .05       0  4401.4     .12       0  4689.8      .1       0
  4982.9     .07       0 5021.42      .1       0  5085.1     .12       0
  5555.9     .05       0
Bank Sta=4982.9,5021.42
XS Rating Curve= 0 ,0
Exp/Cntr=0.3,0.1

Type RM Length L Ch R = 1 ,9217    ,135,135,135
BEGIN DESCRIPTION:
STEWARTS CREEK TRIBUTARY NO 1 16.0
END DESCRIPTION:
XS GIS Cut Line= 3
      3828467.85     10126161.04      3828528.54     10125124.51
      3828510.94     10124447.44
#Sta/Elev= 30
  3961.7  263.46    4152  256.36  4217.7  252.64  4242.1  252.99  4272.2  248.84
  4282.2  249.64  4469.8  240.64  4542.7  237.64  4564.1  237.97    4602   236.4
  4672.9  235.25    4763  231.91  4862.9   231.2  4883.2  230.44  4923.3   231.4
  4963.4   230.5  4973.4  231.15  4983.4  229.63  4991.4  227.16  5013.4  229.72
  5033.5  229.49  5053.5   231.4  5113.5  232.48  5133.5  231.22  5153.5  231.84
  5183.5  230.95  5256.4  231.98  5453.3  237.23  5583.6  243.52  5677.3  246.43
#Mann= 8 ,-1 , 0
  3961.7     .05       0  4469.8     .12       0    4602     .05       0
  4862.9      .1       0  4973.4     .07       0  5053.5      .1       0
  5256.4     .12       0  5453.3     .05       0
Bank Sta=4973.4,5053.5
XS Rating Curve= 0 ,0
Exp/Cntr=0.3,0.1

Type RM Length L Ch R = 1 ,9082    ,582,582,582
BEGIN DESCRIPTION:
STEWARTS CREEK TRIBUTARY NO 1 16.5
END DESCRIPTION:
XS GIS Cut Line= 3
      3828493.58     10126166.23      3828662.68     10125130.54
      3828805.79     10124554.97
#Sta/Elev= 30
  3950.6  263.45  4071.3  259.37  4097.7  256.83  4148.3  256.66  4158.5  254.85
  4255.6  249.25    4351  246.39  4371.3  243.93  4466.8  239.16  4506.3  239.17
  4581.6  235.22  4725.9  230.61  4862.8  229.68  4978.8  229.82  4989.3  230.19
  4995.2  227.42  4999.2  227.42  5002.7     230    5051  237.73  5080.2  237.29
  5092.2   233.5  5126.6  230.44    5154  231.02    5168  231.82  5174.6  234.99
  5184.9  236.76  5380.7  249.31  5463.2  251.25  5504.4  254.16  5593.1  254.18
#Mann= 7 ,-1 , 0
  3950.6     .05       0  4466.8     .12       0  4581.6     .05       0
  4862.8      .1       0  4978.8     .05       0  4989.3     .07       0
  5002.7     .05       0
Bank Sta=4989.3,5002.7
XS Rating Curve= 0 ,0
Exp/Cntr=0.3,0.1

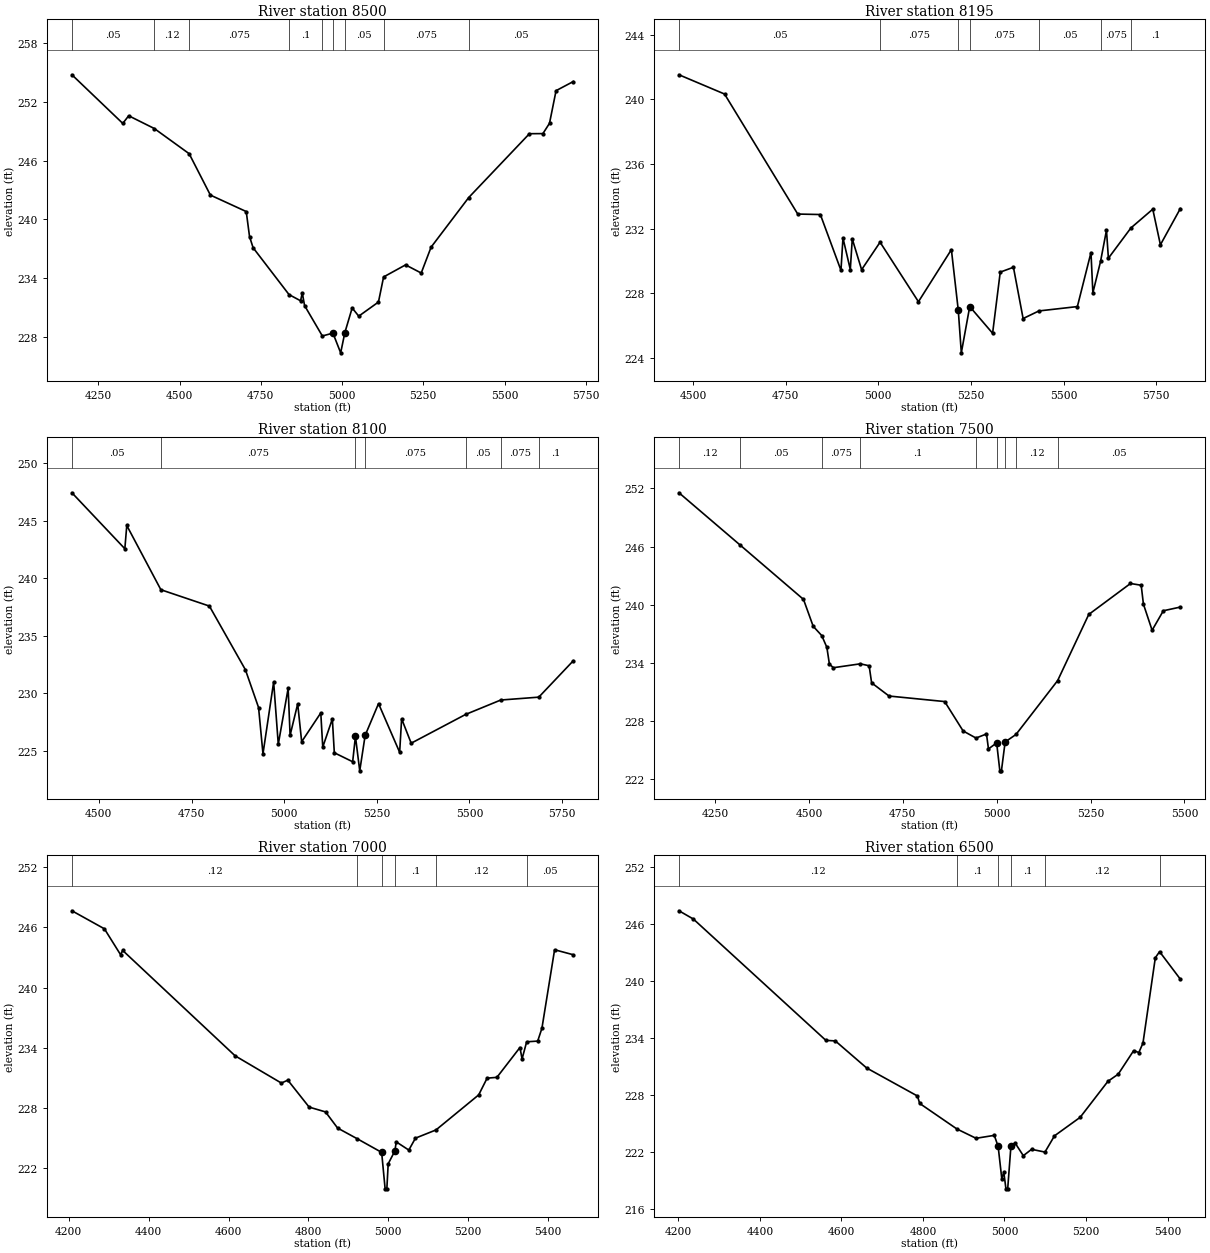
Type RM Length L Ch R = 1 ,8500    ,305,305,305
BEGIN DESCRIPTION:
STEWARTS CREEK TRIBUTARY NO 1 15.0
END DESCRIPTION:
XS GIS Cut Line= 3
      3828786.09     10126109.27      3829052.64     10125321.76
      3828942.59     10124618.72
#Sta/Elev= 30
  4168.6  254.75  4325.1  249.79  4343.3  250.57  4422.1  249.27  4529.4   246.7
  4594.7  242.48  4705.1   240.8  4715.2  238.25  4726.2  237.11  4836.8  232.33
  4872.3   231.7  4877.6   232.5  4884.6  231.21  4939.3  228.11  4971.9   228.4
  4995.7  226.39  5008.6 228.456  5031.1  230.97  5051.3  230.13    5112  231.57
  5127.8  234.13  5195.4  235.36  5243.6  234.53    5274  237.17  5389.8  242.23
  5576.6  248.74  5618.1  248.75  5638.4   249.8  5658.6  253.13  5711.6  254.06
#Mann= 9 ,-1 , 0
  4168.6     .05       0  4422.1     .12       0  4529.4    .075       0
  4836.8      .1       0  4939.3     .05       0  4971.9     .07       0
  5008.6     .05       0  5127.8    .075       0  5389.8     .05       0
Bank Sta=4971.9,5008.6
XS Rating Curve= 0 ,0
Exp/Cntr=0.3,0.1

Type RM Length L Ch R = 1 ,8195    ,95,95,95
BEGIN DESCRIPTION:
Mapping XS 24898910
END DESCRIPTION:
XS GIS Cut Line= 3
      3829152.07     10125795.64      3829337.29     10125290.74
      3829528.81     10124498.77
#Sta/Elev= 30
  4462.2  241.52  4585.1  240.33  4782.6  232.91  4843.6  232.88  4899.2  229.43
  4904.6  231.43  4924.4  229.48  4929.7  231.37  4954.9  229.47  5004.7  231.17
  5108.2  227.49  5197.1  230.71  5215.7  226.96  5223.9  224.33  5246.6  227.19
  5308.3  225.54  5328.9  229.32  5364.5  229.62  5390.6  226.45  5433.2  226.92
    5537  227.19  5573.7  230.53  5578.8  228.04  5599.5  229.98  5615.5  231.91
  5620.7  230.18  5681.4  232.05  5740.4  233.21    5761  231.01  5814.8  233.25
#Mann= 7 ,-1 , 0
  4462.2     .05       0  5004.7    .075       0  5215.7     .07       0
  5246.6    .075       0  5433.2     .05       0  5599.5    .075       0
  5681.4      .1       0
Bank Sta=5215.7,5246.6
XS Rating Curve= 0 ,0
Exp/Cntr=0.3,0.1

Type RM Length L Ch R = 1 ,8100    ,600,600,600
BEGIN DESCRIPTION:
STEWARTS CREEK TRIBUTARY NO 1 14.0
END DESCRIPTION:
XS GIS Cut Line= 3
      3829286.09     10125820.21       3829429.2     10125265.68
      3829684.52     10124528.54
#Sta/Elev= 30
  4427.3  247.42  4570.1  242.56  4575.3  244.58  4667.3     239  4798.2  237.58
  4895.4  232.05  4930.9  228.77  4942.8  224.75  4971.6  230.98  4984.1  225.58
  5010.7  230.43    5016  226.36  5036.5  229.09  5047.2   225.8  5098.8   228.3
  5104.1  225.33    5130  227.78  5135.3  224.84  5184.8  224.06  5192.3  226.26
  5203.9  223.27  5218.5 226.349  5254.6  229.11  5311.6  224.88  5316.9  227.79
  5342.7  225.67  5489.7  228.17  5584.4  229.42    5687  229.67  5780.1  232.83
#Mann= 7 ,-1 , 0
  4427.3     .05       0  4667.3    .075       0  5192.3     .07       0
  5218.5    .075       0  5489.7     .05       0  5584.4    .075       0
    5687      .1       0
Bank Sta=5192.3,5218.5
XS Rating Curve= 0 ,0
Exp/Cntr=0.3,0.1

Type RM Length L Ch R = 1 ,7500    ,500,500,500
BEGIN DESCRIPTION:
STEWARTS CREEK TRIBUTARY NO 1 13.0
END DESCRIPTION:
XS GIS Cut Line= 3
      3829504.15     10125859.49      3829781.68     10125060.31
      3830024.82     10124635.81
#Sta/Elev= 30
    4154  251.54  4316.9  246.15  4485.6  240.55  4511.4  237.78  4534.2  236.82
  4547.8  235.61  4554.6  233.88  4565.2  233.51  4636.9  233.91  4660.4  233.71
    4667  231.95  4713.4  230.59  4861.6  230.02  4910.7  226.99    4945  226.26
  4972.9  226.68  4978.2  225.14    5000  225.76  5008.5  222.88  5012.7  222.88
 5022.57 225.854  5051.5  226.63  5162.4  232.18  5245.3     239  5356.4  242.19
  5384.9  242.01  5390.9  240.06    5414  237.37  5443.9  239.38  5489.2  239.76
#Mann= 9 ,-1 , 0
    4154     .12       0  4316.9     .05       0  4534.2    .075       0
  4636.9      .1       0    4945    .075       0    5000     .07       0
 5022.57    .075       0  5051.5     .12       0  5162.4     .05       0
Bank Sta=5000,5022.57
XS Rating Curve= 0 ,0
Exp/Cntr=0.3,0.1

Type RM Length L Ch R = 1 ,7000    ,500,500,500
BEGIN DESCRIPTION:
STEWARTS CREEK TRIBUTARY NO 1 12.0
END DESCRIPTION:
XS GIS Cut Line= 3
      3829899.12     10125907.23      3830176.75     10125165.37
      3830324.46     10124726.68
#Sta/Elev= 30
  4207.9  247.66  4289.2  245.86  4329.6  243.28    4335   243.7  4616.4  233.18
  4732.2  230.46  4748.3  230.75  4801.7  228.06  4842.7  227.58  4872.9  225.97
  4922.1   224.9  4983.2  223.54  4991.9   219.9  4996.2   219.9  4999.6   222.4
 5016.32 223.686  5019.7  224.59  5051.2  223.77  5067.8  224.96  5119.2  225.78
  5226.1  229.28  5247.2  230.95  5271.7  231.03  5329.4  234.01  5334.7  232.87
  5346.2  234.58  5373.8  234.65  5384.4  235.93  5416.1  243.77  5462.9  243.27
#Mann= 6 ,-1 , 0
  4207.9     .12       0  4922.1      .1       0  4983.2     .07       0
 5016.32      .1       0  5119.2     .12       0  5346.2     .05       0
Bank Sta=4983.2,5016.32
XS Rating Curve= 0 ,0
Exp/Cntr=0.3,0.1

Type RM Length L Ch R = 1 ,6500    ,500,500,500
BEGIN DESCRIPTION:
STEWARTS CREEK TRIBUTARY NO 1 11.0
END DESCRIPTION:
XS GIS Cut Line= 3
      3830276.72     10125963.66        3830584.     10125226.86
      3830649.99     10124800.44
#Sta/Elev= 30
  4201.7  247.39    4237  246.52    4562  233.75  4585.2  233.69  4662.1  230.84
  4786.7  227.89  4792.1  227.11  4883.5  224.42  4930.4  223.44  4975.1  223.75
  4984.6  222.58  4993.5  219.19  4998.5  219.85  5003.7  218.12    5008  218.12
    5016  222.66  5026.1  222.95  5046.3  221.61  5066.6  222.28  5099.4  221.99
  5122.8   223.7  5185.8  225.65  5253.9  229.44  5279.1  230.19    5317  232.67
  5329.7  232.47  5339.8  233.46  5370.1  242.44  5380.5  243.09  5431.5  240.19
#Mann= 6 ,-1 , 0
  4201.7     .12       0  4883.5      .1       0  4984.6     .07       0
    5016      .1       0  5099.4     .12       0  5380.5     .05       0
Bank Sta=4984.6,5016
XS Rating Curve= 0 ,0
Exp/Cntr=0.3,0.1

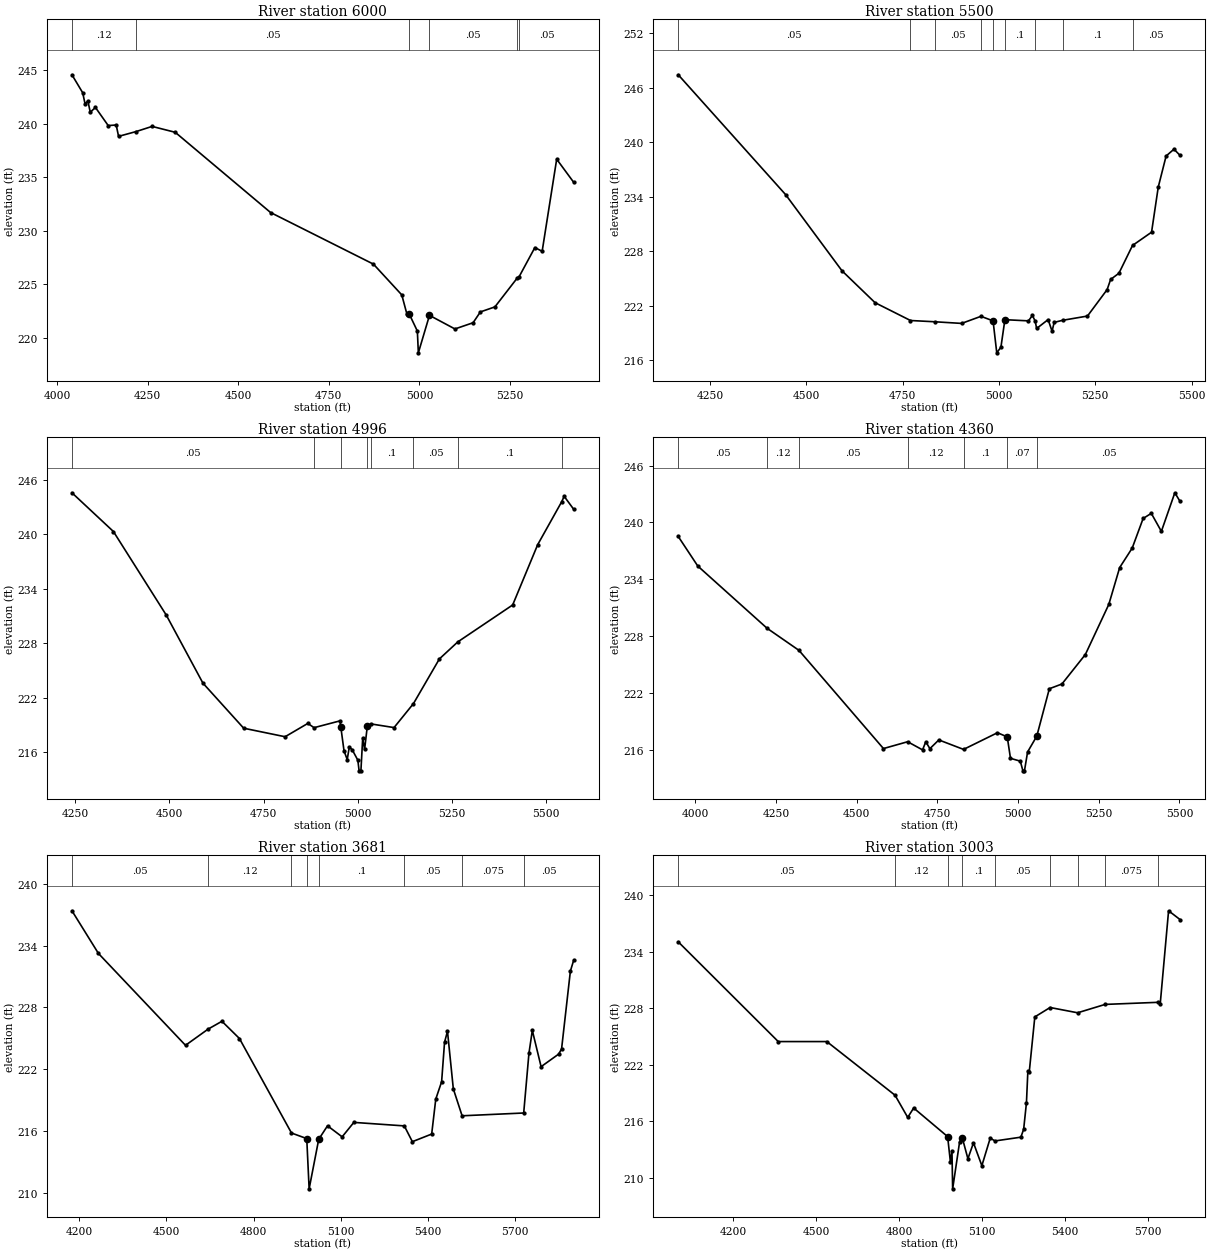
Type RM Length L Ch R = 1 ,6000    ,500,500,500
BEGIN DESCRIPTION:
STEWARTS CREEK TRIBUTARY NO 1 10.0
END DESCRIPTION:
XS GIS Cut Line= 3
      3830411.26     10126015.74      3831024.11     10125278.64
      3831053.51     10124854.26
#Sta/Elev= 30
  4041.4  244.55  4071.1  242.87  4077.6  241.83  4085.4  242.11  4091.9  241.05
  4106.2   241.5  4141.4  239.81  4163.5  239.86    4170   238.8  4218.5  239.25
  4262.5  239.73  4326.3  239.18  4589.3  231.69  4873.1  226.87  4951.2     224
  4965.5  222.19    4972   222.2  4994.2  220.62  4996.9  218.59  5027.6  222.09
  5097.8  220.82  5147.9   221.4    5168  222.41  5208.1  222.88  5269.6  225.57
  5274.9   225.7  5318.3  228.42  5338.4  228.07  5378.5  236.67  5425.4  234.51
#Mann= 6 ,-1 , 0
  4041.4     .12       0  4218.5     .05       0    4972     .07       0
  5027.6     .05       0  5269.6      .1       0  5274.9     .05       0
Bank Sta=4972,5027.6
XS Rating Curve= 0 ,0
Exp/Cntr=0.3,0.1

Type RM Length L Ch R = 1 ,5500    ,504,504,504
BEGIN DESCRIPTION:
STEWARTS CREEK TRIBUTARY NO 1 9.0
END DESCRIPTION:
XS GIS Cut Line= 3
      3831257.63     10126141.58      3831424.17     10125326.12
        3831518.     10124865.78
#Sta/Elev= 30
  4167.7  247.44  4446.3  234.25  4592.7  225.86  4678.5  222.35  4770.4  220.39
  4833.4  220.25  4903.1  220.07  4953.3  220.85  4984.7  220.35  4994.3  216.83
  5005.1  217.45  5015.4  220.48  5076.6  220.35  5086.8  220.95    5094  220.32
  5097.8  219.51  5127.6  220.49  5137.8  219.21  5143.3  220.18  5164.9  220.41
  5229.7  220.88  5280.7  223.79  5289.8  224.91  5311.3  225.59  5346.6  228.65
    5396  230.11  5413.4  235.08  5433.8   238.5  5454.2  239.25  5469.8  238.57
#Mann= 9 ,-1 , 0
  4167.7     .05       0  4770.4     .12       0  4833.4     .05       0
  4953.3      .1       0  4984.7     .07       0  5015.4      .1       0
    5094     .12       0  5164.9      .1       0  5346.6     .05       0
Bank Sta=4984.7,5015.4
XS Rating Curve= 0 ,0
Exp/Cntr=0.3,0.1

Type RM Length L Ch R = 1 ,4996    ,636,636,636
BEGIN DESCRIPTION:
STEWARTS CREEK TRIBUTARY NO 1 8.0
END DESCRIPTION:
XS GIS Cut Line= 3
      3831552.75     10126145.98      3831821.71     10125436.77
      3831865.25     10124865.82
#Sta/Elev= 30
  4241.5  244.59  4351.5  240.32  4491.5  231.12    4589   223.6  4697.1  218.63
    4807  217.69  4867.3  219.16  4883.8  218.69  4952.6  219.44 4954.63 218.814
  4963.3  216.14  4971.8  215.17  4977.2  216.54  4984.7  216.28    5000   215.1
  5003.3  213.93  5008.1  213.93  5012.9  217.57  5017.9  216.29 5025.05 218.842
  5035.1   219.1    5096   218.7  5147.6  221.35  5216.3  226.27  5265.2  228.15
  5410.7  232.22  5477.1  238.87  5540.9  243.61  5547.3   244.2  5572.6  242.77
#Mann= 8 ,-1 , 0
  4241.5     .05       0  4883.8     .12       0 4954.63     .07       0
 5025.05     .12       0  5035.1      .1       0  5147.6     .05       0
  5265.2      .1       0  5540.9     .05       0
Bank Sta=4954.63,5025.05
XS Rating Curve= 0 ,0
Exp/Cntr=0.3,0.1

Type RM Length L Ch R = 1 ,4360    ,679,679,679
BEGIN DESCRIPTION:
STEWARTS CREEK TRIBUTARY NO 1 7.0
END DESCRIPTION:
XS GIS Cut Line= 3
      3832117.85     10126361.08      3832260.08     10125318.03
      3832121.48     10124835.65
#Sta/Elev= 30
  3947.3  238.52  4007.9   235.4  4222.5  228.84  4321.3  226.51  4583.1  216.15
  4658.1  216.87  4704.3  216.01  4714.3  216.87    4727  216.14  4754.7  217.06
  4831.3  216.06  4936.4  217.82  4966.7  217.38  4976.7  215.12  5007.2  214.82
  5015.2   213.8    5020   213.8  5029.7  215.79  5058.2  217.46  5097.1  222.46
  5136.1  222.96  5208.7  226.07  5281.3  231.35    5315  235.24  5353.9   237.3
  5387.7  240.42    5413  240.96  5444.2  239.06  5485.9  243.13  5501.9  242.23
#Mann= 7 ,-1 , 0
  3947.3     .05       0  4222.5     .12       0  4321.3     .05       0
  4658.1     .12       0  4831.3      .1       0  4966.7     .07       0
  5058.2     .05       0
Bank Sta=4966.7,5058.2
XS Rating Curve= 0 ,0
Exp/Cntr=0.3,0.1

Type RM Length L Ch R = 1 ,3681    ,678,678,678
BEGIN DESCRIPTION:
Mapping XS a0a90d26
END DESCRIPTION:
XS GIS Cut Line= 3
      3832338.35     10126406.36      3832631.95     10125635.05
      3832524.99     10124739.71
#Sta/Elev= 30
  4174.7  237.37    4266  233.23  4565.6  224.33  4643.3   225.9    4691  226.66
  4751.2  224.99  4930.4  215.83  4982.9  215.29  4991.1  210.42  5024.1  215.22
  5054.4  216.53  5104.7  215.46    5145  216.86  5318.7  216.52  5346.4  214.99
  5412.9  215.73    5427  219.12  5447.1   220.8  5457.2  224.63  5467.3  225.69
  5487.4  220.11  5517.6   217.5  5729.6  217.77  5747.7  223.56  5759.3  225.77
  5789.5  222.26    5850  223.48    5860  223.98  5890.3  231.52  5901.7  232.58
#Mann= 8 ,-1 , 0
  4174.7     .05       0  4643.3     .12       0  4930.4      .1       0
  4982.9     .07       0  5024.1      .1       0  5318.7     .05       0
  5517.6    .075       0  5729.6     .05       0
Bank Sta=4982.9,5024.1
XS Rating Curve= 0 ,0
Exp/Cntr=0.3,0.1

Type RM Length L Ch R = 1 ,3003    ,335,335,335
BEGIN DESCRIPTION:
STEWARTS CREEK TRIBUTARY NO 1 6.0
END DESCRIPTION:
XS GIS Cut Line= 3
      3832551.01     10126441.11      3833057.91     10125579.69
      3832950.34     10124770.11
#Sta/Elev= 30
  4000.5  235.07  4362.5  224.47  4538.3  224.47  4785.2  218.77  4831.2  216.41
  4852.7  217.41  4975.6  214.37  4985.5  211.72  4991.3  212.82  4993.8  208.82
  5018.8  213.78  5028.9  214.22    5049  212.02  5069.2  213.71  5099.5  211.28
  5129.8  214.21  5147.1  213.91  5240.7  214.31  5250.8  215.15  5260.9  217.96
  5266.1  221.37  5271.1  221.25  5291.2  227.09  5346.5  228.09  5446.1  227.53
  5545.8  228.42  5735.7  228.64  5745.1  228.46  5775.4  238.37  5816.7  237.44
#Mann= 9 ,-1 , 0
  4000.5     .05       0  4785.2     .12       0  4975.6     .07       0
  5028.9      .1       0  5147.1     .05       0  5346.5    .075       0
  5446.1      .1       0  5545.8    .075       0  5735.7      .1       0
Bank Sta=4975.6,5028.9
XS Rating Curve= 0 ,0
Exp/Cntr=0.3,0.1

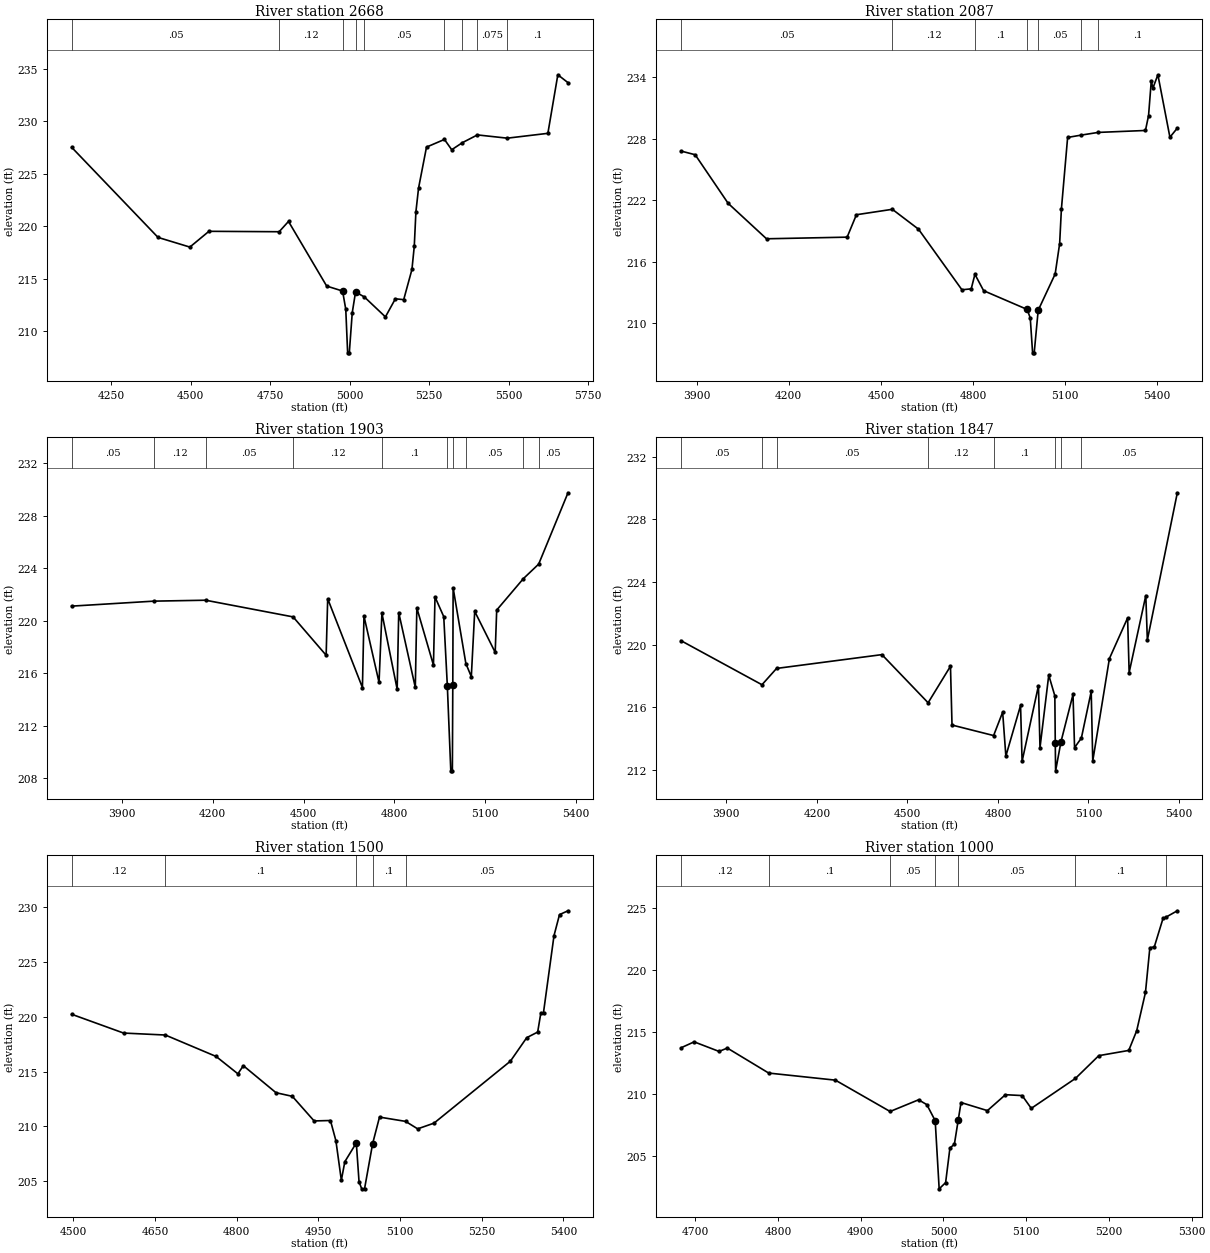
Type RM Length L Ch R = 1 ,2668    ,581,581,581
BEGIN DESCRIPTION:
STEWARTS CREEK TRIBUTARY NO 1 5.0
END DESCRIPTION:
XS GIS Cut Line= 3
      3833196.97     10126302.44      3833231.16     10125429.21
       3833036.4      10124770.4
#Sta/Elev= 30
  4126.1  227.51  4397.7  218.94  4497.8  218.02  4557.8  219.52  4778.6  219.48
    4808  220.46  4928.1  214.31  4978.1  213.84  4988.1   212.1    4994  207.96
  4999.2  207.96  5008.5  211.78  5018.9  213.75  5046.4  213.28  5112.8  211.38
  5144.1   213.1  5170.3  213.02  5196.2  215.89  5203.5  218.08  5208.7  221.38
    5217  223.63    5242  227.53  5298.4  228.26  5321.3  227.28  5354.7  227.95
  5402.1  228.69  5496.1  228.38  5623.7  228.84    5655  234.41    5687  233.66
#Mann= 9 ,-1 , 0
  4126.1     .05       0  4778.6     .12       0  4978.1     .07       0
  5018.9     .12       0  5046.4     .05       0  5298.4    .075       0
  5354.7      .1       0  5402.1    .075       0  5496.1      .1       0
Bank Sta=4978.1,5018.9
XS Rating Curve= 0 ,0
Exp/Cntr=0.3,0.1

Type RM Length L Ch R = 1 ,2087    ,184,184,184
BEGIN DESCRIPTION:
Mapping XS e6dbec3b
END DESCRIPTION:
XS GIS Cut Line= 3
      3833230.77      10126296.8      3833376.94     10125280.92
      3833279.49     10124698.66
#Sta/Elev= 30
  3848.9  226.79  3895.1  226.43  4002.6  221.68  4127.5  218.22  4390.1  218.38
  4420.3  220.57  4537.3   221.1  4622.5  219.16    4764  213.24  4794.3  213.33
  4806.3  214.75  4834.7  213.15  4976.5  211.32  4986.6  210.48  4994.2  207.08
  4999.4  207.08 5012.44 211.239  5067.7  214.78  5082.3  217.75    5088  221.12
  5108.3  228.12  5153.1  228.35  5207.6  228.61  5361.8   228.8  5371.9  230.25
  5380.8  233.66  5385.9  232.92  5402.3  234.24  5441.5  228.14  5465.6  229.03
#Mann= 7 ,-1 , 0
  3848.9     .05       0  4537.3     .12       0  4806.3      .1       0
  4976.5     .07       0 5012.44     .05       0  5153.1    .075       0
  5207.6      .1       0
Bank Sta=4976.5,5012.44
XS Rating Curve= 0 ,0
Exp/Cntr=0.3,0.1

Type RM Length L Ch R = 1 ,1903    ,56,56,56
BEGIN DESCRIPTION:
STEWARTS CREEK TRIBUTARY NO 1 4.0
END DESCRIPTION:
XS GIS Cut Line= 3
      3833289.96     10126302.82      3833504.61     10125054.84
      3833554.61      10124684.4
#Sta/Elev= 30
  3733.7  221.11  4005.3  221.49  4176.3  221.56  4465.4  220.29  4574.6  217.37
  4579.7  221.67  4694.5  214.91  4699.6  220.35  4749.4   215.3  4758.9  220.57
  4809.3  214.78  4814.4  220.62  4869.2  214.92  4874.3  220.97  4929.2  216.62
  4934.3  221.81  4963.2  220.31 4975.02 215.065  4986.5  208.57  4991.7  208.57
  4993.1 215.113  4994.2   222.5  5036.3  216.74  5054.3  215.74  5065.5  220.71
  5133.2  217.59  5138.2  220.81  5226.2   223.2  5276.9  224.31  5373.8  229.74
#Mann= 10 ,-1 , 0
  3733.7     .05       0  4005.3     .12       0  4176.3     .05       0
  4465.4     .12       0  4758.9      .1       0 4975.02     .07       0
  4993.1      .1       0  5036.3     .05       0  5226.2      .1       0
  5276.9     .05       0
Bank Sta=4975.02,4993.1
XS Rating Curve= 0 ,0
Exp/Cntr=0.3,0.1

Type RM Length L Ch R = 1 ,1847    ,347,347,347
BEGIN DESCRIPTION:
STEWARTS CREEK TRIBUTARY NO 1 3.5
END DESCRIPTION:
XS GIS Cut Line= 3
      3833337.44     10126301.18      3833553.99     10125069.87
      3833619.99     10124681.14
#Sta/Elev= 30
  3749.8  220.26  4018.1  217.45  4066.5  218.49  4415.5  219.37  4568.6   216.3
  4642.7  218.63  4647.8  214.88  4785.6  214.21  4815.6   215.7  4826.2   212.9
  4874.9  216.13    4880  212.57  4934.2  217.39  4939.3  213.44  4968.3  218.06
  4988.5  216.74 4989.89 213.765    4991  211.96  5008.9  213.82  5048.7  216.83
  5053.8  213.44  5076.4  214.05    5109  217.02  5114.1  212.59  5169.3  219.12
  5229.6  221.71  5234.7  218.23  5289.9  223.14    5295   220.3  5394.3  229.69
#Mann= 8 ,-1 , 0
  3749.8     .05       0  4018.1     .12       0  4066.5     .05       0
  4568.6     .12       0  4785.6      .1       0 4989.89     .07       0
  5008.9      .1       0  5076.4     .05       0
Bank Sta=4989.89,5008.9
XS Rating Curve= 0 ,0
Exp/Cntr=0.3,0.1

Type RM Length L Ch R = 1 ,1500    ,500,500,500
BEGIN DESCRIPTION:
STEWARTS CREEK TRIBUTARY NO 1 3.0
END DESCRIPTION:
XS GIS Cut Line= 3
      3833795.93     10125586.33      3833794.16     10125083.13
      3833769.92     10124675.45
#Sta/Elev= 30
  4496.8  220.21  4592.1   218.5  4668.9  218.32  4762.1  216.37  4802.1  214.79
  4812.1  215.53  4872.1  213.07  4902.1  212.74  4942.1   210.5  4972.1  210.54
  4982.1   208.7  4992.1   205.1  4998.5  206.79  5019.6   208.5  5024.6  204.97
  5029.5  204.32  5034.7  204.32  5049.6 208.443  5062.2  210.85  5110.1  210.46
  5132.3  209.78  5162.3   210.3  5302.6  215.94  5332.6  218.08  5352.7  218.59
  5358.4  220.29  5363.4  220.37  5382.7  227.37  5392.8  229.28  5408.4  229.63
#Mann= 5 ,-1 , 0
  4496.8     .12       0  4668.9      .1       0  5019.6     .07       0
  5049.6      .1       0  5110.1     .05       0
Bank Sta=5019.6,5049.6
XS Rating Curve= 0 ,0
Exp/Cntr=0.3,0.1

Type RM Length L Ch R = 1 ,1000    ,500,500,500
BEGIN DESCRIPTION:
STEWARTS CREEK TRIBUTARY NO 1 2.0
END DESCRIPTION:
XS GIS Cut Line= 3
      3834226.34     10125256.85      3834196.36     10124941.17
      3834101.78     10124674.76
#Sta/Elev= 30
  4682.9  213.73  4698.8  214.21  4728.9  213.44  4738.9  213.71  4788.9   211.7
  4869.5  211.13  4935.6  208.61    4970  209.55    4980  209.16  4990.1  207.87
  4994.9  202.39  5002.7  202.89  5007.9  205.67  5013.3  205.98    5018 207.948
  5021.3  209.33  5053.2  208.68    5075  209.96  5095.2  209.89  5106.2  208.86
  5159.6  211.27  5187.8   213.1    5224  213.52  5233.6   215.1  5244.2  218.18
  5249.5  221.77  5254.9  221.85  5265.4  224.13  5268.5  224.22  5282.7  224.75
#Mann= 7 ,-1 , 0
  4682.9     .12       0  4788.9      .1       0  4935.6     .05       0
  4990.1     .07       0    5018     .05       0  5159.6      .1       0
  5268.5     .05       0
Bank Sta=4990.1,5018
XS Rating Curve= 0 ,0
Exp/Cntr=0.3,0.1

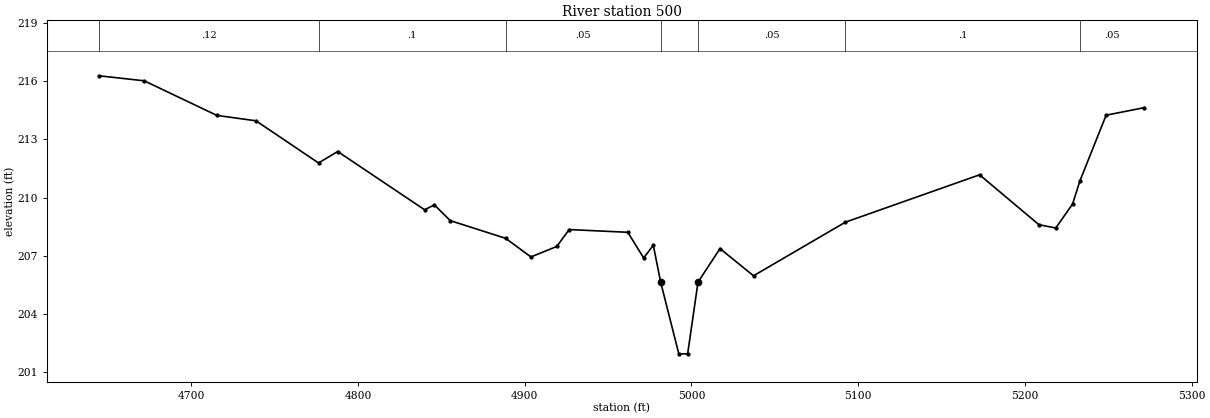
Type RM Length L Ch R = 1 ,500     ,0,0,0
BEGIN DESCRIPTION:
STEWARTS CREEK TRIBUTARY NO 1 1.0
END DESCRIPTION:
XS GIS Cut Line= 3
      3834439.88     10125241.19      3834624.02     10124941.81
      3834590.92     10124668.28
#Sta/Elev= 30
  4644.7  216.27  4671.8  216.01  4715.3  214.23  4738.8  213.95  4776.3  211.78
  4787.8  212.37  4839.9  209.37  4845.8  209.62  4855.3  208.81  4888.5   207.9
  4903.7  206.94  4919.2  207.48  4926.6  208.35  4961.8  208.21  4971.3  206.89
  4977.1  207.54 4981.54 205.629  4992.4  201.95  4997.7  201.95  5003.9  205.64
  5017.1  207.37  5037.2  205.97  5092.3  208.73  5172.8  211.17  5208.4   208.6
  5218.5  208.43  5228.6  209.67  5232.9  210.84  5248.7  214.24  5271.7  214.63
#Mann= 7 ,-1 , 0
  4644.7     .12       0  4776.3      .1       0  4888.5     .05       0
 4981.54     .07       0  5003.9     .05       0  5092.3      .1       0
  5232.9     .05       0
Bank Sta=4981.54,5003.9
XS Rating Curve= 0 ,0
Exp/Cntr=0.3,0.1