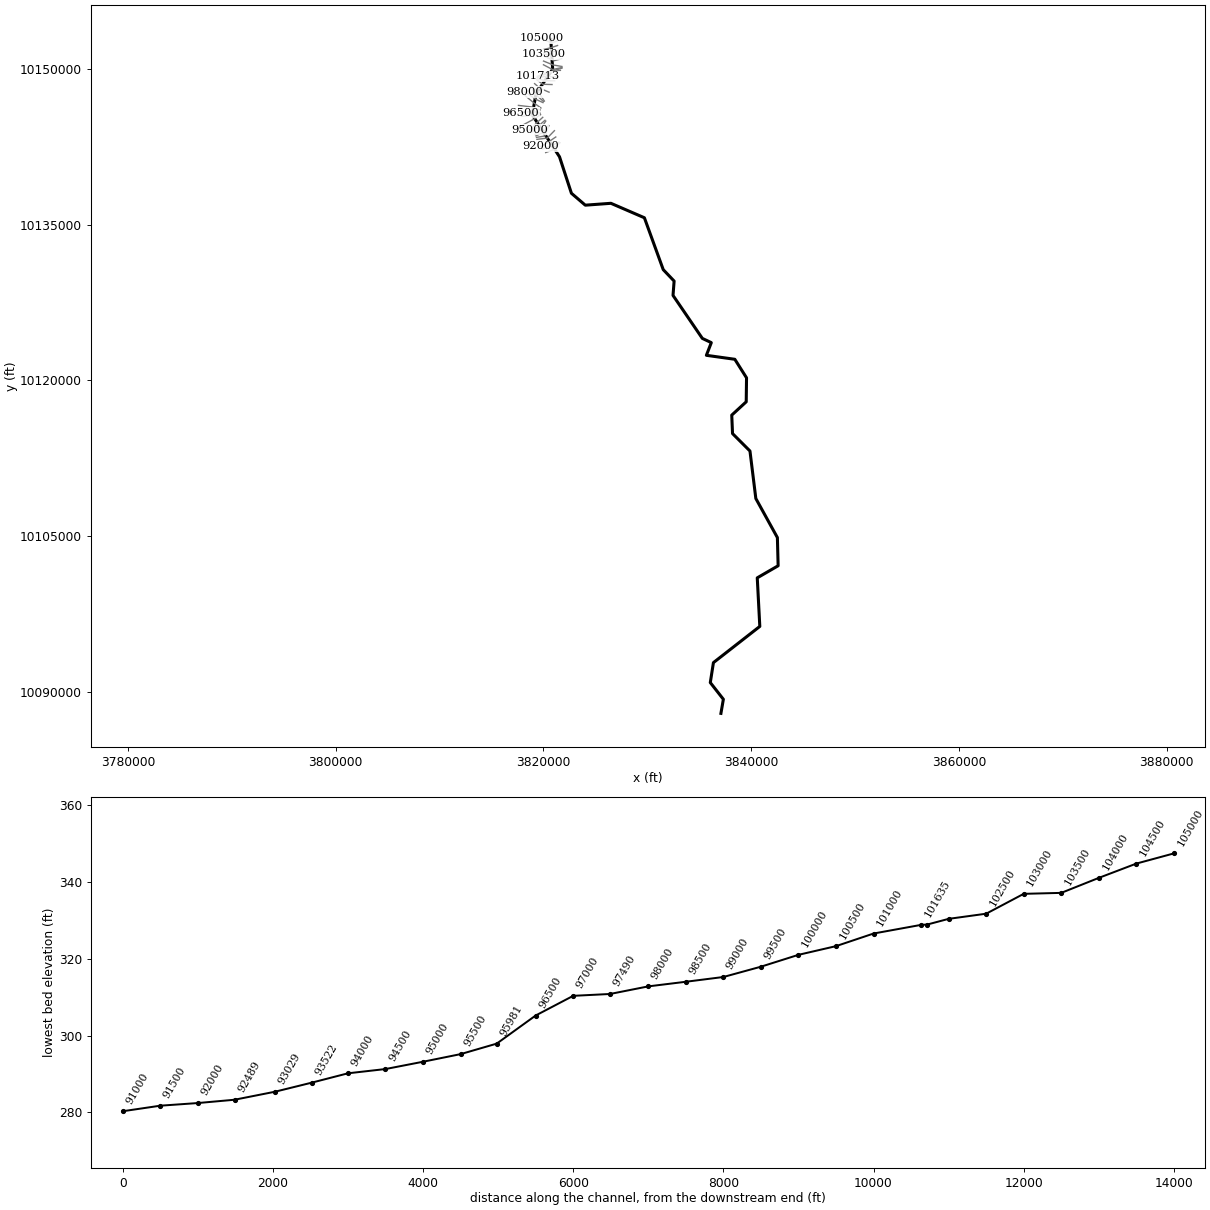
--- STEWARTS CREEK.prj (project) ---

Proj Title=STEWARTS CREEK Base Level Engineering
Current Plan=p01
Default Exp/Contr=0.3,0.1
English Units
Geom File=g01
Flow File=f01
Plan File=p01
Y Axis Title=Elevation
X Axis Title(PF)=Main Channel Distance
X Axis Title(XS)=Station
BEGIN DESCRIPTION:
STEWARTS CREEK
END DESCRIPTION:
DSS Export Rating Curves= 0
DSS Export Rating Curve Sorted= 0
DSS Export Volume Flow Curves= 0
DXF OffsetX= 0
DXF OffsetY= 0
DXF ScaleX= 1
DXF ScaleY= 10

--- STEWARTS CREEK.p01 (plan) ---

Plan Title=Multiple Run
Short Identifier=Multiple
Geom File=g01
Flow File=f01
Subcritical Flow
K Sum by GR= 0
Std Step Tol= 0.01
Critical Tol= 0.01
Num of Std Step Trials= 20
Max Error Tol= 0.3
Flow Tol Ratio= 0.001
Split Flow NTrial= 30
Split Flow Tol= 0.02
Split Flow Ratio= 0.02
Log Output Level= 0
Friction Slope Method= 1
Unsteady Friction Slope Method= 2
Unsteady Bridges Friction Slope Method= 1
Parabolic Critical Depth
Global Vel Dist=  1 , 1 , 1
Global Log Level= 0
CheckData=True
Encroach Param= -1, 0, 0, 0
BEGIN DESCRIPTION:
Multiple Run
END DESCRIPTION:

--- STEWARTS CREEK.f01 (steady flow) ---

Flow Title=Multiple
Program Version=4.10
Number of Profiles= 7
Profile Names=10-year,25-year,50-year,1pct_min,100-year,1pct_plu,500-year
River Rch & RM=STEWARTS CREEK,Reach-1         ,105000
     844    1160    1582     710    2145    6478    4076
River Rch & RM=STEWARTS CREEK,Reach-1         ,98000
    1195    1665    2293    1037    3133    9462    6044
River Rch & RM=STEWARTS CREEK,Reach-1         ,92000
    1506    2115    2929    1330    4017   12131    7816
River Rch & RM=STEWARTS CREEK,Reach-1         ,85500
    1534    2136    2939    1326    4003   12089    7676
River Rch & RM=STEWARTS CREEK,Reach-1         ,81000
    1999    2835    3948    1802    5441   16432   10688
River Rch & RM=STEWARTS CREEK,Reach-1         ,76000
    2057    2908    4043    1841    5559   16788   10869
River Rch & RM=STEWARTS CREEK,Reach-1         ,69000
    2347    3341    4664    2132    6439   19445   12699
River Rch & RM=STEWARTS CREEK,Reach-1         ,68000
    2413    3424    4771    2175    6569   19838   12886
River Rch & RM=STEWARTS CREEK,Reach-1         ,62538
    2485    3530    4923    2247    6785   20490   13332
River Rch & RM=STEWARTS CREEK,Reach-1         ,62000
    2485    3530    4923    2247    6785   20490   13332
River Rch & RM=STEWARTS CREEK,Reach-1         ,61462
    2485    3530    4923    2247    6785   20490   13332
River Rch & RM=STEWARTS CREEK,Reach-1         ,60935
    2485    3530    4923    2247    6785   20490   13332
River Rch & RM=STEWARTS CREEK,Reach-1         ,60263
    3144    4510    6334    2908    8782   26521   17470
River Rch & RM=STEWARTS CREEK,Reach-1         ,52515
    3368    4829    6777    3108    9386   28345   18633
River Rch & RM=STEWARTS CREEK,Reach-1         ,51176
    3655    5267    7419    3415   10312   31142   20618
River Rch & RM=STEWARTS CREEK,Reach-1         ,47000
    3693    5321    7495    3449   10416   31456   20815
River Rch & RM=STEWARTS CREEK,Reach-1         ,44000
    3643    5229    7343    3369   10175   30728   20217
River Rch & RM=STEWARTS CREEK,Reach-1         ,41091
    3798    5459    7674    3524   10641   32135   21175
River Rch & RM=STEWARTS CREEK,Reach-1         ,34500
    3857    5521    7738    3542   10696   32301   21149
River Rch & RM=STEWARTS CREEK,Reach-1         ,34000
    3857    5521    7738    3542   10696   32301   21149
River Rch & RM=STEWARTS CREEK,Reach-1         ,33422
    3857    5521    7738    3542   10696   32301   21149
River Rch & RM=STEWARTS CREEK,Reach-1         ,24500
    4052    5801    8133    3723   11244   33956   22234
River Rch & RM=STEWARTS CREEK,Reach-1         ,22000
    4039    5785    8114    3715   11220   33884   22200
River Rch & RM=STEWARTS CREEK,Reach-1         ,19000
    4202    6005    8407    3843   11605   35047   22876
River Rch & RM=STEWARTS CREEK,Reach-1         ,6500
    4568    6580    9266    4260   12865   38852   25656
River Rch & RM=STEWARTS CREEK,Reach-1         ,494
    5042    7272   10247    4714   14235   42989   28413
Boundary for River Rch & Prof#=STEWARTS CREEK,Reach-1         , 1
Up Type= 0
Dn Type= 3
Dn Slope=0.0005
Boundary for River Rch & Prof#=STEWARTS CREEK,Reach-1         , 2
Up Type= 0
Dn Type= 3
Dn Slope=0.0005
Boundary for River Rch & Prof#=STEWARTS CREEK,Reach-1         , 3
Up Type= 0
Dn Type= 3
Dn Slope=0.0005
Boundary for River Rch & Prof#=STEWARTS CREEK,Reach-1         , 4
Up Type= 0
Dn Type= 3
Dn Slope=0.0005
Boundary for River Rch & Prof#=STEWARTS CREEK,Reach-1         , 5
Up Type= 0
Dn Type= 3
Dn Slope=0.0005
Boundary for River Rch & Prof#=STEWARTS CREEK,Reach-1         , 6
Up Type= 0
Dn Type= 3
Dn Slope=0.0005
Boundary for River Rch & Prof#=STEWARTS CREEK,Reach-1         , 7
Up Type= 0
Dn Type= 3
Dn Slope=0.0005
DSS Import GetInterval= 0
DSS Import GetPeak= 0
DSS Import FillOption= 0

--- STEWARTS CREEK.g01 (geometry) ---

Geom Title=Existing Conditions
Program Version=4.10

River Reach=STEWARTS CREEK  ,Reach-1
Reach XY= 30
       3820705.6     10152844.38      3820887.24     10149971.17
      3819290.12     10147636.23      3818919.86     10145579.78
      3821545.68     10141537.63      3822691.01     10138026.17
      3824026.45     10136878.32      3826492.11     10137059.24
      3829714.75     10135666.42      3831530.19     10130666.77
      3832576.17     10129566.65      3832470.91     10128183.36
      3835294.61     10124040.39      3836156.48     10123636.18
      3835682.09     10122413.66      3838419.87     10122030.46
      3839547.38     10120242.69      3839516.33     10117934.69
      3838123.97     10116649.96      3838198.35     10114873.88
      3839876.84     10113194.37      3840441.89     10108617.49
      3842517.25     10104852.61      3842588.36     10102137.94
      3840579.38     10100973.47      3840824.35     10096293.54
      3836360.16     10092806.06      3836058.82     10090883.07
      3837316.89     10089274.61      3837081.82      10087915.8

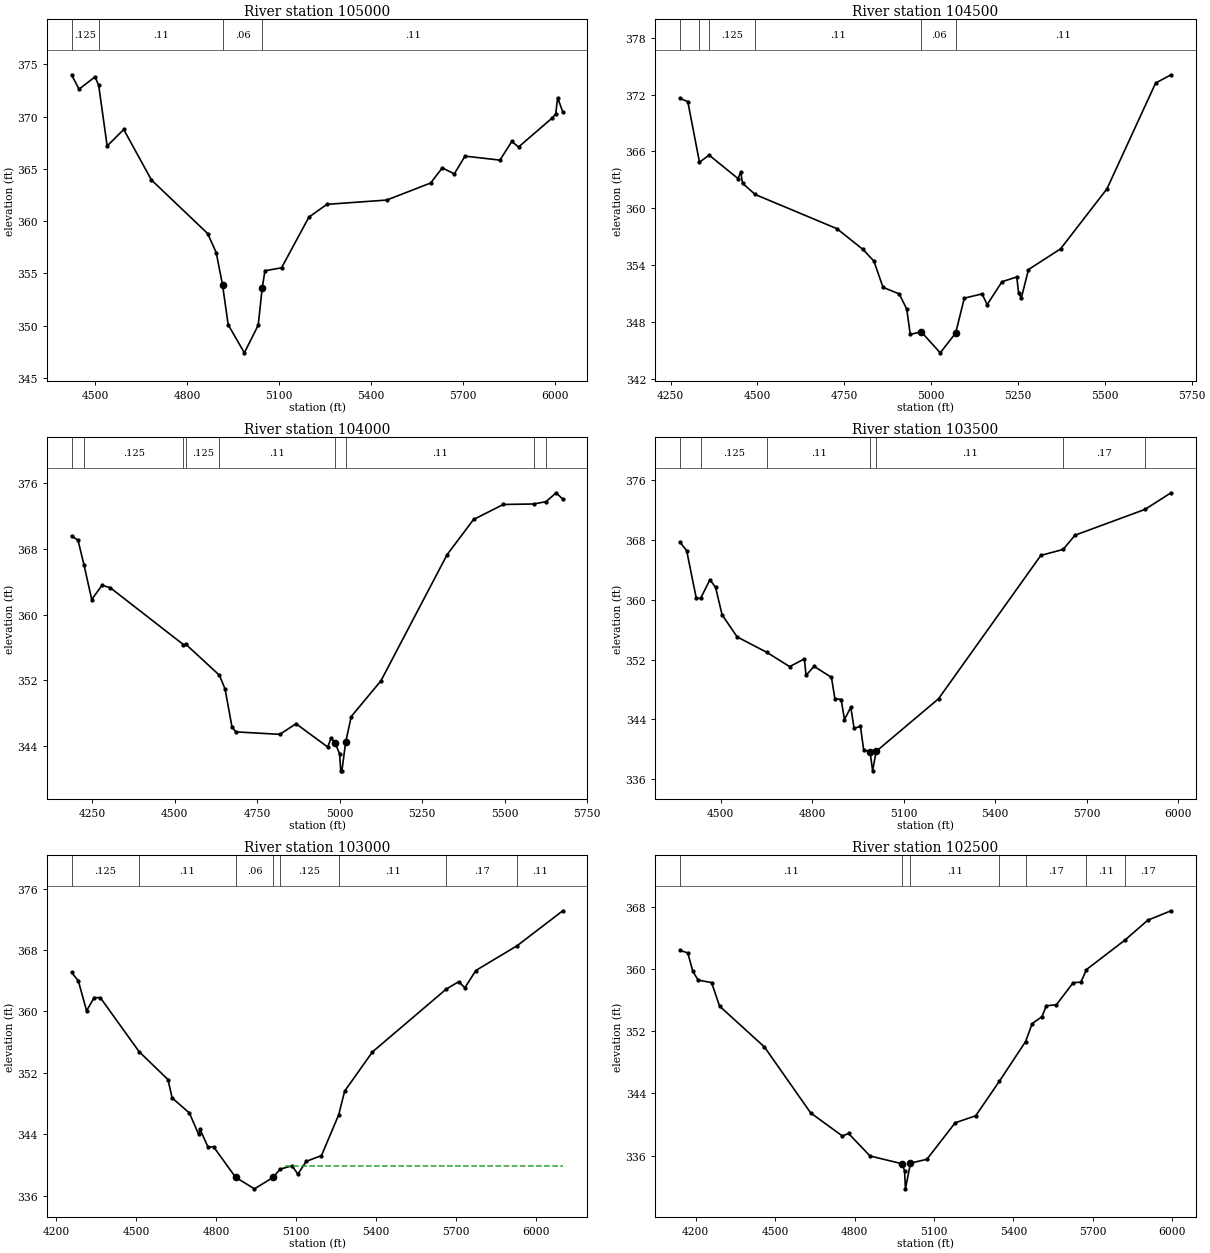
Type RM Length L Ch R = 1 ,105000  ,500,500,500
BEGIN DESCRIPTION:
STEWARTS CREEK 207.0
END DESCRIPTION:
XS GIS Cut Line= 3
      3821291.42     10152679.38       3820736.9     10152518.42
      3819807.06     10152952.79
#Sta/Elev= 30
  4422.6  373.99  4447.1  372.61  4499.2  373.79  4511.2  372.98  4538.9  367.18
  4592.9  368.76  4683.5  363.93  4866.9  358.81  4894.9  356.99  4915.7  353.87
    4934  350.09  4986.8   347.4  5032.1  350.05  5045.2  353.64  5054.1  355.25
  5108.2  355.53  5197.6  360.38  5256.3   361.6  5451.5  362.01    5595  363.64
    5633  365.09  5672.2  364.51  5707.1  366.21  5821.3  365.83  5859.9  367.62
  5881.9  367.08  5992.3  369.87  6003.3  370.25  6009.6   371.8  6026.3  370.44
#Mann= 4 ,-1 , 0
  4422.6    .125       0  4511.2     .11       0  4915.7     .06       0
  5045.2     .11       0
Bank Sta=4915.7,5045.2
XS Rating Curve= 0 ,0
Exp/Cntr=0.3,0.1

Type RM Length L Ch R = 1 ,104500  ,500,500,500
BEGIN DESCRIPTION:
STEWARTS CREEK 206.0
END DESCRIPTION:
XS GIS Cut Line= 3
      3821356.48      10152262.7      3820670.88     10152032.23
      3819997.98     10151876.42
#Sta/Elev= 30
  4276.7   371.6  4299.6  371.26  4333.2  364.87    4361  365.61  4444.1  363.14
  4451.9  363.81  4457.1  362.65  4493.5  361.46  4728.9  357.85  4803.8  355.66
  4835.3  354.43  4861.6  351.66  4908.2  350.97  4929.9  349.36  4939.9   346.7
  4971.5  346.97  5026.3  344.75  5070.7  346.84  5095.5  350.52  5146.8  350.97
  5161.3  349.83  5203.9  352.25  5246.6  352.76  5251.8  351.06  5259.7  350.54
  5280.3  353.54  5372.6  355.72  5506.1  362.05  5646.3  373.22  5690.7  374.09
#Mann= 6 ,-1 , 0
  4276.7    .125       0  4333.2     .11       0    4361    .125       0
  4493.5     .11       0  4971.5     .06       0  5070.7     .11       0
Bank Sta=4971.5,5070.7
XS Rating Curve= 0 ,0
Exp/Cntr=0.3,0.1

Type RM Length L Ch R = 1 ,104000  ,500,500,500
BEGIN DESCRIPTION:
STEWARTS CREEK 205.0
END DESCRIPTION:
XS GIS Cut Line= 3
      3821496.85     10151806.53      3820712.92     10151591.83
        3820038.     10151547.01
#Sta/Elev= 30
  4187.2  369.54  4206.9  369.03  4225.1     366  4248.4  361.83  4279.5  363.55
    4304  363.28  4526.3  356.36  4534.5  356.37  4635.7  352.63  4652.7  350.95
  4673.5  346.38  4685.1  345.76  4818.6  345.46  4867.8  346.75  4963.8  343.92
  4974.1  345.01  4986.8  344.39    5000  343.07  5003.3  341.03  5006.8  341.03
  5018.1 344.471  5035.1  347.62  5125.3  351.97  5325.8  367.28    5406  371.55
  5496.2  373.37  5587.9  373.43  5625.5  373.71  5656.5  374.79  5676.4  374.01
#Mann= 9 ,-1 , 0
  4187.2     .11       0  4225.1    .125       0  4526.3     .11       0
  4534.5    .125       0  4635.7     .11       0  4986.8     .09       0
  5018.1     .11       0  5587.9     .17       0  5625.5     .11       0
Bank Sta=4986.8,5018.1
XS Rating Curve= 0 ,0
Exp/Cntr=0.3,0.1

Type RM Length L Ch R = 1 ,103500  ,500,500,500
BEGIN DESCRIPTION:
STEWARTS CREEK 204.0
END DESCRIPTION:
XS GIS Cut Line= 3
      3821599.03     10151456.57      3820993.88       10151253.
      3820038.02     10151429.05
#Sta/Elev= 30
  4366.4  367.71  4388.7  366.57  4420.4  360.17  4434.8   360.2    4465  362.67
  4483.7  361.64  4504.8  357.99  4554.2  355.03  4652.2  352.95  4726.4  351.06
  4774.8  352.09    4780  349.88  4806.3   351.1  4863.5  349.62  4874.6  346.79
  4895.2  346.66  4906.1  343.98  4926.8  345.63  4937.6  342.83  4958.5  343.07
  4969.1  339.92    4990  339.68  4998.4  337.13 5009.94339.7286  5214.4  346.76
  5549.9  365.92  5623.2  366.72  5661.8  368.62  5891.4  372.07  5976.8  374.29
#Mann= 7 ,-1 , 0
  4366.4     .11       0  4434.8    .125       0  4652.2     .11       0
    4990     .09       0 5009.94     .11       0  5623.2     .17       0
  5891.4     .11       0
Bank Sta=4990,5009.94
XS Rating Curve= 0 ,0
Exp/Cntr=0.3,0.1

Type RM Length L Ch R = 1 ,103000  ,500,500,500
BEGIN DESCRIPTION:
STEWARTS CREEK 203.0
END DESCRIPTION:
XS GIS Cut Line= 3
      3821752.42     10150988.67      3821034.92     10150798.39
      3820031.48      10151247.6
#Sta/Elev= 30
  4257.7  365.07  4283.1  363.98  4314.1  360.08  4342.9   361.8  4365.9  361.77
    4511  354.75  4619.1  351.12  4634.9  348.72  4699.5  346.76  4734.6  343.96
  4739.7  344.61  4769.4  342.32  4790.1  342.36  4872.8  338.38  4943.5  336.88
 5013.95338.3828  5039.4  339.44  5084.4  339.88  5106.3  338.79  5137.5  340.46
  5194.8  341.21  5259.4  346.53  5281.7  349.61  5385.8  354.71  5662.9  362.91
  5709.3  363.86  5732.4  363.07  5773.4  365.32  5928.4  368.55  6099.4   373.1
#Mann= 8 ,-1 , 0
  4257.7    .125       0    4511     .11       0  4872.8     .06       0
 5013.95     .11       0  5039.4    .125       0  5259.4     .11       0
  5662.9     .17       0  5928.4     .11       0
#XS Ineff= 2 , 0
       0                  5062.4       0  339.85
Permanent Ineff=
       F       F
Bank Sta=4872.8,5013.95
XS Rating Curve= 0 ,0
Exp/Cntr=0.3,0.1

Type RM Length L Ch R = 1 ,102500  ,500,500,500
BEGIN DESCRIPTION:
STEWARTS CREEK 202.0
END DESCRIPTION:
XS GIS Cut Line= 3
      3821776.01     10150241.58      3820928.35     10150387.32
      3820006.55     10150764.56
#Sta/Elev= 30
  4139.9   362.4    4170  362.08  4188.8  359.71  4209.1  358.58  4259.8  358.26
  4290.2  355.22  4459.6  349.97  4634.3  341.48  4754.2  338.51  4777.3  338.84
  4858.5  335.94  4980.2  334.93    4989  334.03  4992.3  331.71  5011.3  335.02
  5073.3  335.51  5180.2  340.21  5257.6  341.11  5347.5  345.57  5446.2  350.66
  5471.3  352.98  5508.4  353.88  5524.7  355.28  5562.4  355.39  5626.1  358.24
  5655.5  358.32  5676.3  359.93  5822.2  363.74  5908.2  366.29    5996   367.5
#Mann= 7 ,-1 , 0
  4139.9     .11       0  4980.2     .09       0  5011.3     .11       0
  5347.5    .125       0  5446.2     .17       0  5676.3     .11       0
  5822.2     .17       0
Bank Sta=4980.2,5011.3
XS Rating Curve= 0 ,0
Exp/Cntr=0.3,0.1

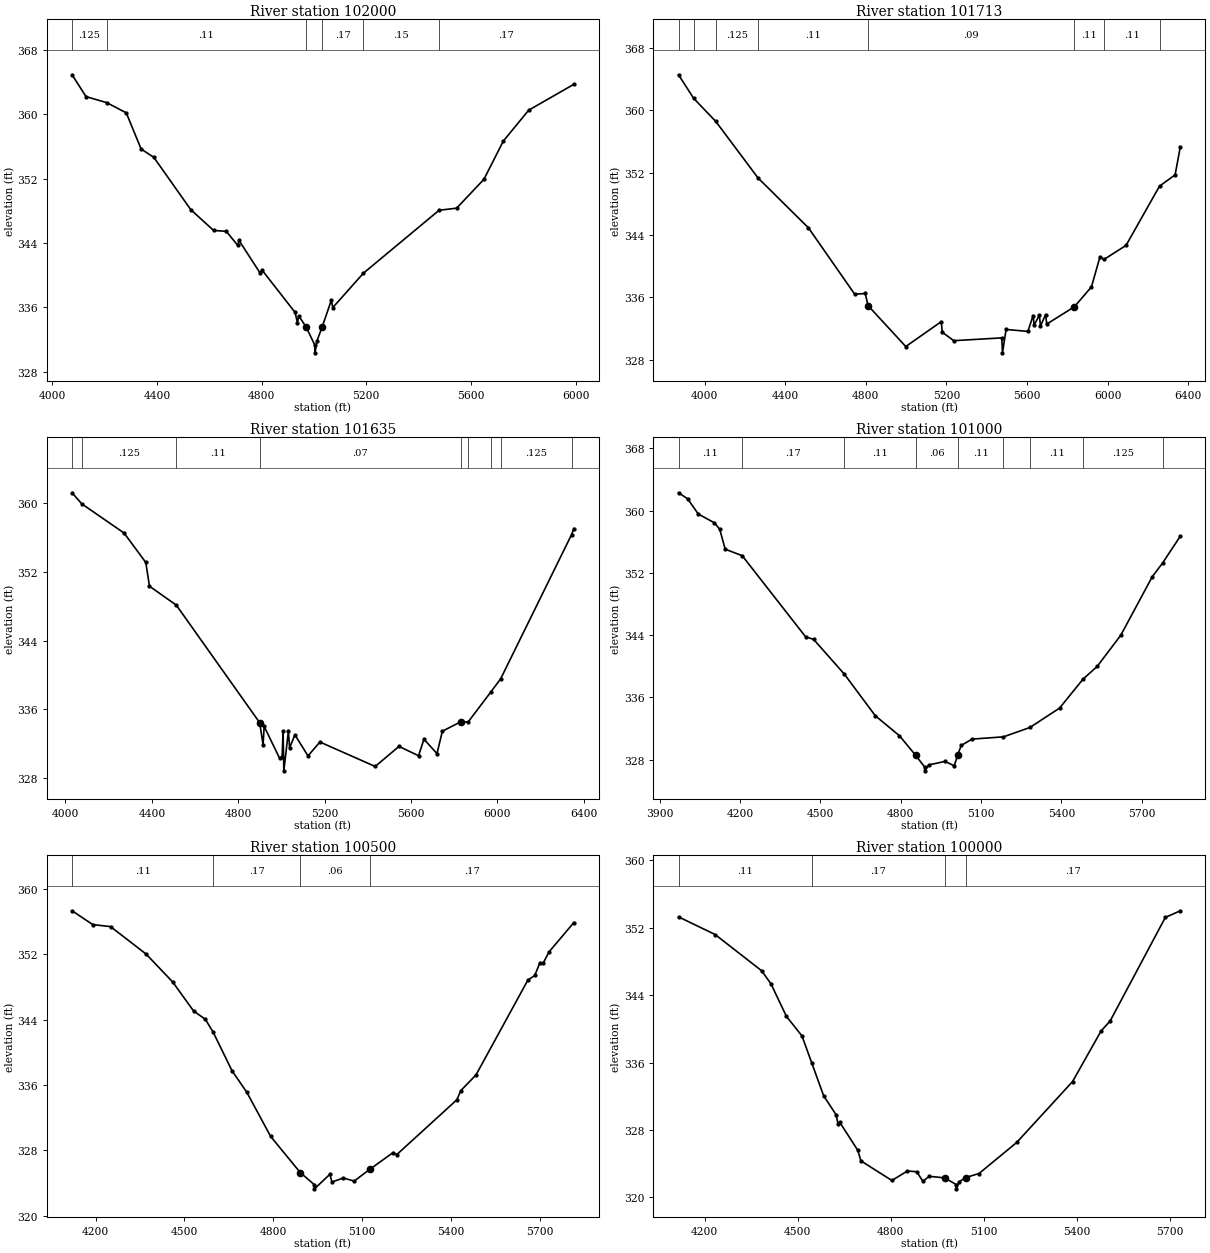
Type RM Length L Ch R = 1 ,102000  ,287,287,287
BEGIN DESCRIPTION:
STEWARTS CREEK 201.0
END DESCRIPTION:
XS GIS Cut Line= 3
      3821779.96     10150143.29      3820877.69     10149943.14
      3819999.37     10150406.39
#Sta/Elev= 30
  4075.8  364.87  4129.2  362.16  4208.4  361.41  4282.8  360.15  4339.6  355.66
  4388.3  354.62  4529.2  348.14  4616.4  345.56  4665.1  345.44  4708.7  343.71
  4713.8  344.31    4795  340.23  4800.9  340.67  4928.1  335.38  4936.8  334.09
  4941.9  334.95 4970.13333.5695  5002.7  331.37  5004.1  330.37  5011.5  331.86
 5031.34333.5748  5066.3  336.89    5072  335.99  5189.2  340.26  5478.1  348.06
  5545.2  348.32  5649.6  351.91  5723.4  356.64  5820.2  360.47    5993  363.69
#Mann= 6 ,-1 , 0
  4075.8    .125       0  4208.4     .11       0 4970.13     .09       0
 5031.34     .17       0  5189.2     .15       0  5478.1     .17       0
Bank Sta=4970.13,5031.34
XS Rating Curve= 0 ,0
Exp/Cntr=0.3,0.1

Type RM Length L Ch R = 1 ,101713  ,78,78,78
BEGIN DESCRIPTION:
Mapping XS 54c76c93
END DESCRIPTION:
XS GIS Cut Line= 3
      3821775.58     10150073.83      3820873.69     10149805.61
       3819411.5     10149296.53
#Sta/Elev= 30
  3870.8  364.56  3945.6  361.54  4054.7   358.6  4265.5  351.31  4515.3  344.92
    4745  336.39    4797   336.5  4810.9  334.94    4998  329.69    5174  332.88
  5179.2  331.52  5236.1  330.44  5474.3   330.8  5477.8  328.88  5495.6  331.88
  5603.9  331.63  5629.7  333.67    5635  332.44  5660.8  333.72  5666.1  332.33
  5691.9  333.79  5697.2  332.57  5834.4  334.79  5919.1  337.34  5961.1  341.17
  5981.2  340.86  6090.8  342.67  6256.7  350.27  6334.2  351.72    6360  355.33
#Mann= 8 ,-1 , 0
  3870.8    .125       0  3945.6     .15       0  4054.7    .125       0
  4265.5     .11       0  4810.9     .09       0  5834.4     .11       0
  5981.2     .11       0  6256.7    .125       0
Bank Sta=4810.9,5834.4
XS Rating Curve= 0 ,0
Exp/Cntr=0.3,0.1

Type RM Length L Ch R = 1 ,101635  ,635,635,635
BEGIN DESCRIPTION:
STEWARTS CREEK 200.0
END DESCRIPTION:
XS GIS Cut Line= 3
      3821628.91     10149864.64      3820679.56     10149669.01
      3819411.81     10149192.05
#Sta/Elev= 30
  4030.7  361.22  4075.6  359.93  4271.5  356.53  4372.1   353.1  4389.1  350.33
  4513.6  348.12  4899.6  334.42  4915.2  331.85  4920.3  333.99  4991.5  330.29
  5003.6  330.41  5007.8  333.45  5011.4  328.81  5032.6  333.45    5038   331.5
  5062.9     333  5123.3  330.55  5178.4  332.17  5434.4  329.32  5544.7  331.66
  5635.3  330.57  5660.2   332.5  5720.7  330.82  5745.5  333.43  5830.9  334.53
  5864.8   334.5  5968.8  337.96  6015.6  339.54    6344  356.35  6354.5  357.05
#Mann= 9 ,-1 , 0
  4030.7     .15       0  4075.6    .125       0  4513.6     .11       0
  4899.6     .07       0  5830.9     .11       0  5864.8    .125       0
  5968.8     .11       0  6015.6    .125       0    6344     .11       0
Bank Sta=4899.6,5830.9
XS Rating Curve= 0 ,0
Exp/Cntr=0.3,0.1

Type RM Length L Ch R = 1 ,101000  ,500,500,500
BEGIN DESCRIPTION:
STEWARTS CREEK 199.0
END DESCRIPTION:
XS GIS Cut Line= 3
      3821281.71     10149222.27      3820253.37     10149282.39
      3819417.83     10149161.07
#Sta/Elev= 30
  3969.9   362.3  4003.8  361.53  4043.9  359.56    4104  358.44    4124  357.59
  4144.1  355.05  4207.8  354.21  4444.6  343.78  4474.6  343.45  4589.1  338.99
    4705  333.63  4795.2  331.06  4855.3  328.56    4889  327.05  4889.2  326.55
  4905.4  327.32  4965.5  327.76    5000   327.2 5012.21 328.554  5025.8  329.81
  5066.2  330.63  5183.6  330.92  5282.8  332.13  5393.3  334.62  5481.1  338.35
  5533.6  339.97    5622  343.99    5739  351.48  5778.6   353.3  5844.3  356.72
#Mann= 9 ,-1 , 0
  3969.9     .11       0  4207.8     .17       0  4589.1     .11       0
  4855.3     .06       0 5012.21     .11       0  5183.6     .17       0
  5282.8     .11       0  5481.1    .125       0  5778.6     .11       0
Bank Sta=4855.3,5012.21
XS Rating Curve= 0 ,0
Exp/Cntr=0.3,0.1

Type RM Length L Ch R = 1 ,100500  ,500,500,500
BEGIN DESCRIPTION:
STEWARTS CREEK 198.0
END DESCRIPTION:
XS GIS Cut Line= 3
      3821077.72     10148862.03      3820198.34     10148867.91
      3819406.69     10149057.34
#Sta/Elev= 30
  4120.6  357.31  4190.5  355.62  4250.5  355.37  4370.5  352.01  4460.5  348.58
  4530.5  345.05  4570.5  344.02  4596.7  342.45  4660.5  337.72  4710.5  335.08
  4790.5   329.7  4890.5  325.27  4938.5  323.77  4938.7  323.27  4990.5  325.05
  4997.7   324.1  5035.8   324.6  5072.5  324.22    5125  325.65    5204  327.71
  5216.4  327.46  5419.4  334.18  5432.4  335.29  5483.8  337.22  5658.6  348.81
    5682  349.39  5699.7  350.97    5710  350.87  5730.5  352.29    5814  355.87
#Mann= 4 ,-1 , 0
  4120.6     .11       0  4596.7     .17       0  4890.5     .06       0
    5125     .17       0
Bank Sta=4890.5,5125
XS Rating Curve= 0 ,0
Exp/Cntr=0.3,0.1

Type RM Length L Ch R = 1 ,100000  ,500,500,500
BEGIN DESCRIPTION:
STEWARTS CREEK 197.0
END DESCRIPTION:
XS GIS Cut Line= 3
      3820825.91     10148501.79      3819942.05     10148526.24
      3819346.87     10148956.82
#Sta/Elev= 30
  4115.8  353.29  4233.9  351.19    4384  346.89    4414  345.34    4464  341.47
    4514  339.16  4545.9  335.92    4584  332.05  4624.1   329.8  4630.7  328.65
  4635.7  328.92  4694.1  325.58  4704.1  324.33  4804.1     322  4854.1  323.13
  4884.2  323.04  4904.2   321.9  4924.2   322.5  4974.2  322.31  5012.1  321.51
  5012.3  321.01  5020.2  321.82  5042.2  322.35  5085.2  322.83  5206.6  326.51
  5386.9  333.74  5478.9  339.74  5508.3  340.94  5686.2  353.22  5734.6  354.01
#Mann= 4 ,-1 , 0
  4115.8     .11       0  4545.9     .17       0  4974.2     .06       0
  5042.2     .17       0
Bank Sta=4974.2,5042.2
XS Rating Curve= 0 ,0
Exp/Cntr=0.3,0.1

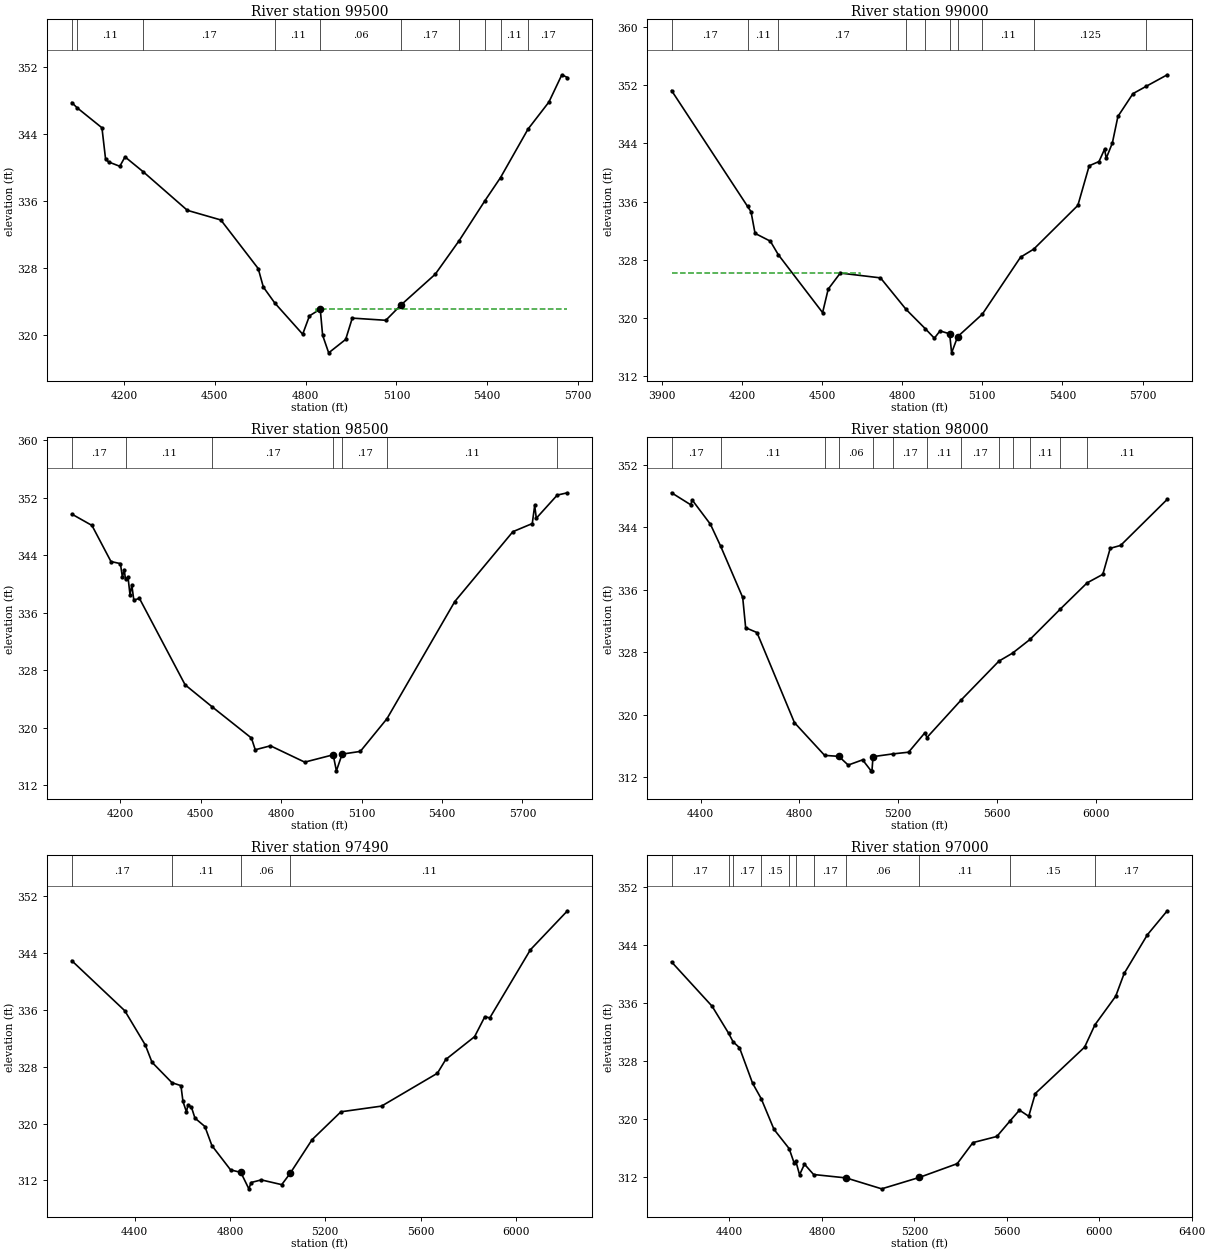
Type RM Length L Ch R = 1 ,99500   ,500,500,500
BEGIN DESCRIPTION:
STEWARTS CREEK 196.0
END DESCRIPTION:
XS GIS Cut Line= 3
      3820539.53     10147763.92      3819645.56     10148146.78
      3819147.69     10148587.33
#Sta/Elev= 30
  4027.5  347.76  4045.4  347.13  4127.2  344.75  4139.1  341.04    4149  340.68
  4186.2  340.16  4203.4  341.28  4263.7   339.5  4409.3  334.91  4519.9  333.76
  4643.3  327.97  4660.3  325.76  4698.1  323.86  4790.2  320.14  4812.6  322.33
  4848.2  323.13  4856.1  320.01  4876.1  317.92  4932.2  319.52    4954  322.06
  5064.8   321.8    5115  323.63    5228  327.29  5307.3  331.31  5392.2  336.06
  5443.6  338.81  5534.4  344.59  5603.5  347.82  5646.2  351.07  5664.8  350.74
#Mann= 10 ,-1 , 0
  4027.5     .17       0  4045.4     .11       0  4263.7     .17       0
  4698.1     .11       0  4848.2     .06       0    5115     .17       0
  5307.3    .125       0  5392.2     .17       0  5443.6     .11       0
  5534.4     .17       0
#XS Ineff= 2 ,-1
  4848.2  4834.3  323.13  4834.3  4703.8  323.18
Permanent Ineff=
       F       F
Bank Sta=4848.2,5115
XS Rating Curve= 0 ,0
Exp/Cntr=0.3,0.1

Type RM Length L Ch R = 1 ,99000   ,500,500,500
BEGIN DESCRIPTION:
STEWARTS CREEK 195.0
END DESCRIPTION:
XS GIS Cut Line= 3
      3820083.77     10146913.23      3819498.08     10147800.56
      3818864.12     10148276.11
#Sta/Elev= 30
  3936.8  351.25  4221.4  335.34  4234.3  334.62  4249.4  331.64  4306.6  330.57
  4336.3  328.72  4502.3  320.76  4523.3  323.99  4568.5  326.19    4719  325.53
  4815.1  321.19  4886.5  318.56  4920.7  317.25  4941.8  318.25  4977.9  317.85
  4985.2  315.24  5007.9  317.46  5100.3  320.55  5243.3  328.37  5292.8  329.48
  5457.9  335.48  5500.3  340.92    5537   341.5  5557.8  343.19  5564.1  341.95
    5587  344.04  5607.8  347.69  5664.1  350.82  5714.3  351.84  5792.5  353.41
#Mann= 10 ,-1 , 0
  3936.8     .17       0  4221.4     .11       0  4336.3     .17       0
  4815.1     .11       0  4886.5     .17       0  4977.9     .09       0
  5007.9     .17       0  5100.3     .11       0  5292.8    .125       0
  5714.3     .11       0
#XS Ineff= 2 , 0
       0  4640.8  326.23               0
Permanent Ineff=
       F       F
Bank Sta=4977.9,5007.9
XS Rating Curve= 0 ,0
Exp/Cntr=0.3,0.1

Type RM Length L Ch R = 1 ,98500   ,500,500,500
BEGIN DESCRIPTION:
STEWARTS CREEK 194.0
END DESCRIPTION:
XS GIS Cut Line= 3
      3820009.99     10146856.81      3819286.26     10147517.58
      3818807.71     10148241.38
#Sta/Elev= 30
    4020   349.7  4095.2  348.12  4166.1   343.1  4201.3  342.81  4208.7  340.94
  4215.5  341.97  4220.3  340.62  4229.7  340.92  4237.1  338.47  4243.8  339.83
  4251.3  337.74  4272.2  337.98  4442.5  325.96  4542.9  322.91  4689.7  318.56
  4703.9  316.93  4760.7  317.48  4888.3  315.21  4994.4  316.23  5006.4     314
 5027.84316.3272  5095.5   316.7  5194.9  321.25  5447.7  337.54  5664.2  347.25
  5736.5  348.38  5745.5  350.91  5751.5  349.12  5829.6  352.34  5867.7  352.66
#Mann= 7 ,-1 , 0
    4020     .17       0  4220.3     .11       0  4542.9     .17       0
  4994.4     .09       0 5027.84     .17       0  5194.9     .11       0
  5829.6     .17       0
Bank Sta=4994.4,5027.84
XS Rating Curve= 0 ,0
Exp/Cntr=0.3,0.1

Type RM Length L Ch R = 1 ,98000   ,510,510,510
BEGIN DESCRIPTION:
STEWARTS CREEK 193.0
END DESCRIPTION:
XS GIS Cut Line= 3
      3819949.19     10146761.34      3819298.11     10147064.26
      3818226.11      10147781.3
#Sta/Elev= 30
  4281.9  348.45  4359.7  346.91  4365.2  347.54  4439.3  344.42  4480.7  341.61
  4570.1  335.03  4582.1  331.15  4627.9  330.53  4779.7  318.98    4902  314.78
  4959.3  314.66  4997.4  313.54  5055.8  314.21  5090.1   312.8  5093.7   312.8
  5097.9  314.62  5177.9  314.97    5242  315.19  5308.1  317.68  5316.3  317.07
  5454.8  321.88    5608  326.87    5663  327.89  5733.5  329.64  5856.5  333.54
  5965.1   336.9  6028.7  337.99  6058.7  341.33  6100.8   341.7  6289.7  347.61
#Mann= 13 ,-1 , 0
  4281.9     .17       0  4480.7     .11       0    4902     .17       0
  4959.3     .06       0  5097.9     .11       0  5177.9     .17       0
  5316.3     .11       0  5454.8     .17       0    5608     .11       0
    5663     .17       0  5733.5     .11       0  5856.5     .17       0
  5965.1     .11       0
#XS Ineff= 2 , 0
       0                  5308.1       0  317.68
Permanent Ineff=
       F       F
Bank Sta=4959.3,5097.9
XS Rating Curve= 0 ,0
Exp/Cntr=0.3,0.1

Type RM Length L Ch R = 1 ,97490   ,490,490,490
BEGIN DESCRIPTION:
STEWARTS CREEK 192.0
END DESCRIPTION:
XS GIS Cut Line= 3
       3819758.2     10146240.53      3819057.81     10146746.43
      3818122.42     10147524.83
#Sta/Elev= 30
    4136  342.92  4358.5  335.88  4444.8  331.05  4472.8  328.63  4556.7  325.75
  4594.3  325.34  4602.8  323.11  4617.5  321.64  4623.7  322.62  4638.4  322.31
  4653.1  320.77  4694.8  319.59  4724.3   316.9  4802.6  313.49  4845.7  313.13
  4879.4  310.82  4888.9  311.71  4931.6  312.08  5017.3  311.41  5052.4  312.98
  5144.8  317.74  5265.9  321.66  5436.5  322.46  5670.8  327.08    5706  329.02
    5827  332.23    5870  335.04  5890.8  334.87  6061.4  344.46  6216.9  349.94
#Mann= 4 ,-1 , 0
    4136     .17       0  4556.7     .11       0  4845.7     .06       0
  5052.4     .11       0
Bank Sta=4845.7,5052.4
XS Rating Curve= 0 ,0
Exp/Cntr=0.3,0.1

Type RM Length L Ch R = 1 ,97000   ,500,500,500
BEGIN DESCRIPTION:
STEWARTS CREEK 191.0
END DESCRIPTION:
XS GIS Cut Line= 3
      3819680.11     10146058.21      3818877.95     10146341.45
      3817592.66     10146492.21
#Sta/Elev= 30
  4149.3  341.71  4324.9  335.58    4396  331.86  4415.5  330.67  4443.3  329.85
  4499.8  324.95  4537.2  322.81  4592.6  318.56    4658  315.91  4680.1  313.88
  4686.9  314.19  4703.2  312.28  4724.4  313.75    4764  312.32  4904.7  311.85
  5058.5  310.34  5221.6  311.92  5385.4  313.82  5453.2  316.73  5556.8  317.58
    5615  319.77  5654.6  321.22  5694.8  320.37  5723.2  323.52  5936.5  329.93
  5981.3  333.02  6071.1  336.97  6107.6  340.11  6208.3  345.47  6294.1  348.78
#Mann= 11 ,-1 , 0
  4149.3     .17       0    4396     .11       0  4415.5     .17       0
  4537.2     .15       0    4658     .17       0  4686.9     .11       0
    4764     .17       0  4904.7     .06       0  5221.6     .11       0
    5615     .15       0  5981.3     .17       0
#XS Ineff= 2 , 0
       0  4724.4  313.75               0
Permanent Ineff=
       F       F
Bank Sta=4904.7,5221.6
XS Rating Curve= 0 ,0
Exp/Cntr=0.3,0.1

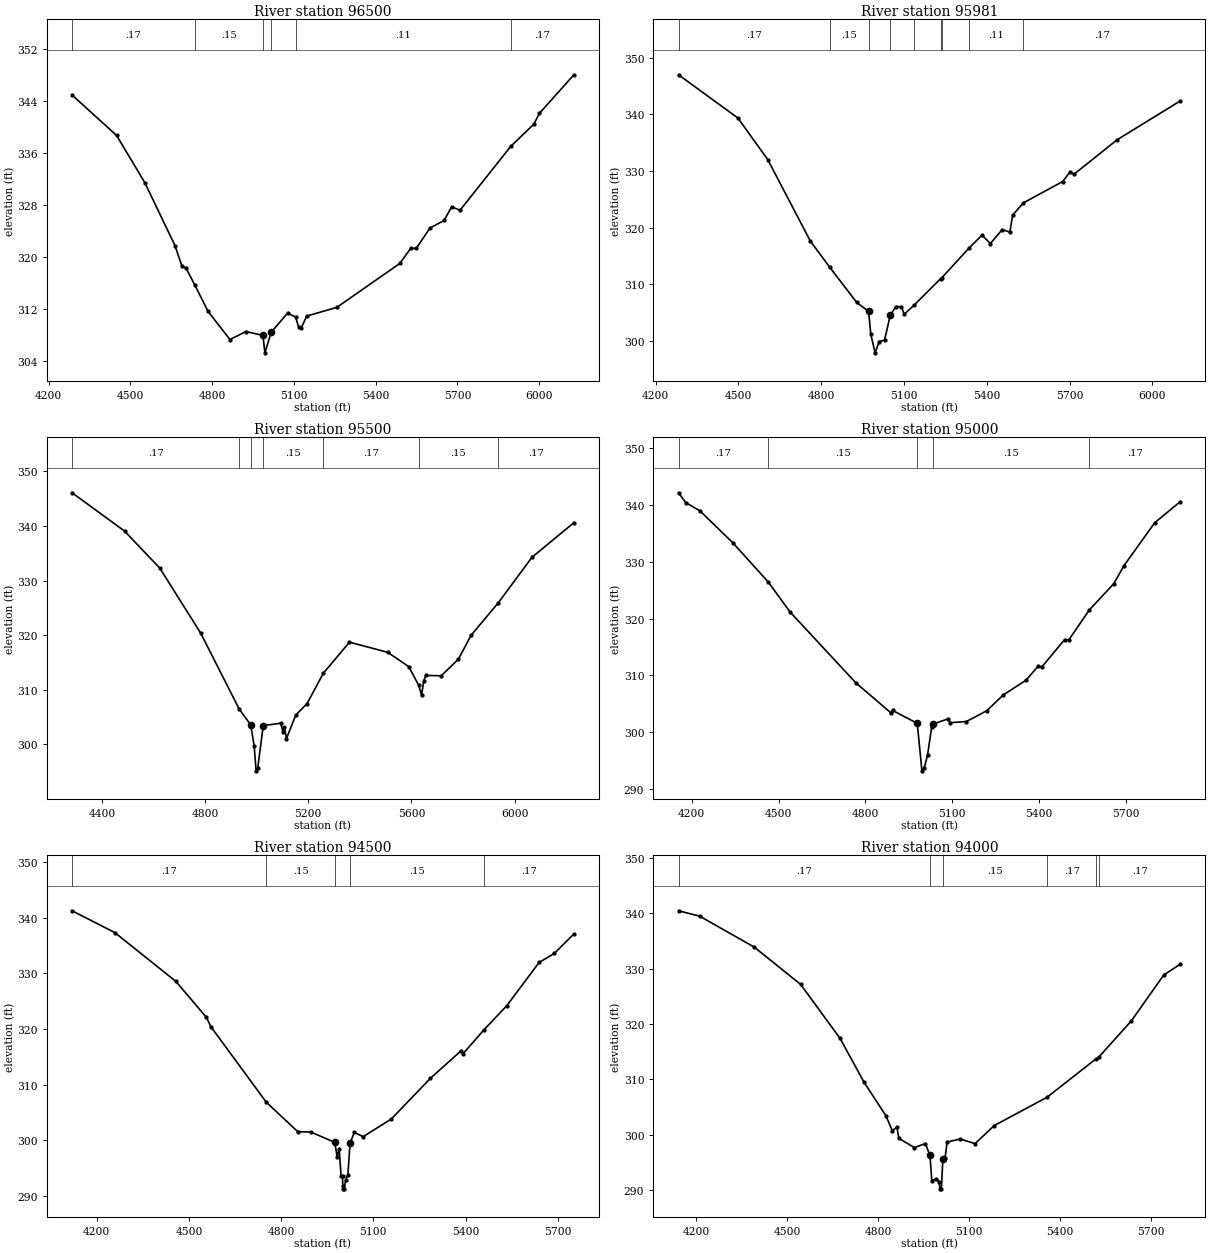
Type RM Length L Ch R = 1 ,96500   ,519,519,519
BEGIN DESCRIPTION:
STEWARTS CREEK 190.0
END DESCRIPTION:
XS GIS Cut Line= 3
      3819632.41     10145815.15      3818924.11     10145905.22
      3817801.83     10145802.23
#Sta/Elev= 30
    4286  344.98  4449.4  338.74  4552.7  331.48  4663.6  321.76  4689.2  318.57
  4703.9   318.3  4736.5  315.67  4784.5  311.64  4865.2  307.27  4924.1  308.51
  4986.2   307.9  4993.5  305.22  5016.3  308.38  5076.6  311.34  5106.1  310.74
  5116.8  309.27  5126.8  309.06  5146.9  310.89  5257.3  312.23  5488.3     319
  5528.5  321.34  5548.6  321.32  5598.8  324.45  5650.6  325.63  5679.1  327.75
  5709.2   327.2  5896.1  337.09  5980.5   340.5  6000.4  342.14    6127   348.1
#Mann= 6 ,-1 , 0
    4286     .17       0  4736.5     .15       0  4986.2     .04       0
  5016.3     .17       0  5106.1     .11       0  5896.1     .17       0
#XS Ineff= 2 , 0
       0                  5076.6       0  311.34
Permanent Ineff=
       F       F
Bank Sta=4986.2,5016.3
XS Rating Curve= 0 ,0
Exp/Cntr=0.3,0.1

Type RM Length L Ch R = 1 ,95981   ,481,481,481
BEGIN DESCRIPTION:
STEWARTS CREEK 189.0
END DESCRIPTION:
XS GIS Cut Line= 3
      3819671.45     10145697.97      3818968.13     10145560.13
      3817874.58     10145428.87
#Sta/Elev= 30
  4283.3  346.99  4498.5  339.35  4606.5  332.02    4761  317.62  4831.3     313
  4928.9  306.79    4972  305.21  4979.9  301.17  4995.5   297.9  5010.3  299.89
  5029.8  300.15  5050.6  304.56  5070.8  306.08  5090.9  306.04    5101  304.71
  5137.2  306.34  5232.6  310.98  5236.1   311.1  5335.1  316.36    5383  318.68
  5413.2   317.2  5456.1  319.66  5483.7  319.22  5493.8  322.21    5533  324.38
  5675.1  328.14  5702.8   329.9  5715.4   329.4  5872.3  335.51  6101.4  342.38
#Mann= 9 ,-1 , 0
  4283.3     .17       0  4831.3     .15       0    4972     .04       0
  5050.6     .15       0  5137.2     .11       0  5232.6     .15       0
  5236.1     .17       0  5335.1     .11       0    5533     .17       0
Bank Sta=4972,5050.6
XS Rating Curve= 0 ,0
Exp/Cntr=0.3,0.1

Type RM Length L Ch R = 1 ,95500   ,500,500,500
BEGIN DESCRIPTION:
STEWARTS CREEK 188.0
END DESCRIPTION:
XS GIS Cut Line= 3
      3819719.15     10145602.46      3819129.54     10145195.52
      3818043.85     10144617.25
#Sta/Elev= 30
  4283.6  346.09  4487.1  339.08  4624.3  332.27  4782.5  320.39    4932  306.47
  4976.6  303.59  4989.9  299.76  4997.5  295.17  5003.8  295.67  5025.2  303.45
  5092.6  303.89  5101.7  302.36  5107.4  303.16  5115.2  301.07  5151.3  305.38
  5195.2  307.49  5258.5  313.06  5359.6  318.73  5507.7  316.88  5589.9  314.24
  5627.5   310.9  5639.5  309.04  5647.7  311.64  5655.8  312.64  5715.7  312.58
    5782  315.61  5831.6     320  5936.8  325.93  6067.5  334.27  6230.1  340.61
#Mann= 7 ,-1 , 0
  4283.6     .17       0    4932     .15       0  4976.6     .04       0
  5025.2     .15       0  5258.5     .17       0  5627.5     .15       0
  5936.8     .17       0
Bank Sta=4976.6,5025.2
XS Rating Curve= 0 ,0
Exp/Cntr=0.3,0.1

Type RM Length L Ch R = 1 ,95000   ,500,500,500
BEGIN DESCRIPTION:
STEWARTS CREEK 187.0
END DESCRIPTION:
XS GIS Cut Line= 3
      3819931.88     10145342.09      3819307.05     10144772.17
      3818691.71     10144132.36
#Sta/Elev= 30
  4154.3  342.17  4179.1  340.45  4228.4  338.98  4341.9  333.36  4464.3  326.45
  4539.9  321.15  4766.8  308.69  4887.1  303.44  4893.9  303.83    4979  301.55
    4995  293.19    5003  293.69  5014.5  295.97  5028.6  300.88 5032.23301.4037
    5085  302.34  5092.2  301.67  5148.8  301.88  5219.5  303.79  5276.1  306.56
  5353.8  309.12  5396.3   311.6  5410.4  311.56  5488.1  316.31  5502.2  316.23
  5572.7  321.49  5657.9  326.17  5693.4  329.36  5799.4   336.9  5887.7  340.62
#Mann= 5 ,-1 , 0
  4154.3     .17       0  4464.3     .15       0    4979     .04       0
 5032.23     .15       0  5572.7     .17       0
Bank Sta=4979,5032.23
XS Rating Curve= 0 ,0
Exp/Cntr=0.3,0.1

Type RM Length L Ch R = 1 ,94500   ,500,500,500
BEGIN DESCRIPTION:
STEWARTS CREEK 186.0
END DESCRIPTION:
XS GIS Cut Line= 3
      3820148.01     10145057.36      3819485.32      10144477.9
      3818951.44     10143947.59
#Sta/Elev= 30
  4119.7  341.22  4258.9   337.3  4457.3  328.55  4556.9  322.08  4571.2  320.42
  4751.3  306.87    4854  301.56  4896.7  301.48  4974.6  299.64  4982.1  297.04
  4988.8   298.5    4995  293.66    5000  293.66  5000.4  291.79  5000.8  291.29
  5005.3  291.29  5010.1   292.9  5017.2  293.83  5024.3  299.49  5038.4  301.44
  5066.7  300.65  5158.6  303.83  5285.9  311.15  5384.9  316.05  5391.9  315.54
  5458.9  319.78  5533.4  324.12  5639.4  331.94  5688.9  333.56  5752.5  337.06
#Mann= 5 ,-1 , 0
  4119.7     .17       0  4751.3     .15       0  4974.6     .04       0
  5024.3     .15       0  5458.9     .17       0
Bank Sta=4974.6,5024.3
XS Rating Curve= 0 ,0
Exp/Cntr=0.3,0.1

Type RM Length L Ch R = 1 ,94000   ,478,478,478
BEGIN DESCRIPTION:
STEWARTS CREEK 185.0
END DESCRIPTION:
XS GIS Cut Line= 3
      3820222.84     10144981.68      3819758.37     10144258.85
      3819202.83     10143688.22
#Sta/Elev= 30
  4140.8  340.47  4210.8  339.49  4391.1  333.88  4543.7  327.15  4673.9  317.38
  4752.5  309.49  4825.1   303.4  4846.3  300.67  4861.4  301.38  4867.4  299.32
  4918.9  297.64  4955.2  298.37  4970.4  296.23  4976.4  291.67  4991.6     292
    5000  291.48  5003.6  290.18  5008.1  290.18  5012.9   295.6    5020  295.69
    5027  298.64  5069.5   299.2  5119.1  298.36  5182.6  301.63  5356.6  306.74
  5518.2  313.69  5527.7  314.03  5635.3  320.59  5741.3  328.83  5796.4  330.83
#Mann= 6 ,-1 , 0
  4140.8     .17       0  4970.4     .04       0  5012.9     .15       0
  5356.6     .17       0  5518.2     .15       0  5527.7     .17       0
#XS Ineff= 2 , 0
       0  4861.4  301.38               0
Permanent Ineff=
       F       F
Bank Sta=4970.4,5012.9
XS Rating Curve= 0 ,0
Exp/Cntr=0.3,0.1

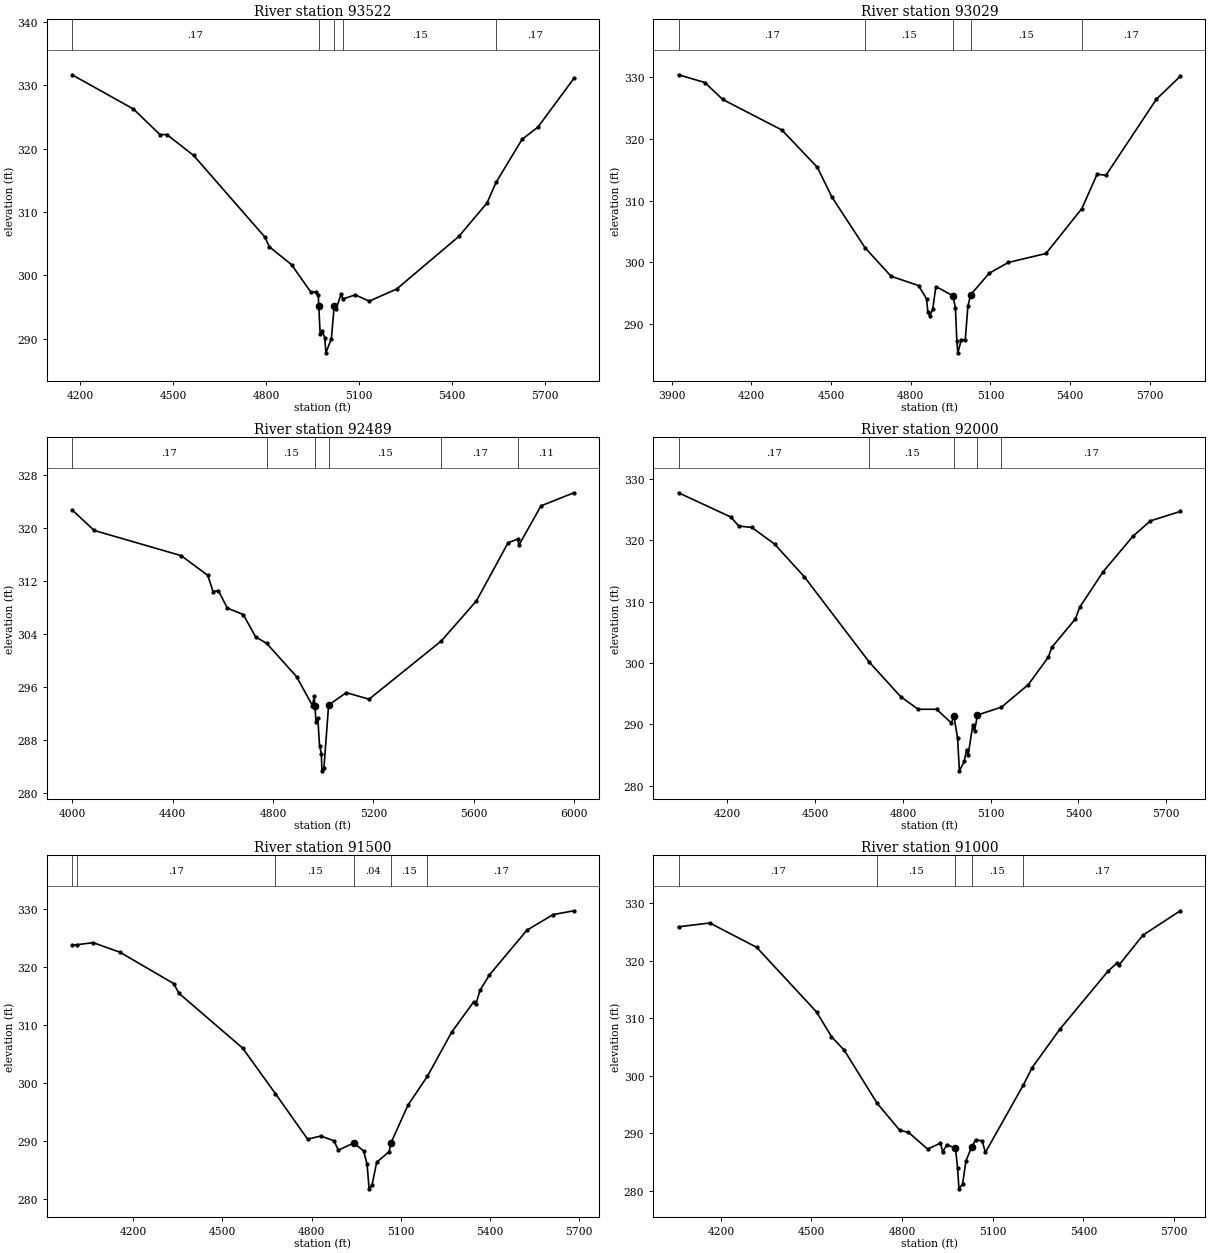
Type RM Length L Ch R = 1 ,93522   ,493,493,493
BEGIN DESCRIPTION:
STEWARTS CREEK 184.0
END DESCRIPTION:
XS GIS Cut Line= 3
      3820470.22     10144573.67      3819997.95     10143896.49
      3819281.88     10143554.13
#Sta/Elev= 30
  4174.4  331.67  4372.6  326.26    4458  322.23  4480.4  322.23  4566.7  318.93
  4796.2  306.07    4811  304.51  4882.6  301.69  4945.6  297.31  4960.2   297.4
  4968.9  296.83  4970.5295.2194    4975  290.69  4982.2  291.18  4989.9  290.15
  4993.5  287.77  5011.2  290.01  5020.4   295.2    5026  294.68  5043.1  297.08
  5048.5  296.28  5088.5  296.92  5133.1  295.93  5221.8  297.84  5422.6  306.15
  5513.3  311.42    5543  314.71  5626.6  321.48  5677.5  323.39  5793.7  331.09
#Mann= 5 ,-1 , 0
  4174.4     .17       0  4970.5     .04       0  5020.4     .17       0
  5048.5     .15       0    5543     .17       0
Bank Sta=4970.5,5020.4
XS Rating Curve= 0 ,0
Exp/Cntr=0.3,0.1

Type RM Length L Ch R = 1 ,93029   ,540,540,540
BEGIN DESCRIPTION:
STEWARTS CREEK 183.0
END DESCRIPTION:
XS GIS Cut Line= 3
      3820522.31     10144543.31      3820132.99     10143542.15
       3819328.7     10143410.46
#Sta/Elev= 30
  3925.8  330.34  4024.8  329.09  4092.2  326.35  4315.2   321.4  4448.6  315.37
    4503  310.59  4627.9  302.38    4726  297.77  4829.5  296.26  4859.4  294.13
  4864.7  291.93  4872.4  291.36  4883.1  292.53  4894.6  296.11  4958.2  294.63
  4968.2   292.7  4973.6  287.29  4977.4  285.39  4990.4  287.51  5005.2  287.44
  5015.3  292.93  5025.5  294.78  5095.4  298.25  5167.3     300  5309.2  301.45
  5444.4  308.72  5501.7  314.27    5535  314.09  5724.7  326.38    5815  330.11
#Mann= 5 ,-1 , 0
  3925.8     .17       0  4627.9     .15       0  4958.2     .04       0
  5025.5     .15       0  5444.4     .17       0
Bank Sta=4958.2,5025.5
XS Rating Curve= 0 ,0
Exp/Cntr=0.3,0.1

Type RM Length L Ch R = 1 ,92489   ,489,489,489
BEGIN DESCRIPTION:
STEWARTS CREEK 182.0
END DESCRIPTION:
XS GIS Cut Line= 3
      3821056.15     10144057.17      3820359.57     10143339.41
      3819367.79      10143219.5
#Sta/Elev= 30
  3999.8  322.79  4087.8  319.67  4434.3  315.86  4540.3  312.88  4561.6  310.43
  4582.7  310.57  4618.2  307.93  4681.8  306.95  4731.4  303.55  4775.2  302.59
    4894  297.56  4957.5  293.18  4964.7  294.61  4967.3293.1691  4971.7  290.73
  4978.9  291.28  4985.8   287.1    4993  285.88  4995.2   283.3  5003.4   283.8
  5021.9  293.25  5092.4  295.13    5183  294.14  5470.9  302.95  5611.1  309.03
    5737  317.81  5775.9  318.38    5780  317.44    5868  323.39    5999  325.37
#Mann= 6 ,-1 , 0
  3999.8     .17       0  4775.2     .15       0  4967.3     .04       0
  5021.9     .15       0  5470.9     .17       0  5775.9     .11       0
Bank Sta=4967.3,5021.9
XS Rating Curve= 0 ,0
Exp/Cntr=0.3,0.1

Type RM Length L Ch R = 1 ,92000   ,500,500,500
BEGIN DESCRIPTION:
STEWARTS CREEK 181.0
END DESCRIPTION:
XS GIS Cut Line= 3
      3821186.38     10143449.54      3820386.32     10142905.69
      3819736.68     10142533.72
#Sta/Elev= 30
  4032.6  327.74  4211.4  323.79  4238.4  322.32  4283.3  322.09  4361.1  319.38
  4462.9  314.05  4684.9  300.15  4792.6  294.51    4852  292.47    4915  292.47
  4965.8  290.23    4974  291.45  4986.8  287.79  4993.1  282.44  5009.8  283.99
  5017.4   285.9  5023.2  285.08    5039  289.93  5044.8  288.89  5054.9  291.53
  5136.9  292.82  5228.7  296.48  5296.6  300.92  5309.4  302.58    5390  307.21
  5404.5  309.09  5485.1  314.91  5587.3  320.69  5646.3  323.16  5748.6   324.7
#Mann= 5 ,-1 , 0
  4032.6     .17       0  4684.9     .15       0    4974     .04       0
  5054.9     .15       0  5136.9     .17       0
Bank Sta=4974,5054.9
XS Rating Curve= 0 ,0
Exp/Cntr=0.3,0.1

Type RM Length L Ch R = 1 ,91500   ,500,500,500
BEGIN DESCRIPTION:
STEWARTS CREEK 180.0
END DESCRIPTION:
XS GIS Cut Line= 3
      3821481.49     10142954.73      3820575.64     10142517.18
       3819927.7      10142303.7
#Sta/Elev= 30
    3994  323.69  4009.6  323.79  4065.1  324.15  4155.5  322.49  4336.3  317.09
  4353.3  315.44  4567.8  305.99  4678.4  298.13  4786.5   290.3    4831  290.85
  4875.4  290.02  4889.8  288.41    4942  289.66  4974.7  288.28  4986.4  286.04
  4993.3  281.75  5003.2  282.37  5018.7  286.33  5060.8  288.16  5066.8  289.65
    5124  296.16  5189.7  301.16  5271.4  308.75  5345.1  313.95  5352.7  313.57
  5366.2  315.91  5397.8  318.57  5524.1  326.29  5612.2  328.98  5682.2  329.64
#Mann= 6 ,-1 , 0
    3994     .11       0  4009.6     .17       0  4678.4     .15       0
    4942     .04       0  5066.8     .15       0  5189.7     .17       0
Bank Sta=4942,5066.8
XS Rating Curve= 0 ,0
Exp/Cntr=0.3,0.1

Type RM Length L Ch R = 1 ,91000   ,500,500,500
BEGIN DESCRIPTION:
STEWARTS CREEK 179.0
END DESCRIPTION:
XS GIS Cut Line= 3
      3821537.94     10142876.63      3820888.41     10142197.27
       3820214.1     10141943.44
#Sta/Elev= 30
  4060.1  325.91  4163.2  326.58  4318.6  322.34  4516.7   311.1  4566.1   306.8
  4608.6  304.42  4717.6  295.18  4792.6  290.47  4820.9  290.14  4884.4  287.23
  4926.9  288.27  4934.1  286.74  4948.2  288.01  4976.5  287.36  4983.5  283.88
    4988  280.31    5000  281.16  5011.3  285.19  5029.6  287.54  5043.3  288.84
  5065.1  288.65  5075.4  286.64  5200.4  298.32  5230.4  301.42  5321.1  308.04
    5481  318.18  5511.2  319.62  5516.6  319.19  5596.6  324.45  5720.5   328.7
#Mann= 5 ,-1 , 0
  4060.1     .17       0  4717.6     .15       0  4976.5     .04       0
  5029.6     .15       0  5200.4     .17       0
Bank Sta=4976.5,5029.6
XS Rating Curve= 0 ,0
Exp/Cntr=0.3,0.1