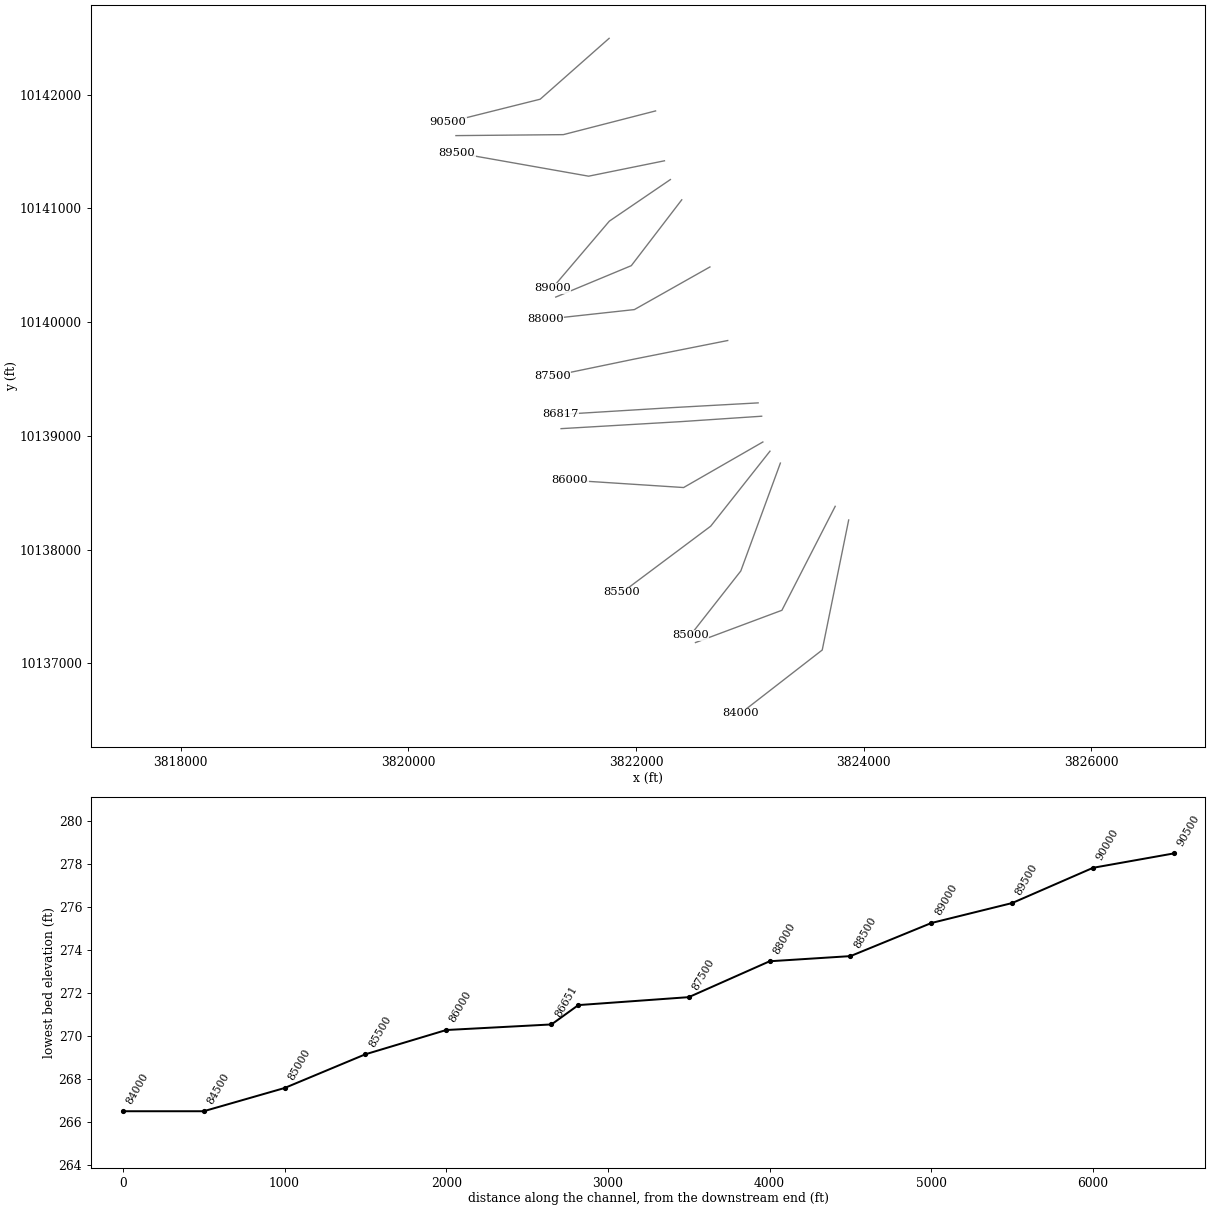
HEC-RAS study STEWARTS CREEK.prj: STEWARTS CREEK Base Level Engineering

--- STEWARTS CREEK.g01 (geometry) --- (continued)

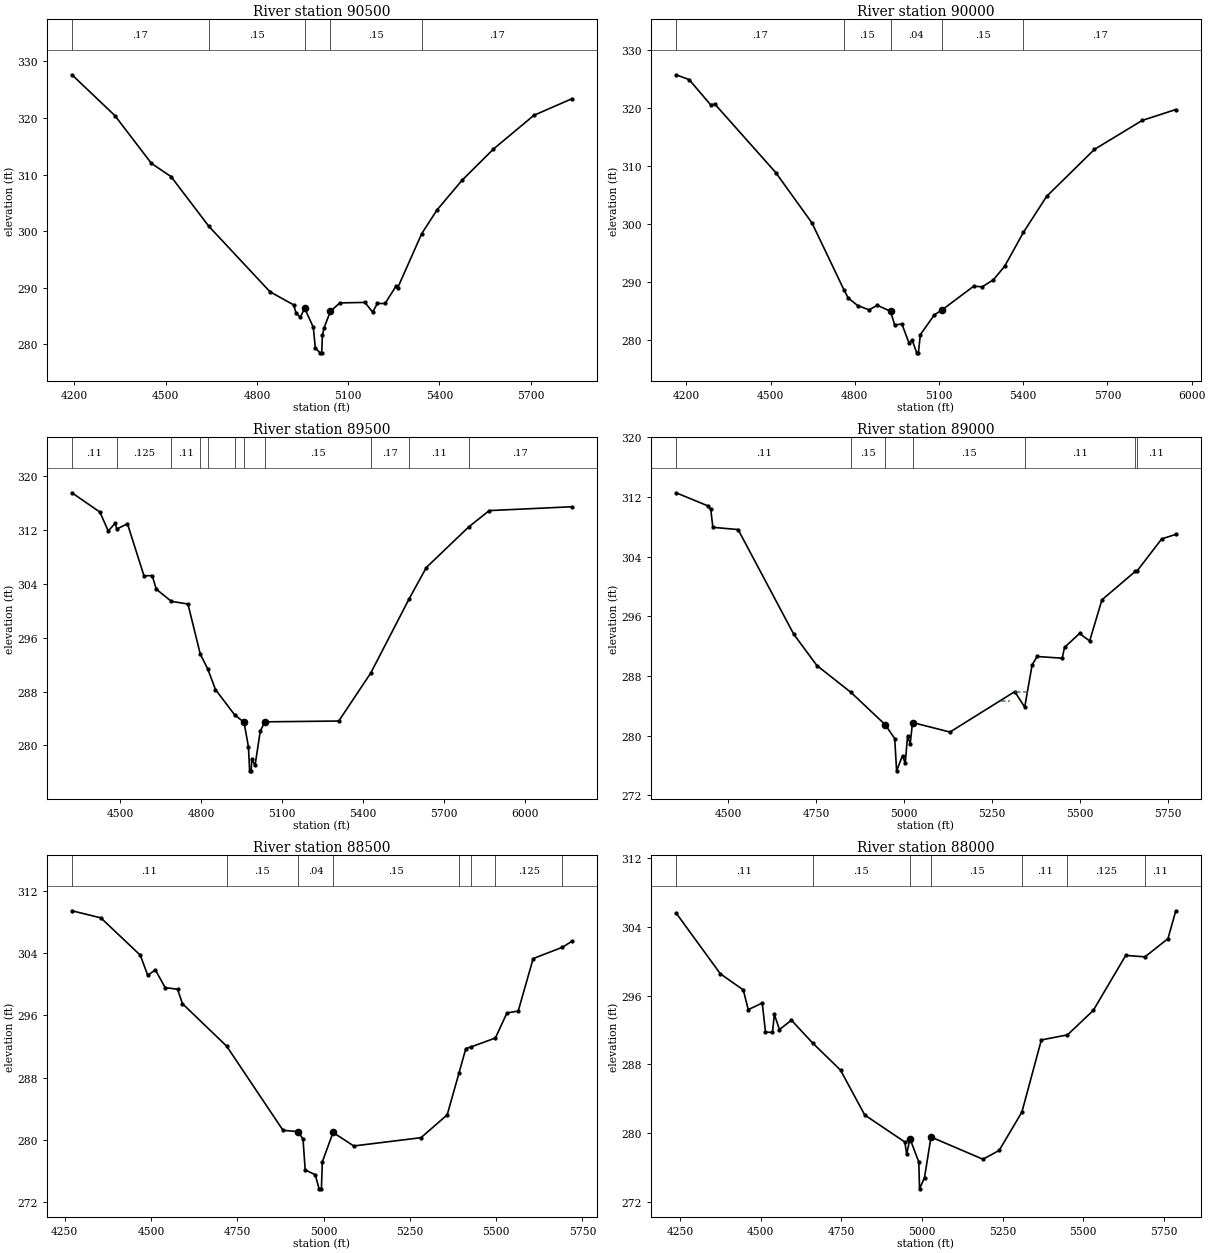
Type RM Length L Ch R = 1 ,90500   ,500,500,500
BEGIN DESCRIPTION:
STEWARTS CREEK 178.0
END DESCRIPTION:
XS GIS Cut Line= 3
      3821763.64     10142494.69      3821158.25      10141959.7
      3820348.68     10141756.82
#Sta/Elev= 30
  4192.1  327.64  4333.3  320.42  4453.4  311.98  4517.8  309.65  4641.9  300.88
  4843.2  289.29    4921  286.98  4928.6  285.54  4942.8   284.8    4957  286.38
  4985.4  283.03  4992.1  279.37  5007.5  278.51    5013  278.51  5015.4  281.65
    5021  282.96  5041.6  285.84  5072.6  287.33    5155  287.42  5180.2  285.72
  5196.3  287.23  5221.3  287.23  5257.4   290.3  5262.5  289.96  5341.9  299.58
  5392.2  303.77  5474.6  309.01  5577.7  314.52  5710.4  320.47  5834.6  323.39
#Mann= 5 ,-1 , 0
  4192.1     .17       0  4641.9     .15       0    4957     .04       0
  5041.6     .15       0  5341.9     .17       0
Bank Sta=4957,5041.6
XS Rating Curve= 0 ,0
Exp/Cntr=0.3,0.1

Type RM Length L Ch R = 1 ,90000   ,500,500,500
BEGIN DESCRIPTION:
STEWARTS CREEK 177.0
END DESCRIPTION:
XS GIS Cut Line= 3
      3822171.59     10141856.64      3821361.68      10141648.2
      3820418.12     10141639.63
#Sta/Elev= 30
  4163.7   325.7  4210.1  324.87  4286.3  320.55  4301.8  320.65  4518.6  308.87
  4647.6   300.2  4761.2  288.72  4776.8  287.28  4810.4  285.98  4851.1  285.24
    4880  286.02  4927.4  285.01    4942  282.66  4968.1  282.79  4993.6  279.48
  5004.4  280.04  5020.9  277.84  5026.7  277.84  5033.8  280.98  5083.8  284.39
  5109.6285.1776  5223.8  289.31  5253.8   289.2  5293.8  290.41  5333.8  292.73
  5400.9  298.58  5483.8  304.79  5653.9  312.86  5823.9  317.84  5943.6  319.72
#Mann= 5 ,-1 , 0
  4163.7     .17       0  4761.2     .15       0  4927.4     .04       0
  5109.6     .15       0  5400.9     .17       0
Bank Sta=4927.4,5109.6
XS Rating Curve= 0 ,0
Exp/Cntr=0.3,0.1

Type RM Length L Ch R = 1 ,89500   ,500,500,500
BEGIN DESCRIPTION:
STEWARTS CREEK 176.0
END DESCRIPTION:
XS GIS Cut Line= 3
      3822249.68     10141418.27      3821583.78     10141283.04
      3820426.84     10141487.72
#Sta/Elev= 30
  4320.5  317.57  4424.4  314.69    4455  311.88  4481.4  313.06  4486.6  312.17
  4526.5  312.96  4587.8  305.21  4618.3  305.25  4633.3  303.23  4689.2  301.42
  4750.9  301.02  4796.9  293.54  4824.1  291.39    4853   288.3    4924  284.54
  4959.1283.4221  4975.4  279.77  4979.8   276.2  4985.6   276.2  4987.8  277.92
    5000  277.01  5019.3  282.11  5036.5  283.49  5310.7  283.61  5429.6  290.77
  5571.1  301.74  5635.6  306.45  5792.6  312.48  5869.2  314.92  6174.9  315.49
#Mann= 11 ,-1 , 0
  4320.5     .11       0  4486.6    .125       0  4689.2     .11       0
  4796.9     .17       0  4824.1     .15       0    4924     .17       0
  4959.1     .04       0  5036.5     .15       0  5429.6     .17       0
  5571.1     .11       0  5792.6     .17       0
Bank Sta=4959.1,5036.5
XS Rating Curve= 0 ,0
Exp/Cntr=0.3,0.1

Type RM Length L Ch R = 1 ,89000   ,500,500,500
BEGIN DESCRIPTION:
STEWARTS CREEK 175.0
END DESCRIPTION:
XS GIS Cut Line= 3
       3822301.8     10141253.34      3821765.66      10140887.8
      3821264.49     10140298.49
#Sta/Elev= 30
  4351.1  312.55  4440.8  310.81  4449.7  310.33  4455.8  307.92  4527.6  307.62
  4686.1  293.58  4751.9  289.39  4849.1  285.78  4946.3  281.46  4973.4   279.6
  4978.8  275.27  4995.6  277.31  5003.3  276.27  5009.9  279.88  5017.6  278.92
  5024.1  281.75  5130.7  280.47  5315.2  285.89  5343.5  283.81  5364.6  289.48
  5378.9   290.6  5450.3  290.37  5456.8  291.82  5499.7  293.69  5528.3  292.68
  5563.4   298.2  5658.6  302.02  5663.4  302.07  5733.6  306.37  5773.6  306.97
#Mann= 7 ,-1 , 0
  4351.1     .11       0  4849.1     .15       0  4946.3     .04       0
  5024.1     .15       0  5343.5     .11       0  5658.6    .125       0
  5663.4     .11       0
#XS Ineff= 2 ,-1
  5272.3  5300.9   284.7  5315.2  5350.3  285.89
Permanent Ineff=
       F       F
Bank Sta=4946.3,5024.1
XS Rating Curve= 0 ,0
Exp/Cntr=0.3,0.1

Type RM Length L Ch R = 1 ,88500   ,500,500,500
BEGIN DESCRIPTION:
STEWARTS CREEK 174.0
END DESCRIPTION:
XS GIS Cut Line= 3
      3822401.62     10141075.37      3821958.61     10140496.54
      3821294.88     10140220.37
#Sta/Elev= 30
  4271.1   309.4  4354.8  308.49  4469.1   303.7  4490.6  301.13  4512.7  301.82
    4541  299.55  4577.1  299.33  4591.3  297.48  4719.2  292.04  4882.6  281.24
  4926.1  281.07  4940.6   280.1  4946.9  276.15    4976  275.54  4987.1  273.73
  4993.9  273.73  4996.5  277.19  5027.6  280.96  5087.5  279.23  5282.3  280.29
  5358.3  283.22  5392.8  288.63  5412.3  291.73  5428.3  291.95    5498  293.08
  5531.5   296.3    5564  296.53  5607.4  303.27  5692.1  304.72  5718.9  305.47
#Mann= 8 ,-1 , 0
  4271.1     .11       0  4719.2     .15       0  4926.1     .04       0
  5027.6     .15       0  5392.8     .11       0  5428.3     .15       0
    5498    .125       0  5692.1     .11       0
Bank Sta=4926.1,5027.6
XS Rating Curve= 0 ,0
Exp/Cntr=0.3,0.1

Type RM Length L Ch R = 1 ,88000   ,500,500,500
BEGIN DESCRIPTION:
STEWARTS CREEK 173.0
END DESCRIPTION:
XS GIS Cut Line= 3
      3822649.06     10140485.14      3821985.56     10140110.42
      3821203.71     10140025.05
#Sta/Elev= 30
    4238  305.63    4375  298.55  4446.1  296.67  4461.6  294.37  4504.9  295.14
    4515  291.75  4536.7  291.72  4542.4  293.82  4558.3  292.05  4595.4  293.14
  4660.7   290.5  4747.5  287.32  4822.6  282.09  4946.8  278.95  4952.5  277.53
  4962.7  279.34  4990.1  276.61  4992.3  273.49  5007.8  274.81  5027.9  279.53
  5188.8  276.94  5239.1  277.96  5309.6  282.44  5369.9  290.84  5450.9  291.43
  5530.8  294.28  5631.4  300.69    5691  300.52  5762.2  302.64  5786.5  305.89
#Mann= 7 ,-1 , 0
    4238     .11       0  4660.7     .15       0  4962.7     .04       0
  5027.9     .15       0  5309.6     .11       0  5450.9    .125       0
    5691     .11       0
Bank Sta=4962.7,5027.9
XS Rating Curve= 0 ,0
Exp/Cntr=0.3,0.1

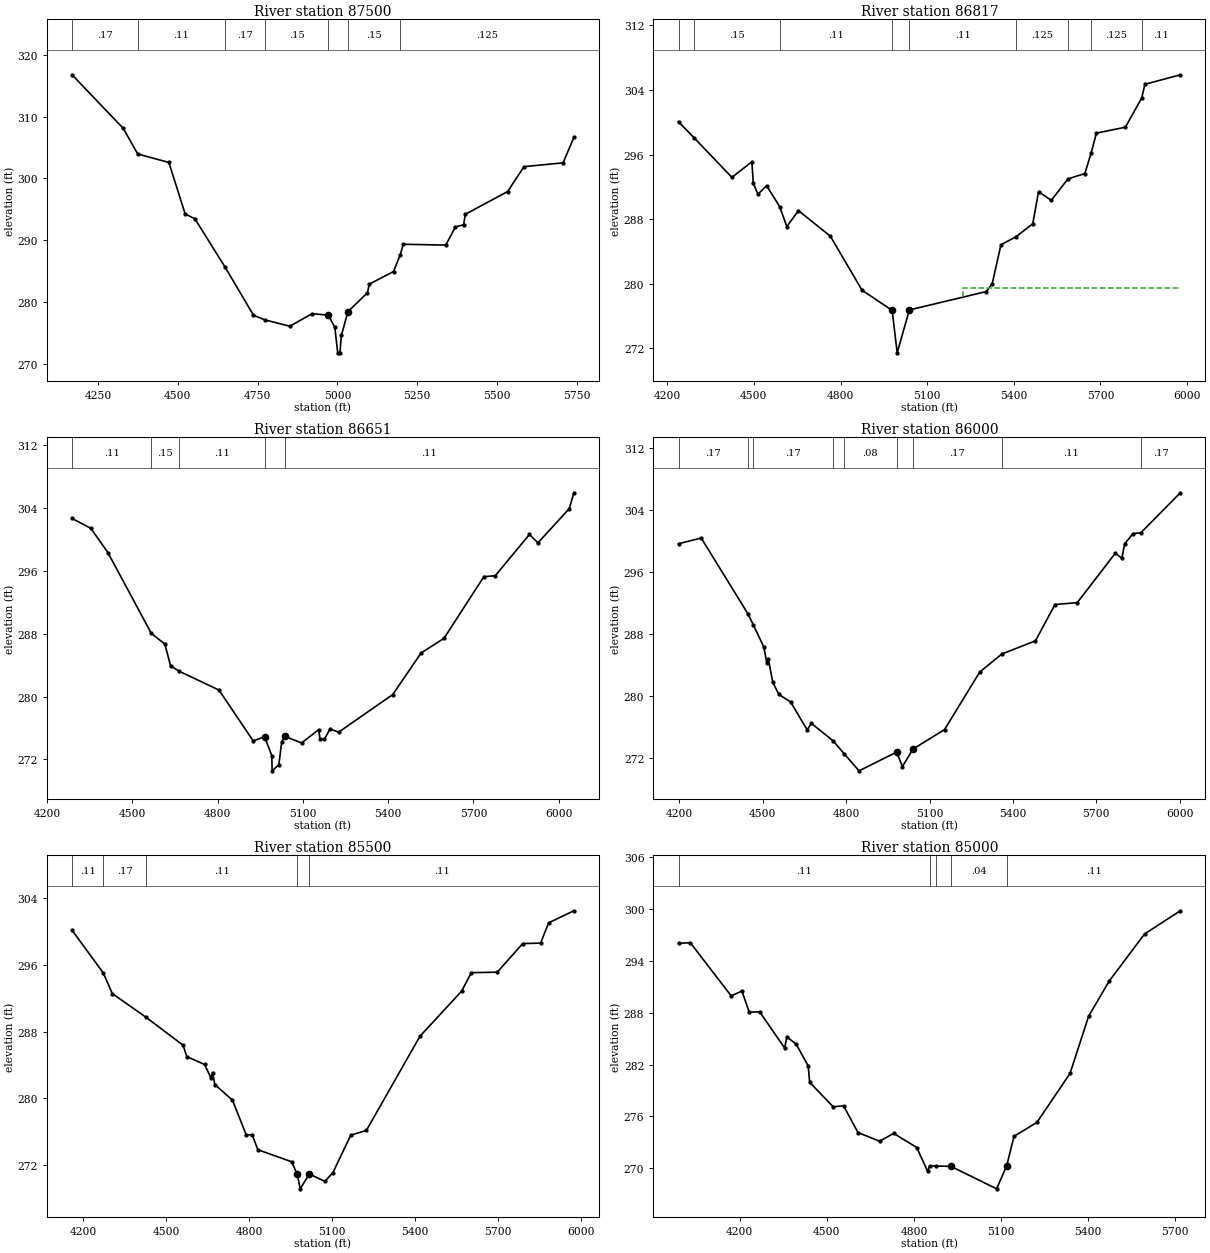
Type RM Length L Ch R = 1 ,87500   ,683,683,683
BEGIN DESCRIPTION:
STEWARTS CREEK 172.0
END DESCRIPTION:
XS GIS Cut Line= 3
      3822805.24     10139838.41      3821989.89     10139676.35
      3821264.82     10139525.99
#Sta/Elev= 30
  4168.7  316.76  4329.2  308.09  4374.3  303.96  4471.9  302.59  4522.9  294.28
  4553.5  293.48  4648.5  285.63    4737   277.9  4773.7  277.13  4850.9  276.12
  4920.5  278.15  4971.5  277.91  4991.9  275.92  5000.7  271.82  5007.8  271.82
  5012.3  274.64  5032.7  278.46    5094  281.54  5099.5  282.92  5175.7  284.96
  5196.5  287.67  5206.3  289.37  5339.1  289.23  5369.7  292.18  5395.3  292.52
  5400.4  294.21  5533.1  297.89  5584.2  301.91  5706.8  302.53  5740.5  306.63
#Mann= 7 ,-1 , 0
  4168.7     .17       0  4374.3     .11       0  4648.5     .17       0
  4773.7     .15       0  4971.5     .04       0  5032.7     .15       0
  5196.5    .125       0
#XS Ineff= 2 , 0
       0                  5099.5       0  282.92
Permanent Ineff=
       F       F
Bank Sta=4971.5,5032.7
XS Rating Curve= 0 ,0
Exp/Cntr=0.3,0.1

Type RM Length L Ch R = 1 ,86817   ,166,166,166
BEGIN DESCRIPTION:
STEWARTS CREEK 171.0
END DESCRIPTION:
XS GIS Cut Line= 3
      3823072.32     10139290.31      3822312.68     10139248.33
       3821337.9     10139188.74
#Sta/Elev= 30
  4239.2  300.05  4293.8  298.04    4424  293.17  4493.1   295.1  4498.1  292.43
  4514.1  291.08  4544.1  292.15  4589.6  289.54  4614.2  287.08  4654.3  289.05
  4764.5  285.91  4874.6   279.2 4978.88 276.703  4996.3  271.45  5038.4  276.76
  5305.4  279.04  5325.4  280.03  5355.5  284.82  5408.5  285.84  5465.7  287.43
  5485.7   291.4  5529.7  290.33  5587.5  292.98    5646  293.64  5667.4  296.14
  5686.1  298.65  5786.3  299.38  5843.2  303.02  5853.9  304.69  5976.6  305.87
#Mann= 9 ,-1 , 0
  4239.2     .11       0  4293.8     .15       0  4589.6     .11       0
 4978.88     .04       0  5038.4     .11       0  5408.5    .125       0
  5587.5     .11       0  5667.4    .125       0  5843.2     .11       0
#XS Ineff= 2 , 0
       0                  5225.2       0  279.51
Permanent Ineff=
       F       F
Bank Sta=4978.88,5038.4
XS Rating Curve= 0 ,0
Exp/Cntr=0.3,0.1

Type RM Length L Ch R = 1 ,86651   ,651,651,651
BEGIN DESCRIPTION:
STEWARTS CREEK 170.0
END DESCRIPTION:
XS GIS Cut Line= 3
      3823103.59     10139173.12      3822393.09     10139125.45
       3821341.7     10139063.81
#Sta/Elev= 30
  4287.9  302.67  4353.8  301.42  4413.9  298.33  4566.6  288.05  4614.4  286.68
  4634.4  283.92  4665.2  283.22  4804.8  280.83  4925.1  274.36  4965.2  274.88
  4990.5  272.49  4991.8  270.55  5015.3  271.33  5025.3  274.19  5035.3  274.96
  5095.4   274.1  5155.4  275.79  5160.4  274.55  5175.5  274.57  5195.6  275.88
  5225.6  275.47    5416  280.26  5516.1  285.56  5596.3  287.41  5736.5  295.26
  5776.6  295.38  5896.8  300.63  5926.8  299.57    6037  303.92  6053.2  305.94
#Mann= 5 ,-1 , 0
  4287.9     .11       0  4566.6     .15       0  4665.2     .11       0
  4965.2     .04       0  5035.3     .11       0
Bank Sta=4965.2,5035.3
XS Rating Curve= 0 ,0
Exp/Cntr=0.3,0.1

Type RM Length L Ch R = 1 ,86000   ,500,500,500
BEGIN DESCRIPTION:
STEWARTS CREEK 169.0
END DESCRIPTION:
XS GIS Cut Line= 3
      3823113.93     10138946.54      3822417.97     10138546.19
      3821417.87     10138611.07
#Sta/Elev= 30
  4197.1  299.62  4278.7  300.36  4447.4  290.53  4466.4  289.12  4504.3  286.25
  4514.4  284.24  4520.1  284.78  4535.9  281.73  4557.5  280.18  4600.6  279.17
  4659.6  275.59  4675.3  276.42  4753.5  274.15  4792.5  272.51  4846.5  270.29
  4981.5  272.71  5002.6  270.85  5040.2  273.09    5154  275.62  5280.7  283.05
  5360.2  285.38  5481.1  287.08  5551.3  291.77  5631.4  292.01  5768.6  298.41
  5791.8  297.72  5801.8   299.6  5831.9  300.93  5860.1  301.03  6002.2   306.2
#Mann= 9 ,-1 , 0
  4197.1     .17       0  4447.4     .11       0  4466.4     .17       0
  4753.5     .11       0  4792.5     .08       0  4981.5     .04       0
  5040.2     .17       0  5360.2     .11       0  5860.1     .17       0
#XS Ineff= 2 , 0
       0  4675.3  276.42               0
Permanent Ineff=
       F       F
Bank Sta=4981.5,5040.2
XS Rating Curve= 0 ,0
Exp/Cntr=0.3,0.1

Type RM Length L Ch R = 1 ,85500   ,500,500,500
BEGIN DESCRIPTION:
STEWARTS CREEK 168.0
END DESCRIPTION:
XS GIS Cut Line= 3
      3823176.46     10138865.82      3822655.93     10138206.54
      3821876.99     10137623.64
#Sta/Elev= 30
    4160  300.17  4272.3  295.07  4305.4  292.57  4426.9  289.74    4561  286.38
  4574.7  285.01  4638.8  284.07  4661.3  282.49  4667.7   283.1  4675.7  281.66
  4739.4   279.8  4789.6   275.6  4810.4  275.67  4831.2  273.85  4953.1  272.41
  4973.3270.9196  4984.5  269.16  5016.9  270.95  5073.2  270.05  5102.3   271.1
    5167   275.6  5223.2  276.16    5417  287.46  5567.1  292.85  5602.5  295.08
  5696.3  295.14    5788  298.57  5852.6  298.62  5881.8  301.06  5972.9   302.5
#Mann= 5 ,-1 , 0
    4160     .11       0  4272.3     .17       0  4426.9     .11       0
  4973.3     .04       0  5016.9     .11       0
Bank Sta=4973.3,5016.9
XS Rating Curve= 0 ,0
Exp/Cntr=0.3,0.1

Type RM Length L Ch R = 1 ,85000   ,500,500,500
BEGIN DESCRIPTION:
STEWARTS CREEK 167.0
END DESCRIPTION:
XS GIS Cut Line= 3
      3823267.86      10138761.1      3822920.17     10137812.62
      3822477.67      10137248.2
#Sta/Elev= 30
  3989.8  296.05  4030.3  296.12  4170.9  289.96    4208  290.51  4233.1  288.07
    4269  288.11  4355.1  283.91  4362.6   285.2  4394.6  284.37    4436  281.84
  4441.3  279.94  4522.2   277.1    4558  277.21  4607.6  274.11  4682.1  273.11
  4730.4  274.02  4809.9  272.38  4847.1  269.63  4854.6  270.27  4877.3  270.23
  4927.1   270.2  5084.8  267.59 5119.47270.2693  5144.8  273.68  5223.5  275.29
  5337.4  280.96  5401.5   287.6  5472.1  291.66  5594.1  297.13  5717.2  299.82
#Mann= 5 ,-1 , 0
  3989.8     .11       0  4854.6     .17       0  4877.3     .15       0
  4927.1     .04       0 5119.47     .11       0
Bank Sta=4927.1,5119.47
XS Rating Curve= 0 ,0
Exp/Cntr=0.3,0.1

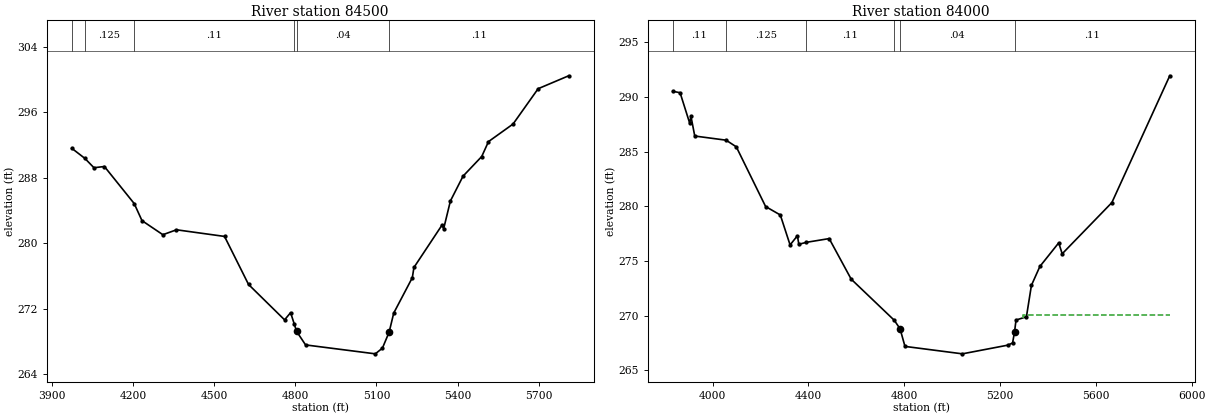
Type RM Length L Ch R = 1 ,84500   ,500,500,500
BEGIN DESCRIPTION:
STEWARTS CREEK 166.0
END DESCRIPTION:
XS GIS Cut Line= 3
      3823749.38     10138381.01      3823281.29     10137467.22
      3822521.99     10137183.44
#Sta/Elev= 30
  3973.3  291.62    4022  290.38  4055.5  289.24  4094.2  289.39  4204.4  284.86
  4233.1  282.78  4310.3  281.06  4360.7  281.66  4538.3  280.85  4627.1  274.98
  4760.3  270.66  4782.5  271.54  4796.2  270.14  4804.7  269.25  4837.9   267.6
  5095.8  266.51    5122  267.21  5146.9  269.17  5163.8  271.49  5232.5  275.81
  5238.5  277.06    5343  282.27  5348.3  281.78  5373.3  285.18    5420  288.21
  5489.1  290.61  5514.1  292.43    5605  294.58  5697.6  298.89  5810.6  300.47
#Mann= 6 ,-1 , 0
  3973.3     .11       0    4022    .125       0  4204.4     .11       0
  4796.2     .15       0  4804.7     .04       0  5146.9     .11       0
#XS Ineff= 2 , 0
       0  4782.5  271.54               0
Permanent Ineff=
       F       F
Bank Sta=4804.7,5146.9
XS Rating Curve= 0 ,0
Exp/Cntr=0.3,0.1

Type RM Length L Ch R = 1 ,84000   ,500,500,500
BEGIN DESCRIPTION:
STEWARTS CREEK 165.0
END DESCRIPTION:
XS GIS Cut Line= 3
      3823867.84     10138261.03      3823635.51     10137118.11
      3822917.83     10136561.06
#Sta/Elev= 30
  3833.7  290.52  3864.3  290.39  3904.5   287.6  3909.6  288.24  3925.5  286.43
  4056.4  286.05    4099  285.44  4221.4  279.98  4282.7  279.21  4323.5  276.47
  4354.1  277.31    4360  276.53    4392  276.71  4486.7  277.05  4578.6  273.34
  4758.4  269.58  4782.7   268.8  4803.1  267.19  5042.8  266.51  5231.4   267.3
  5252.3   267.5  5260.4  268.49  5266.7   269.6  5310.2   269.9    5331  272.77
  5366.3   274.5    5445  276.66  5459.5  275.66  5666.8  280.34  5908.5  291.94
#Mann= 6 ,-1 , 0
  3833.7     .11       0  4056.4    .125       0    4392     .11       0
  4758.4     .15       0  4782.7     .04       0  5260.4     .11       0
#XS Ineff= 2 , 0
       0                  5295.7       0  270.06
Permanent Ineff=
       F       F
Bank Sta=4782.7,5260.4
XS Rating Curve= 0 ,0
Exp/Cntr=0.3,0.1