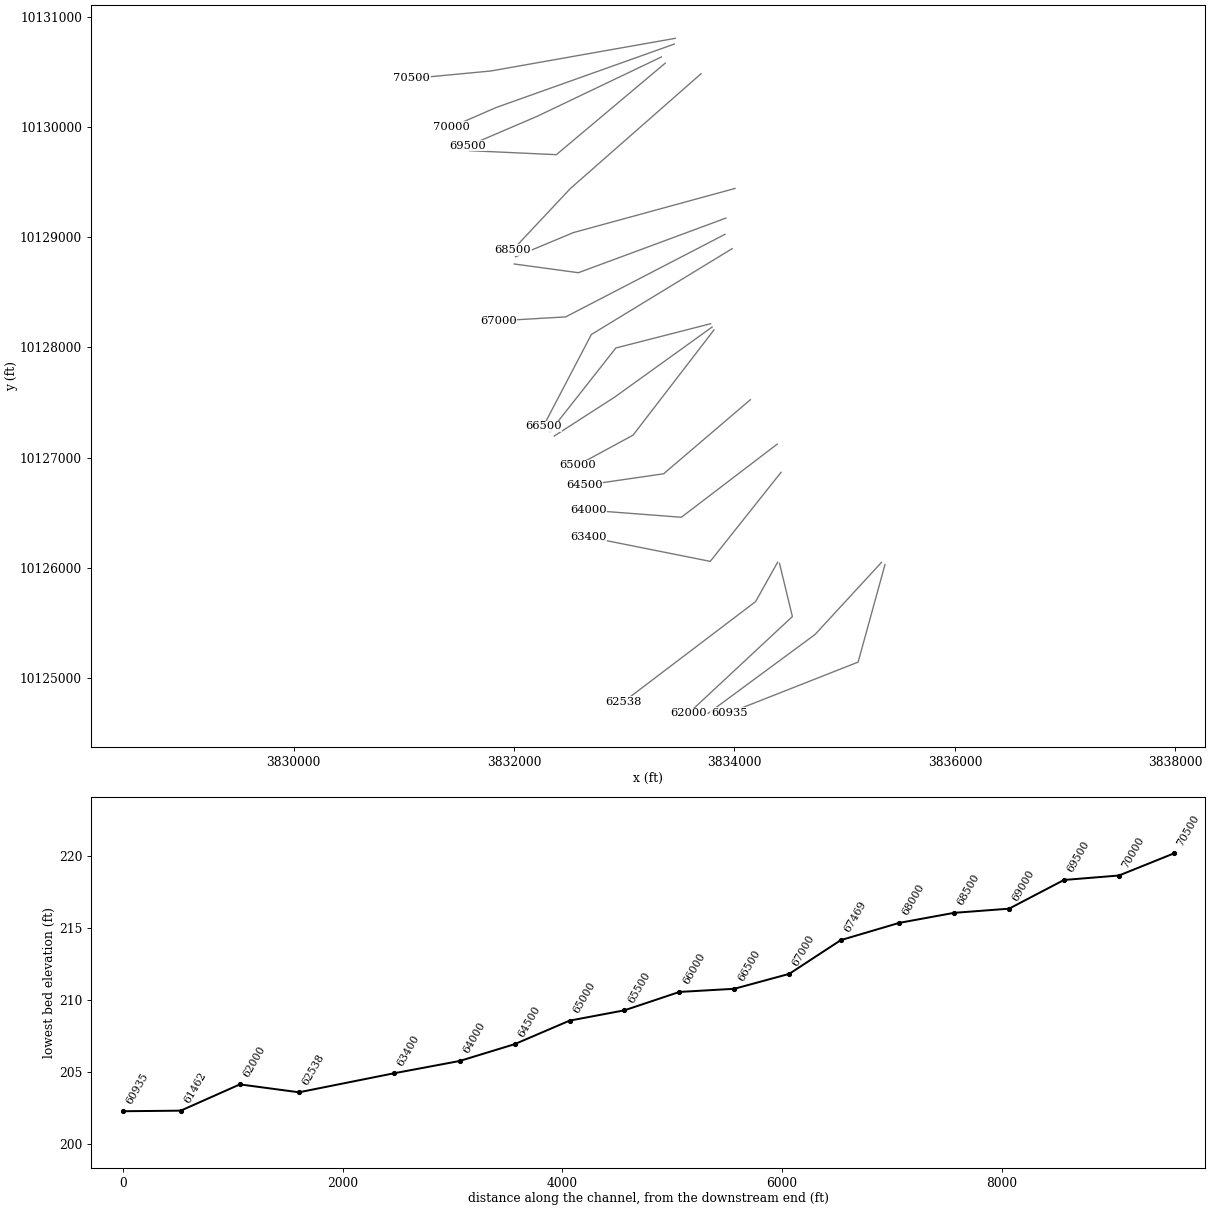
HEC-RAS study STEWARTS CREEK.prj: STEWARTS CREEK Base Level Engineering

--- STEWARTS CREEK.g01 (geometry) --- (continued)

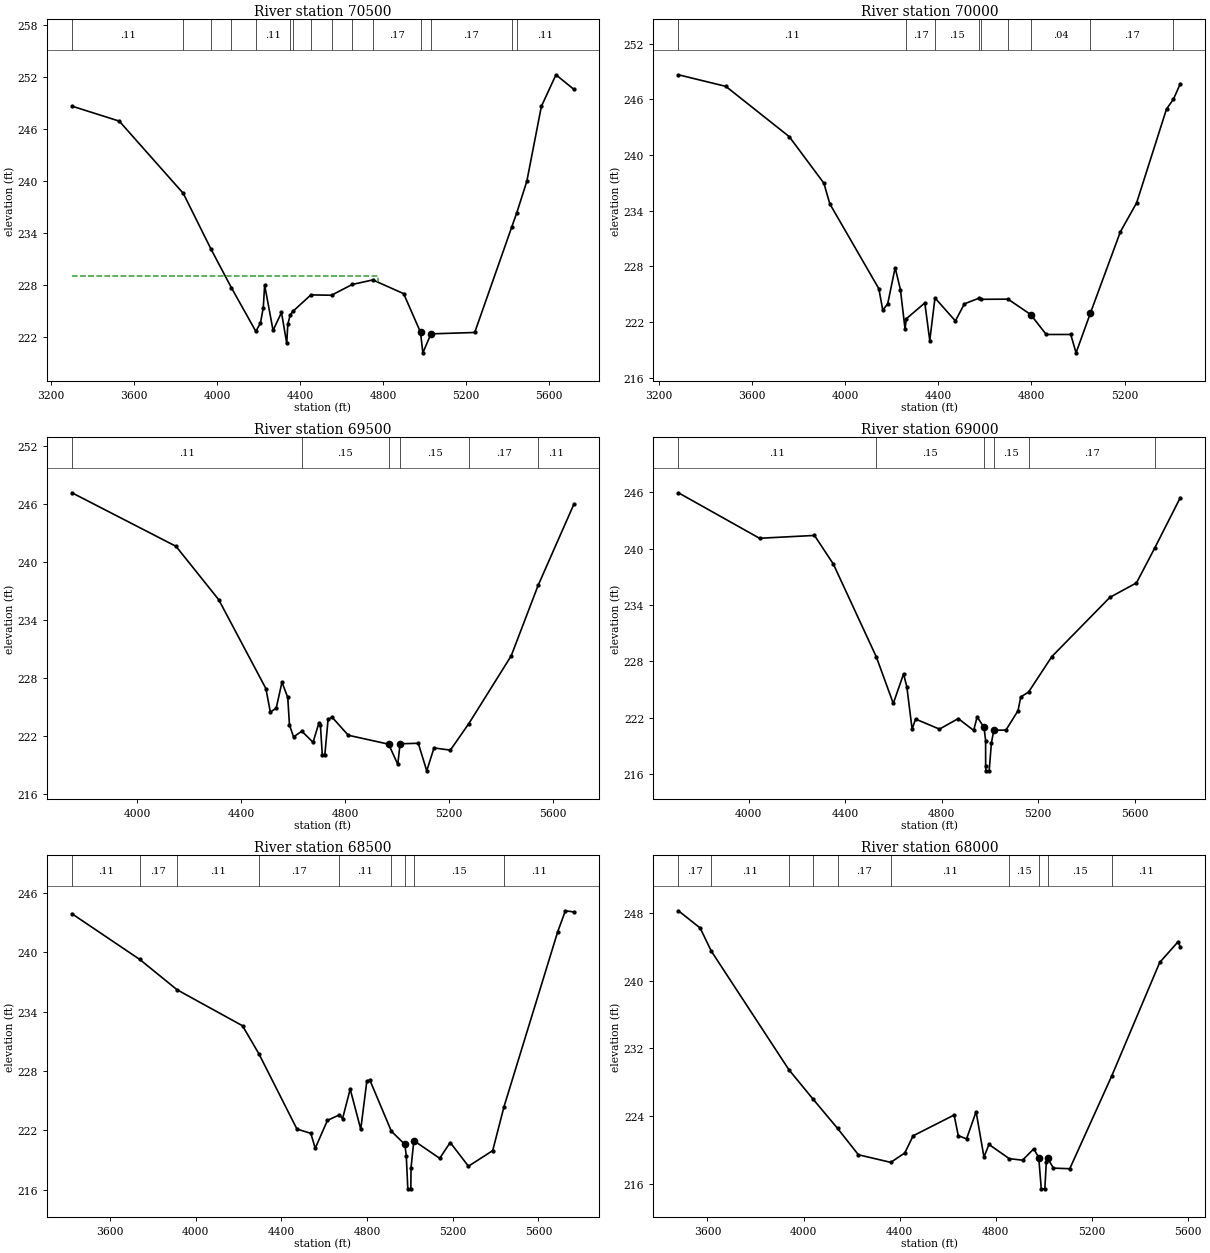
Type RM Length L Ch R = 1 ,70500   ,500,500,500
BEGIN DESCRIPTION:
STEWARTS CREEK 138.0
END DESCRIPTION:
XS GIS Cut Line= 3
       3833462.7     10130806.72      3831788.37      10130510.1
      3831071.98     10130442.21
#Sta/Elev= 30
  3299.6  248.69  3527.7  246.96  3836.4  238.62  3969.5  232.21  4068.1  227.74
  4186.2  222.69  4208.4  223.64  4222.1  225.42  4228.7  228.03  4269.3   222.8
  4309.9  224.87  4335.3   221.3  4340.4  223.51  4352.2  224.61  4366.8  225.04
  4451.7   226.9  4551.2  226.86  4650.8   228.1  4750.3  228.63    4899  227.04
  4980.2  222.59  4991.5  220.21  5030.7   222.4  5241.6  222.56  5419.5  234.69
  5443.6  236.32  5492.7     240    5563  248.66  5633.3  252.31  5719.6  250.63
#Mann= 15 ,-1 , 0
  3299.6     .11       0  3836.4     .17       0  3969.5     .11       0
  4068.1     .17       0  4186.2     .11       0  4352.2     .17       0
  4366.8     .11       0  4451.7     .15       0  4551.2     .11       0
  4650.8     .15       0  4750.3     .17       0  4980.2     .04       0
  5030.7     .17       0  5419.5     .15       0  5443.6     .11       0
#XS Ineff= 2 , 0
       0  4777.1  229.09               0
Permanent Ineff=
       F       F
Bank Sta=4980.2,5030.7
XS Rating Curve= 0 ,0
Exp/Cntr=0.3,0.1

Type RM Length L Ch R = 1 ,70000   ,500,500,500
BEGIN DESCRIPTION:
STEWARTS CREEK 137.0
END DESCRIPTION:
XS GIS Cut Line= 3
      3833454.04     10130754.65      3831838.22      10130178.7
      3831435.79     10130003.78
#Sta/Elev= 30
  3284.6  248.65  3488.2   247.4  3760.3  241.98    3909  236.96  3934.5  234.73
  4144.9  225.58  4161.7  223.27  4182.9  223.96  4214.8  227.85  4237.4  225.49
  4257.3  221.25    4263  222.35  4342.2  224.05  4363.4  219.99  4385.8  224.59
  4473.3  222.11    4512  223.95    4573  224.55  4582.9  224.44  4699.3  224.46
  4796.4   222.8  4863.3  220.65  4968.5  220.65  4991.3  218.67  5053.1  222.97
  5181.3  231.71  5251.2  234.84  5379.7  244.97  5409.4  246.02  5438.8  247.69
#Mann= 9 ,-1 , 0
  3284.6     .11       0    4263     .17       0  4385.8     .15       0
    4573     .11       0  4582.9     .15       0  4699.3     .17       0
  4796.4     .04       0  5053.1     .17       0  5409.4     .11       0
#XS Ineff= 2 , 0
       0  4214.8  227.85               0
Permanent Ineff=
       F       F
Bank Sta=4796.4,5053.1
XS Rating Curve= 0 ,0
Exp/Cntr=0.3,0.1

Type RM Length L Ch R = 1 ,69500   ,500,500,500
BEGIN DESCRIPTION:
STEWARTS CREEK 136.0
END DESCRIPTION:
XS GIS Cut Line= 3
      3833336.79     10130637.44      3832207.95     10130097.79
      3831583.37     10129830.17
#Sta/Elev= 30
  3748.8  247.12  4149.2  241.58  4313.4  236.06  4494.8  226.87    4512  224.43
  4534.6  224.85  4556.7  227.53  4578.9  225.95  4585.5  223.12  4601.1  221.87
  4633.1  222.46  4676.3  221.31  4698.9  223.33  4704.5  223.11  4711.9  219.97
  4721.6  220.03  4734.1  223.68  4749.8   223.9  4811.7  222.04  4966.9  221.12
  5002.2  219.03    5011  221.16  5081.1  221.21  5113.6  218.36  5141.5  220.73
  5204.4   220.5  5275.6  223.25  5438.4  230.25  5542.2  237.55  5679.5  245.93
#Mann= 6 ,-1 , 0
  3748.8     .11       0  4633.1     .15       0  4966.9     .04       0
    5011     .15       0  5275.6     .17       0  5542.2     .11       0
#XS Ineff= 2 , 0
       0  4556.7  227.53               0
Permanent Ineff=
       F       F
Bank Sta=4966.9,5011
XS Rating Curve= 0 ,0
Exp/Cntr=0.3,0.1

Type RM Length L Ch R = 1 ,69000   ,500,500,500
BEGIN DESCRIPTION:
STEWARTS CREEK 135.0
END DESCRIPTION:
XS GIS Cut Line= 3
       3833371.5       10130581.      3832383.98     10129750.38
      3831596.32     10129786.75
#Sta/Elev= 30
  3709.6  245.95  4045.5  241.11  4273.1  241.41  4351.2  238.37  4529.6  228.47
  4599.6  223.53  4642.1  226.67  4655.6  225.32  4677.6   220.8  4691.9  221.87
  4790.8   220.8  4868.8  221.92  4932.6  220.66  4946.9   222.1  4975.5  220.98
    4982  219.58  4982.2  216.86  4982.7  216.36  4996.8  216.36  5006.1  219.37
  5016.2  220.68  5066.2   220.7  5116.3  222.76  5127.4  224.22  5159.8  224.74
  5256.4  228.52  5496.7  234.82  5606.8  236.36  5682.9  240.09  5788.5  245.44
#Mann= 6 ,-1 , 0
  3709.6     .11       0  4529.6     .15       0  4975.5     .04       0
  5016.2     .15       0  5159.8     .17       0  5682.9     .11       0
#XS Ineff= 2 , 0
       0  4642.1  226.67               0
Permanent Ineff=
       F       F
Bank Sta=4975.5,5016.2
XS Rating Curve= 0 ,0
Exp/Cntr=0.3,0.1

Type RM Length L Ch R = 1 ,68500   ,500,500,500
BEGIN DESCRIPTION:
STEWARTS CREEK 134.0
END DESCRIPTION:
XS GIS Cut Line= 3
      3833697.02     10130485.51      3832511.42     10129443.25
      3831987.93     10128884.99
#Sta/Elev= 30
  3421.4  243.92  3738.2  239.29  3912.6  236.22  4217.9  232.58  4294.2  229.75
  4472.2  222.12  4536.7  221.69  4557.6  220.18  4614.5     223  4670.4  223.56
  4685.2  223.18  4720.8  226.17  4770.1   222.1  4798.6  226.99  4812.8  227.07
  4913.1   221.9    4976  220.57  4982.7  219.43  4989.9  216.07    5004  216.07
  5004.9  218.19    5018  220.95  5138.7  219.16    5188  220.76    5273  218.36
  5386.3  219.94  5438.9  224.37  5690.1  242.11  5725.8  244.22  5765.3   244.1
#Mann= 9 ,-1 , 0
  3421.4     .11       0  3738.2     .17       0  3912.6     .11       0
  4294.2     .17       0  4670.4     .11       0  4913.1     .15       0
    4976     .04       0    5018     .15       0  5438.9     .11       0
Bank Sta=4976,5018
XS Rating Curve= 0 ,0
Exp/Cntr=0.3,0.1

Type RM Length L Ch R = 1 ,68000   ,531,531,531
BEGIN DESCRIPTION:
STEWARTS CREEK 133.0
END DESCRIPTION:
XS GIS Cut Line= 3
      3834005.26     10129443.88      3832538.19     10129042.83
      3832013.06     10128823.22
#Sta/Elev= 30
  3479.1  248.26  3569.7  246.22    3616  243.49  3939.4  229.45  4040.7  225.95
  4141.9  222.52  4228.6   219.4  4363.5   218.5  4421.9  219.62  4456.4  221.64
  4627.1   224.1  4644.6  221.66    4679  221.28  4718.8  224.49  4751.5  219.13
  4772.3  220.62  4856.9  218.94  4912.1  218.76  4958.9   220.1  4979.6  219.07
  4990.2  215.37    5005  215.37  5011.2  218.56  5017.1  218.96  5040.9  217.82
  5108.8  217.75  5283.4  228.71  5483.4  242.15  5560.2  244.61  5569.2  243.96
#Mann= 10 ,-1 , 0
  3479.1     .17       0    3616     .11       0  3939.4     .17       0
  4040.7     .11       0  4141.9     .17       0  4363.5     .11       0
  4856.9     .15       0  4979.6     .04       0  5017.1     .15       0
  5283.4     .11       0
Bank Sta=4979.6,5017.1
XS Rating Curve= 0 ,0
Exp/Cntr=0.3,0.1

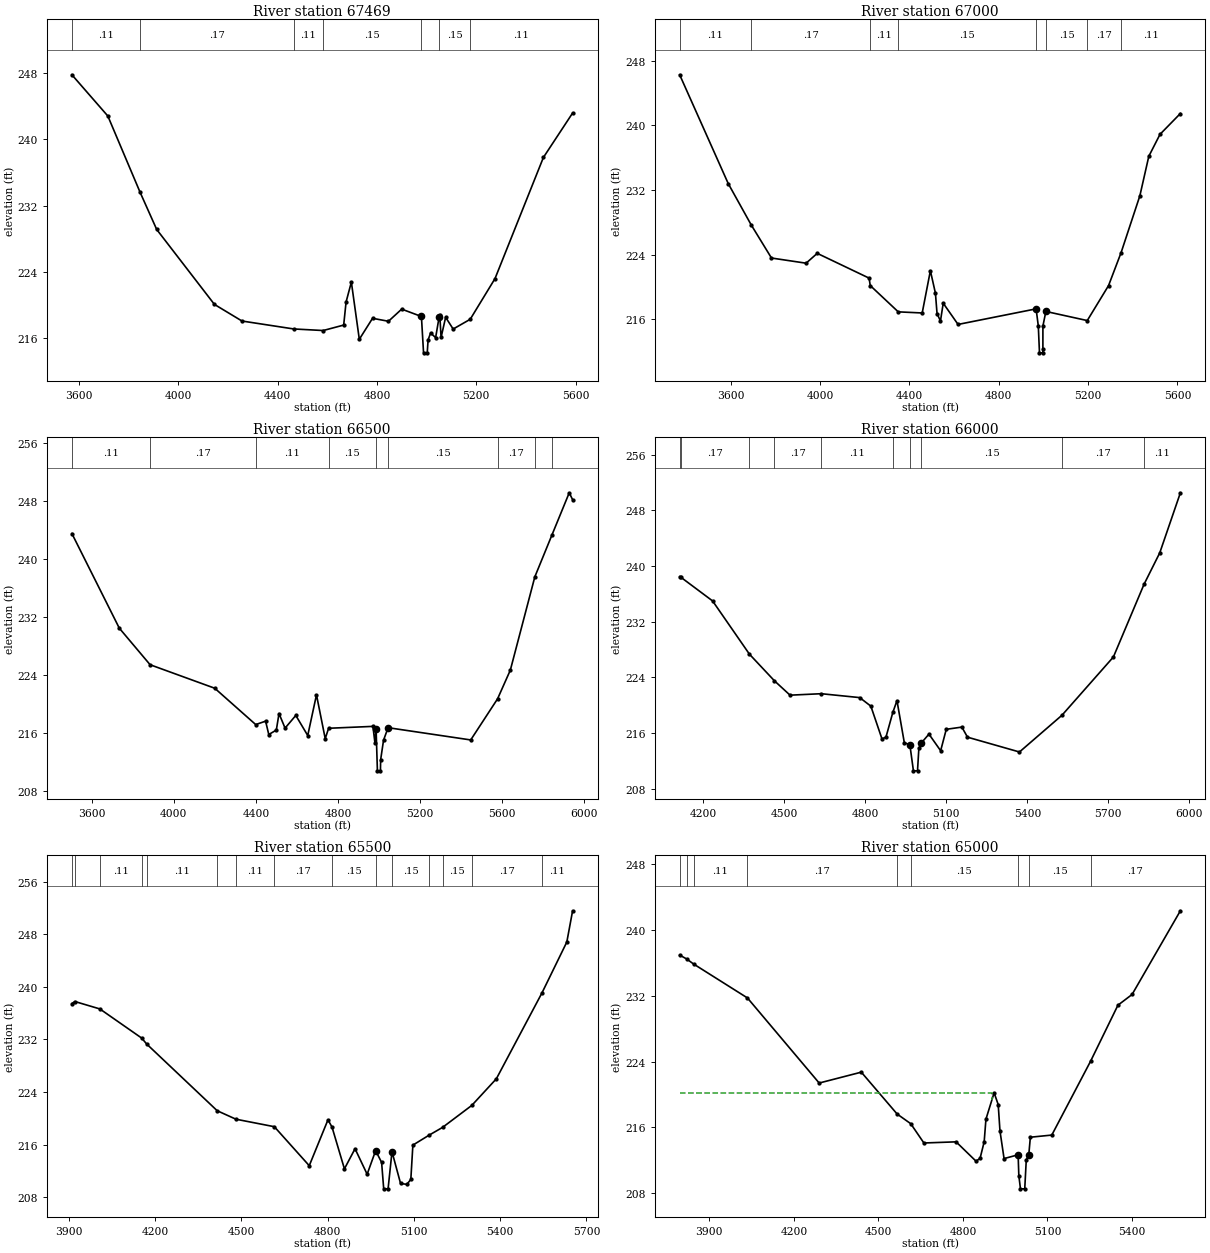
Type RM Length L Ch R = 1 ,67469   ,469,469,469
BEGIN DESCRIPTION:
STEWARTS CREEK 132.0
END DESCRIPTION:
XS GIS Cut Line= 3
      3833922.74     10129174.77       3832583.9     10128678.67
      3832001.46     10128757.91
#Sta/Elev= 30
  3572.2  247.82  3716.9  242.83  3846.3  233.63  3913.6   229.1    4146  220.03
  4256.9  218.02  4465.2  217.06  4583.7  216.87  4666.3  217.53  4675.9  220.32
  4697.2  222.73  4729.2  215.81  4782.5  218.35  4846.5  217.99  4899.8  219.46
  4979.2  218.57  4987.8  214.17  5002.6  214.17  5006.1  215.74  5016.2  216.57
  5036.4  216.01 5050.66218.5363  5053.2  218.76  5058.3  216.03  5076.7  218.47
    5107  217.05  5175.6  218.23  5275.5  223.16  5470.3  237.82  5587.8  243.19
#Mann= 7 ,-1 , 0
  3572.2     .11       0  3846.3     .17       0  4465.2     .11       0
  4583.7     .15       0  4979.2     .04       0 5050.66     .15       0
  5175.6     .11       0
Bank Sta=4979.2,5050.66
XS Rating Curve= 0 ,0
Exp/Cntr=0.3,0.1

Type RM Length L Ch R = 1 ,67000   ,500,500,500
BEGIN DESCRIPTION:
STEWARTS CREEK 131.0
END DESCRIPTION:
XS GIS Cut Line= 3
      3833914.06      10129027.2      3832468.61      10128277.5
      3831856.77     10128241.61
#Sta/Elev= 30
  3371.7  246.28  3589.2  232.79  3691.8  227.68  3782.7  223.57  3937.6  222.93
  3987.5  224.15  4219.6  221.08  4224.7  220.16  4350.1   216.9  4457.3  216.76
  4493.9     222  4516.5  219.21  4523.7  216.69    4539  215.76  4551.4  217.97
  4617.8  215.34  4967.1  217.27    4977  215.15  4982.2  211.82    4997  211.82
  4997.5  212.32  4997.6  215.14  5010.8  216.95  5196.1  215.82  5291.3  220.15
  5347.4  224.23  5431.5  231.28  5471.6  236.18  5521.7   238.9  5612.9  241.48
#Mann= 8 ,-1 , 0
  3371.7     .11       0  3691.8     .17       0  4224.7     .11       0
  4350.1     .15       0  4967.1     .04       0  5010.8     .15       0
  5196.1     .17       0  5347.4     .11       0
Bank Sta=4967.1,5010.8
XS Rating Curve= 0 ,0
Exp/Cntr=0.3,0.1

Type RM Length L Ch R = 1 ,66500   ,500,500,500
BEGIN DESCRIPTION:
STEWARTS CREEK 130.0
END DESCRIPTION:
XS GIS Cut Line= 3
      3833979.14     10128896.98       3832701.8     10128117.85
      3832264.78     10127282.46
#Sta/Elev= 30
  3503.8   243.5  3734.8  230.45  3884.8  225.41  4199.6  222.17  4399.2  217.16
  4447.4  217.63  4462.8  215.79  4499.6   216.4  4512.7  218.68  4542.2  216.67
  4594.5  218.42  4652.6  215.65  4695.2  221.26  4737.8  215.22  4754.3  216.65
  4970.2  216.91  4979.8  214.67  4985.6  216.53    4992  210.78  5006.8  210.78
  5007.7   212.3  5021.9  215.01    5044  216.73  5446.5  215.04  5577.3  220.71
  5639.5  224.67  5758.8  237.53  5841.3  243.24  5926.4  249.12  5942.8  248.17
#Mann= 9 ,-1 , 0
  3503.8     .11       0  3884.8     .17       0  4399.2     .11       0
  4754.3     .15       0  4985.6     .04       0    5044     .15       0
  5577.3     .17       0  5758.8     .11       0  5841.3     .17       0
Bank Sta=4985.6,5044
XS Rating Curve= 0 ,0
Exp/Cntr=0.3,0.1

Type RM Length L Ch R = 1 ,66000   ,500,500,500
BEGIN DESCRIPTION:
STEWARTS CREEK 129.0
END DESCRIPTION:
XS GIS Cut Line= 3
      3833783.83     10128215.57      3832923.92      10127995.2
       3832326.1      10127235.4
#Sta/Elev= 30
  4112.3  238.48  4116.9  238.39  4234.2  234.99  4370.8  227.33  4463.4   223.5
  4521.1  221.44  4636.7  221.65  4779.2  221.09  4820.4  219.86  4861.7  215.14
  4876.4  215.41    4902  218.99  4917.2  220.65  4944.3  214.62    4965  214.28
  4978.1  210.56  4993.2  210.56  4998.2  213.79  5006.7  214.54  5035.6  215.84
  5078.9  213.45  5099.7  216.53  5157.5  216.85  5178.3   215.4  5370.8  213.27
  5528.4  218.56  5718.7  226.93  5832.4   237.4  5890.4   241.9  5966.8  250.54
#Mann= 10 ,-1 , 0
  4112.3     .11       0  4116.9     .17       0  4370.8     .11       0
  4463.4     .17       0  4636.7     .11       0    4902     .15       0
    4965     .04       0  5006.7     .15       0  5528.4     .17       0
  5832.4     .11       0
Bank Sta=4965,5006.7
XS Rating Curve= 0 ,0
Exp/Cntr=0.3,0.1

Type RM Length L Ch R = 1 ,65500   ,500,500,500
BEGIN DESCRIPTION:
STEWARTS CREEK 128.0
END DESCRIPTION:
XS GIS Cut Line= 3
       3833796.9     10128185.21      3832912.89     10127548.91
      3832364.98     10127195.86
#Sta/Elev= 30
  3910.8  237.45  3921.1  237.77  4008.1  236.64  4153.4  232.21  4171.2  231.29
    4416  221.16  4481.2  219.87  4614.7  218.73  4736.1   212.8  4801.2  219.78
  4815.3  218.67  4858.4  212.32  4895.3  215.38  4937.4   211.5  4966.9  215.09
  4987.7   213.3    4995  209.28  5010.2  209.28  5023.8  214.93  5053.6   210.1
  5075.3  209.96  5089.3  210.71  5096.4  215.93  5152.3  217.43  5199.8  218.63
  5301.3  221.97  5386.7  226.02  5545.3  239.08  5631.7  246.82  5651.8  251.57
#Mann= 15 ,-1 , 0
  3910.8     .11       0  3921.1     .17       0  4008.1     .11       0
  4153.4     .17       0  4171.2     .11       0    4416     .17       0
  4481.2     .11       0  4614.7     .17       0  4815.3     .15       0
  4966.9     .04       0  5023.8     .15       0  5152.3     .17       0
  5199.8     .15       0  5301.3     .17       0  5545.3     .11       0
Bank Sta=4966.9,5023.8
XS Rating Curve= 0 ,0
Exp/Cntr=0.3,0.1

Type RM Length L Ch R = 1 ,65000   ,500,500,500
BEGIN DESCRIPTION:
STEWARTS CREEK 127.0
END DESCRIPTION:
XS GIS Cut Line= 3
      3833814.21     10128159.11      3833079.69     10127203.61
      3832577.25     10126930.85
#Sta/Elev= 30
  3794.8  236.91  3819.9  236.43    3844  235.83  4035.3  231.71  4289.9  221.39
  4439.4  222.71  4566.6  217.63  4614.8  216.46  4661.5  214.12  4775.7  214.26
  4846.3  211.92  4860.8  212.25  4875.4  214.26  4881.7  217.01  4910.7  220.21
  4925.2  218.78  4931.5  215.58    4946  212.23  4995.9  212.69  4998.4  210.17
  5004.2  208.56  5019.4  208.56  5024.8  212.07  5033.6  212.64  5039.3  214.82
  5115.4  215.08  5253.1  224.04  5350.1  230.83  5400.3  232.13  5571.7  242.28
#Mann= 9 ,-1 , 0
  3794.8     .11       0  3819.9     .17       0    3844     .11       0
  4035.3     .17       0  4566.6     .11       0  4614.8     .15       0
  4995.9     .04       0  5033.6     .15       0  5253.1     .17       0
#XS Ineff= 2 , 0
       0  4902.5  220.18               0
Permanent Ineff=
       F       F
Bank Sta=4995.9,5033.6
XS Rating Curve= 0 ,0
Exp/Cntr=0.3,0.1

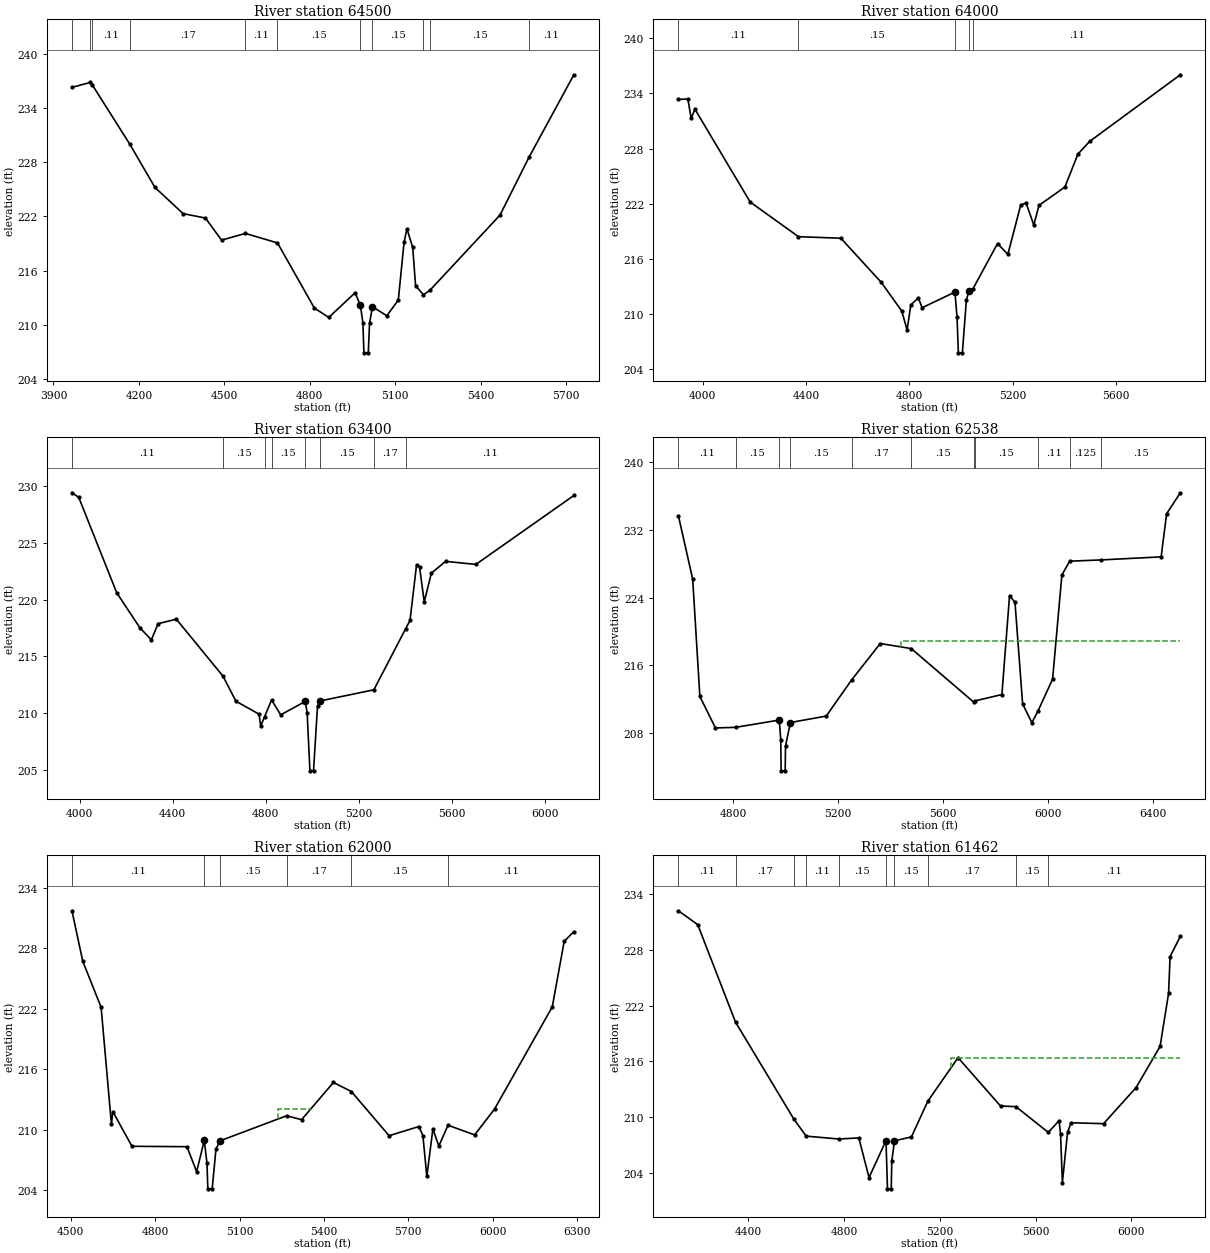
Type RM Length L Ch R = 1 ,64500   ,500,500,500
BEGIN DESCRIPTION:
STEWARTS CREEK 126.0
END DESCRIPTION:
XS GIS Cut Line= 3
      3834144.09     10127525.46      3833357.43     10126853.02
      3832638.07     10126748.56
#Sta/Elev= 30
  3965.1  236.27  4029.5  236.81  4035.7  236.58  4168.1  229.99  4256.4  225.21
  4355.2  222.31  4433.8  221.82  4490.2  219.38  4574.1  220.12  4686.6  219.07
  4816.2  211.86  4866.7  210.84    4959  213.56  4977.5212.1695  4986.4  210.24
    4990  206.92  5005.3  206.92  5009.7  210.18  5019.8  212.02  5070.3  211.02
  5110.7  212.75  5130.9  219.15    5141  220.63  5161.2  218.58  5171.4  214.33
  5199.1  213.34  5221.5  213.83  5467.7  222.15  5569.8  228.56  5726.9  237.66
#Mann= 11 ,-1 , 0
  3965.1     .11       0  4029.5     .15       0  4035.7     .11       0
  4168.1     .17       0  4574.1     .11       0  4686.6     .15       0
  4977.5     .04       0  5019.8     .15       0  5199.1     .11       0
  5221.5     .15       0  5569.8     .11       0
#XS Ineff= 2 , 0
       0                    5141       0  220.63
Permanent Ineff=
       F       F
Bank Sta=4977.5,5019.8
XS Rating Curve= 0 ,0
Exp/Cntr=0.3,0.1

Type RM Length L Ch R = 1 ,64000   ,600,600,600
BEGIN DESCRIPTION:
STEWARTS CREEK 125.0
END DESCRIPTION:
XS GIS Cut Line= 3
      3834387.18     10127121.84      3833518.15     10126458.13
      3832672.82     10126522.86
#Sta/Elev= 30
  3906.5  233.34    3943   233.4    3956  231.27  3970.2  232.29  4184.2  222.17
  4370.9   218.4  4534.8  218.23  4691.2  213.42  4770.2  210.31    4791  208.25
  4805.5  210.97  4834.6  211.73  4849.1  210.66    4976  212.37  4984.2  209.61
  4989.3  205.75  5004.7  205.75  5020.4  211.52  5030.4   212.5  5045.3   212.7
  5140.7  217.65  5180.8  216.48  5230.5  221.85    5251  222.07  5281.1  219.68
  5301.2  221.81  5401.5  223.81  5451.6  227.39  5496.8  228.77  5847.8  236.03
#Mann= 5 ,-1 , 0
  3906.5     .11       0  4370.9     .15       0    4976     .04       0
  5030.4     .15       0  5045.3     .11       0
#XS Ineff= 2 , 0
       0                  5140.7       0  217.65
Permanent Ineff=
       F       F
Bank Sta=4976,5030.4
XS Rating Curve= 0 ,0
Exp/Cntr=0.3,0.1

Type RM Length L Ch R = 1 ,63400   ,862,862,862
BEGIN DESCRIPTION:
STEWARTS CREEK 124.0
END DESCRIPTION:
XS GIS Cut Line= 3
      3834422.72     10126866.57      3833780.33     10126057.73
      3832677.12     10126278.07
#Sta/Elev= 30
  3967.1  229.42  3996.2  229.02  4159.6   220.6  4258.9  217.52  4308.5  216.44
  4337.4  217.87  4415.9  218.27  4616.6  213.24  4672.2  211.03  4771.6  209.89
  4778.6  208.84  4795.6  209.68  4825.4  211.14  4864.5  209.83  4970.2  211.01
  4978.2  210.03  4990.3  204.89  5005.7  204.89  5022.9   210.6  5033.1  211.05
  5265.2  212.04  5401.4  217.41  5420.6  218.16  5448.6  223.04  5461.4  222.88
  5481.8   219.8  5512.4  222.33  5573.6  223.37  5703.7   223.1    6125  229.18
#Mann= 8 ,-1 , 0
  3967.1     .11       0  4616.6     .15       0  4795.6     .11       0
  4825.4     .15       0  4970.2     .04       0  5033.1     .15       0
  5265.2     .17       0  5401.4     .11       0
Bank Sta=4970.2,5033.1
XS Rating Curve= 0 ,0
Exp/Cntr=0.3,0.1

Type RM Length L Ch R = 1 ,62538   ,538,538,538
BEGIN DESCRIPTION:
STEWARTS CREEK 123.0
END DESCRIPTION:
XS GIS Cut Line= 3
      3834391.48     10126049.74      3834191.87     10125692.41
      3832993.92      10124782.4
#Sta/Elev= 30
  4590.7  233.65  4645.1  226.19  4672.5  212.34  4731.9  208.63  4808.5   208.7
  4975.2  209.56  4980.9  207.22  4982.3  203.57  4997.8  203.57    4999  206.48
  5017.6  209.27  5154.4  210.03  5250.8  214.28  5360.3  218.59  5478.6  217.99
  5717.2  211.66  5720.3  211.81  5824.1  212.57  5853.2  224.22    5874  223.45
  5903.1  211.47  5938.4  209.25    5962  210.65  6017.4  214.39  6052.8  226.67
  6082.5   228.3  6202.9  228.45  6431.3  228.81  6452.1  233.89  6504.4  236.37
#Mann= 11 ,-1 , 0
  4590.7     .11       0  4808.5     .15       0  4975.2     .04       0
  5017.6     .15       0  5250.8     .17       0  5478.6     .15       0
  5717.2     .17       0  5720.3     .15       0    5962     .11       0
  6082.5    .125       0  6202.9     .15       0
#XS Ineff= 2 , 0
       0                  5439.3       0  218.94
Permanent Ineff=
       F       F
Bank Sta=4975.2,5017.6
XS Rating Curve= 0 ,0
Exp/Cntr=0.3,0.1

Type RM Length L Ch R = 1 ,62000   ,538,538,538
BEGIN DESCRIPTION:
STEWARTS CREEK 122.0
END DESCRIPTION:
XS GIS Cut Line= 3
      3834408.85     10126038.51       3834525.5     10125556.52
      3833582.66     10124677.55
#Sta/Elev= 30
  4504.1   231.7  4542.6  226.69  4607.8  222.13  4644.5  210.52  4649.6  211.77
  4717.5  208.34    4913   208.3  4947.6  205.82  4974.7  208.93  4984.3  206.66
  4987.3  204.12  5002.8  204.12  5016.3  208.06  5030.5  208.88  5267.7  211.37
  5320.7  210.98    5434  214.67  5497.9  213.77  5631.9  209.39  5737.9   210.3
  5752.1   209.4  5766.2  205.35  5787.7  210.07  5808.7  208.36  5841.5  210.43
  5936.2  209.47  6007.1  212.04  6212.3  222.17  6254.6  228.66    6289  229.64
#Mann= 6 ,-1 , 0
  4504.1     .11       0  4974.7     .04       0  5030.5     .15       0
  5267.7     .17       0  5497.9     .15       0  5841.5     .11       0
#XS Ineff= 2 ,-1
  5235.7  5355.8  212.03    5434  6070.6  214.67
Permanent Ineff=
       F       F
Bank Sta=4974.7,5030.5
XS Rating Curve= 0 ,0
Exp/Cntr=0.3,0.1

Type RM Length L Ch R = 1 ,61462   ,527,527,527
BEGIN DESCRIPTION:
STEWARTS CREEK 121.0
END DESCRIPTION:
XS GIS Cut Line= 3
      3835334.19     10126048.89      3834730.81     10125393.56
      3833761.67      10124678.3
#Sta/Elev= 30
  4109.2   232.2  4189.8  230.71  4347.6  220.22    4591   209.8  4642.4  207.96
  4778.7  207.65  4862.4  207.77  4904.9   203.5  4975.8  207.48    4982  202.29
  4997.6  202.29    5000  205.27  5011.2  207.45  5082.2  207.88    5150   211.7
  5276.5   216.4  5453.9   211.2  5518.1  211.13  5653.4  208.36  5698.3  209.63
  5704.5  208.19  5712.1  202.96  5733.7  208.36  5748.4   209.4  5884.1   209.3
  6019.8  213.18    6120  217.61  6155.5  223.32  6161.7  227.26  6204.5  229.45
#Mann= 10 ,-1 , 0
  4109.2     .11       0  4347.6     .17       0    4591     .15       0
  4642.4     .11       0  4778.7     .15       0  4975.8     .04       0
  5011.2     .15       0    5150     .17       0  5518.1     .15       0
  5653.4     .11       0
#XS Ineff= 2 , 0
       0                  5247.2       0  216.33
Permanent Ineff=
       F       F
Bank Sta=4975.8,5011.2
XS Rating Curve= 0 ,0
Exp/Cntr=0.3,0.1

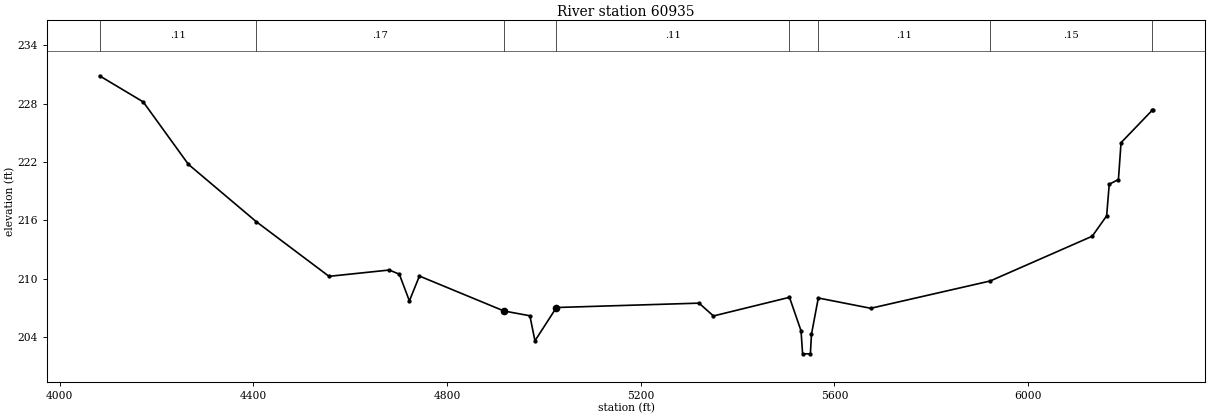
Type RM Length L Ch R = 1 ,60935   ,672,672,672
BEGIN DESCRIPTION:
STEWARTS CREEK 120.0
END DESCRIPTION:
XS GIS Cut Line= 3
      3835365.47     10126028.12      3835121.89     10125143.13
       3833952.1       10124682.
#Sta/Elev= 30
  4082.1  230.88  4172.4  228.19  4265.7  221.76  4405.8  215.86  4556.1  210.23
  4680.6  210.88  4701.3  210.45  4722.1   207.7  4742.8  210.26  4917.5  206.66
    4971  206.17  4981.4  203.59  5025.8  207.02  5320.3  207.47  5350.1  206.15
  5507.1  208.07    5531  204.62  5534.2  202.25  5550.3  202.25  5552.5  204.25
  5566.6     208  5674.9  206.94  5921.6  209.75  6132.4  214.36  6162.2  216.46
  6167.5  219.71  6186.5   220.2  6191.9  223.99  6256.7  227.35  6257.4  227.37
#Mann= 8 ,-1 , 0
  4082.1     .11       0  4405.8     .17       0  4917.5     .04       0
  5025.8     .11       0  5507.1     .12       0  5566.6     .11       0
  5921.6     .15       0  6256.7     .11       0
#XS Ineff= 2 , 0
       0  4680.6  210.88               0
Permanent Ineff=
       F       F
Bank Sta=4917.5,5025.8
XS Rating Curve= 0 ,0
Exp/Cntr=0.3,0.1