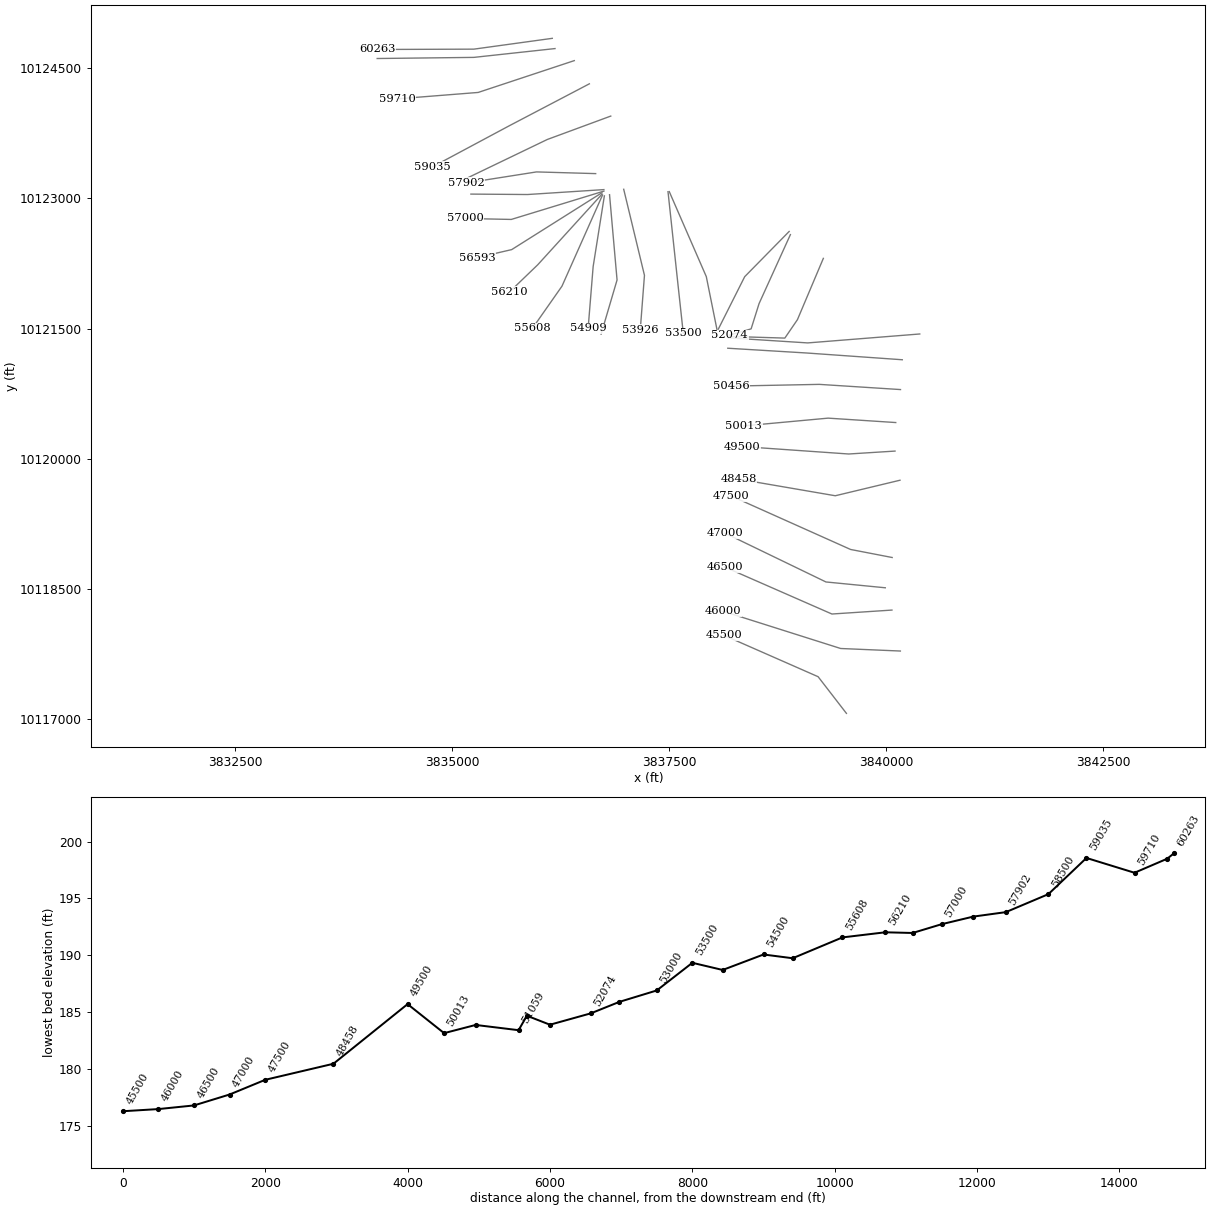
HEC-RAS study STEWARTS CREEK.prj: STEWARTS CREEK Base Level Engineering

--- STEWARTS CREEK.g01 (geometry) --- (continued)

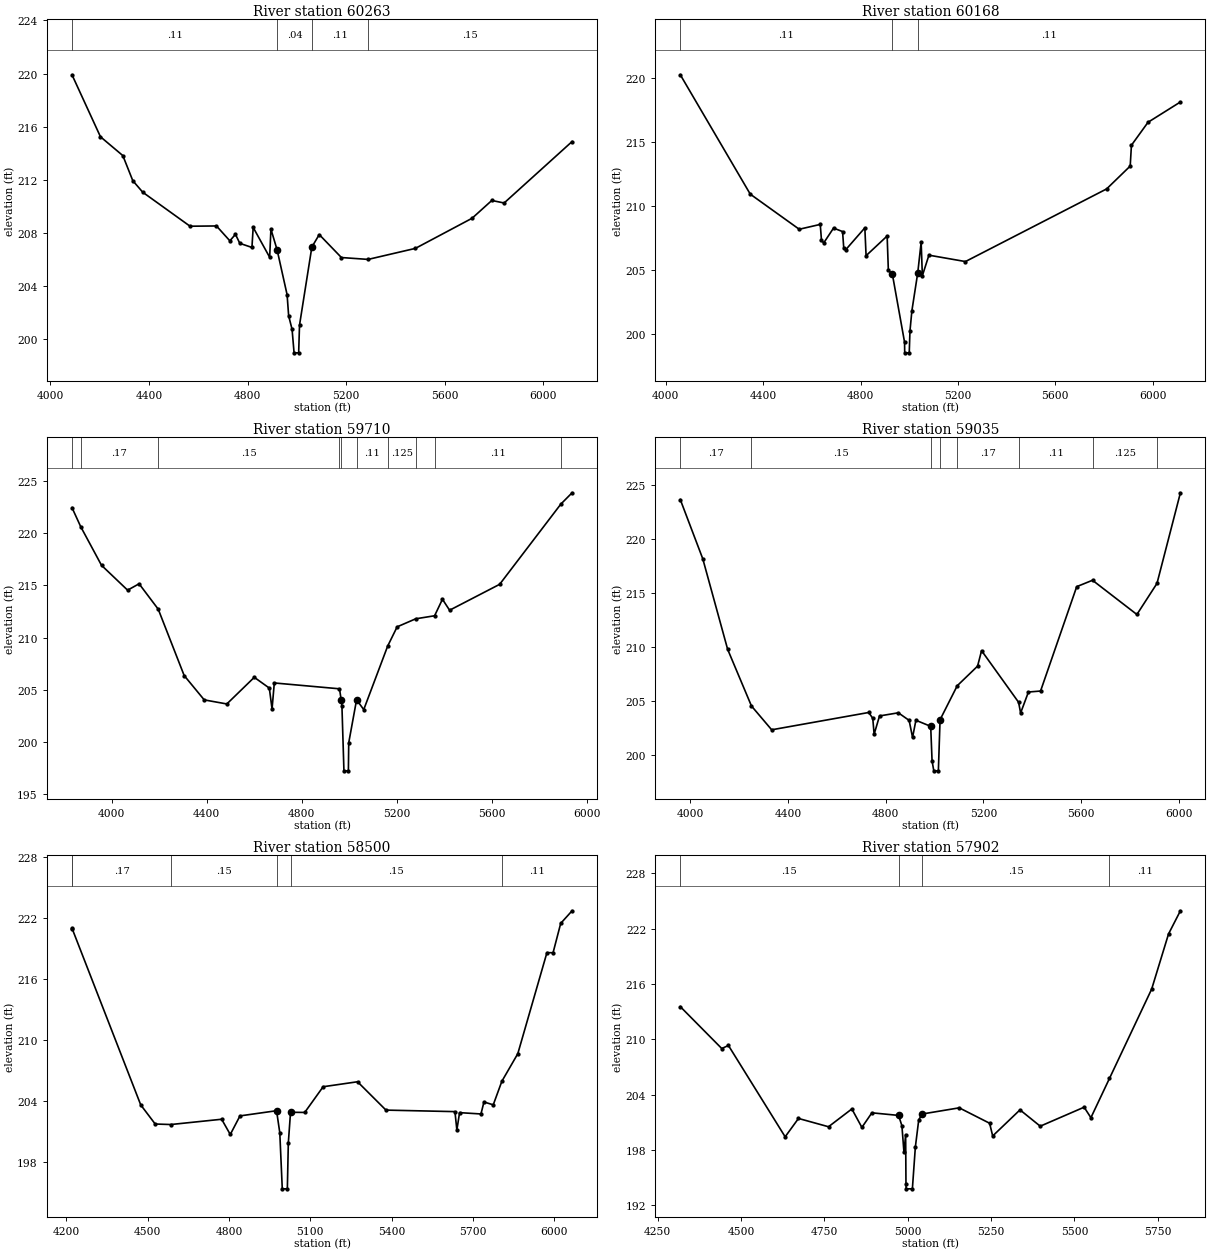
Type RM Length L Ch R = 1 ,60263   ,95,95,95
BEGIN DESCRIPTION:
STEWARTS CREEK 118.0
END DESCRIPTION:
XS GIS Cut Line= 3
      3836152.25     10124846.32      3835248.31     10124721.65
      3834132.11     10124717.86
#Sta/Elev= 30
  4087.5  219.91    4203  215.24  4293.8  213.82  4334.2  211.93  4374.6  211.06
  4566.4   208.5  4673.6  208.52  4727.9   207.4  4750.6  207.89  4768.3  207.21
  4817.5   206.9  4822.5  208.41  4889.4  206.16  4894.5  208.28  4919.7  206.71
  4960.1  203.34  4966.4  201.75  4980.3  200.73  4988.4  198.96    5007  198.96
  5010.5  201.05  5060.5  206.93  5090.5  207.87  5180.5  206.14  5288.8     206
  5480.5  206.83  5710.5   209.1  5790.5  210.44  5840.5  210.25  6116.2  214.88
#Mann= 4 ,-1 , 0
  4087.5     .11       0  4919.7     .04       0  5060.5     .11       0
  5288.8     .15       0
Bank Sta=4919.7,5060.5
XS Rating Curve= 0 ,0
Exp/Cntr=0.3,0.1

Type RM Length L Ch R = 1 ,60168   ,458,458,458
BEGIN DESCRIPTION:
STEWARTS CREEK 117.0
END DESCRIPTION:
XS GIS Cut Line= 3
      3836183.53     10124728.27      3835248.53     10124626.68
      3834134.91     10124613.69
#Sta/Elev= 30
  4059.5  220.27  4346.9  210.92    4548  208.17  4634.4  208.55  4639.4   207.3
  4648.6   207.1  4688.9  208.26    4726  207.99    4731  206.67  4739.2  206.57
  4817.5  208.28  4822.6   206.1  4909.1  207.64  4914.1  204.94  4930.3  204.68
  4980.6  199.33  4981.3  198.49  4999.9  198.49  5002.8  200.19  5010.7  201.78
 5034.88 204.768  5048.8  207.15  5053.8  204.53  5080.7  206.14  5230.7  205.64
  5810.7  211.33  5907.5  213.12  5912.5  214.75  5980.7  216.55  6113.7  218.14
#Mann= 3 , 0 , 0
  4059.5     .11       0  4930.3     .04       0 5034.88     .11       0
Bank Sta=4930.3,5034.88
XS Rating Curve= 0 ,0
Exp/Cntr=0.3,0.1

Type RM Length L Ch R = 1 ,59710   ,675,675,675
BEGIN DESCRIPTION:
Mapping XS 3ce9fcac
END DESCRIPTION:
XS GIS Cut Line= 3
       3836405.8     10124589.39      3835298.39     10124222.52
      3834364.12     10124148.41
#Sta/Elev= 30
  3833.4  222.45    3870  220.63  3957.6  216.93  4067.4  214.55  4115.7  215.16
  4196.2  212.73  4305.3  206.38  4389.7  204.05  4484.8  203.66  4600.3  206.21
  4663.5  205.18    4675  203.18  4684.5  205.67  4958.7  205.11    4966 204.029
    4969  203.46  4977.4  197.26  4996.1  197.26  4997.6  199.95  5030.6  204.06
  5060.7  203.12  5161.4   209.2  5201.2  211.04  5279.4  211.81  5358.8   212.1
  5391.8  213.68  5421.9  212.63  5632.5  215.11    5890  222.79  5937.2  223.87
#Mann= 10 ,-1 , 0
  3833.4     .11       0    3870     .17       0  4196.2     .15       0
  4958.7     .11       0    4966     .04       0  5030.6     .11       0
  5161.4    .125       0  5279.4     .15       0  5358.8     .11       0
    5890     .15       0
Bank Sta=4966,5030.6
XS Rating Curve= 0 ,0
Exp/Cntr=0.3,0.1

Type RM Length L Ch R = 1 ,59035   ,535,535,535
BEGIN DESCRIPTION:
STEWARTS CREEK 116.0
END DESCRIPTION:
XS GIS Cut Line= 3
      3836579.36     10124322.01      3835658.17      10123839.1
      3834771.58     10123364.35
#Sta/Elev= 30
  3959.9  223.61  4051.9  218.14  4153.6  209.78    4251  204.55  4333.7  202.35
  4730.8  203.95  4747.2  203.41  4752.8  201.94  4774.9  203.63  4851.8  203.92
    4896  203.22    4910  201.64  4923.7  203.23  4984.2  202.67  4989.8  199.48
  4996.9  198.56  5015.6  198.56  5022.5  203.28  5092.8  206.42    5176  208.23
  5192.3  209.66  5343.8  204.89    5352   203.9    5384  205.84  5433.6  205.93
  5581.5  215.57  5646.1  216.16  5827.7     213  5909.9  215.87  6005.7  224.24
#Mann= 8 ,-1 , 0
  3959.9     .17       0    4251     .15       0  4984.2     .04       0
  5022.5     .15       0  5092.8     .17       0  5343.8     .11       0
  5646.1    .125       0  5909.9     .11       0
Bank Sta=4984.2,5022.5
XS Rating Curve= 0 ,0
Exp/Cntr=0.3,0.1

Type RM Length L Ch R = 1 ,58500   ,598,598,598
BEGIN DESCRIPTION:
STEWARTS CREEK 115.0
END DESCRIPTION:
XS GIS Cut Line= 3
      3836825.73     10123949.98        3836095.     10123680.31
      3835134.97     10123217.87
#Sta/Elev= 30
  4221.1  221.05  4222.2  220.96  4474.7  203.64    4528  201.76  4585.6  201.71
  4773.1  202.23  4804.9  200.73  4840.7  202.56  4975.6  203.07  4987.5  200.91
  4996.7  195.38  5015.4  195.38    5019   199.9 5027.15202.9162  5079.5   202.9
  5147.4  205.43  5274.3  205.92  5379.1  203.13  5633.5  202.98  5640.6  201.18
  5650.6  202.88  5729.5  202.75  5740.5  203.93  5774.8  203.65  5806.6  205.97
  5865.3  208.68  5972.8  218.63  5995.4  218.62  6023.6  221.51  6065.6  222.75
#Mann= 6 ,-1 , 0
  4221.1     .11       0  4222.2     .17       0  4585.6     .15       0
  4975.6     .04       0 5027.15     .15       0  5806.6     .11       0
Bank Sta=4975.6,5027.15
XS Rating Curve= 0 ,0
Exp/Cntr=0.3,0.1

Type RM Length L Ch R = 1 ,57902   ,456,456,456
BEGIN DESCRIPTION:
STEWARTS CREEK 114.0
END DESCRIPTION:
XS GIS Cut Line= 3
      3836652.08     10123286.78      3835970.66     10123306.35
      3835162.71     10123179.17
#Sta/Elev= 30
  4318.3  213.55  4442.6  209.01  4462.6  209.34  4632.7  199.44  4672.7  201.43
  4762.7  200.53  4832.7  202.46  4862.8  200.46  4892.8  202.04  4972.8  201.76
  4982.8  200.64    4989  197.74    4994  199.68    4995   194.3  4995.5   193.8
  5014.2   193.8  5023.1  198.32  5033.2  201.26  5043.3  201.91  5154.7  202.58
  5245.8  200.91    5255  199.53  5336.9  202.36  5397.6  200.59  5529.2  202.65
  5549.5  201.51  5605.2  205.77  5731.7  215.45  5782.3  221.43  5817.9  223.94
#Mann= 4 ,-1 , 0
  4318.3     .15       0  4972.8     .04       0  5043.3     .15       0
  5605.2     .11       0
Bank Sta=4972.8,5043.3
XS Rating Curve= 0 ,0
Exp/Cntr=0.3,0.1

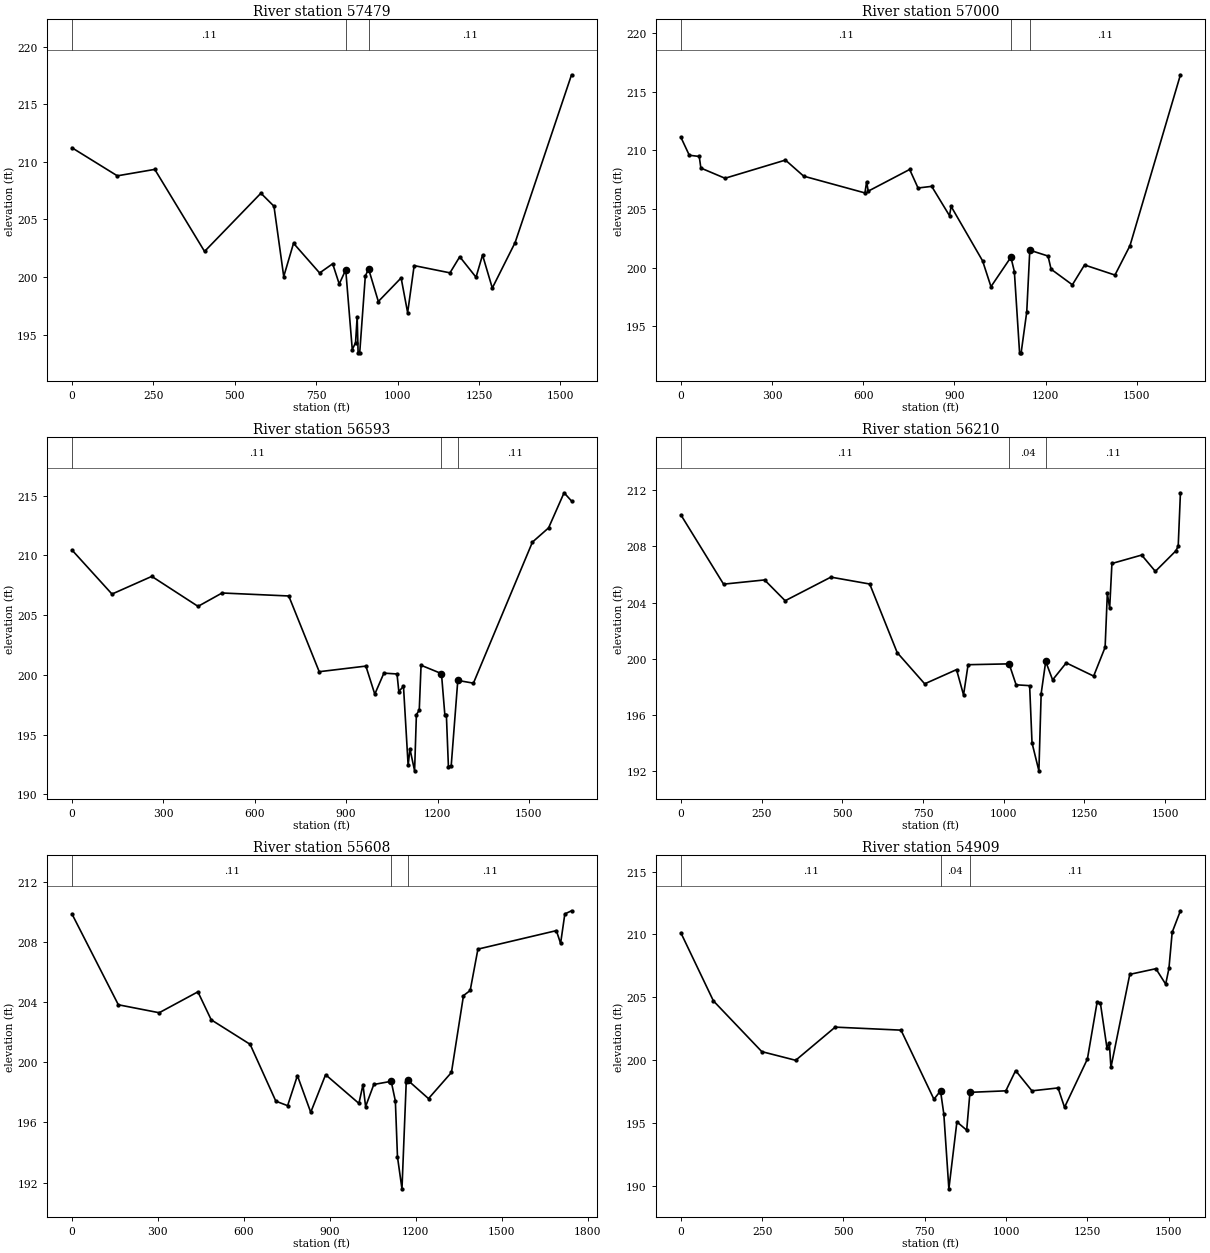
Type RM Length L Ch R = 1 ,57479   ,446,446,446
XS GIS Cut Line= 3
      3836746.82     10123102.42      3835867.17     10123045.71
      3835214.59     10123050.66
#Sta/Elev= 30
       0  211.23   139.3  208.79   254.3  209.35   407.2  202.22   580.2  207.28
   620.3  206.15   650.3  200.04   680.4  202.93   760.5  200.35   800.6  201.15
   820.7  199.39   840.7  200.62   860.8  193.69   870.8  194.29   875.8  196.54
   878.7  193.41   883.6  193.41   900.8  200.07   910.8  200.71   940.8  197.87
  1010.8  199.92  1030.8   196.9  1050.8  200.99  1160.8  200.36  1190.8  201.76
  1240.8  199.98  1260.8  201.91  1290.8  199.04  1360.8  202.99  1534.1  217.57
#Mann= 3 , 0 , 0
       0     .11       0   840.7     .04       0   910.8     .11       0
Bank Sta=840.7,910.8
XS Rating Curve= 0 ,0
Exp/Cntr=0.3,0.1

Type RM Length L Ch R = 1 ,57000   ,407,407,407
XS GIS Cut Line= 3
      3836746.82     10123084.98      3835679.85      10122758.5
      3835152.09     10122769.41
#Sta/Elev= 30
       0  211.12    27.8  209.58    60.5  209.48    65.8  208.49   145.3  207.62
     344  209.17     404   207.8   605.5  206.37   611.1  207.32   616.3  206.52
   752.6  208.37   780.2  206.79   825.1  206.93   883.7  204.43     889  205.22
   992.5  200.58  1020.1  198.38  1085.6  200.89    1097  199.67  1114.2  192.74
  1119.3  192.74  1137.8  196.24  1147.8  201.49  1207.8  200.99  1217.8  199.87
  1287.8  198.54  1327.8  200.23  1427.9  199.37  1477.4  201.88  1643.3  216.44
#Mann= 3 , 0 , 0
       0     .11       0  1085.6     .04       0  1147.8     .11       0
Bank Sta=1085.6,1147.8
XS Rating Curve= 0 ,0
Exp/Cntr=0.3,0.1

Type RM Length L Ch R = 1 ,56593   ,384,384,384
XS GIS Cut Line= 3
      3836724.01     10123066.19      3835684.38     10122410.57
      3835284.03     10122318.03
#Sta/Elev= 30
       0  210.46   131.4  206.77   262.1  208.25   413.9  205.74   492.8  206.86
   711.7  206.61   811.7  200.27   964.9  200.74   994.1  198.39    1024  200.15
  1067.1  200.08    1073  198.61  1088.3  199.05  1103.6  192.42  1109.5  193.81
  1124.8  191.97  1130.7  196.67  1140.1  197.06    1146  200.81    1213  200.11
  1224.1  196.66  1229.1  196.66  1235.8  192.33    1245  192.41  1266.6  199.54
  1317.9  199.31  1511.6  211.12  1564.6  212.31  1615.5  215.25    1640  214.56
#Mann= 3 , 0 , 0
       0     .11       0    1213     .04       0  1266.6     .11       0
Bank Sta=1213,1266.6
XS Rating Curve= 0 ,0
Exp/Cntr=0.3,0.1

Type RM Length L Ch R = 1 ,56210   ,602,602,602
XS GIS Cut Line= 3
      3836725.35     10123050.09      3835984.97     10122236.19
       3835662.5     10121925.66
#Sta/Elev= 30
       0  210.24   132.3  205.31   259.3  205.61   323.1  204.13   464.7  205.81
     585  205.32   670.1  200.44   755.3  198.22   853.9  199.23   875.6  197.43
   889.7  199.58  1016.8  199.64  1038.4  198.15  1080.3  198.09  1087.7  194.02
    1109  192.03    1116  197.52  1130.1  199.81  1151.5   198.5  1193.7  199.71
  1278.6  198.77  1314.1  200.82    1321  204.65  1328.2  203.61  1335.2  206.78
  1427.3  207.38  1469.7  206.22  1533.3  207.68  1540.5  208.02  1547.4  211.81
#Mann= 3 , 0 , 0
       0     .11       0  1016.8     .04       0  1130.1     .11       0
Bank Sta=1016.8,1130.1
XS Rating Curve= 0 ,0
Exp/Cntr=0.3,0.1

Type RM Length L Ch R = 1 ,55608   ,699,699,699
XS GIS Cut Line= 3
      3836730.72     10123039.35      3836263.62     10121988.79
      3835922.92     10121502.05
#Sta/Elev= 30
       0  209.86   161.9  203.82   304.5  203.29   439.6  204.68   486.1  202.82
   621.9  201.19   711.7  197.41   752.8  197.11     787  199.11   833.5  196.67
   885.4  199.17  1001.7  197.26  1015.9  198.51    1025  197.05  1053.7  198.52
  1114.4  198.73  1128.9  197.42  1136.3   193.7    1152  191.58  1166.9   198.7
    1173  198.79  1244.6  197.58  1324.7  199.32  1366.7  204.43  1390.1  204.77
  1417.1  207.52  1690.9  208.75  1705.7   207.9  1720.5  209.86  1743.9  210.07
#Mann= 3 , 0 , 0
       0     .11       0  1114.4     .04       0    1173     .11       0
Bank Sta=1114.4,1173
XS Rating Curve= 0 ,0
Exp/Cntr=0.3,0.1

Type RM Length L Ch R = 1 ,54909   ,409,409,409
XS GIS Cut Line= 3
      3836752.19     10123029.96        3836623.     10122215.36
      3836565.28     10121505.53
#Sta/Elev= 30
       0  210.13   100.1  204.71     249  200.67   353.2  199.98   474.7  202.62
   677.2  202.38   778.5  196.88   798.7  197.55   808.9   195.7   824.4  189.75
   849.1  195.08   879.2  194.42   889.3  197.43   999.6  197.55  1029.7  199.16
  1079.9  197.55  1160.2  197.78  1180.2  196.24  1250.5  200.08  1280.6  204.64
  1290.6  204.51  1310.7  200.96  1317.9  201.39  1322.9  199.41  1380.9  206.82
  1461.2  207.27  1491.3  206.04  1501.3  207.29  1511.3  210.17  1536.7  211.88
#Mann= 3 , 0 , 0
       0     .11       0   798.7     .04       0   889.3     .11       0
Bank Sta=798.7,889.3
XS Rating Curve= 0 ,0
Exp/Cntr=0.3,0.1

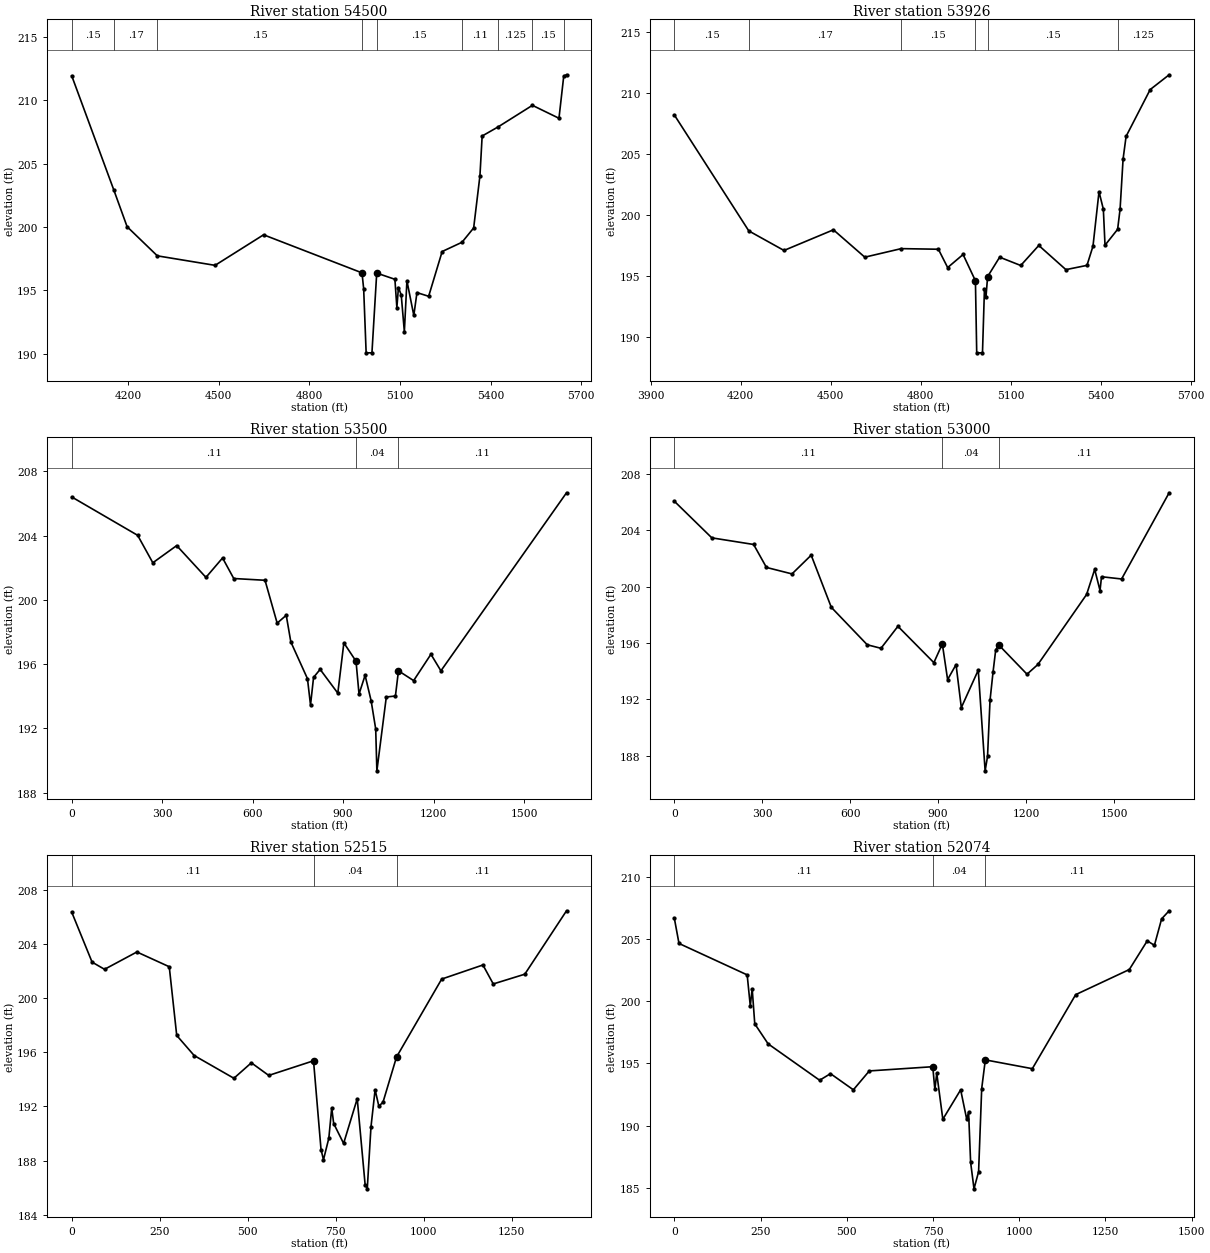
Type RM Length L Ch R = 1 ,54500   ,574,574,574
BEGIN DESCRIPTION:
STEWARTS CREEK 107.0
END DESCRIPTION:
XS GIS Cut Line= 3
      3836811.81     10123043.71      3836898.44     10122060.62
       3836714.6     10121436.12
#Sta/Elev= 30
  4013.1  211.93  4152.5  202.92  4196.4  200.03  4296.5  197.73  4487.6  196.98
  4648.2  199.39    4974196.3879  4979.5  195.13  4987.7  190.08  5006.9  190.08
  5022.7  196.37  5082.9  195.88  5089.4  193.65  5094.6  195.23  5103.8  194.65
  5114.2  191.75  5122.7  195.76  5145.5  193.03  5155.9  194.83  5194.6  194.54
  5239.3  198.07    5305   198.8  5343.6  199.93  5364.4  204.05  5371.7  207.18
  5425.3  207.91  5538.1   209.6    5626  208.58  5641.8  211.91    5651  212.01
#Mann= 9 ,-1 , 0
  4013.1     .15       0  4152.5     .17       0  4296.5     .15       0
    4974     .04       0  5022.7     .15       0    5305     .11       0
  5425.3    .125       0  5538.1     .15       0  5641.8    .125       0
Bank Sta=4974,5022.7
XS Rating Curve= 0 ,0
Exp/Cntr=0.3,0.1

Type RM Length L Ch R = 1 ,53926   ,426,426,426
BEGIN DESCRIPTION:
STEWARTS CREEK 106.0
END DESCRIPTION:
XS GIS Cut Line= 3
      3836975.01     10123106.19      3837214.14     10122113.79
      3837165.97     10121488.14
#Sta/Elev= 30
  3979.2  208.19  4227.3   198.7  4344.5   197.1  4509.1  198.79  4613.7  196.55
  4735.1  197.25  4858.8   197.2  4889.7   195.7  4941.1  196.77  4982.2  194.62
  4986.5  188.72  5005.7  188.72  5012.3  193.97  5017.3  193.28  5022.8  194.96
  5062.9  196.55  5133.1  195.87  5193.3  197.51  5283.6  195.53  5353.8  195.88
  5373.8  197.45  5393.9  201.91  5408.3  200.48  5413.9  197.53  5455.9  198.83
  5464.1  200.49  5474.1  204.59  5484.1  206.44  5564.4  210.27  5627.5  211.48
#Mann= 6 ,-1 , 0
  3979.2     .15       0  4227.3     .17       0  4735.1     .15       0
  4982.2     .04       0  5022.8     .15       0  5455.9    .125       0
#XS Ineff= 2 , 0
       0                  5393.9       0  201.91
Permanent Ineff=
       F       F
Bank Sta=4982.2,5022.8
XS Rating Curve= 0 ,0
Exp/Cntr=0.3,0.1

Type RM Length L Ch R = 1 ,53500   ,500,500,500
XS GIS Cut Line= 3
      3837485.36     10123078.56      3837593.67     10122068.47
      3837661.14     10121446.89
#Sta/Elev= 30
       0  206.41   218.7  204.02     269  202.31   348.1  203.38   445.2   201.4
   500.3  202.61   537.4  201.33   641.1  201.22   681.4  198.55   711.5  199.04
   726.7  197.38   781.9  195.09     792  193.45   802.1  195.17   823.9  195.67
   882.5  194.19   902.6  197.32   942.9  196.18   952.9  194.13     973   195.3
   993.1  193.71  1008.2  191.96  1012.1  189.35  1043.4  193.95  1073.6  194.01
  1083.7  195.58    1134  194.97  1191.4  196.61  1224.5  195.58  1641.1  206.67
#Mann= 3 , 0 , 0
       0     .11       0   942.9     .04       0  1083.7     .11       0
Bank Sta=942.9,1083.7
XS Rating Curve= 0 ,0
Exp/Cntr=0.3,0.1

Type RM Length L Ch R = 1 ,53000   ,524,524,524
XS GIS Cut Line= 3
      3837499.99     10123079.13      3837926.51      10122099.4
      3838048.86       10121492.
#Sta/Elev= 30
       0  206.06   127.9  203.46   270.5  202.99   314.2  201.36   401.4   200.9
   466.9  202.23   535.5  198.53   658.1  195.87     705  195.62   762.8  197.18
   885.4   194.6   914.3  195.93   932.3   193.4   961.1  194.46   979.1  191.41
  1036.9  194.07  1060.3  186.92  1068.5  187.94    1077  191.92  1087.2  193.91
  1096.5  195.52  1107.6  195.84  1203.2  193.78  1240.3  194.47  1406.5  199.44
  1434.1  201.22  1452.3  199.72  1457.4   200.7  1525.9  200.54  1688.1  206.66
#Mann= 3 , 0 , 0
       0     .11       0   914.3     .04       0  1107.6     .11       0
Bank Sta=914.3,1107.6
XS Rating Curve= 0 ,0
Exp/Cntr=0.3,0.1

Type RM Length L Ch R = 1 ,52515   ,402,402,402
XS GIS Cut Line= 3
      3838881.02     10122619.84      3838368.91     10122098.55
      3838064.97     10121494.15
#Sta/Elev= 30
       0  206.34    57.9  202.65    93.3  202.12   185.2   203.4   277.2  202.31
   298.4  197.24   347.9  195.76   460.9  194.08   510.5  195.22   559.9  194.29
   687.2  195.37   708.5  188.82   715.5  188.07   730.7  189.66   738.9  191.89
   744.5  190.74   772.7  189.27   811.4  192.57   833.8  186.24   839.9  185.92
   850.5   190.5   862.2  193.23   872.8  192.02   884.6  192.31   923.1  195.65
  1051.4   201.4  1168.6  202.44    1198  201.04  1287.6  201.76  1406.2  206.44
#Mann= 3 , 0 , 0
       0     .11       0   687.2     .04       0   923.1     .11       0
Bank Sta=687.2,923.1
XS Rating Curve= 0 ,0
Exp/Cntr=0.3,0.1

Type RM Length L Ch R = 1 ,52074   ,574,574,574
XS GIS Cut Line= 4
      3838895.34     10122583.38      3838534.45     10121788.27
      3838442.88      10121496.9      3838195.49     10121425.29
#Sta/Elev= 30
       0  206.69    13.5  204.66   211.2  202.13   220.2  199.64   225.7  201.01
   233.2  198.19   271.9  196.58   421.3  193.65   452.8  194.18   519.1  192.88
   565.3   194.4   749.3  194.74   755.4  192.91   760.9  194.21   778.5  190.51
   830.2  192.88   847.7  190.52   853.2  191.08   859.1  187.04   868.9  184.91
   882.2  186.29   891.2  192.98   901.7  195.29    1038  194.58  1163.7  200.54
  1319.2  202.56  1371.2  204.87    1392  204.51  1412.9  206.64  1434.7  207.29
#Mann= 3 , 0 , 0
       0     .11       0   749.3     .04       0   901.7     .11       0
Bank Sta=749.3,901.7
XS Rating Curve= 0 ,0
Exp/Cntr=0.3,0.1

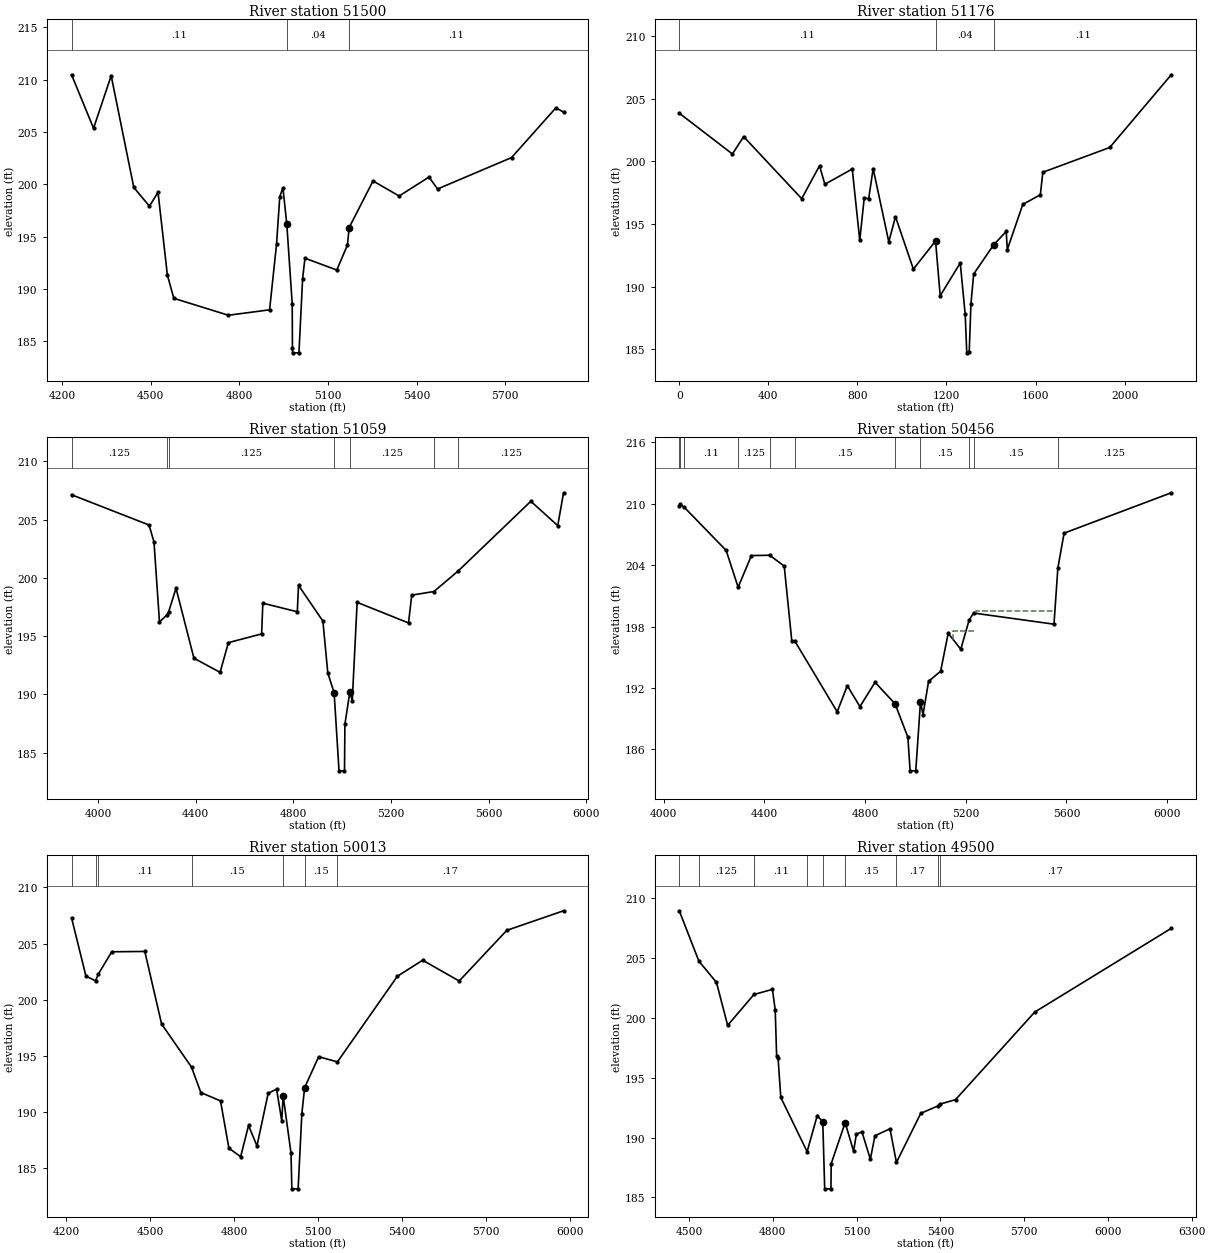
Type RM Length L Ch R = 1 ,51500   ,324,324,324
BEGIN DESCRIPTION:
STEWARTS CREEK 101.0
END DESCRIPTION:
XS GIS Cut Line= 4
      3839274.86     10122309.56      3838976.44     10121602.99
      3838831.34     10121390.56      3838191.99     10121410.07
#Sta/Elev= 30
    4233  210.47  4307.3  205.36  4366.9  210.38  4443.4  199.71  4496.2  197.92
  4525.4  199.24    4557  191.34  4578.7  189.12  4763.3   187.5  4902.7  188.02
  4926.1  194.26  4937.2  198.84  4947.8  199.67  4960.9  196.21  4979.2   188.6
    4980  184.41  4980.5  183.91    5002  183.91  5014.4  191.01  5022.3  192.95
    5130  191.82  5165.9   194.2  5171.9  195.88  5252.6  200.33  5340.8  198.89
  5441.8   200.7  5470.8  199.56    5721  202.56    5871  207.31  5896.9  206.91
#Mann= 3 , 0 , 0
    4233     .11       0  4960.9     .04       0  5171.9     .11       0
#XS Ineff= 2 , 0
       0  4947.8  199.67               0
Permanent Ineff=
       F       F
Bank Sta=4960.9,5171.9
XS Rating Curve= 0 ,0
Exp/Cntr=0.3,0.1

Type RM Length L Ch R = 1 ,51176   ,117,117,117
XS GIS Cut Line= 3
      3840385.79     10121437.98      3839094.76     10121334.94
      3838181.95     10121393.48
#Sta/Elev= 30
       0  203.85   238.7  200.59   288.9  201.98   549.7  197.02   629.9  199.65
   653.7  198.17   776.8  199.39   810.5  193.69   830.6  197.08   850.6  197.02
   870.7  199.42   940.9  193.57     971  195.58  1051.3  191.39  1150.9  193.64
  1171.7  189.26  1261.9  191.88    1284  187.78  1291.1   184.7  1302.1  184.77
  1309.9  188.62  1322.1     191  1412.3  193.34  1468.2   194.4  1473.2  192.95
  1542.6  196.56  1621.5  197.33  1632.7  199.13  1933.1  201.11  2209.4  206.92
#Mann= 3 , 0 , 0
       0     .11       0  1150.9     .04       0  1412.3     .11       0
Bank Sta=1150.9,1412.3
XS Rating Curve= 0 ,0
Exp/Cntr=0.3,0.1

Type RM Length L Ch R = 1 ,51059   ,603,603,603
BEGIN DESCRIPTION:
STEWARTS CREEK 99.0
END DESCRIPTION:
XS GIS Cut Line= 3
      3840184.51     10121140.88      3839078.77     10121219.02
      3838174.12     10121273.69
#Sta/Elev= 30
  3891.5  207.14  4208.9  204.54    4229  203.08  4251.5  196.22  4281.9  196.81
  4288.5  197.05  4319.2  199.11  4392.6   193.1  4499.7  191.89  4533.7  194.44
  4669.8  195.19  4674.8  197.83  4815.9  197.09  4820.9  199.36  4920.7  196.29
  4940.8  191.84 4966.72190.1411  4986.8  183.43  5009.2  183.43  5010.9  187.43
    5031  190.19    5041  189.46    5061   197.9  5271.4  196.13  5284.6  198.52
  5375.5  198.83  5474.6  200.59  5772.3  206.58  5882.5  204.49  5906.3  207.31
#Mann= 7 ,-1 , 0
  3891.5    .125       0  4281.9     .11       0  4288.5    .125       0
 4966.72     .04       0    5031    .125       0  5375.5     .11       0
  5474.6    .125       0
Bank Sta=4966.72,5031
XS Rating Curve= 0 ,0
Exp/Cntr=0.3,0.1

Type RM Length L Ch R = 1 ,50456   ,443,443,443
BEGIN DESCRIPTION:
Mapping XS a3c352fb
END DESCRIPTION:
XS GIS Cut Line= 3
      3840163.71     10120797.12      3839228.23     10120857.05
      3838212.33     10120836.99
#Sta/Elev= 30
  4062.6  209.83    4067  209.95  4082.1  209.67  4248.8  205.44  4296.3  201.84
    4349  204.94  4421.8  204.97  4479.3  203.91  4509.4  196.59  4520.9   196.6
  4689.7  189.66  4729.8  192.22  4779.9  190.17  4840.1  192.55  4919.4190.4442
  4970.3  187.18  4979.2  183.89  5001.6  183.89  5020.4  190.64  5030.4  189.38
  5052.5  192.64  5100.4  193.63  5130.4  197.34  5180.4  195.78  5213.5  198.63
  5231.1  199.32  5550.5  198.23  5565.8   203.7  5590.5  207.13  6016.1  211.08
#Mann= 11 ,-1 , 0
  4062.6     .11       0    4067    .125       0  4082.1     .11       0
  4296.3    .125       0  4421.8     .11       0  4520.9     .15       0
  4919.4     .04       0  5020.4     .15       0  5213.5    .125       0
  5231.1     .15       0  5565.8    .125       0
#XS Ineff= 2 ,-1
  5150.4  5240.4  197.52  5240.4  5555.8  199.48
Permanent Ineff=
       F       F
Bank Sta=4919.4,5020.4
XS Rating Curve= 0 ,0
Exp/Cntr=0.3,0.1

Type RM Length L Ch R = 1 ,50013   ,513,513,513
BEGIN DESCRIPTION:
STEWARTS CREEK 98.0
END DESCRIPTION:
XS GIS Cut Line= 3
        3840109.     10120416.92      3839329.96     10120467.77
       3838356.4     10120377.85
#Sta/Elev= 30
  4219.3  207.28  4270.6  202.11  4304.9  201.68    4315  202.29  4362.8  204.27
    4481   204.3  4541.1  197.84    4648     194  4681.4  191.74  4751.6     191
  4781.6  186.79  4823.6  186.03  4851.8  188.81  4881.9  186.99  4921.9  191.67
    4952  192.05  4970.5  189.23  4975.5  191.45  5003.6  186.35  5006.6  183.17
    5029  183.17  5042.3  189.86  5052.3  192.18  5102.5  194.93  5169.5  194.47
  5383.7  202.09  5474.1  203.52  5604.7  201.67    5775  206.18  5977.7  207.92
#Mann= 7 ,-1 , 0
  4219.3     .11       0  4304.9    .125       0    4315     .11       0
    4648     .15       0  4975.5     .04       0  5052.3     .15       0
  5169.5     .17       0
Bank Sta=4975.5,5052.3
XS Rating Curve= 0 ,0
Exp/Cntr=0.3,0.1

Type RM Length L Ch R = 1 ,49500   ,1042,1042,1042
BEGIN DESCRIPTION:
STEWARTS CREEK 97.0
END DESCRIPTION:
XS GIS Cut Line= 3
      3840100.75     10120087.94       3839566.8      10120054.4
      3838342.89     10120140.03
#Sta/Elev= 30
    4465  208.97  4535.2  204.76  4598.2  202.98  4638.2  199.39  4732.5  201.97
  4798.6   202.4  4808.6  200.68  4813.7  196.82  4818.7  196.68  4828.6  193.36
  4922.8  188.83  4958.9  191.83  4978.9  191.34  4985.8  185.72  5008.2  185.72
    5009  187.82  5059.1  191.26  5089.2  188.86  5099.2  190.29  5119.2  190.48
  5149.3   188.2  5165.8  190.16  5219.5  190.74  5242.7  187.93  5329.8  192.03
  5390.9  192.65    5397  192.79  5454.4  193.18    5738   200.5  6226.9   207.5
#Mann= 9 ,-1 , 0
    4465     .11       0  4535.2    .125       0  4732.5     .11       0
  4922.8     .15       0  4978.9     .04       0  5059.1     .15       0
  5242.7     .17       0  5390.9     .15       0    5397     .17       0
Bank Sta=4978.9,5059.1
XS Rating Curve= 0 ,0
Exp/Cntr=0.3,0.1

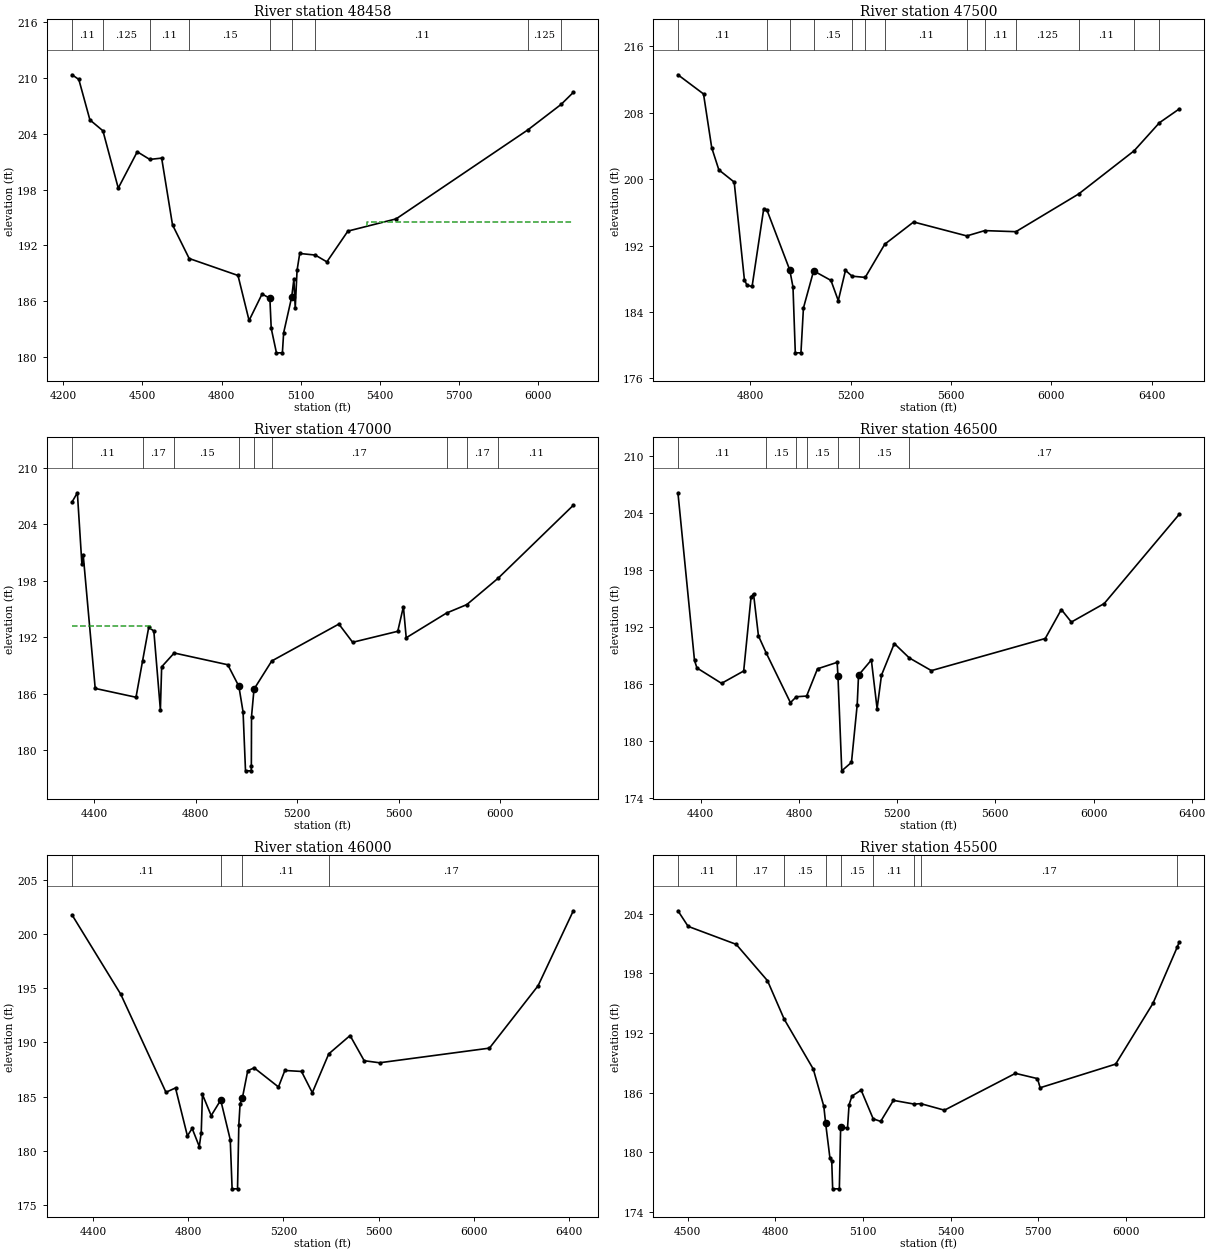
Type RM Length L Ch R = 1 ,48458   ,958,958,958
BEGIN DESCRIPTION:
STEWARTS CREEK 95.0
END DESCRIPTION:
XS GIS Cut Line= 3
      3840158.07     10119752.01      3839412.47     10119572.98
      3838296.07     10119765.03
#Sta/Elev= 30
  4233.2  210.31  4258.9  209.81  4300.9  205.47  4350.2   204.3  4408.3  198.15
  4480.3  202.05  4527.7  201.23  4572.8  201.37  4613.9  194.21  4677.1   190.6
  4862.1  188.78  4904.1  183.95  4953.3  186.79  4982.9  186.33    4988  183.11
  5007.8  180.48  5030.3  180.48  5035.1  182.63  5065.6  186.47  5073.9  188.38
    5079  185.28  5085.9  189.32    5096  191.14  5154.9  190.97  5198.9  190.24
  5278.6  193.54  5461.3  194.85  5961.1  204.41  6086.5  207.13  6132.8  208.42
#Mann= 9 ,-1 , 0
  4233.2     .11       0  4350.2    .125       0  4527.7     .11       0
  4677.1     .15       0  4982.9     .04       0  5065.6     .15       0
  5154.9     .11       0  5961.1    .125       0  6086.5     .15       0
#XS Ineff= 2 , 0
       0                  5349.7       0  194.56
Permanent Ineff=
       F       F
Bank Sta=4982.9,5065.6
XS Rating Curve= 0 ,0
Exp/Cntr=0.3,0.1

Type RM Length L Ch R = 1 ,47500   ,500,500,500
BEGIN DESCRIPTION:
STEWARTS CREEK 93.0
END DESCRIPTION:
XS GIS Cut Line= 3
      3840067.86     10118861.07      3839588.83     10118953.69
      3838211.92      10119570.6
#Sta/Elev= 30
  4512.1  212.58    4614  210.27  4646.7  203.79  4675.1  201.12  4736.2  199.65
  4776.9  187.87  4787.1  187.22  4807.5  187.07  4853.9  196.45  4866.5  196.29
  4957.5  189.06  4970.4     187  4979.6  179.07  5002.1  179.07    5012  184.47
  5052.6  188.95  5121.6   187.8  5150.8  185.36  5179.5  189.01  5205.6  188.31
  5258.1  188.16  5335.9  192.16  5450.9  194.84  5662.7  193.16  5734.2   193.8
  5858.3  193.67    6108  198.21  6329.3  203.42    6430   206.8  6508.8  208.46
#Mann= 13 ,-1 , 0
  4512.1     .11       0  4866.5     .15       0  4957.5     .04       0
  5052.6     .15       0  5205.6     .17       0  5258.1     .15       0
  5335.9     .11       0  5662.7    .125       0  5734.2     .11       0
  5858.3    .125       0    6108     .11       0  6329.3    .125       0
    6430     .15       0
#XS Ineff= 2 , 0
       0  4853.9  196.45  5450.9       0  194.84
Permanent Ineff=
       F       F
Bank Sta=4957.5,5052.6
XS Rating Curve= 0 ,0
Exp/Cntr=0.3,0.1

Type RM Length L Ch R = 1 ,47000   ,500,500,500
BEGIN DESCRIPTION:
STEWARTS CREEK 92.0
END DESCRIPTION:
XS GIS Cut Line= 3
      3839988.74     10118511.99      3839304.82     10118579.13
      3838145.02     10119140.46
#Sta/Elev= 30
  4312.8  206.39  4333.8  207.37  4351.7  199.74  4356.7  200.79  4404.1  186.55
  4564.9  185.61  4590.6  189.45  4615.1  193.07  4635.2  192.65    4661  184.28
    4666  188.85  4715.4  190.32  4926.6  189.07  4970.3  186.78  4986.9  184.05
  4996.5  177.78    5019  177.78  5019.5  178.28  5020.2  183.56    5030  186.47
  5099.9  189.47  5364.5   193.4  5418.8  191.46  5596.6  192.63  5618.8  195.25
  5629.9  191.94  5788.7  194.57  5868.7  195.47  5992.3  198.28  6288.5  206.04
#Mann= 9 ,-1 , 0
  4312.8     .11       0  4590.6     .17       0  4715.4     .15       0
  4970.3     .04       0    5030     .15       0  5099.9     .17       0
  5788.7     .11       0  5868.7     .17       0  5992.3     .11       0
#XS Ineff= 2 , 0
       0  4625.2   193.2  5364.5       0   193.4
Permanent Ineff=
       F       F
Bank Sta=4970.3,5030
XS Rating Curve= 0 ,0
Exp/Cntr=0.3,0.1

Type RM Length L Ch R = 1 ,46500   ,500,500,500
BEGIN DESCRIPTION:
STEWARTS CREEK 91.0
END DESCRIPTION:
XS GIS Cut Line= 3
      3840065.19     10118255.04      3839373.58     10118209.61
      3838138.12     10118751.55
#Sta/Elev= 30
  4306.9  206.09  4374.4  188.44  4384.4  187.65  4484.6  186.03  4574.8  187.33
  4604.9  195.15  4614.9  195.45  4634.9  191.03  4666.3  189.24  4765.2     184
  4789.3  184.62  4831.1  184.69  4875.5  187.56  4955.6  188.24 4958.83186.8073
  4974.4  176.82  5013.9  177.71  5037.3  183.79  5042.7  186.89  5094.9  188.49
  5118.3  183.37  5136.2  186.89  5188.4  190.22  5249.3  188.71  5339.5  187.37
  5803.4  190.75  5868.9   193.8  5909.7  192.48  6043.6  194.43  6349.1  203.82
#Mann= 7 ,-1 , 0
  4306.9     .11       0  4666.3     .15       0  4789.3     .17       0
  4831.1     .15       0 4958.83     .04       0  5042.7     .15       0
  5249.3     .17       0
#XS Ineff= 2 , 0
       0  4614.9  195.45               0
Permanent Ineff=
       F       F
Bank Sta=4958.83,5042.7
XS Rating Curve= 0 ,0
Exp/Cntr=0.3,0.1

Type RM Length L Ch R = 1 ,46000   ,500,500,500
BEGIN DESCRIPTION:
STEWARTS CREEK 90.0
END DESCRIPTION:
XS GIS Cut Line= 3
      3840162.41     10117782.82      3839474.34     10117812.12
      3838121.75     10118240.83
#Sta/Elev= 30
  4311.3  201.75    4516  194.44  4706.2   185.4  4746.3   185.8  4796.3  181.38
  4816.3  182.07  4846.3   180.4  4854.5  181.68  4859.6   185.2  4896.4  183.25
  4936.4  184.68  4976.5  181.03  4984.3   176.5  5007.1   176.5  5012.6  182.42
  5017.8  184.33  5027.8  184.91  5050.1  187.39  5077.1  187.65  5179.2  185.89
  5206.1  187.41  5276.1  187.32  5321.5  185.36  5390.6  188.94  5480.3  190.63
  5539.6  188.31  5604.2  188.12  6066.3  189.47  6270.8  195.22  6418.9  202.13
#Mann= 4 ,-1 , 0
  4311.3     .11       0  4936.4     .04       0  5027.8     .11       0
  5390.6     .17       0
#XS Ineff= 2 , 0
       0                  5480.3       0  190.63
Permanent Ineff=
       F       F
Bank Sta=4936.4,5027.8
XS Rating Curve= 0 ,0
Exp/Cntr=0.3,0.1

Type RM Length L Ch R = 1 ,45500   ,500,500,500
BEGIN DESCRIPTION:
STEWARTS CREEK 89.0
END DESCRIPTION:
XS GIS Cut Line= 3
      3839540.84      10117064.1      3839214.68     10117486.79
      3838131.98     10117963.01
#Sta/Elev= 30
  4466.1  204.31    4501  202.74  4665.6  200.93  4772.8  197.27  4830.1  193.39
  4929.6  188.37  4965.7  184.62    4972  182.89  4986.5  179.45  4992.9  179.07
    4996  176.31  5018.9  176.31  5023.4  182.58  5046.8  182.41  5052.2  184.78
  5062.1  185.65  5093.5  186.25  5134.8  183.36  5160.4   183.1  5204.1  185.22
  5275.9  184.84  5297.4  184.89  5378.9  184.23  5621.9  187.94  5697.4  187.41
  5706.6  186.49  5965.1  188.87  6092.8  194.98  6175.9  200.64  6182.8  201.15
#Mann= 9 ,-1 , 0
  4466.1     .11       0  4665.6     .17       0  4830.1     .15       0
    4972     .04       0  5023.4     .15       0  5134.8     .11       0
  5275.9     .15       0  5297.4     .17       0  6175.9     .11       0
Bank Sta=4972,5023.4
XS Rating Curve= 0 ,0
Exp/Cntr=0.3,0.1