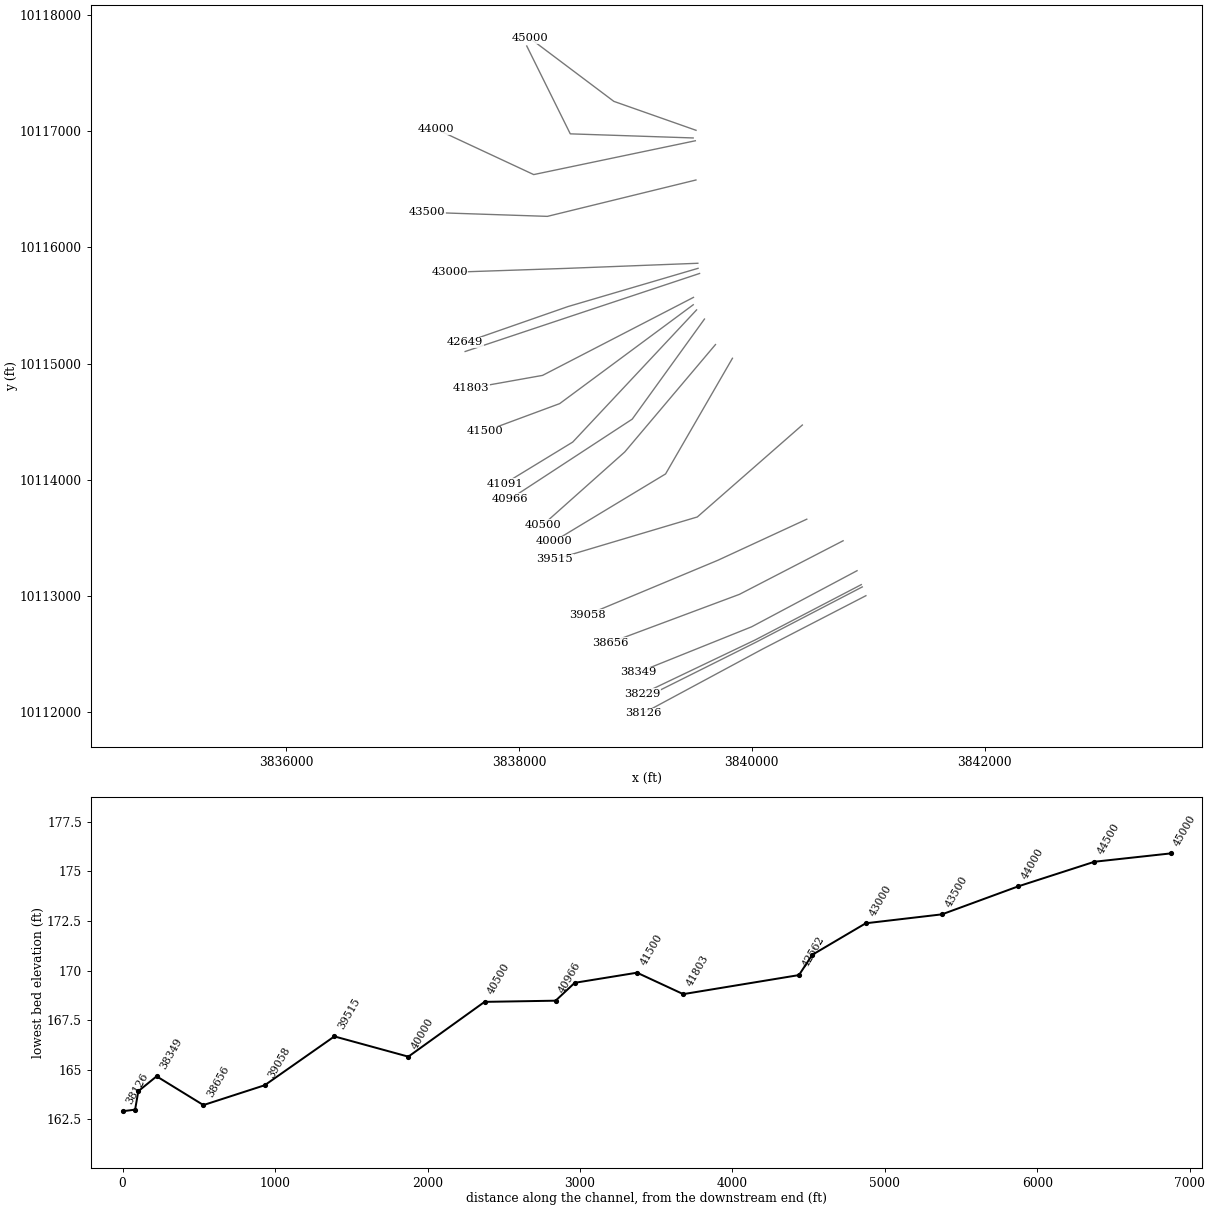
HEC-RAS study STEWARTS CREEK.prj: STEWARTS CREEK Base Level Engineering

--- STEWARTS CREEK.g01 (geometry) --- (continued)

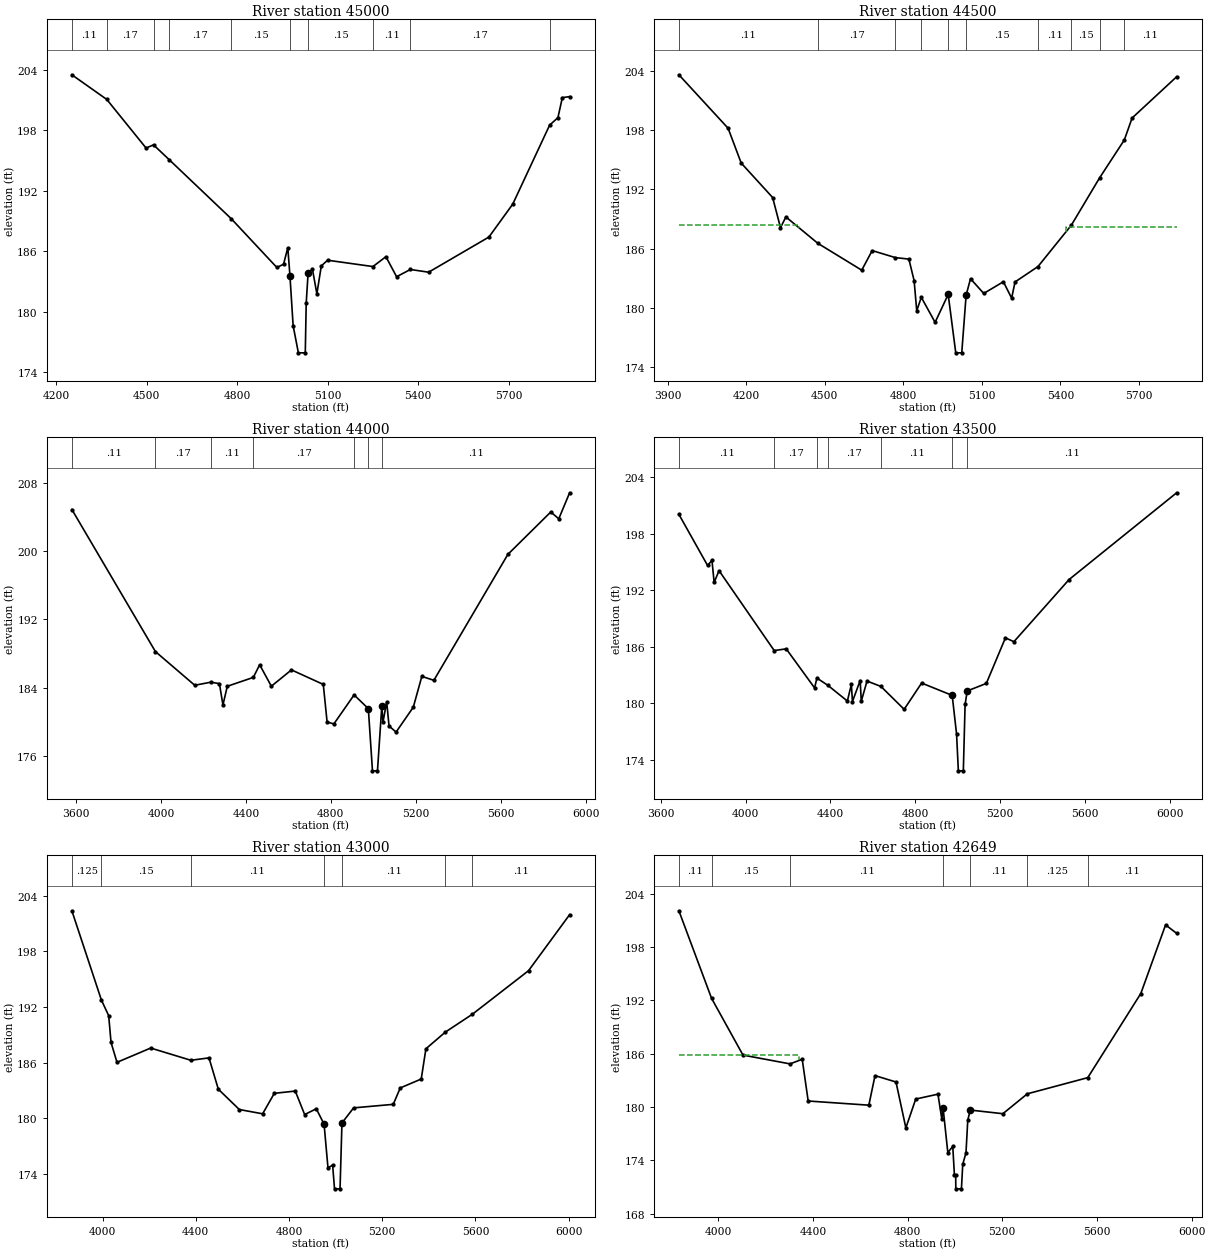
Type RM Length L Ch R = 1 ,45000   ,500,500,500
BEGIN DESCRIPTION:
STEWARTS CREEK 88.0
END DESCRIPTION:
XS GIS Cut Line= 3
      3839520.06      10117008.5      3838813.86     10117257.48
      3838092.91     10117800.21
#Sta/Elev= 30
  4251.2  203.52    4367  201.07  4497.4  196.24    4522  196.56  4574.3  195.08
    4780  189.22  4931.2  184.38  4953.4   184.7  4967.5  186.34  4974.6  183.57
  4985.2   178.6  5002.6   175.9  5025.5   175.9  5028.6  180.84  5034.9  183.85
  5049.4  184.18    5064  181.76  5078.6  184.53  5099.4   185.1  5249.9  184.47
    5293  185.45  5328.4  183.46  5374.2  184.18  5434.7  183.91  5634.6   187.4
  5713.7  190.67  5836.1  198.52  5863.6  199.26  5878.2  201.25  5902.4  201.35
#Mann= 10 ,-1 , 0
  4251.2     .11       0    4367     .17       0    4522     .11       0
  4574.3     .17       0    4780     .15       0  4974.6     .04       0
  5034.9     .15       0  5249.9     .11       0  5374.2     .17       0
  5836.1     .11       0
Bank Sta=4974.6,5034.9
XS Rating Curve= 0 ,0
Exp/Cntr=0.3,0.1

Type RM Length L Ch R = 1 ,44500   ,500,500,500
BEGIN DESCRIPTION:
STEWARTS CREEK 87.0
END DESCRIPTION:
XS GIS Cut Line= 3
      3839495.67     10116942.54      3838439.16     10116977.91
      3838065.18     10117734.19
#Sta/Elev= 30
  3942.9  203.57  4130.8  198.17  4180.9  194.65  4300.9  191.17  4330.9  188.13
  4351.6  189.21  4473.2  186.55  4641.1  183.83  4681.1  185.81  4769.7   185.1
  4821.2  184.95  4841.2  182.77  4851.2  179.73  4868.6  181.09  4921.3  178.56
  4971.3  181.38  5000.2  175.48  5023.1  175.48  5039.7  181.29  5056.5  182.97
    5107  181.48    5182  182.66  5213.6  181.01  5226.6  182.64  5314.3   184.2
  5441.7  188.38  5549.3  193.15    5644  196.99  5673.5   199.2  5843.7  203.37
#Mann= 10 ,-1 , 0
  3942.9     .11       0  4473.2     .17       0  4769.7     .11       0
  4868.6     .15       0  4971.3     .04       0  5039.7     .15       0
  5314.3     .11       0  5441.7     .15       0  5549.3     .17       0
    5644     .11       0
#XS Ineff= 2 , 0
       0    4401  188.41  5421.1       0  188.24
Permanent Ineff=
       F       F
Bank Sta=4971.3,5039.7
XS Rating Curve= 0 ,0
Exp/Cntr=0.3,0.1

Type RM Length L Ch R = 1 ,44000   ,500,500,500
BEGIN DESCRIPTION:
STEWARTS CREEK 86.0
END DESCRIPTION:
XS GIS Cut Line= 3
      3839514.02     10116918.31       3838124.9     10116627.18
      3837287.46     10117018.14
#Sta/Elev= 30
  3580.7  204.87    3974  188.22  4159.2  184.27  4234.9  184.63  4275.4  184.46
    4292  181.96  4312.4  184.15  4434.9  185.19  4464.9  186.67  4519.9  184.16
  4614.6  186.07  4764.4  184.37  4782.4  179.96  4814.3  179.74  4909.5  183.14
  4976.5  181.53    4996  174.24  5019.5  174.24    5040  181.84  5045.5  179.95
  5062.9  182.33    5074   179.5  5107.1  178.78  5188.2   181.7  5228.4  185.31
  5285.1  184.85  5633.5  199.61  5835.5  204.58  5873.1  203.78  5924.2  206.83
#Mann= 7 ,-1 , 0
  3580.7     .11       0    3974     .17       0  4234.9     .11       0
  4434.9     .17       0  4909.5     .11       0  4976.5     .04       0
    5040     .11       0
#XS Ineff= 2 ,-1
  4614.6  4464.9  186.07  4464.9  3975.3  186.67
Permanent Ineff=
       F       F
Bank Sta=4976.5,5040
XS Rating Curve= 0 ,0
Exp/Cntr=0.3,0.1

Type RM Length L Ch R = 1 ,43500   ,500,500,500
BEGIN DESCRIPTION:
STEWARTS CREEK 85.0
END DESCRIPTION:
XS GIS Cut Line= 3
      3839519.28     10116580.57      3838242.63     10116267.42
       3837211.1     10116301.93
#Sta/Elev= 30
  3685.5  200.06  3820.8  194.63  3841.4  195.18  3851.7  192.84  3874.9  194.08
  4134.8   185.6  4191.5  185.78  4325.4  181.63  4336.1  182.68  4387.7  181.91
  4479.8  180.24  4498.6  182.01  4503.7  180.19  4540.2  182.42  4545.3  180.22
  4572.5  182.36  4638.1  181.79  4747.5  179.36  4829.9  182.15    4974  180.84
  4994.6  176.73    5003  172.83  5026.5  172.83  5034.8  179.88  5044.8  181.31
  5134.9  182.11  5224.9  186.95  5264.9  186.54  5525.1  193.14  6032.1  202.35
#Mann= 7 ,-1 , 0
  3685.5     .11       0  4134.8     .17       0  4336.1     .11       0
  4387.7     .17       0  4638.1     .11       0    4974     .04       0
  5044.8     .11       0
Bank Sta=4974,5044.8
XS Rating Curve= 0 ,0
Exp/Cntr=0.3,0.1

Type RM Length L Ch R = 1 ,43000   ,351,351,351
BEGIN DESCRIPTION:
STEWARTS CREEK 84.0
END DESCRIPTION:
XS GIS Cut Line= 3
      3839535.77     10115863.63      3838405.13     10115819.57
       3837401.6     10115785.54
#Sta/Elev= 30
  3868.5  202.36  3995.3  192.73  4026.5  191.05  4036.5  188.17  4062.1  186.02
  4206.7  187.56  4379.2  186.24  4456.9   186.5  4496.9  183.12    4587  180.93
    4687  180.47  4737.1  182.68  4827.1  182.92  4867.2  180.39  4917.2  181.01
 4950.61179.3528  4967.3  174.65  4987.3  174.93  4995.4  172.38  5019.1  172.38
  5027.3  179.48  5077.3  181.11  5247.4  181.49  5277.4  183.26  5367.5  184.22
  5387.5  187.48  5470.4  189.27  5587.1  191.21  5827.8   195.9  6004.1  201.94
#Mann= 7 ,-1 , 0
  3868.5    .125       0  3995.3     .15       0  4379.2     .11       0
 4950.61     .04       0  5027.3     .11       0  5470.4    .125       0
  5587.1     .11       0
Bank Sta=4950.61,5027.3
XS Rating Curve= 0 ,0
Exp/Cntr=0.3,0.1

Type RM Length L Ch R = 1 ,42649   ,87,87,87
BEGIN DESCRIPTION:
Mapping XS cf581715
END DESCRIPTION:
XS GIS Cut Line= 3
      3839537.51     10115820.06      3838419.28      10115490.8
      3837534.92     10115182.05
#Sta/Elev= 30
  3834.3   202.1  3972.2  192.25    4105  185.85  4303.6  184.86  4355.2  185.38
  4380.4  180.68  4636.6  180.21  4662.7  183.54  4751.3  182.82    4793  177.65
  4834.6   180.9  4928.5  181.45    4945  178.63  4950.3  179.87  4970.2  174.87
  4991.1  175.57  4998.1  172.33  5003.4  172.33    5004  170.79  5027.7  170.79
  5033.3  173.57  5046.9  174.83  5054.5  178.54  5065.1  179.66  5202.8  179.25
    5306  181.49  5561.3  183.31  5785.3  192.78    5890  200.51  5936.7  199.56
#Mann= 7 ,-1 , 0
  3834.3     .11       0  3972.2     .15       0  4303.6     .11       0
  4950.3     .04       0  5065.1     .11       0    5306    .125       0
  5561.3     .11       0
#XS Ineff= 2 , 0
       0  4341.8  185.85               0
Permanent Ineff=
       F       F
Bank Sta=4950.3,5065.1
XS Rating Curve= 0 ,0
Exp/Cntr=0.3,0.1

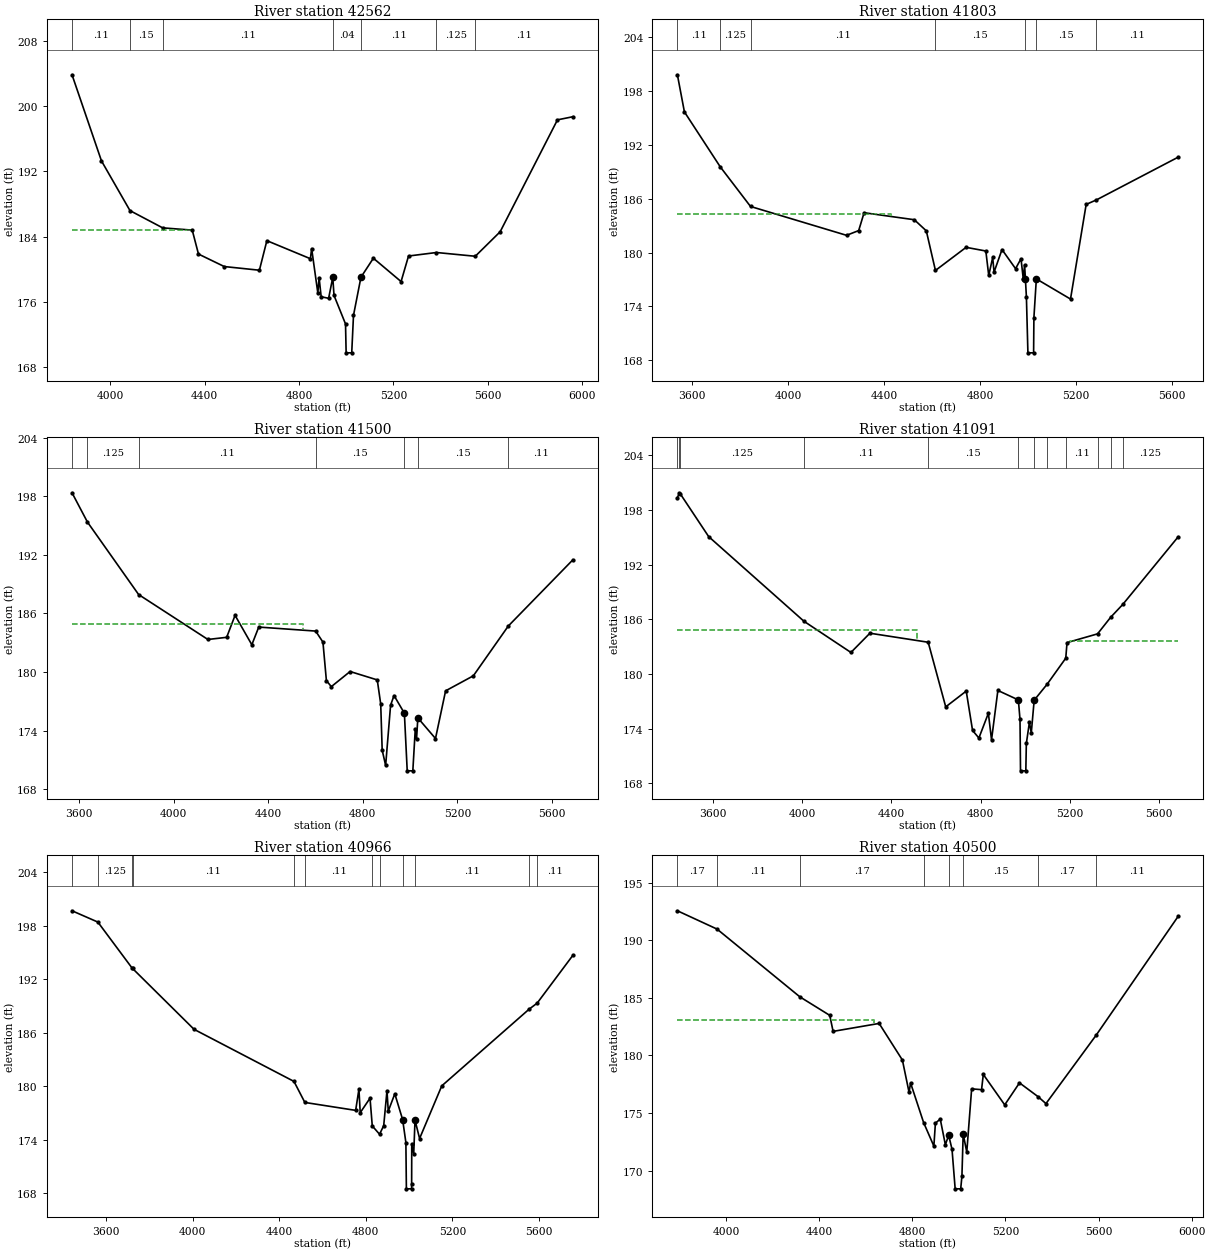
Type RM Length L Ch R = 1 ,42562   ,759,759,759
BEGIN DESCRIPTION:
STEWARTS CREEK 83.0
END DESCRIPTION:
XS GIS Cut Line= 3
      3839550.53     10115775.79      3838446.92     10115408.58
       3837535.6     10115103.93
#Sta/Elev= 30
  3836.9  203.83  3961.8  193.28  4082.8  187.19  4221.3  185.08  4346.8   184.8
  4373.2  181.87  4482.6  180.34  4631.6  179.89  4663.3  183.51  4847.9   181.3
  4853.2  182.54  4879.5  177.09  4884.8  178.98  4893.6  176.64  4925.2  176.45
  4942.8  179.01  4948.1   176.8  4996.9  173.31  4999.5  169.77  5023.2  169.77
  5030.7  174.36  5062.3  179.03    5115  181.36  5232.5   178.5  5264.1  181.63
  5382.7  182.06  5547.2   181.6  5652.7   184.6  5895.8  198.31  5960.9  198.69
#Mann= 7 ,-1 , 0
  3836.9     .11       0  4082.8     .15       0  4221.3     .11       0
  4942.8     .04       0  5062.3     .11       0  5382.7    .125       0
  5547.2     .11       0
#XS Ineff= 2 , 0
       0  4341.6  184.82               0
Permanent Ineff=
       F       F
Bank Sta=4942.8,5062.3
XS Rating Curve= 0 ,0
Exp/Cntr=0.3,0.1

Type RM Length L Ch R = 1 ,41803   ,303,303,303
BEGIN DESCRIPTION:
STEWARTS CREEK 82.0
END DESCRIPTION:
XS GIS Cut Line= 3
      3839498.04     10115569.86       3838201.1      10114898.3
      3837586.51     10114788.59
#Sta/Elev= 30
  3539.5  199.83  3568.7  195.69  3717.9  189.56  3843.9  185.14  4243.6  181.92
  4294.2  182.45  4316.7  184.44  4525.7  183.66  4575.7  182.42  4613.7     178
  4741.4  180.58  4823.5  180.17  4835.6  177.44  4852.1  179.45  4857.7  177.81
  4890.8  180.33  4947.3   178.2  4969.9  179.31  4979.3  177.08  4984.9  178.63
  4988.3177.0116  4992.4  175.06  4998.7  168.81  5022.4  168.81  5023.6  172.73
  5033.8  177.06    5176  174.81  5241.2  185.37  5283.9  185.87  5624.3  190.64
#Mann= 7 ,-1 , 0
  3539.5     .11       0  3717.9    .125       0  3843.9     .11       0
  4613.7     .15       0  4988.3     .04       0  5033.8     .15       0
  5283.9     .11       0
#XS Ineff= 2 , 0
       0  4429.3  184.35               0
Permanent Ineff=
       F       F
Bank Sta=4988.3,5033.8
XS Rating Curve= 0 ,0
Exp/Cntr=0.3,0.1

Type RM Length L Ch R = 1 ,41500   ,409,409,409
BEGIN DESCRIPTION:
STEWARTS CREEK 81.0
END DESCRIPTION:
XS GIS Cut Line= 3
       3839496.3      10115506.5      3838348.19     10114655.34
      3837703.73      10114416.2
#Sta/Elev= 30
  3570.8  198.36    3636  195.36  3852.3  187.94  4145.1  183.34  4224.4  183.56
  4259.9  185.81  4330.8   182.8    4360  184.61  4600.5   184.2  4631.3  183.07
  4645.9  179.13  4666.7  178.51  4746.1  180.06  4860.9   179.2  4875.5  176.73
  4881.7  172.01  4896.3  170.44  4917.2  176.61  4931.8   177.6  4975.5  175.79
  4987.5  169.89  5011.2  169.89  5021.5  174.14  5026.8   173.1  5032.4  175.31
    5107   173.2  5149.7  178.08    5267  179.62  5414.8  184.72  5687.4  191.49
#Mann= 7 ,-1 , 0
  3570.8     .11       0    3636    .125       0  3852.3     .11       0
  4600.5     .15       0  4975.5     .04       0  5032.4     .15       0
  5414.8     .11       0
#XS Ineff= 2 , 0
       0  4545.7  184.91               0
Permanent Ineff=
       F       F
Bank Sta=4975.5,5032.4
XS Rating Curve= 0 ,0
Exp/Cntr=0.3,0.1

Type RM Length L Ch R = 1 ,41091   ,125,125,125
BEGIN DESCRIPTION:
STEWARTS CREEK 80.0
END DESCRIPTION:
XS GIS Cut Line= 3
      3839524.94     10115462.23      3838460.57     10114324.35
      3837876.49     10113967.42
#Sta/Elev= 30
  3441.9  199.33  3450.3  199.89  3454.4  199.79    3582  195.08  4008.8  185.79
    4219  182.37    4304  184.48    4565  183.49  4643.5   176.4  4735.3  178.13
  4763.7  173.81    4792  172.98  4834.5   175.7  4848.6  172.78    4877   178.2
  4968.8  177.16  4976.1  175.02  4978.4  169.38  5002.2  169.38  5004.5  172.38
  5018.3  174.71  5026.6  173.53  5039.6  177.13  5097.5  178.88    5181  181.74
  5186.7  183.45  5323.4  184.41  5382.1  186.23  5436.4  187.64  5684.5  195.06
#Mann= 12 ,-1 , 0
  3441.9    .125       0  3450.3     .11       0  3454.4    .125       0
  4008.8     .11       0    4565     .15       0  4968.8     .04       0
  5039.6     .15       0  5097.5     .15       0    5181     .11       0
  5323.4     .17       0  5382.1     .11       0  5436.4    .125       0
#XS Ineff= 2 , 0
       0    4516  184.81  5202.1       0  183.61
Permanent Ineff=
       F       F
Bank Sta=4968.8,5039.6
XS Rating Curve= 0 ,0
Exp/Cntr=0.3,0.1

Type RM Length L Ch R = 1 ,40966   ,466,466,466
BEGIN DESCRIPTION:
Mapping XS c4c9fd89
END DESCRIPTION:
XS GIS Cut Line= 3
      3839592.63     10115383.37      3838971.97     10114521.81
       3837924.5     10113835.35
#Sta/Elev= 30
  3442.1   199.7  3561.6  198.43  3720.2  193.25  3721.9  193.22    4006  186.39
  4467.8  180.54    4518  178.18  4752.8  177.29  4767.9  179.67  4773.9  177.03
  4819.2  178.66  4829.6  175.54  4863.2  174.61  4882.4  175.57  4897.5   179.5
  4903.5  177.21  4933.7  179.15  4969.8  176.26  4984.9  173.68  4987.2  168.48
    5011  168.48  5011.5  168.98    5012  173.47  5021.1  172.44  5027.1  176.19
  5048.2  174.13  5150.7  180.04  5553.8  188.64  5591.5  189.33  5756.3  194.69
#Mann= 12 ,-1 , 0
  3442.1     .11       0  3561.6    .125       0  3720.2     .17       0
  3721.9     .11       0  4467.8     .17       0    4518     .11       0
  4829.6     .15       0  4863.2     .11       0  4969.8     .04       0
  5027.1     .11       0  5553.8    .125       0  5591.5     .11       0
Bank Sta=4969.8,5027.1
XS Rating Curve= 0 ,0
Exp/Cntr=0.3,0.1

Type RM Length L Ch R = 1 ,40500   ,500,500,500
BEGIN DESCRIPTION:
STEWARTS CREEK 79.0
END DESCRIPTION:
XS GIS Cut Line= 3
      3839687.27     10115163.77       3838907.6      10114239.1
      3838204.59     10113611.64
#Sta/Elev= 30
  3790.5  192.56  3960.9  190.97  4316.6  185.09  4445.2  183.48  4459.5  182.09
  4657.3  182.78  4757.3   179.6  4785.9   176.8  4792.4  177.61  4848.5  174.17
  4892.5  172.13  4899.1  174.12  4919.9  174.48  4941.9  172.25  4956.2  173.07
  4970.5  171.85    4984  168.42  5007.8  168.42    5013   169.5 5018.43173.1794
  5033.9  171.61  5054.8   177.1  5097.4  177.03  5104.9  178.35  5196.9  175.71
  5260.4  177.62    5341  176.41  5374.1  175.82  5590.5  181.78  5942.3  192.08
#Mann= 8 ,-1 , 0
  3790.5     .17       0  3960.9     .11       0  4316.6     .17       0
  4848.5     .15       0  4956.2     .04       0 5018.43     .15       0
    5341     .17       0  5590.5     .11       0
#XS Ineff= 2 , 0
       0  4636.4  183.07               0
Permanent Ineff=
       F       F
Bank Sta=4956.2,5018.43
XS Rating Curve= 0 ,0
Exp/Cntr=0.3,0.1

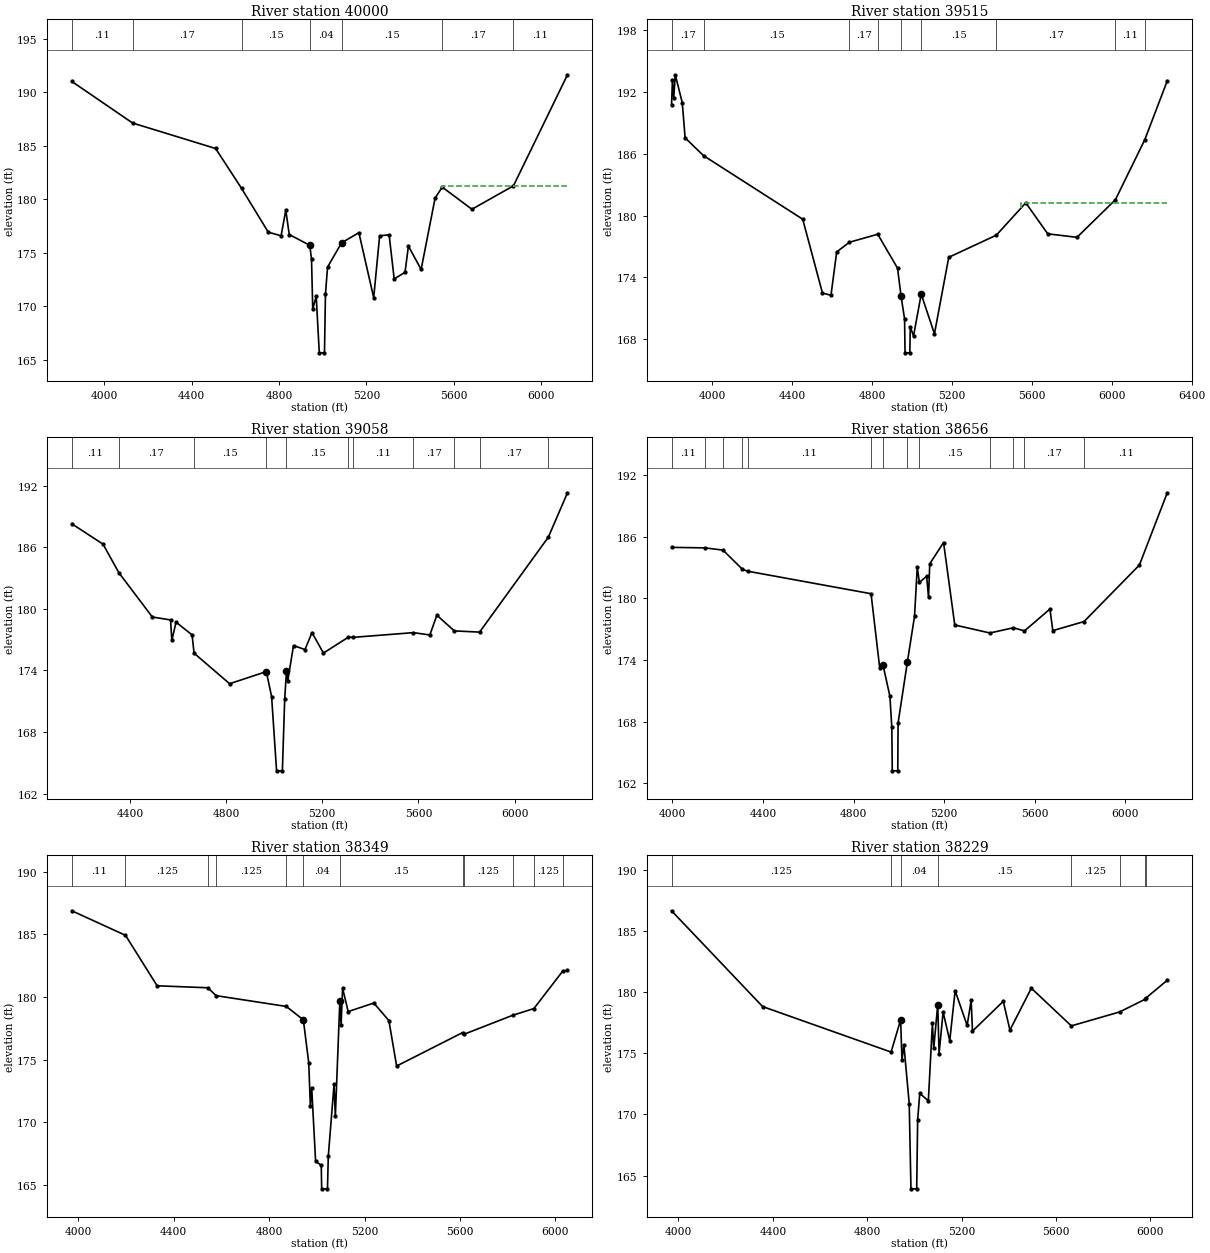
Type RM Length L Ch R = 1 ,40000   ,485,485,485
BEGIN DESCRIPTION:
STEWARTS CREEK 78.0
END DESCRIPTION:
XS GIS Cut Line= 3
      3839833.08     10115045.68      3839258.29     10114049.86
      3838298.39     10113469.32
#Sta/Elev= 30
  3850.2  191.03    4129  187.14  4509.3  184.76  4628.4  181.03  4750.6  176.94
  4809.5   176.6    4831     179  4846.8  176.72  4940.9  175.71  4948.8  174.44
  4954.5  169.74  4970.3  170.95  4984.5  165.66  5008.3  165.66  5012.7  171.14
  5022.3  173.67  5086.4  175.94  5165.9  176.89  5233.8  170.82    5261   176.6
  5304.4  176.69  5327.7  172.57  5377.4  173.19  5392.9  175.64  5451.1  173.45
  5515.1  180.12  5547.9  181.15  5683.9  179.08  5874.2  181.27  6121.8  191.65
#Mann= 7 ,-1 , 0
  3850.2     .11       0    4129     .17       0  4628.4     .15       0
  4940.9     .04       0  5086.4     .15       0  5547.9     .17       0
  5874.2     .11       0
#XS Ineff= 2 , 0
       0                  5546.2       0  181.22
Permanent Ineff=
       F       F
Bank Sta=4940.9,5086.4
XS Rating Curve= 0 ,0
Exp/Cntr=0.3,0.1

Type RM Length L Ch R = 1 ,39515   ,457,457,457
BEGIN DESCRIPTION:
STEWARTS CREEK 77.0
END DESCRIPTION:
XS GIS Cut Line= 3
      3840433.76     10114471.02      3839531.14      10113679.4
      3838304.92      10113313.6
#Sta/Elev= 30
  3797.4  190.72  3801.8  193.19  3808.4  191.45    3816  193.69  3851.1  190.97
  3865.3  187.56  3957.8  185.83  4453.7  179.66  4552.4  172.49  4595.1  172.27
  4623.6  176.48  4686.9  177.42    4829   178.2  4928.2   174.9 4945.51172.2081
  4963.3  169.97  4965.6  166.68  4989.5  166.68  4991.8  169.19  5008.1  168.32
  5046.5  172.38  5112.8  168.53  5184.3  175.96  5422.4  178.11  5569.7  181.25
  5679.7  178.24  5825.8   177.9  6018.1  181.55  6165.1  187.38  6277.6   193.1
#Mann= 9 ,-1 , 0
  3797.4     .17       0  3957.8     .15       0  4686.9     .17       0
    4829     .15       0 4945.51     .04       0  5046.5     .15       0
  5422.4     .17       0  6018.1     .11       0  6165.1    .125       0
#XS Ineff= 2 , 0
       0                  5544.1       0  181.25
Permanent Ineff=
       F       F
Bank Sta=4945.51,5046.5
XS Rating Curve= 0 ,0
Exp/Cntr=0.3,0.1

Type RM Length L Ch R = 1 ,39058   ,402,402,402
BEGIN DESCRIPTION:
STEWARTS CREEK 76.0
END DESCRIPTION:
XS GIS Cut Line= 3
      3840471.97     10113660.27      3839708.06     10113306.61
      3838582.89     10112836.07
#Sta/Elev= 30
  4158.2   188.3  4288.3  186.31  4354.3  183.52  4493.3  179.21  4568.9  178.93
  4574.4  176.94  4591.8  178.71  4658.6  177.47  4666.7  175.69  4814.6  172.71
  4967.2  173.89  4989.2  171.46  5009.9  164.22    5034  164.22  5043.6   171.2
  5051.1  173.94  5056.5     173  5080.3  176.43  5127.9  176.04  5157.2  177.69
  5204.8   175.7  5308.8  177.25  5327.7  177.23  5579.1  177.69  5647.3  177.46
  5676.5  179.39  5748.8  177.86  5854.1  177.74  6139.9  186.99  6219.6  191.32
#Mann= 11 ,-1 , 0
  4158.2     .11       0  4354.3     .17       0  4666.7     .15       0
  4967.2     .04       0  5051.1     .15       0  5308.8     .15       0
  5327.7     .11       0  5579.1     .17       0  5748.8     .11       0
  5854.1     .17       0  6139.9     .11       0
Bank Sta=4967.2,5051.1
XS Rating Curve= 0 ,0
Exp/Cntr=0.3,0.1

Type RM Length L Ch R = 1 ,38656   ,307,307,307
BEGIN DESCRIPTION:
STEWARTS CREEK 75.0
END DESCRIPTION:
XS GIS Cut Line= 3
      3840784.23      10113474.5      3839892.98      10113013.1
      3838782.55     10112597.96
#Sta/Elev= 30
  3996.4  184.96  4144.2  184.91  4223.7  184.69  4309.3  182.83  4332.6  182.64
  4877.4  180.45  4915.7  173.22  4930.4  173.49  4960.7  170.47  4969.1  167.44
  4971.1  163.22  4995.4  163.22  4996.8  167.87  5037.5  173.76  5069.5  178.27
  5081.4  183.03  5090.8  181.56  5122.9  182.14  5131.3  180.09  5136.6  183.36
  5197.6  185.43  5247.1  177.41  5402.4  176.63  5506.2  177.14  5554.8  176.83
  5667.4  178.96  5680.1  176.86  5817.8  177.74  6062.4  183.24  6185.5  190.27
#Mann= 13 ,-1 , 0
  3996.4     .11       0  4144.2     .15       0  4223.7     .11       0
  4309.3     .15       0  4332.6     .11       0  4877.4     .15       0
  4930.4     .04       0  5037.5    .125       0  5090.8     .15       0
  5402.4    .125       0  5506.2     .11       0  5554.8     .17       0
  5817.8     .11       0
#XS Ineff= 2 , 0
       0                  5081.4       0  183.03
Permanent Ineff=
       F       F
Bank Sta=4930.4,5037.5
XS Rating Curve= 0 ,0
Exp/Cntr=0.3,0.1

Type RM Length L Ch R = 1 ,38349   ,120,120,120
BEGIN DESCRIPTION:
Mapping XS c63de7b3
END DESCRIPTION:
XS GIS Cut Line= 3
        3840904.     10113216.67      3839998.14     10112733.85
       3839023.8     10112341.68
#Sta/Elev= 30
  3973.5  186.88  4198.6  184.92  4331.1  180.89  4543.3  180.73  4578.3   180.1
  4872.1  179.24  4943.7  178.17  4966.3  174.74    4973  171.32  4978.7  172.75
    4995  166.89  5018.7  166.54  5020.5  164.67  5044.8  164.67  5048.2  167.27
  5072.4  173.03  5077.8  170.45  5096.6  179.66  5101.9  177.78  5108.1   180.7
  5131.5  178.83    5239  179.51  5302.1  178.11  5334.5  174.48  5610.9  177.15
  5618.8  177.03  5820.4  178.53  5909.6  179.07  6029.9  182.05  6050.3  182.11
#Mann= 12 ,-1 , 0
  3973.5     .11       0  4198.6    .125       0  4543.3     .11       0
  4578.3    .125       0  4872.1     .11       0  4943.7     .04       0
  5096.6     .15       0  5610.9     .11       0  5618.8    .125       0
  5820.4     .11       0  5909.6    .125       0  6029.9     .11       0
Bank Sta=4943.7,5096.6
XS Rating Curve= 0 ,0
Exp/Cntr=0.3,0.1

Type RM Length L Ch R = 1 ,38229   ,21,21,21
BEGIN DESCRIPTION:
STEWARTS CREEK 74.0
END DESCRIPTION:
XS GIS Cut Line= 3
      3840940.48     10113096.89      3840028.18     10112620.47
      3839061.86     10112158.21
#Sta/Elev= 30
  3970.8  186.65  4356.6  178.82    4901   175.1  4941.5  177.74  4947.1  174.43
  4955.2  175.69  4977.8  170.89  4985.2  163.92  5009.5  163.92  5013.6  169.58
  5022.5  171.72  5058.9  171.12  5076.1  177.46  5081.6   175.4  5098.7  178.98
  5104.3  174.98  5121.4  178.37  5149.6  176.03  5172.3  180.11  5223.2  177.28
  5240.3  179.33  5245.9  176.81  5376.3  179.25  5404.6   176.9  5495.2  180.32
  5664.8  177.24  5869.3  178.38  5976.7  179.41    5981  179.52  6071.2  180.97
#Mann= 8 ,-1 , 0
  3970.8    .125       0    4901     .11       0  4941.5     .04       0
  5098.7     .15       0  5664.8    .125       0  5869.3     .15       0
  5976.7    .125       0    5981     .11       0
Bank Sta=4941.5,5098.7
XS Rating Curve= 0 ,0
Exp/Cntr=0.3,0.1

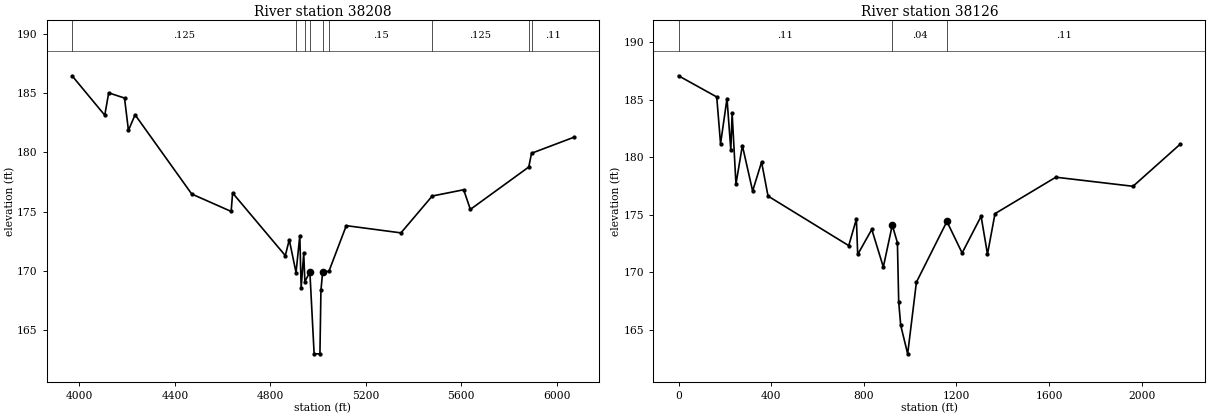
Type RM Length L Ch R = 1 ,38208   ,82,82,82
BEGIN DESCRIPTION:
STEWARTS CREEK 73.0
END DESCRIPTION:
XS GIS Cut Line= 3
      3840948.88       10113077.      3840034.66     10112600.59
      3839076.56     10112121.31
#Sta/Elev= 30
  3969.1  186.46  4106.1  183.13  4122.5  185.02  4188.8  184.58  4205.3  181.85
    4233  183.17  4470.4  176.48  4635.6  175.01  4641.6  176.57  4862.5  171.28
    4879  172.62  4907.4  169.85  4923.2  172.97  4928.8  168.55  4939.6  171.46
  4944.4  169.09 4965.41169.8817  4983.2  162.99  5007.5  162.99  5011.7  168.34
  5018.8  169.88  5045.2  169.96  5117.9  173.81    5347   173.2  5477.9  176.31
  5609.7  176.84  5637.7  175.18  5882.4  178.76    5894  179.92  6071.3  181.27
#Mann= 9 ,-1 , 0
  3969.1    .125       0  4907.4     .11       0  4944.4    .125       0
 4965.41     .04       0  5018.8    .125       0  5045.2     .15       0
  5477.9    .125       0  5882.4     .15       0    5894     .11       0
Bank Sta=4965.41,5018.8
XS Rating Curve= 0 ,0
Exp/Cntr=0.3,0.1

Type RM Length L Ch R = 1 ,38126   ,502,502,502
XS GIS Cut Line= 3
      3840980.17      10113001.5      3840092.33     10112542.34
      3839064.47     10111988.37
#Sta/Elev= 30
       0  187.09     165  185.25   181.5  181.17   209.3  185.11   225.8  180.64
   231.5  183.82     248  177.67   275.7  181.02     320  177.07   358.7  179.59
   386.5  176.63   735.1  172.32   768.1  174.63   773.8  171.55   834.6  173.73
   884.5  170.46   923.1   174.1   945.3  172.58   950.9  167.41   959.6  165.39
   989.6  162.91  1027.4  169.14  1159.1  174.42  1224.8  171.68  1306.8  174.87
  1334.3  171.58  1366.8   175.1  1629.6  178.27  1962.9  177.48  2167.2  181.15
#Mann= 3 , 0 , 0
       0     .11       0   923.1     .04       0  1159.1     .11       0
Bank Sta=923.1,1159.1
XS Rating Curve= 0 ,0
Exp/Cntr=0.3,0.1