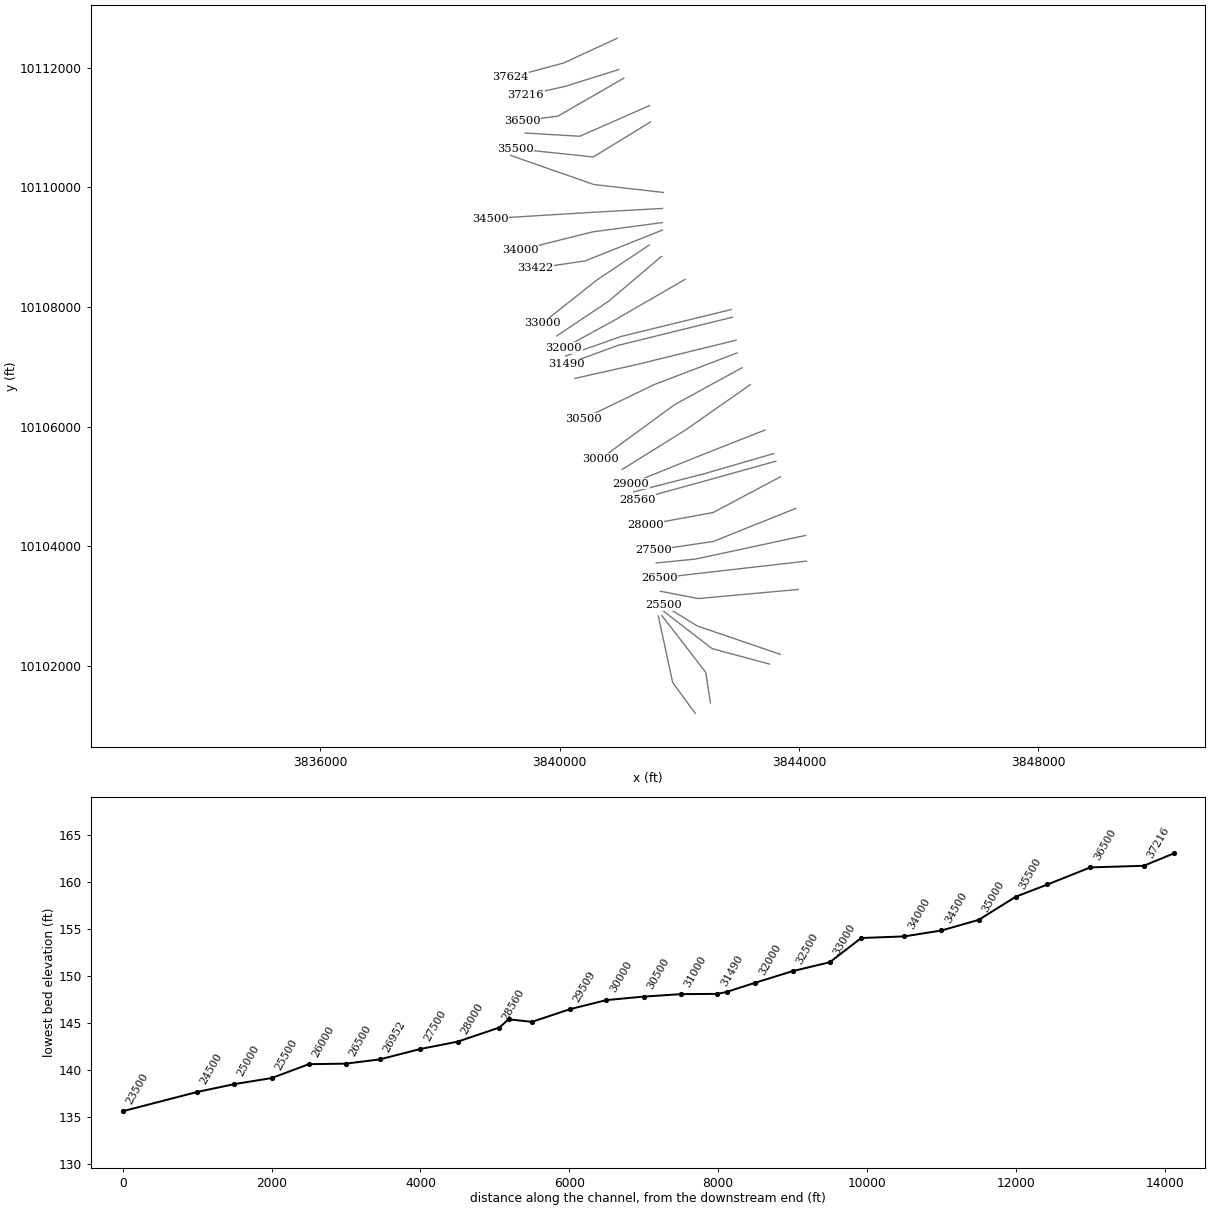
HEC-RAS study STEWARTS CREEK.prj: STEWARTS CREEK Base Level Engineering

--- STEWARTS CREEK.g01 (geometry) --- (continued)

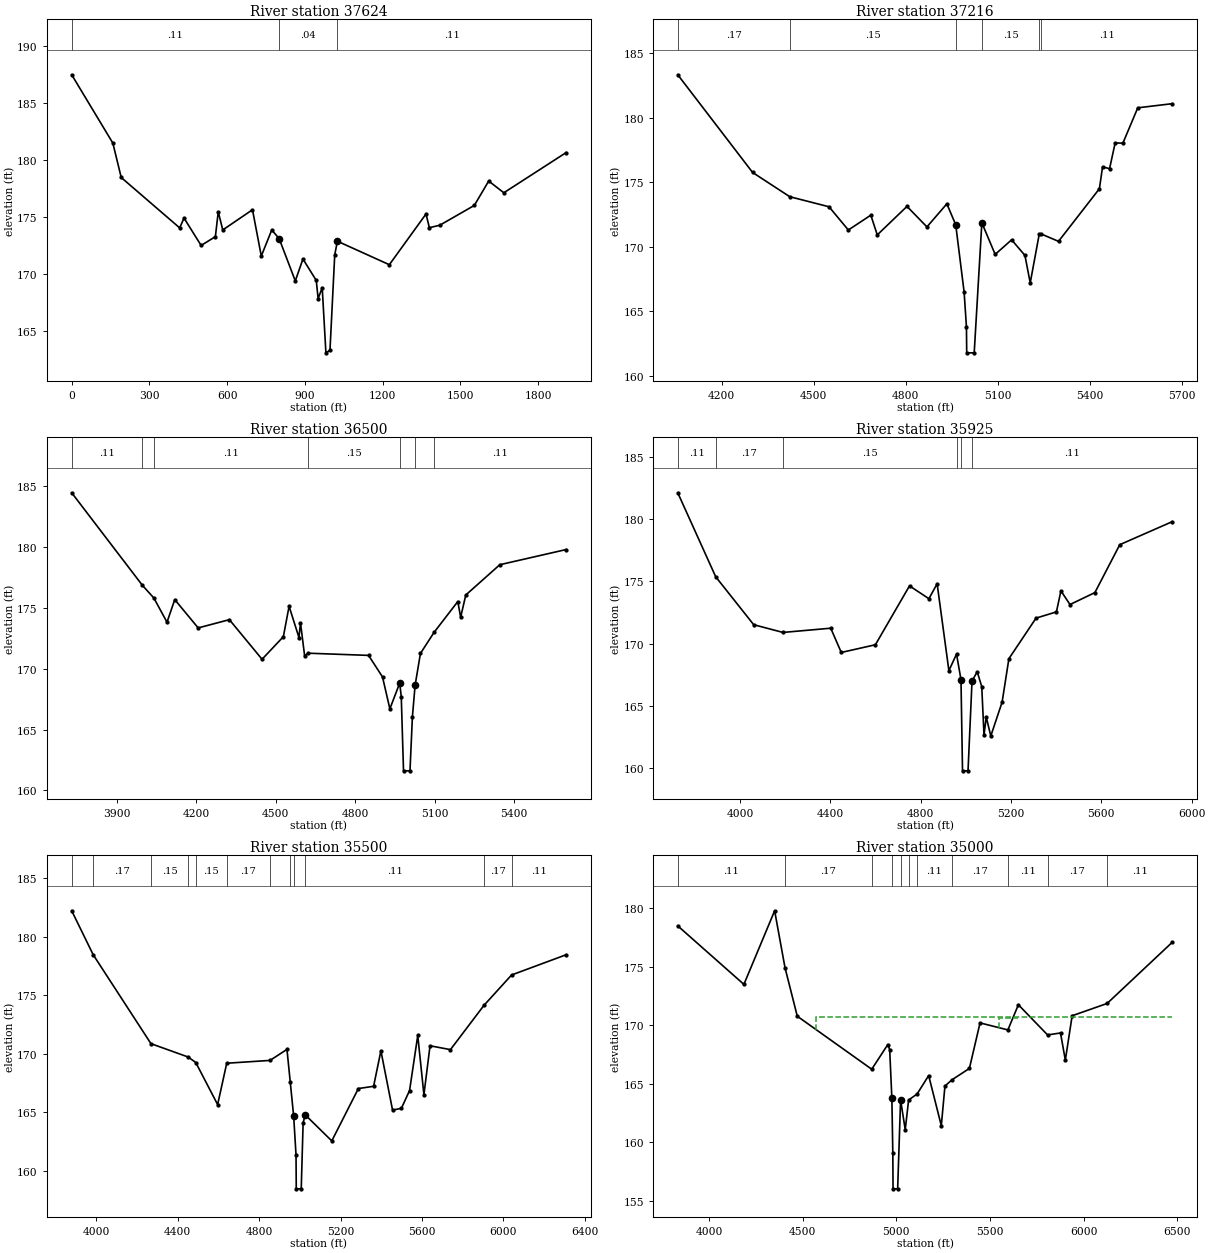
Type RM Length L Ch R = 1 ,37624   ,407,407,407
XS GIS Cut Line= 3
       3840961.4     10112490.51      3840068.45     10112078.81
      3839175.49     10111837.75
#Sta/Elev= 30
       0  187.48   158.7  181.49   191.1  178.47   416.7  174.05   433.4  174.91
   499.4  172.51   554.4  173.28   565.5  175.46   582.9  173.87   697.6  175.64
   731.6  171.58     772  173.87   800.5  173.11   862.8   169.4   892.3  171.32
   943.7  169.44   950.9  167.85   966.7   168.8   980.9  163.09   996.6  163.31
    1015   171.7  1025.3  172.88  1225.7  170.82  1367.2  175.27  1380.1  174.07
    1420  174.28  1553.6  176.02  1609.1  178.16  1667.5  177.13  1908.2  180.66
#Mann= 3 , 0 , 0
       0     .11       0   800.5     .04       0  1025.3     .11       0
Bank Sta=800.5,1025.3
XS Rating Curve= 0 ,0
Exp/Cntr=0.3,0.1

Type RM Length L Ch R = 1 ,37216   ,716,716,716
BEGIN DESCRIPTION:
STEWARTS CREEK 72.0
END DESCRIPTION:
XS GIS Cut Line= 3
      3840988.28     10111967.93      3840088.27     10111686.78
       3839436.2     10111540.85
#Sta/Elev= 30
  4057.1  183.32  4300.9  175.75    4422  173.87  4549.9  173.09  4612.8  171.29
  4686.1  172.44  4707.1  170.91  4803.9  173.12  4868.9  171.53  4933.8  173.32
 4962.67171.6952    4990  166.49  4997.6  163.79  4998.5  161.77  5022.9  161.77
  5047.8  171.85  5091.2   169.4  5144.8  170.53  5188.2  169.32  5205.4  167.19
    5235     171  5240.3  170.99  5297.6  170.41  5430.8  174.49  5441.1  176.19
  5463.9  176.04  5482.1  178.04  5507.3  178.02  5555.8  180.76  5668.2  181.08
#Mann= 6 ,-1 , 0
  4057.1     .17       0    4422     .15       0 4962.67     .04       0
  5047.8     .15       0    5235     .17       0  5240.3     .11       0
Bank Sta=4962.67,5047.8
XS Rating Curve= 0 ,0
Exp/Cntr=0.3,0.1

Type RM Length L Ch R = 1 ,36500   ,575,575,575
BEGIN DESCRIPTION:
STEWARTS CREEK 71.0
END DESCRIPTION:
XS GIS Cut Line= 3
      3841075.15     10111825.59      3839974.26     10111191.18
      3839381.78     10111113.91
#Sta/Elev= 30
  3729.4  184.48  3996.6  176.86  4039.8  175.82  4089.4  173.83  4118.7  175.69
  4207.2  173.36    4325  174.04  4448.5  170.78    4529  172.64  4550.6  175.14
  4587.9  172.57  4593.7  173.78  4609.4  171.05  4622.4  171.28  4850.8   171.1
  4903.5  169.33  4931.3   166.7  4968.6  168.83  4974.4  167.68  4982.9   161.6
  5007.3   161.6  5016.5  166.06  5026.6  168.63  5046.8  171.26  5098.5     173
    5188  175.53  5198.7  174.24  5218.2  176.07  5346.6  178.56  5597.5  179.81
#Mann= 7 ,-1 , 0
  3729.4     .11       0  3996.6     .17       0  4039.8     .11       0
  4622.4     .15       0  4968.6     .04       0  5026.6     .15       0
  5098.5     .11       0
#XS Ineff= 2 , 0
       0  4550.6  175.14               0
Permanent Ineff=
       F       F
Bank Sta=4968.6,5026.6
XS Rating Curve= 0 ,0
Exp/Cntr=0.3,0.1

Type RM Length L Ch R = 1 ,35925   ,425,425,425
BEGIN DESCRIPTION:
STEWARTS CREEK 70.0
END DESCRIPTION:
XS GIS Cut Line= 3
      3841505.68     10111367.25      3840338.41      10110854.3
      3839425.85     10110908.91
#Sta/Elev= 30
    3725  182.12    3893  175.37  4061.2  171.52  4190.7   170.9  4402.2  171.24
  4448.9  169.29  4599.9  169.91  4750.9  174.64  4836.8  173.61  4873.2  174.81
  4925.3  167.83  4959.1  169.16  4978.8  167.11  4985.6  159.78    5010  159.78
  5027.7     167  5050.7  167.74  5070.7  166.55  5080.7  162.67  5090.7  164.09
  5110.8  162.58  5160.9   165.3  5190.9  168.79  5311.1  172.05  5401.3  172.55
  5421.3  174.24  5461.4  173.14  5571.6   174.1  5681.8  177.95  5914.2   179.8
#Mann= 6 ,-1 , 0
    3725     .11       0    3893     .17       0  4190.7     .15       0
  4959.1     .11       0  4978.8     .04       0  5027.7     .11       0
#XS Ineff= 2 , 0
       0  4873.2  174.81               0
Permanent Ineff=
       F       F
Bank Sta=4978.8,5027.7
XS Rating Curve= 0 ,0
Exp/Cntr=0.3,0.1

Type RM Length L Ch R = 1 ,35500   ,500,500,500
BEGIN DESCRIPTION:
STEWARTS CREEK 69.0
END DESCRIPTION:
XS GIS Cut Line= 3
      3841519.58     10111092.95      3840564.08     10110508.25
      3839262.75     10110645.01
#Sta/Elev= 30
  3879.8  182.21  3985.3  178.46    4269  170.87  4451.7  169.73  4489.2  169.26
  4596.5  165.67  4641.2   169.2  4853.8  169.44    4937  170.38  4953.4  167.56
 4969.88164.6881  4981.5  161.38  4982.7  158.48  5007.1  158.48  5016.3  164.09
  5026.4   164.8  5157.1  162.57  5287.8  167.04  5362.5  167.23  5398.4  170.26
  5455.6   165.2    5499  165.35  5539.2  166.87  5579.4  171.57  5609.6  166.51
  5639.7  170.69  5739.9  170.36  5904.6  174.14  6040.2  176.73  6308.5  178.46
#Mann= 12 ,-1 , 0
  3879.8     .11       0  3985.3     .17       0    4269     .15       0
  4451.7     .17       0  4489.2     .15       0  4641.2     .17       0
  4853.8     .15       0  4953.4     .11       0 4969.88     .04       0
  5026.4     .11       0  5904.6     .17       0  6040.2     .11       0
#XS Ineff= 2 , 0
       0                  5579.4       0  171.57
Permanent Ineff=
       F       F
Bank Sta=4969.88,5026.4
XS Rating Curve= 0 ,0
Exp/Cntr=0.3,0.1

Type RM Length L Ch R = 1 ,35000   ,500,500,500
BEGIN DESCRIPTION:
STEWARTS CREEK 68.0
END DESCRIPTION:
XS GIS Cut Line= 3
       3841731.4     10109915.85      3840572.71     10110048.01
      3839182.79      10110533.9
#Sta/Elev= 30
  3833.8  178.48  4186.7  173.48  4350.7  179.77    4406  174.91  4471.5  170.76
  4868.8  166.23  4954.6  168.34  4964.6   167.9 4976.23163.7314  4981.3  159.03
  4982.5  156.01  5007.1  156.01  5022.7  163.61  5047.5  161.07  5065.6   163.6
  5110.7  164.11  5172.6  165.69    5240  161.41  5259.4  164.79  5296.2  165.32
  5389.9   166.3  5446.7  170.19  5595.2  169.59  5651.3  171.74  5807.1  169.16
    5876  169.33  5901.8  167.01  5938.1   170.8  6124.8  171.85  6472.4  177.08
#Mann= 11 ,-1 , 0
  3833.8     .11       0    4406     .17       0  4868.8     .15       0
 4976.23     .04       0  5022.7     .15       0  5065.6     .17       0
  5110.7     .11       0  5296.2     .17       0  5595.2     .11       0
  5807.1     .17       0  6124.8     .11       0
#XS Ineff= 3 ,-1
  4572.1  4454.9  170.73  5545.4  5651.3  170.64  5651.3  6150.1  171.74
Permanent Ineff=
       F       F       F
Bank Sta=4976.23,5022.7
XS Rating Curve= 0 ,0
Exp/Cntr=0.3,0.1

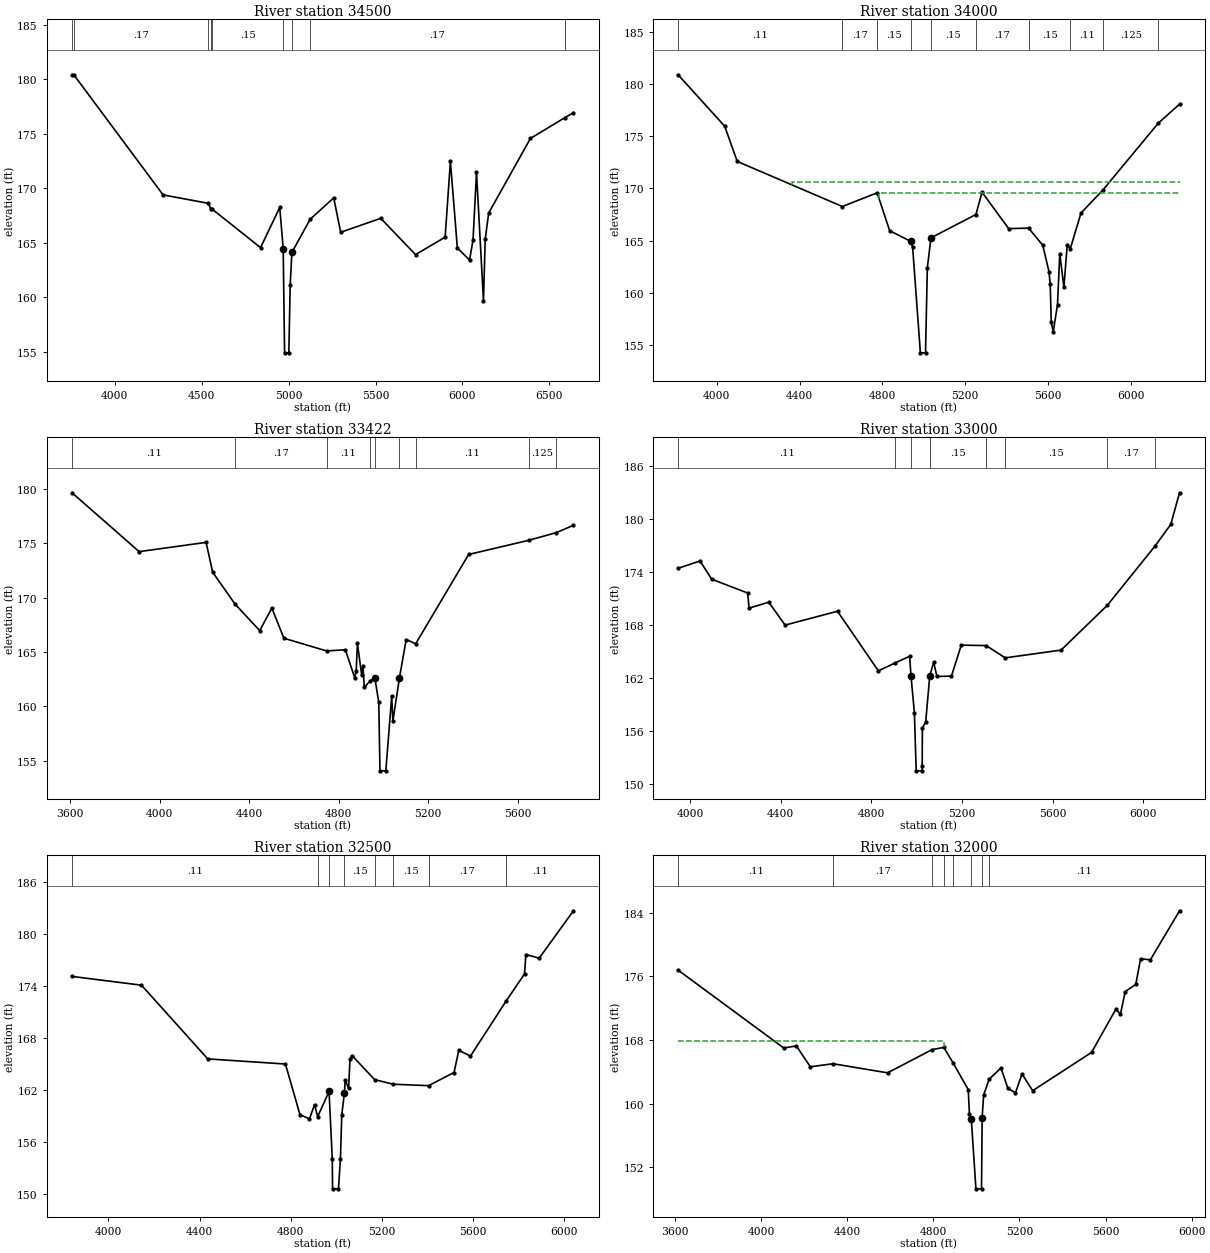
Type RM Length L Ch R = 1 ,34500   ,500,500,500
BEGIN DESCRIPTION:
STEWARTS CREEK 67.0
END DESCRIPTION:
XS GIS Cut Line= 3
      3841720.92     10109648.49      3840476.55     10109579.13
      3838840.94     10109478.47
#Sta/Elev= 30
  3753.7  180.39  3763.9  180.41  4277.6  169.38  4537.3  168.61  4552.7  168.09
    4561  168.06  4838.4  164.54  4948.6  168.23  4968.6  164.44  4976.4  154.88
    5001  154.88  5008.7  161.09  5018.7  164.11  5123.9  167.15  5259.2  169.11
  5299.3  165.95  5529.7  167.23  5730.1   163.9  5900.4   165.5  5930.5  172.47
  5970.5  164.51  6040.7   163.4  6060.7  165.24  6080.7  171.45  6120.8  159.66
  6130.8  165.31  6150.9  167.72  6391.3  174.57  6587.7  176.46  6638.7  176.93
#Mann= 9 ,-1 , 0
  3753.7     .11       0  3763.9     .17       0  4537.3     .15       0
  4552.7     .17       0    4561     .15       0  4968.6     .06       0
  5018.7     .15       0  5123.9     .17       0  6587.7     .11       0
#XS Ineff= 2 , 0
       0                  5930.5       0  172.47
Permanent Ineff=
       F       F
Bank Sta=4968.6,5018.7
XS Rating Curve= 0 ,0
Exp/Cntr=0.3,0.1

Type RM Length L Ch R = 1 ,34000   ,578,578,578
BEGIN DESCRIPTION:
STEWARTS CREEK 66.0
END DESCRIPTION:
XS GIS Cut Line= 3
      3841720.94     10109412.38      3840544.61     10109255.04
      3839345.92     10108954.04
#Sta/Elev= 30
  3813.2  180.89  4038.3  175.96  4098.8  172.59  4606.7  168.27  4774.8  169.58
  4835.3  165.95  4936.2  164.94  4946.3  164.36  4983.7  154.25  5008.5  154.25
  5017.3  162.39  5034.8  165.27  5251.9   167.5  5281.7  169.64  5410.3  166.15
  5506.6   166.2  5574.9  164.56    5605  162.04  5610.9  160.81  5616.1  157.17
  5625.6  156.27  5646.2  158.87  5657.2  163.75  5677.1  160.52  5693.2   164.6
  5708.2  164.24  5759.6  167.64  5865.6  169.85  6133.8  176.27  6235.9  178.07
#Mann= 10 ,-1 , 0
  3813.2     .11       0  4606.7     .17       0  4774.8     .15       0
  4936.2     .06       0  5034.8     .15       0  5251.9     .17       0
  5506.6     .15       0  5708.2     .11       0  5865.6    .125       0
  6133.8     .11       0
#XS Ineff= 3 ,-1
  4361.1  4280.4   170.6  4784.9  4361.1  169.59  5281.7    5873  169.64
Permanent Ineff=
       F       F       F
Bank Sta=4936.2,5034.8
XS Rating Curve= 0 ,0
Exp/Cntr=0.3,0.1

Type RM Length L Ch R = 1 ,33422   ,422,422,422
BEGIN DESCRIPTION:
STEWARTS CREEK 65.0
END DESCRIPTION:
XS GIS Cut Line= 3
      3841720.98     10109287.39      3840428.69     10108771.66
      3839588.13     10108648.09
#Sta/Elev= 30
  3608.6  179.64  3908.5  174.23  4207.6  175.08  4237.3  172.33  4337.3   169.4
  4447.5  166.97  4501.4  169.04  4555.3  166.27  4746.2   165.1  4830.1  165.21
  4871.7  162.65  4878.6  163.26    4884  165.79  4902.9  162.91  4908.3  163.76
  4914.8  161.75  4941.7  162.37  4962.2  162.58  4979.4  160.37  4984.8  154.08
  5010.8  154.08  5037.3  160.93  5042.4  158.64  5071.6   162.6  5101.9  166.15
  5144.4  165.76    5381  173.97  5649.3  175.27  5773.2  175.98  5849.6  176.65
#Mann= 9 ,-1 , 0
  3608.6     .11       0  4337.3     .17       0  4746.2     .11       0
  4941.7     .15       0  4962.2     .06       0  5071.6     .15       0
  5144.4     .11       0  5649.3    .125       0  5773.2     .11       0
Bank Sta=4962.2,5071.6
XS Rating Curve= 0 ,0
Exp/Cntr=0.3,0.1

Type RM Length L Ch R = 1 ,33000   ,500,500,500
BEGIN DESCRIPTION:
STEWARTS CREEK 64.0
END DESCRIPTION:
XS GIS Cut Line= 3
      3841498.04     10109036.75      3840623.31     10108451.78
      3839714.19     10107730.33
#Sta/Elev= 30
  3947.7  174.43  4044.5  175.26  4095.6   173.2  4254.7  171.63  4260.7  169.92
  4347.8  170.59  4419.9     168  4651.1  169.57  4831.3  162.82  4905.8  163.72
  4969.4  164.47  4975.4  162.24  4990.4  158.08  4998.3   151.5  5024.3   151.5
  5024.8     152  5025.7  156.39  5040.1  156.98 5058.11162.2471  5075.4  163.79
  5089.8  162.19  5153.9  162.22  5197.2  165.73  5307.6  165.68  5390.9  164.29
  5637.7  165.17  5841.8  170.24  6052.4  176.95  6121.6  179.39  6160.6  182.98
#Mann= 8 ,-1 , 0
  3947.7     .11       0  4905.8     .15       0  4975.4     .04       0
 5058.11     .15       0  5307.6     .17       0  5390.9     .15       0
  5841.8     .17       0  6052.4     .11       0
Bank Sta=4975.4,5058.11
XS Rating Curve= 0 ,0
Exp/Cntr=0.3,0.1

Type RM Length L Ch R = 1 ,32500   ,500,500,500
BEGIN DESCRIPTION:
STEWARTS CREEK 63.0
END DESCRIPTION:
XS GIS Cut Line= 3
      3841701.97     10108845.73      3840817.55     10108096.21
      3839952.87     10107517.63
#Sta/Elev= 30
  3840.7  175.07  4145.3  174.06    4436  165.55  4776.8  164.96  4840.6  159.11
  4882.3  158.63  4904.4  160.27  4918.2  158.88  4968.1   161.8  4982.3  154.01
  4983.5  150.55  5009.5  150.55    5018  153.99    5024   159.1 5035.61161.6523
    5039  163.11    5054  162.17    5060  165.51    5069  165.94  5167.7  163.16
  5249.4  162.63  5404.4  162.46  5516.4  163.98  5537.4  166.55  5588.4  165.87
  5744.4  172.21  5825.6  175.36  5831.6   177.6    5890  177.18  6040.4  182.65
#Mann= 8 ,-1 , 0
  3840.7     .11       0  4918.2     .15       0  4968.1     .04       0
 5035.61     .15       0  5167.7     .17       0  5249.4     .15       0
  5404.4     .17       0  5744.4     .11       0
Bank Sta=4968.1,5035.61
XS Rating Curve= 0 ,0
Exp/Cntr=0.3,0.1

Type RM Length L Ch R = 1 ,32000   ,385,385,385
BEGIN DESCRIPTION:
STEWARTS CREEK 62.0
END DESCRIPTION:
XS GIS Cut Line= 3
      3842096.76     10108462.04      3840897.33     10107768.72
      3840068.97      10107316.2
#Sta/Elev= 30
  3614.6  176.77  4105.2     167    4164  167.26  4228.6  164.64  4334.3  165.02
  4587.5  163.88  4794.8   166.8  4848.7  167.07  4891.8  165.13  4962.2  161.78
  4967.9  158.72  4976.3  158.14    4998  149.32    5024  149.32  5026.9158.1824
  5033.6  161.09  5059.6  163.09  5114.4  164.49  5146.7  161.92  5181.7  161.38
  5212.2  163.74  5261.5  161.64    5535  166.44  5647.7  171.85  5669.5  171.27
  5691.3  174.06  5740.7  174.99  5762.9  178.19  5808.4  178.07  5943.9  184.22
#Mann= 8 ,-1 , 0
  3614.6     .11       0  4334.3     .17       0  4794.8     .15       0
  4848.7     .17       0  4891.8     .15       0  4976.3     .04       0
  5026.9     .15       0  5059.6     .11       0
#XS Ineff= 2 , 0
         4848.01  167.85
Permanent Ineff=
       F       F
Bank Sta=4976.3,5026.9
XS Rating Curve= 0 ,0
Exp/Cntr=0.3,0.1

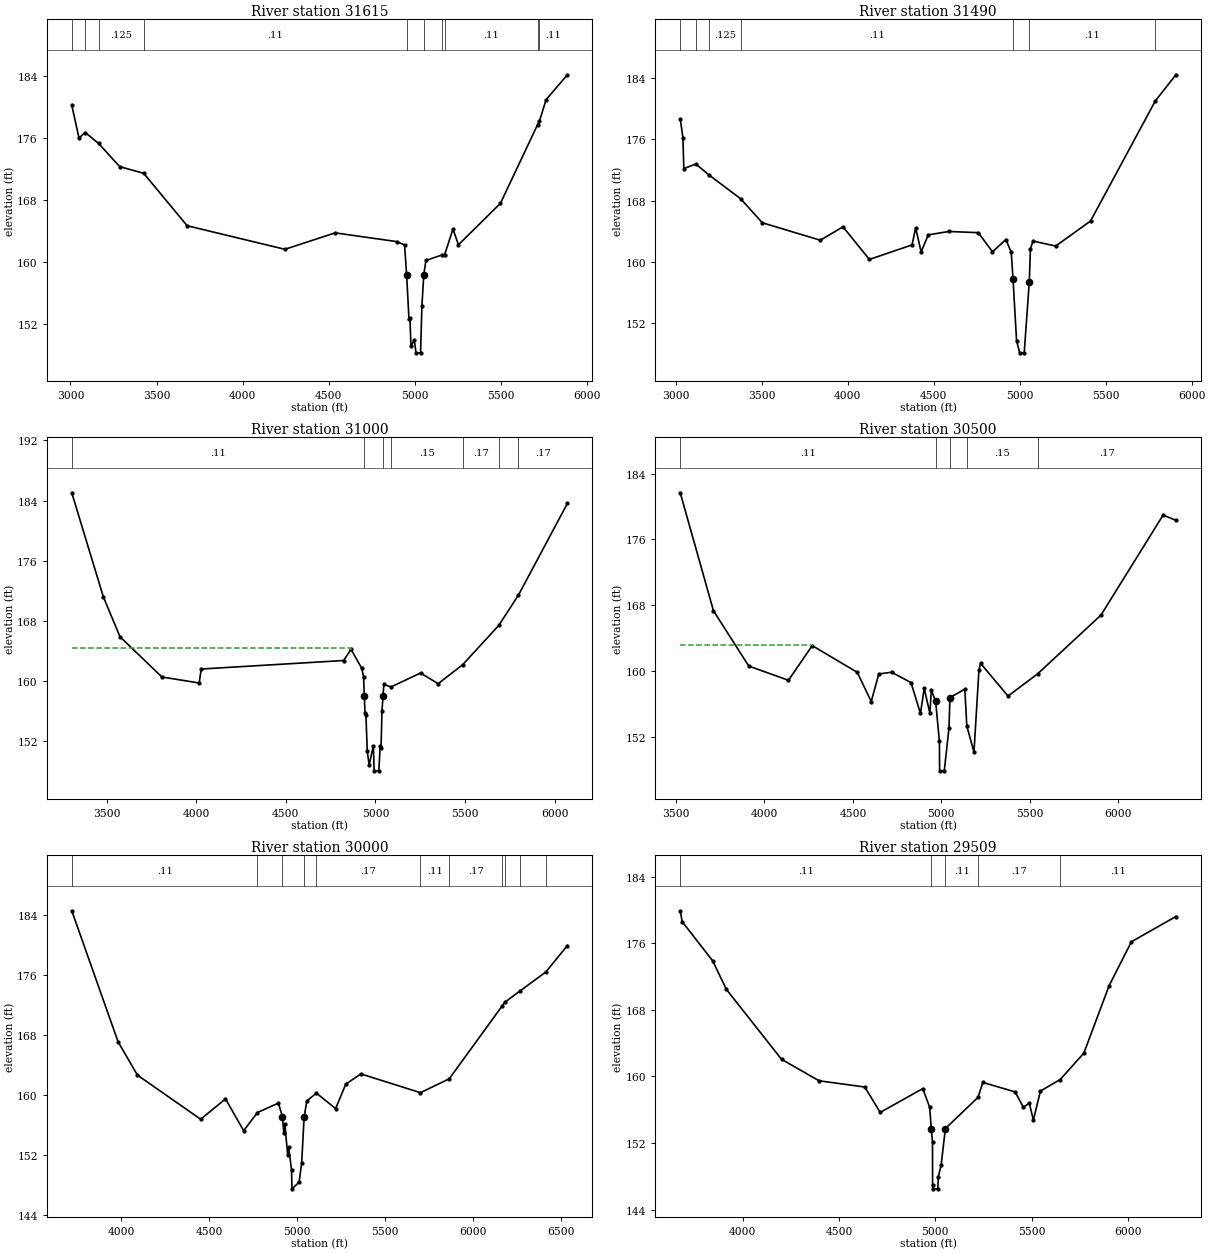
Type RM Length L Ch R = 1 ,31615   ,125,125,125
BEGIN DESCRIPTION:
Mapping XS 66d0620b
END DESCRIPTION:
XS GIS Cut Line= 3
      3842868.44     10107958.58      3841036.89     10107511.54
      3840101.14     10107182.29
#Sta/Elev= 30
    3008  180.26  3049.8  176.03  3086.3  176.73  3163.4  175.33  3286.5  172.33
  3425.3  171.48  3677.7  164.72  4245.3  161.68    4537   163.8  4895.5  162.67
    4940  162.24  4951.9158.3719  4965.6  152.66  4970.9  152.84  4977.1   149.2
  4996.6  149.97  5006.4  148.34  5032.7  148.34  5040.7  154.42  5051.3  158.38
  5063.8  160.24  5155.3  160.94  5171.8  160.94  5220.9  164.29  5252.7  162.26
  5496.6  167.61  5711.8  177.73  5722.2  178.16  5761.6  180.97  5885.3  184.17
#Mann= 10 ,-1 , 0
    3008    .125       0  3086.3     .15       0  3163.4    .125       0
  3425.3     .11       0  4951.9     .04       0  5051.3     .11       0
  5155.3     .15       0  5171.8     .11       0  5711.8    .125       0
  5722.2     .11       0
Bank Sta=4951.9,5051.3
XS Rating Curve= 0 ,0
Exp/Cntr=0.3,0.1

Type RM Length L Ch R = 1 ,31490   ,490,490,490
BEGIN DESCRIPTION:
STEWARTS CREEK 61.0
END DESCRIPTION:
XS GIS Cut Line= 3
      3842886.91     10107830.13      3840970.39     10107358.05
      3840117.81     10107044.54
#Sta/Elev= 30
  3026.2   178.7  3041.9  176.23  3047.1  172.19  3116.7   172.8  3192.5  171.38
  3377.8  168.25  3503.6  165.12  3840.8  162.84  3972.7  164.59  4126.2  160.33
  4374.4  162.23    4395  164.47    4427  161.31  4468.5  163.54  4587.8  163.98
    4759  163.83    4842  161.33  4919.9  162.93  4951.1  161.26  4961.4  157.74
    4982   149.7  5000.2  148.13  5026.5  148.13    5056  157.44  5062.5  161.71
  5077.3  162.73  5209.5  162.08  5412.2  165.35    5789  181.04  5908.4  184.45
#Mann= 7 ,-1 , 0
  3026.2    .125       0  3116.7     .11       0  3192.5    .125       0
  3377.8     .11       0  4961.4     .04       0    5056     .11       0
    5789    .125       0
Bank Sta=4961.4,5056
XS Rating Curve= 0 ,0
Exp/Cntr=0.3,0.1

Type RM Length L Ch R = 1 ,31000   ,500,500,500
BEGIN DESCRIPTION:
STEWARTS CREEK 60.0
END DESCRIPTION:
XS GIS Cut Line= 3
      3842949.23     10107446.44      3841303.58     10107042.93
      3840258.26     10106808.42
#Sta/Elev= 30
  3305.6  185.05  3482.1   171.2  3574.7  165.92  3808.7  160.57  4016.7  159.77
  4027.8  161.63  4822.3  162.76  4863.9  164.24  4923.5  161.73  4933.8  160.58
 4938.13 157.982  4941.9  155.72    4947  155.52  4954.4  150.77  4964.7  148.85
  4988.6  151.45  4992.7   148.1    5019   148.1  5026.3  151.34  5031.4   151.2
  5036.6  156.09 5042.35158.0439  5046.9  159.59  5086.9  159.25  5251.8   161.1
  5350.1  159.68  5487.9  162.23  5688.4  167.43  5797.7  171.44  6071.3  183.64
#Mann= 7 ,-1 , 0
  3305.6     .11       0 4938.13     .04       0 5042.35     .11       0
  5086.9     .15       0  5487.9     .17       0  5688.4     .11       0
  5797.7     .17       0
#XS Ineff= 2 , 0
         4861.36  164.38
Permanent Ineff=
       F       F
Bank Sta=4938.13,5042.35
XS Rating Curve= 0 ,0
Exp/Cntr=0.3,0.1

Type RM Length L Ch R = 1 ,30500   ,500,500,500
BEGIN DESCRIPTION:
STEWARTS CREEK 59.0
END DESCRIPTION:
XS GIS Cut Line= 3
      3842966.54     10107233.75      3841587.39     10106706.78
      3840392.86     10106131.36
#Sta/Elev= 30
  3523.6  181.68  3711.4  167.33  3911.1  160.59  4135.6  158.86  4269.9  163.08
  4524.4  159.83  4603.4  156.27  4646.2  159.63  4718.8  159.84  4828.2  158.58
  4881.7  154.83  4903.2  157.87  4935.3  154.83  4943.3  157.65  4967.4  156.34
  4988.8  151.46  4990.2  147.84  5016.5  147.84    5043  153.06  5048.6  156.76
  5132.7  157.78  5143.8  153.31  5184.3  150.11  5212.5  160.12  5221.5  160.93
  5376.9  156.94  5544.5  159.65  5902.2  166.79  6253.8  178.97  6325.9  178.33
#Mann= 5 ,-1 , 0
  3523.6     .11       0  4967.4     .04       0  5048.6     .11       0
  5143.8     .15       0  5544.5     .17       0
#XS Ineff= 2 , 0
         4270.45   163.2
Permanent Ineff=
       F       F
Bank Sta=4967.4,5048.6
XS Rating Curve= 0 ,0
Exp/Cntr=0.3,0.1

Type RM Length L Ch R = 1 ,30000   ,491,491,491
BEGIN DESCRIPTION:
STEWARTS CREEK 58.0
END DESCRIPTION:
XS GIS Cut Line= 3
      3843049.04     10106986.36      3841925.53     10106371.63
      3840683.57     10105462.91
#Sta/Elev= 30
  3719.3  184.54  3982.8  167.07    4093  162.63  4452.5  156.75  4593.8  159.46
  4697.2  155.22  4775.3  157.64  4894.8   158.9  4917.6  157.09  4925.7  154.97
  4931.4  156.11  4947.6  152.02  4953.3  153.01  4969.4  150.01  4972.3  147.47
  5012.6  148.36  5027.2  150.92 5040.92156.9952  5056.5  159.19  5110.9  160.23
  5220.2  158.17  5278.1  161.43  5363.8  162.79  5703.1  160.29  5866.6  162.14
  6169.5  171.91  6181.2  172.32  6271.5  173.89  6416.7  176.39  6538.9  179.91
#Mann= 11 ,-1 , 0
  3719.3     .11       0  4775.3     .15       0  4917.6     .04       0
 5040.92     .15       0  5110.9     .17       0  5703.1     .11       0
  5866.6     .17       0  6169.5    .125       0  6181.2     .17       0
  6271.5    .125       0  6416.7     .11       0
Bank Sta=4917.6,5040.92
XS Rating Curve= 0 ,0
Exp/Cntr=0.3,0.1

Type RM Length L Ch R = 1 ,29509   ,509,509,509
BEGIN DESCRIPTION:
STEWARTS CREEK 57.0
END DESCRIPTION:
XS GIS Cut Line= 3
      3843187.91     10106704.23      3842103.67     10105945.75
      3841044.73     10105285.53
#Sta/Elev= 30
  3676.8   179.9    3687  178.59  3844.8   173.9  3916.3  170.46  4202.3  162.06
  4396.9  159.48    4634  158.73  4714.2  155.68  4934.8  158.54  4970.6  156.31
  4979.3  153.69  4985.4   152.1  4985.9     147  4986.4   146.5    5013   146.5
  5015.5  147.97  5030.4  149.37  5052.1  153.74  5221.1  157.48  5246.8  159.28
  5414.3  158.14  5456.8  156.29  5487.5   156.8  5508.7  154.75  5545.3  158.25
  5647.9  159.63  5770.6  162.81  5901.6  170.91  6017.2  176.18  6247.9  179.21
#Mann= 5 ,-1 , 0
  3676.8     .11       0  4979.3     .04       0  5052.1     .11       0
  5221.1     .17       0  5647.9     .11       0
Bank Sta=4979.3,5052.1
XS Rating Curve= 0 ,0
Exp/Cntr=0.3,0.1

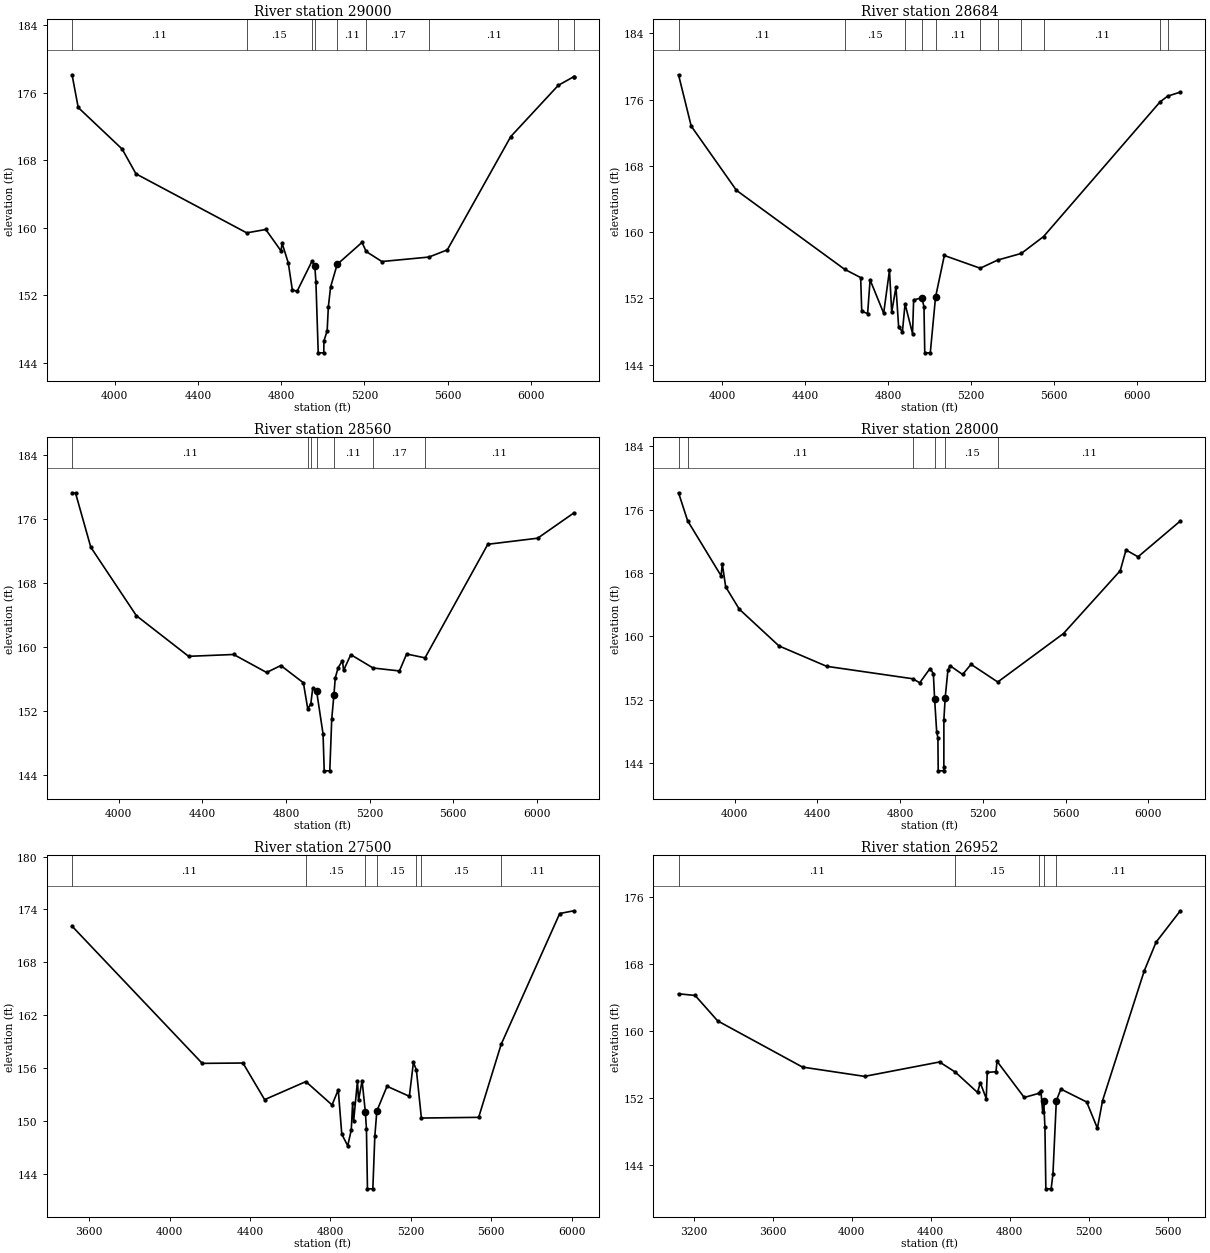
Type RM Length L Ch R = 1 ,29000   ,316,316,316
BEGIN DESCRIPTION:
STEWARTS CREEK 56.0
END DESCRIPTION:
XS GIS Cut Line= 3
       3843433.6     10105945.57      3842312.24     10105503.65
        3841194.     10105051.47
#Sta/Elev= 30
  3794.7  178.13  3824.2  174.25  4035.4  169.32  4101.8  166.38    4634  159.38
  4725.6  159.78  4798.8  157.24  4804.2  158.15  4833.9   155.8  4852.9  152.66
  4875.7  152.43  4947.4  156.01  4961.2  155.49  4966.6  153.55  4977.7  145.15
  5004.3  145.15  5005.1  146.56  5020.6  147.76  5026.3  150.59  5037.1  152.97
  5068.8  155.64  5188.1  158.25  5208.1  157.17  5283.4  155.98  5509.7  156.51
    5598  157.36    5903   170.8  6131.4  176.88  6204.9  177.89  6206.2  177.89
#Mann= 9 ,-1 , 0
  3794.7     .11       0    4634     .15       0  4947.4     .11       0
  4961.2     .04       0  5068.8     .11       0  5208.1     .17       0
  5509.7     .11       0  6131.4     .15       0  6204.9    .125       0
Bank Sta=4961.2,5068.8
XS Rating Curve= 0 ,0
Exp/Cntr=0.3,0.1

Type RM Length L Ch R = 1 ,28684   ,124,124,124
BEGIN DESCRIPTION:
Mapping XS 3c21ce2f
END DESCRIPTION:
XS GIS Cut Line= 3
      3843576.58      10105551.4      3842412.32     10105213.88
      3841238.69     10104912.54
#Sta/Elev= 30
  3787.8  179.01    3849  172.81  4067.6  165.05  4589.6  155.52  4667.6  154.51
  4672.8  150.43  4701.2  150.17  4713.1  154.23  4778.7  150.21  4806.8   155.4
  4817.5  150.32  4838.1  153.38  4851.1  148.52  4869.3  147.98    4882  151.34
  4918.2  147.74  4923.4   151.8    4963  152.08  4973.4  150.99  4977.2  145.42
  5003.9  145.42 5029.16152.1329  5071.7  157.18    5245  155.64  5329.6  156.63
  5443.7  157.43  5551.2  159.47  6113.3  175.72  6149.8  176.42  6211.7  176.92
#Mann= 11 ,-1 , 0
  3787.8     .11       0  4589.6     .15       0    4882     .11       0
    4963     .04       0 5029.16     .11       0    5245     .17       0
  5329.6     .11       0  5443.7     .17       0  5551.2     .11       0
  6113.3     .15       0  6149.8    .125       0
Bank Sta=4963,5029.16
XS Rating Curve= 0 ,0
Exp/Cntr=0.3,0.1

Type RM Length L Ch R = 1 ,28560   ,560,560,560
BEGIN DESCRIPTION:
STEWARTS CREEK 55.0
END DESCRIPTION:
XS GIS Cut Line= 3
      3843614.14     10105424.67      3842436.04     10105095.95
      3841300.96     10104784.63
#Sta/Elev= 30
  3776.9  179.31  3793.8  179.25  3866.5   172.5  4084.5  163.94  4334.3  158.86
  4549.8  159.09  4707.4  156.84  4775.6  157.71  4883.3  155.55  4904.4  152.26
    4919  152.95  4927.9  154.87  4946.2  154.56  4977.4  149.15  4982.9  144.54
  5009.6  144.54  5018.9  151.02  5029.2  153.98  5035.9  156.19    5050  157.46
  5070.3  158.32  5075.5   157.1    5110  159.07  5216.5   157.4  5342.7  157.03
  5377.1  159.15  5465.1  158.67  5765.5  172.87  6003.9  173.63    6177  176.79
#Mann= 7 ,-1 , 0
  3776.9     .11       0  4904.4     .15       0    4919     .11       0
  4946.2     .04       0  5029.2     .11       0  5216.5     .17       0
  5465.1     .11       0
Bank Sta=4946.2,5029.2
XS Rating Curve= 0 ,0
Exp/Cntr=0.3,0.1

Type RM Length L Ch R = 1 ,28000   ,500,500,500
BEGIN DESCRIPTION:
STEWARTS CREEK 54.0
END DESCRIPTION:
XS GIS Cut Line= 3
      3843691.54     10105164.51      3842568.38     10104567.42
      3841432.02     10104359.12
#Sta/Elev= 30
    3728  178.13  3772.1  174.59    3934  167.65  3939.7  169.16    3956  166.26
  4021.9  163.44  4214.1   158.8  4444.5  156.23  4861.1  154.66  4894.7  154.15
  4944.3  155.95  4960.6  155.32  4966.6  152.15  4976.9  147.91  4982.6  147.23
  4984.1  143.04  5010.9  143.04  5011.4  143.54  5011.6   149.5 5017.85 152.289
    5031  155.72  5041.2  156.31  5102.2   155.2  5142.9  156.48  5272.1  154.25
  5590.2  160.37  5864.7   168.3  5892.5  170.91  5950.7  170.05  6155.3  174.57
#Mann= 6 ,-1 , 0
    3728    .125       0  3772.1     .11       0  4861.1     .15       0
  4966.6     .04       0 5017.85     .15       0  5272.1     .11       0
Bank Sta=4966.6,5017.85
XS Rating Curve= 0 ,0
Exp/Cntr=0.3,0.1

Type RM Length L Ch R = 1 ,27500   ,548,548,548
BEGIN DESCRIPTION:
STEWARTS CREEK 53.0
END DESCRIPTION:
XS GIS Cut Line= 3
      3843946.75     10104635.86      3842568.46      10104083.1
      3841568.26     10103937.08
#Sta/Elev= 30
    3515  172.09  4162.4  156.51    4365  156.55  4472.7  152.39  4677.8  154.44
    4808  151.79    4839   153.5  4856.5  148.47    4886  147.15  4903.7  148.95
  4910.3  151.99  4915.6  149.99  4934.5  154.52  4939.8  152.31  4957.6  154.54
 4973.73150.9657  4979.1   149.1  4984.2  142.26    5011  142.26  5020.8  148.22
  5030.9   151.1  5081.5  153.91  5192.6  152.77  5212.8  156.62  5227.5  155.77
  5252.4   150.3  5537.3  150.38    5649  158.66  5940.5  173.53  6010.8  173.84
#Mann= 7 ,-1 , 0
    3515     .11       0  4677.8     .15       0 4973.73     .04       0
  5030.9     .15       0  5227.5     .11       0  5252.4     .15       0
    5649     .11       0
Bank Sta=4973.73,5030.9
XS Rating Curve= 0 ,0
Exp/Cntr=0.3,0.1

Type RM Length L Ch R = 1 ,26952   ,452,452,452
BEGIN DESCRIPTION:
STEWARTS CREEK 52.0
END DESCRIPTION:
XS GIS Cut Line= 3
      3844111.66     10104184.47      3842277.56     10103790.22
      3841616.03     10103724.41
#Sta/Elev= 30
    3124  164.46  3208.1  164.26  3322.2  161.22  3751.8   155.7  4065.9  154.59
  4445.5  156.31  4525.4   155.1  4637.8  152.67  4651.9  153.82  4682.1  151.94
  4687.2  155.06  4731.4  155.15  4736.5   156.4  4874.4  152.07  4948.3  152.56
  4958.8  152.89    4968  150.29  4973.1   151.6  4979.2  148.52  4983.9  141.15
  5010.7  141.15  5019.8  142.92    5037151.6908    5060  153.07  5190.6  151.53
  5244.9  148.39    5271  151.69  5482.1   167.2  5542.1  170.63  5664.8  174.38
#Mann= 5 ,-1 , 0
    3124     .11       0  4525.4     .15       0  4948.3     .11       0
  4973.1     .04       0    5037     .11       0
Bank Sta=4973.1,5037
XS Rating Curve= 0 ,0
Exp/Cntr=0.3,0.1

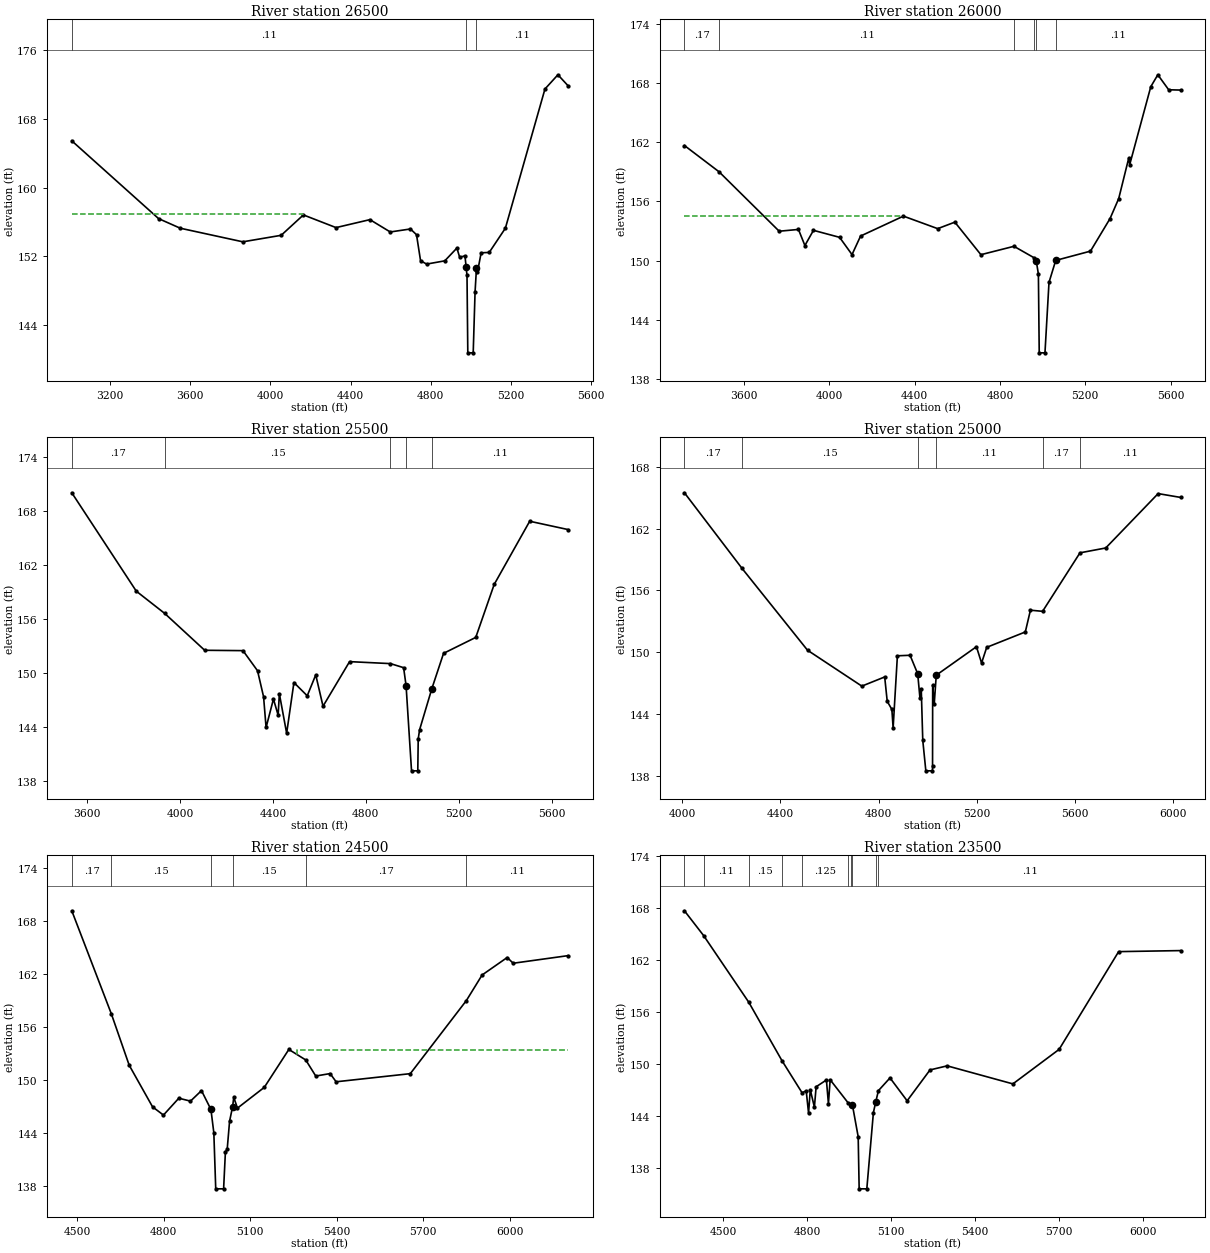
Type RM Length L Ch R = 1 ,26500   ,500,500,500
BEGIN DESCRIPTION:
STEWARTS CREEK 51.0
END DESCRIPTION:
XS GIS Cut Line= 3
      3844124.76     10103754.79      3842148.15     10103529.53
      3841668.11     10103472.67
#Sta/Elev= 30
  3010.6  165.45  3443.1  156.37    3551  155.25    3863  153.66  4054.1  154.42
  4164.9   156.8  4327.5  155.32  4496.4  156.25  4597.7  154.81  4698.4  155.16
  4728.6  154.49  4748.7  151.46  4778.9  151.06  4869.5  151.44  4929.8  152.93
  4943.6  151.86  4970.1  152.02  4975.9 150.705  4980.2  149.73  4984.2   140.7
  5011.1   140.7  5020.4  147.81  5027.5  150.62  5032.5  150.14  5050.7  152.38
  5090.9  152.42  5171.5  155.25  5368.7   171.5  5433.3  173.16  5483.4  171.89
#Mann= 3 , 0 , 0
  3010.6     .11       0  4975.9     .04       0  5027.5     .11       0
#XS Ineff= 2 , 0
         4164.77  156.93
Permanent Ineff=
       F       F
Bank Sta=4975.9,5027.5
XS Rating Curve= 0 ,0
Exp/Cntr=0.3,0.1

Type RM Length L Ch R = 1 ,26000   ,500,500,500
BEGIN DESCRIPTION:
STEWARTS CREEK 50.0
END DESCRIPTION:
XS GIS Cut Line= 3
       3843990.2      10103281.7       3842318.3     10103129.56
        3841683.     10103252.04
#Sta/Elev= 30
  3321.2  161.66  3483.8  158.99  3765.4  152.97  3855.7  153.15  3885.9  151.52
    3926  153.06  4048.5  152.35  4106.8   150.6  4146.9  152.48  4347.8   154.5
  4508.4  153.23  4588.8  153.89  4710.9  150.59  4865.9  151.44  4958.4   150.3
  4970.3  149.96  4980.4  148.63  4984.3  140.64  5011.2  140.64  5030.1  147.78
  5061.6  150.01  5224.5  150.95  5316.2  154.25  5356.9  156.28  5403.5  160.35
  5408.5  159.73  5507.2  167.62  5540.2  168.83  5591.1  167.31    5647  167.28
#Mann= 6 ,-1 , 0
  3321.2     .17       0  3483.8     .11       0  4865.9     .17       0
  4958.4     .11       0  4970.3     .04       0  5061.6     .11       0
#XS Ineff= 2 , 0
         4339.77  154.51
Permanent Ineff=
       F       F
Bank Sta=4970.3,5061.6
XS Rating Curve= 0 ,0
Exp/Cntr=0.3,0.1

Type RM Length L Ch R = 1 ,25500   ,500,500,500
BEGIN DESCRIPTION:
STEWARTS CREEK 49.0
END DESCRIPTION:
XS GIS Cut Line= 3
      3843689.03     10102197.47       3842302.4     10102671.46
      3841731.34     10103021.48
#Sta/Elev= 30
  3534.6  170.02  3812.2   159.1  3934.5  156.63  4106.5  152.54  4271.3   152.5
  4333.9  150.27  4359.9  147.38  4370.7  143.97  4402.4  147.13  4422.6  145.33
  4427.8  147.72  4459.2  143.33  4490.5  148.96  4547.8  147.49  4584.4  149.81
  4615.7  146.33    4730  151.28    4906  151.06  4962.5  150.61  4973.1  148.63
  4996.6  139.16  5023.5  139.16  5025.4  142.71  5031.3  143.72  5083.5  148.24
  5134.4   152.2    5273  153.97  5352.3  159.85  5505.1  166.86  5669.8  165.94
#Mann= 5 ,-1 , 0
  3534.6     .17       0  3934.5     .15       0    4906     .11       0
  4973.1     .04       0  5083.5     .11       0
Bank Sta=4973.1,5083.5
XS Rating Curve= 0 ,0
Exp/Cntr=0.3,0.1

Type RM Length L Ch R = 1 ,25000   ,500,500,500
BEGIN DESCRIPTION:
STEWARTS CREEK 48.0
END DESCRIPTION:
XS GIS Cut Line= 3
      3843506.56     10102035.29      3842548.85     10102293.07
      3841731.38      10102922.8
#Sta/Elev= 30
  4008.2  165.47  4241.9  158.18  4510.3  150.21  4731.8  146.73    4825  147.62
  4835.3  145.26  4854.3  144.47  4859.4  142.68  4876.8  149.67  4928.5  149.72
  4959.6  147.93  4968.9  145.55  4974.1  146.46  4980.3  141.48  4992.8  138.52
  5019.7  138.52  5020.2  139.02  5020.7  146.81  5027.1  145.02  5035.3  147.79
  5199.2  150.55  5220.1  148.97  5241.1  150.49  5398.5  151.98  5419.4  154.09
    5469  153.98  5621.5  159.65  5726.5  160.12  5940.3  165.39  6031.9  165.02
#Mann= 6 ,-1 , 0
  4008.2     .17       0  4241.9     .15       0  4959.6     .04       0
  5035.3     .11       0    5469     .17       0  5621.5     .11       0
Bank Sta=4959.6,5035.3
XS Rating Curve= 0 ,0
Exp/Cntr=0.3,0.1

Type RM Length L Ch R = 1 ,24500   ,1000,1000,1000
BEGIN DESCRIPTION:
STEWARTS CREEK 47.0
END DESCRIPTION:
XS GIS Cut Line= 3
      3842521.28     10101384.24      3842442.82     10101896.97
      3841707.58      10102847.5
#Sta/Elev= 30
  4481.3  169.16  4618.6  157.48  4680.4  151.67  4761.4  146.96  4799.1  146.03
  4852.4  147.94  4892.9  147.61    4931   148.8  4963.7  146.67  4973.8  144.03
  4980.4  137.68  5007.7  137.68  5013.9  141.83  5020.2  142.18  5028.4  145.34
 5038.61146.9313  5042.9  148.03  5055.8  146.82  5148.8  149.17  5233.9  153.46
  5292.5  152.27  5327.2  150.45    5377  150.73  5397.8   149.8    5655  150.72
  5849.5     159    5904  161.89    5991  163.87  6011.8  163.22  6201.7  164.08
#Mann= 6 ,-1 , 0
  4481.3     .17       0  4618.6     .15       0  4963.7     .04       0
 5038.61     .15       0  5292.5     .17       0  5849.5     .11       0
#XS Ineff= 2 , 0
                          5262.5          153.42
Permanent Ineff=
       F       F
Bank Sta=4963.7,5038.61
XS Rating Curve= 0 ,0
Exp/Cntr=0.3,0.1

Type RM Length L Ch R = 1 ,23500   ,500,500,500
BEGIN DESCRIPTION:
STEWARTS CREEK 46.0
END DESCRIPTION:
XS GIS Cut Line= 3
      3842267.87     10101211.04      3841889.91     10101727.26
      3841650.58     10102837.87
#Sta/Elev= 30
  4360.2  167.69  4428.9  164.83  4590.6  157.14  4709.1  150.42  4781.2  146.71
  4796.1  146.93  4804.5  144.36  4810.7  147.05  4825.4  145.05  4831.6   147.4
  4868.4  148.18  4875.6  145.45  4881.8  148.21  4946.2  145.54  4957.3  145.33
  4961.3  145.33  4982.1  141.64  4985.6  135.63    5013  135.63  5036.6  144.43
  5044.8  145.63  5054.5  146.95    5096  148.42  5157.3  145.78  5239.2  149.34
  5300.6  149.81  5535.8  147.73  5701.3  151.71  5914.3  162.98  6136.1   163.1
#Mann= 10 ,-1 , 0
  4360.2     .17       0  4428.9     .11       0  4590.6     .15       0
  4709.1     .11       0  4781.2    .125       0  4946.2     .11       0
  4957.3    .125       0  4961.3     .04       0  5044.8    .125       0
  5054.5     .11       0
Bank Sta=4961.3,5044.8
XS Rating Curve= 0 ,0
Exp/Cntr=0.3,0.1