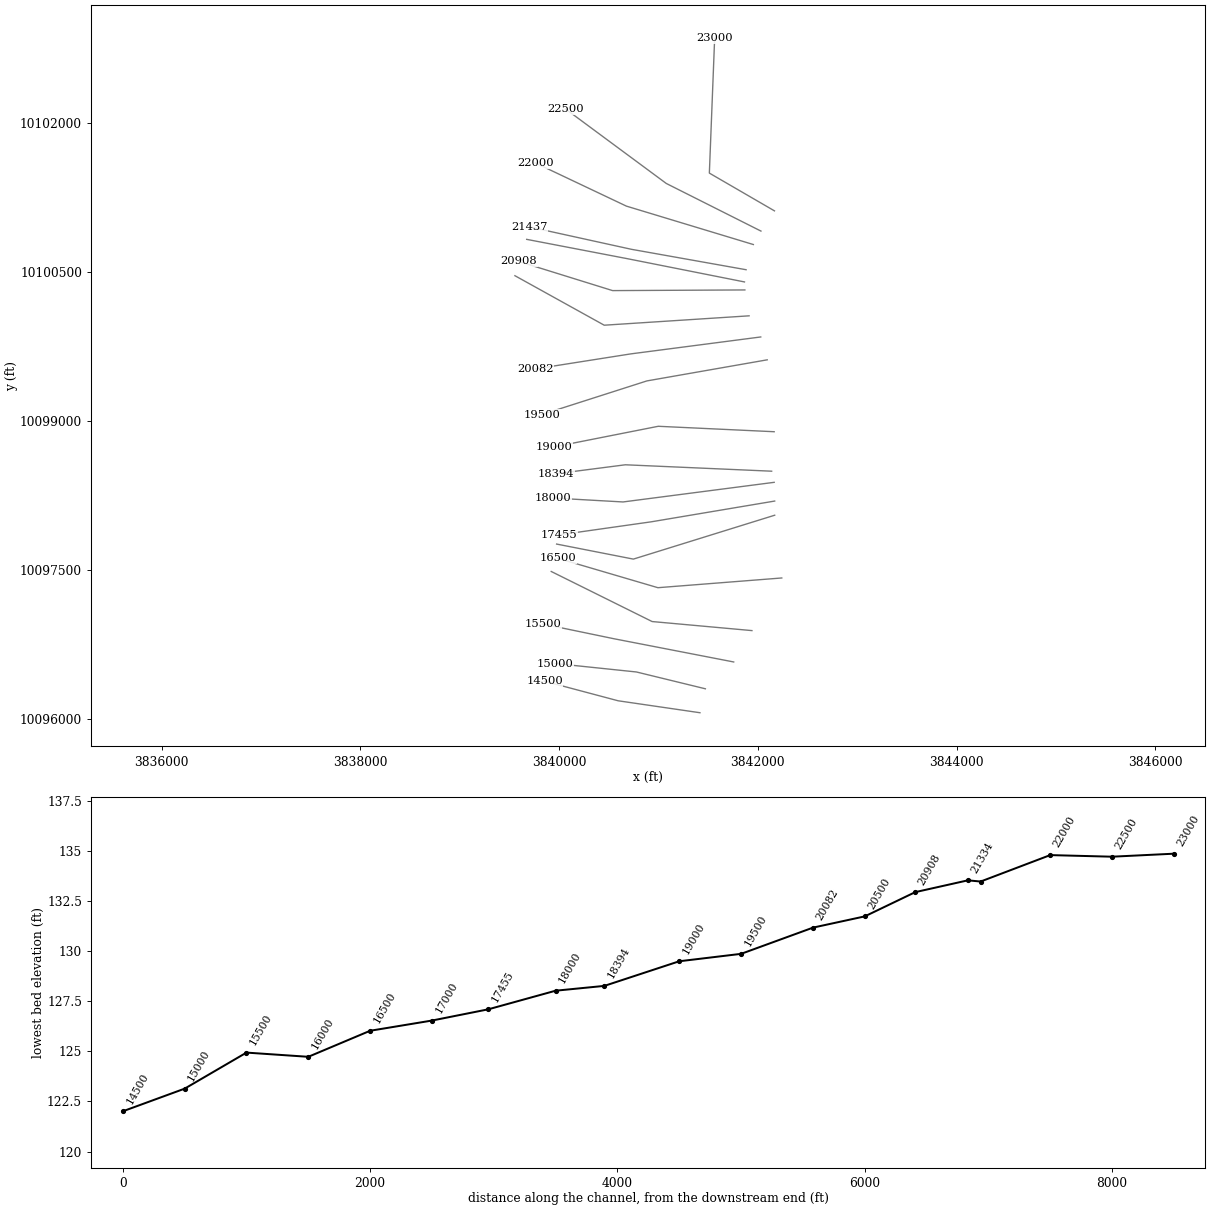
HEC-RAS study STEWARTS CREEK.prj: STEWARTS CREEK Base Level Engineering

--- STEWARTS CREEK.g01 (geometry) --- (continued)

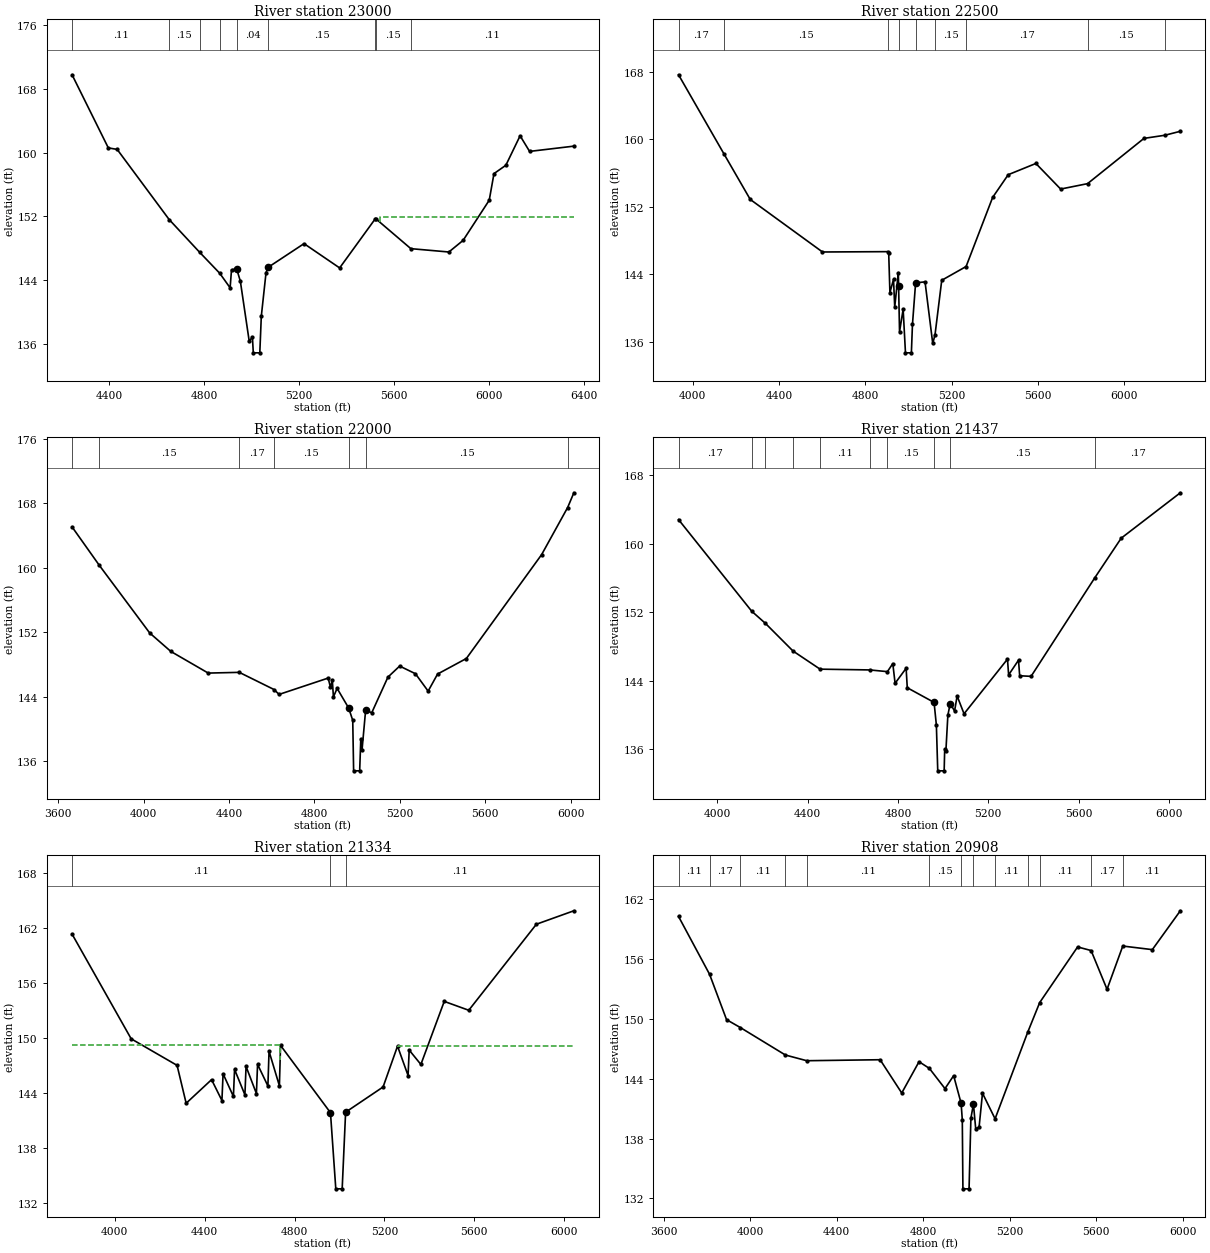
Type RM Length L Ch R = 1 ,23000   ,500,500,500
BEGIN DESCRIPTION:
STEWARTS CREEK 45.0
END DESCRIPTION:
XS GIS Cut Line= 3
      3842167.85     10101111.07      3841512.49     10101491.13
      3841565.79     10102847.49
#Sta/Elev= 30
  4242.4  169.78  4395.2   160.6  4432.5  160.41  4651.5  151.61  4779.6  147.51
  4864.8  144.86  4908.6  143.03  4914.4  145.29    4936  145.43  4951.7  143.86
    4989  136.34  5002.5  136.84  5006.3  134.87  5033.7  134.87    5040  139.46
    5060  144.95    5070  145.63  5220.1  148.58  5370.2  145.53  5520.9  151.72
  5521.6  151.73  5670.3  147.95  5830.6  147.53  5890.6  148.99  6000.7  154.03
  6020.7  157.37  6070.8  158.42  6130.8  162.12  6170.8  160.16  6357.4  160.82
#Mann= 9 ,-1 , 0
  4242.4     .11       0  4651.5     .15       0  4779.6     .11       0
  4864.8     .15       0    4936     .04       0    5070     .15       0
  5520.9     .11       0  5521.6     .15       0  5670.3     .11       0
#XS Ineff= 2 , 0
                         5539.77          151.95
Permanent Ineff=
       F       F
Bank Sta=4936,5070
XS Rating Curve= 0 ,0
Exp/Cntr=0.3,0.1

Type RM Length L Ch R = 1 ,22500   ,500,500,500
BEGIN DESCRIPTION:
STEWARTS CREEK 44.0
END DESCRIPTION:
XS GIS Cut Line= 3
      3842031.69      10100907.7      3841079.01     10101386.87
      3840066.44     10102135.56
#Sta/Elev= 30
  3933.6  167.64  4145.1  158.23    4266  152.88  4600.8  146.66  4904.3   146.7
  4907.7  146.51  4913.3  141.86    4930  143.41  4935.6  140.14  4952.3  144.23
 4953.56142.6502  4957.9  137.21  4974.6  139.88  4985.4  134.72  5012.8  134.72
  5017.8  138.08  5032.4  143.01  5076.1  143.12  5111.8  135.83  5122.3  136.85
  5153.5  143.31  5266.4  144.94  5389.4  153.12  5461.6  155.81  5589.8  157.14
  5704.6  154.11  5829.3  154.75  6090.8  160.11  6187.6  160.48  6259.3  160.95
#Mann= 9 ,-1 , 0
  3933.6     .17       0  4145.1     .15       0  4904.3     .11       0
 4953.56     .04       0  5032.4     .11       0  5122.3     .15       0
  5266.4     .17       0  5829.3     .15       0  6187.6     .11       0
Bank Sta=4953.56,5032.4
XS Rating Curve= 0 ,0
Exp/Cntr=0.3,0.1

Type RM Length L Ch R = 1 ,22000   ,563,563,563
BEGIN DESCRIPTION:
STEWARTS CREEK 43.0
END DESCRIPTION:
XS GIS Cut Line= 3
      3841955.34     10100772.27      3840677.91     10101158.71
      3839761.49     10101593.18
#Sta/Elev= 30
  3665.4  165.09  3793.2  160.31  4028.8  151.92  4127.6  149.63  4302.7  146.94
  4448.1  147.03  4610.6   144.9  4634.4  144.29  4864.2  146.32  4874.7  145.19
  4883.6  146.02  4888.8  143.98    4906  145.04  4959.9  142.61  4979.2  141.07
  4983.3   134.8  5011.6   134.8  5016.9  138.75  5022.5  137.34  5039.7  142.39
  5067.9     142  5143.9  146.44  5198.8  147.81  5272.6  146.86  5332.1   144.7
  5376.3  146.82    5511  148.75  5863.3  161.65  5985.1   167.5  6014.2  169.33
#Mann= 7 ,-1 , 0
  3665.4     .17       0  3793.2     .15       0  4448.1     .17       0
  4610.6     .15       0  4959.9     .04       0  5039.7     .15       0
  5985.1     .17       0
Bank Sta=4959.9,5039.7
XS Rating Curve= 0 ,0
Exp/Cntr=0.3,0.1

Type RM Length L Ch R = 1 ,21437   ,103,103,103
BEGIN DESCRIPTION:
STEWARTS CREEK 42.0
END DESCRIPTION:
XS GIS Cut Line= 3
      3841882.34     10100518.82      3840728.58     10100724.22
      3839702.06     10100949.75
#Sta/Elev= 30
  3828.1  162.81  4152.4  152.11  4213.2  150.69  4335.1  147.47  4455.1  145.35
  4675.2  145.26  4753.4  145.06  4777.3     146  4787.4   143.7  4836.3  145.45
  4841.4  143.18  4960.1  141.47  4970.3  138.82  4976.4  133.48  5004.8  133.48
  5007.2  136.04  5012.4  135.76  5021.2  139.97  5031.5  141.34    5051  140.46
  5062.2  142.22  5092.9  140.14  5285.3  146.52  5290.4  144.68  5334.2   146.4
  5339.3  144.58  5389.8  144.51  5672.2  156.02  5789.1  160.64    6051  165.94
#Mann= 10 ,-1 , 0
  3828.1     .17       0  4152.4     .11       0  4213.2     .17       0
  4335.1     .15       0  4455.1     .11       0  4675.2     .17       0
  4753.4     .15       0  4960.1     .04       0  5031.5     .15       0
  5672.2     .17       0
Bank Sta=4960.1,5031.5
XS Rating Curve= 0 ,0
Exp/Cntr=0.3,0.1

Type RM Length L Ch R = 1 ,21334   ,426,426,426
BEGIN DESCRIPTION:
Mapping XS 6e584a58
END DESCRIPTION:
XS GIS Cut Line= 3
      3841865.92     10100395.96      3840698.41     10100627.76
      3839674.01     10100824.37
#Sta/Elev= 30
  3809.7  161.37  4072.8  149.93  4277.1  147.03  4317.5  142.89  4430.6  145.47
  4476.7  143.19  4481.8  146.11  4527.8  143.64  4532.9  146.59    4579  143.81
  4584.1  146.91  4630.2  143.95  4635.3  147.14  4681.3  144.78  4686.4  148.57
  4732.5   144.8  4737.6  149.21  4959.8  141.86  4983.5  133.54  5011.9  133.54
  5027.2141.9127    5194  144.67  5258.3  149.13  5305.2  145.92  5310.2   148.7
  5362.2  147.13  5466.2  154.02  5575.3  153.05  5876.3  162.45  6043.1  163.92
#Mann= 3 , 0 , 0
  3809.7     .11       0  4959.8     .04       0  5027.2     .11       0
#XS Ineff= 2 , 0
          4735.8  149.29 5259.09          149.12
Permanent Ineff=
       F       F
Bank Sta=4959.8,5027.2
XS Rating Curve= 0 ,0
Exp/Cntr=0.3,0.1

Type RM Length L Ch R = 1 ,20908   ,408,408,408
BEGIN DESCRIPTION:
STEWARTS CREEK 41.0
END DESCRIPTION:
XS GIS Cut Line= 3
      3841869.98     10100315.38       3840538.7     10100308.77
      3839594.21     10100602.14
#Sta/Elev= 30
  3668.7  160.29  3812.1  154.49  3890.8  149.93  3954.5  149.14    4163  146.38
  4261.6  145.81  4600.8  145.91  4700.8  142.57  4780.8  145.71  4828.6  145.04
  4900.8  143.01  4940.8  144.31 4975.34141.5389  4980.8  139.89  4983.7  132.95
  5012.1  132.95  5020.6  140.03  5032.3  141.47  5042.8  138.99  5058.4  139.13
  5074.2  142.55  5132.4  139.98  5283.7  148.69  5338.8  151.65    5514  157.23
  5576.4  156.87  5650.1  152.98  5722.9  157.32  5859.5  156.96    5989  160.86
#Mann= 13 ,-1 , 0
  3668.7     .11       0  3812.1     .17       0  3954.5     .11       0
    4163     .17       0  4261.6     .11       0  4828.6     .15       0
 4975.34     .04       0  5032.3     .15       0  5132.4     .11       0
  5283.7     .17       0  5338.8     .11       0  5576.4     .17       0
  5722.9     .11       0
Bank Sta=4975.34,5032.3
XS Rating Curve= 0 ,0
Exp/Cntr=0.3,0.1

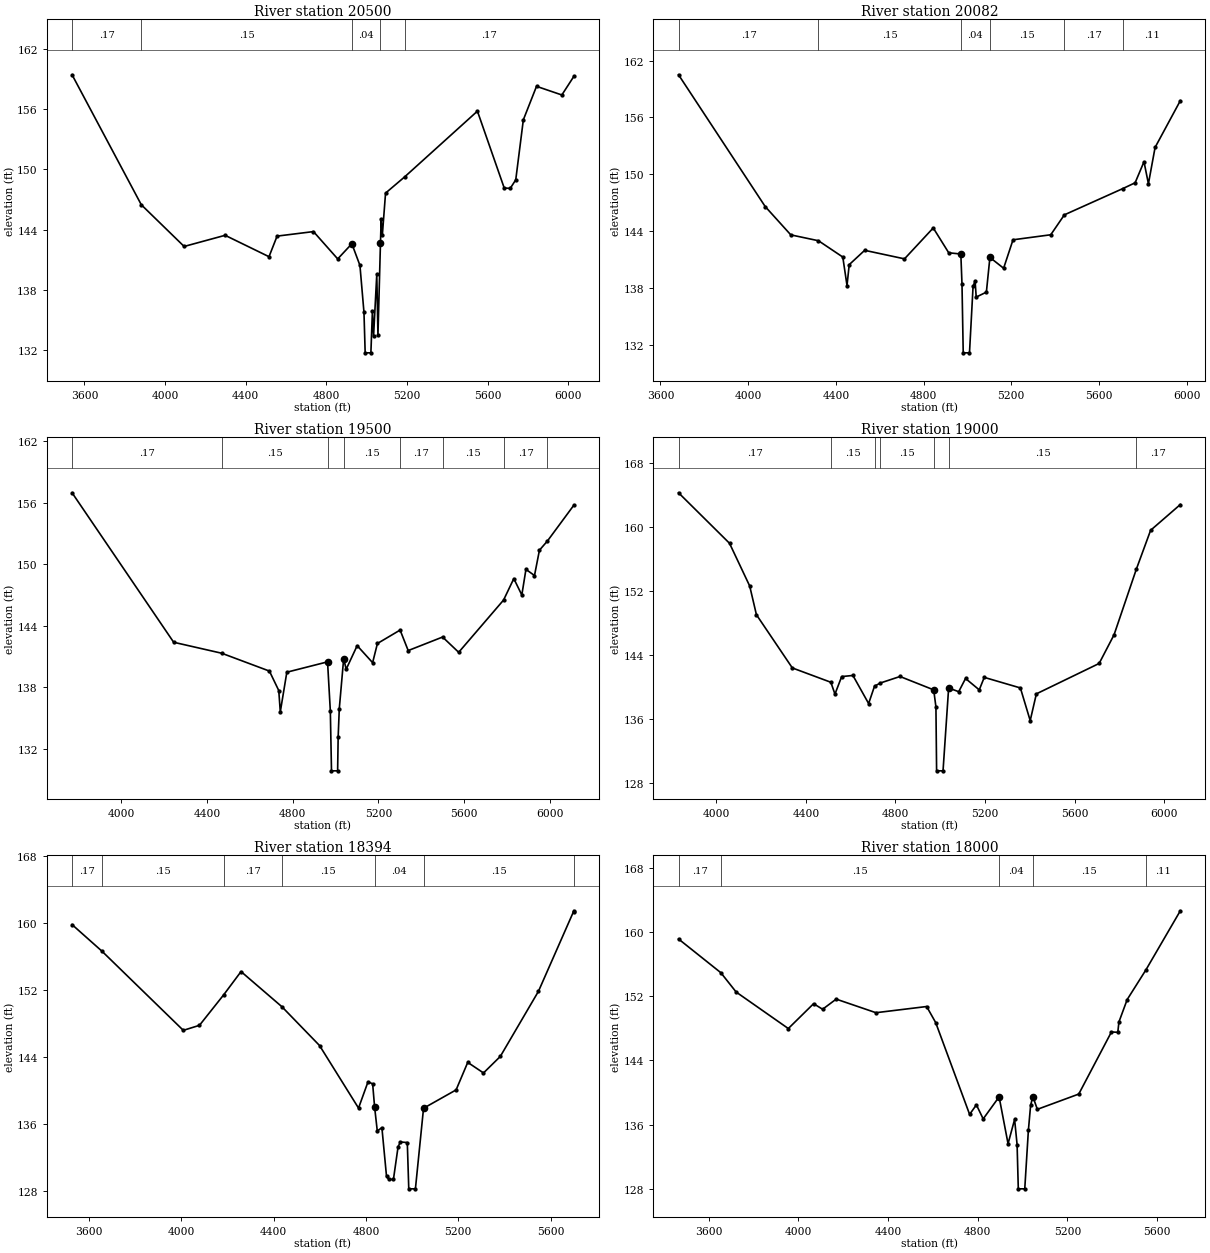
Type RM Length L Ch R = 1 ,20500   ,418,418,418
BEGIN DESCRIPTION:
STEWARTS CREEK 40.0
END DESCRIPTION:
XS GIS Cut Line= 3
      3841912.53     10100054.96      3840454.38     10099960.56
      3839555.76      10100458.6
#Sta/Elev= 30
  3538.8  159.42  3882.2  146.48  4094.6  142.33  4297.8  143.44  4515.5  141.31
  4555.6  143.36    4736  143.81  4856.2  141.09  4926.4   142.6  4966.5  140.44
  4986.5  135.76  4992.4  131.74  5020.8  131.74  5028.3  135.88    5034  133.39
    5050  139.55  5055.8   133.5 5068.28142.6788  5071.8  145.05  5077.5  143.44
  5093.5  147.64  5189.6  149.28  5549.1   155.8    5682  148.15  5711.7  148.11
  5739.2  148.96  5776.9  154.94  5842.2  158.27  5967.8  157.41  6027.4  159.26
#Mann= 5 ,-1 , 0
  3538.8     .17       0  3882.2     .15       0  4926.4     .04       0
 5068.28     .15       0  5189.6     .17       0
Bank Sta=4926.4,5068.28
XS Rating Curve= 0 ,0
Exp/Cntr=0.3,0.1

Type RM Length L Ch R = 1 ,20082   ,582,582,582
BEGIN DESCRIPTION:
STEWARTS CREEK 39.0
END DESCRIPTION:
XS GIS Cut Line= 3
      3842029.69     10099842.28      3840723.32     10099672.17
      3839764.14     10099521.11
#Sta/Elev= 30
  3682.6   160.5  4077.7  146.61  4194.5  143.62  4320.8     143  4431.7  141.28
  4450.9  138.28    4461  140.48  4531.5  141.99  4713.1  141.09  4844.2  144.35
  4914.8  141.73    4970   141.6  4975.3  138.43  4980.9  131.18  5009.5  131.18
  5025.8  138.18    5035  138.78  5040.1  137.06  5086.5  137.58  5102.6  141.24
  5165.1   140.1    5208   143.1  5380.1  143.63  5442.1  145.73  5708.8   148.5
  5764.8  149.11  5805.3  151.33  5825.5  149.01  5855.9  152.84    5971  157.77
#Mann= 6 ,-1 , 0
  3682.6     .17       0  4320.8     .15       0    4970     .04       0
  5102.6     .15       0  5442.1     .17       0  5708.8     .11       0
Bank Sta=4970,5102.6
XS Rating Curve= 0 ,0
Exp/Cntr=0.3,0.1

Type RM Length L Ch R = 1 ,19500   ,500,500,500
BEGIN DESCRIPTION:
STEWARTS CREEK 38.0
END DESCRIPTION:
XS GIS Cut Line= 3
      3842094.87     10099612.26      3840884.03     10099400.02
      3839824.85     10099061.03
#Sta/Elev= 30
  3770.7  156.99  4244.8  142.41    4469  141.34  4691.5   139.6  4735.2   137.7
  4742.3  135.62  4772.8  139.49  4962.8   140.5  4975.8   135.7  4981.2  129.87
  5009.8  129.87  5012.3  133.17  5017.6  135.94    5038  140.81  5049.7  139.78
    5101  142.08  5173.1  140.42  5195.5  142.29  5301.3   143.6  5339.1   141.6
  5499.6  142.92  5574.7  141.43  5784.2  146.53  5831.9  148.62  5869.3  147.02
  5888.5  149.52  5928.4  148.92  5951.5  151.39  5988.9  152.29  6112.1  155.78
#Mann= 8 ,-1 , 0
  3770.7     .17       0    4469     .15       0  4962.8     .04       0
    5038     .15       0  5301.3     .17       0  5499.6     .15       0
  5784.2     .17       0  5988.9     .11       0
Bank Sta=4962.8,5038
XS Rating Curve= 0 ,0
Exp/Cntr=0.3,0.1

Type RM Length L Ch R = 1 ,19000   ,606,606,606
BEGIN DESCRIPTION:
STEWARTS CREEK 37.0
END DESCRIPTION:
XS GIS Cut Line= 3
      3842164.98      10098888.7      3840998.26     10098943.45
      3839947.79     10098735.79
#Sta/Elev= 30
    3832  164.25  4059.4  157.94  4149.5   152.6  4179.5  149.01  4339.7  142.36
  4511.5  140.57  4529.9  139.09  4559.9  141.28    4610  141.42  4680.1  137.91
  4706.4  140.08  4732.7  140.48  4820.2  141.29  4970.4  139.62  4980.4  137.49
  4983.4   129.5  5012.1   129.5  5037.1  139.86    5082  139.39  5112.5  141.04
  5173.7  139.62    5196  141.18  5357.2  139.86    5401  135.78  5428.5  139.12
  5708.6  142.92  5775.1   146.5  5874.3  154.68  5938.2  159.56  6070.8  162.78
#Mann= 7 ,-1 , 0
    3832     .17       0  4511.5     .15       0  4706.4     .17       0
  4732.7     .15       0  4970.4     .04       0  5037.1     .15       0
  5874.3     .17       0
Bank Sta=4970.4,5037.1
XS Rating Curve= 0 ,0
Exp/Cntr=0.3,0.1

Type RM Length L Ch R = 1 ,18394   ,394,394,394
BEGIN DESCRIPTION:
STEWARTS CREEK 36.0
END DESCRIPTION:
XS GIS Cut Line= 3
      3842139.55     10098491.53      3840667.07     10098556.07
      3839971.64     10098466.24
#Sta/Elev= 30
  3526.1  159.78  3655.3  156.62  4008.3  147.17  4078.3  147.77  4182.8  151.39
  4258.5  154.18  4435.6  149.99  4598.8  145.36  4767.8   137.9    4809  141.04
    4829  140.79  4837.5138.0212  4849.1  135.17  4869.1  135.57  4889.1  129.77
  4899.1   129.4  4919.1  129.39  4939.2  133.28  4949.2  133.86  4979.2  133.79
  4985.6  128.27  5014.4  128.27  5049.6  137.88  5190.8  140.07  5241.2  143.35
  5309.5  142.09  5382.4  144.06  5547.6  151.82  5699.9  161.34  5701.2  161.43
#Mann= 7 ,-1 , 0
  3526.1     .17       0  3655.3     .15       0  4182.8     .17       0
  4435.6     .15       0  4837.5     .04       0  5049.6     .15       0
  5699.9     .17       0
Bank Sta=4837.5,5049.6
XS Rating Curve= 0 ,0
Exp/Cntr=0.3,0.1

Type RM Length L Ch R = 1 ,18000   ,545,545,545
BEGIN DESCRIPTION:
STEWARTS CREEK 35.0
END DESCRIPTION:
XS GIS Cut Line= 3
      3842165.01     10098379.51      3840643.67     10098182.02
      3839941.28     10098221.57
#Sta/Elev= 30
  3465.9  159.11  3654.4  154.92  3722.9  152.51  3955.4  147.97  4068.1  151.06
  4108.4  150.37  4168.9  151.63  4346.2  149.94  4572.3  150.71  4612.6  148.71
  4763.9  137.29  4794.1  138.48  4824.4  136.73  4895.4  139.47  4935.3  133.64
  4964.5  136.66  4975.6  133.54    4981  128.03  5009.8  128.03  5025.9  135.29
  5035.9  138.42  5045.9  139.51  5065.9  137.92  5250.6  139.82  5396.4  147.55
  5424.7   147.5  5429.7  148.79  5466.6  151.58  5549.9  155.26  5703.5  162.62
#Mann= 5 ,-1 , 0
  3465.9     .17       0  3654.4     .15       0  4895.4     .04       0
  5045.9     .15       0  5549.9     .11       0
Bank Sta=4895.4,5045.9
XS Rating Curve= 0 ,0
Exp/Cntr=0.3,0.1

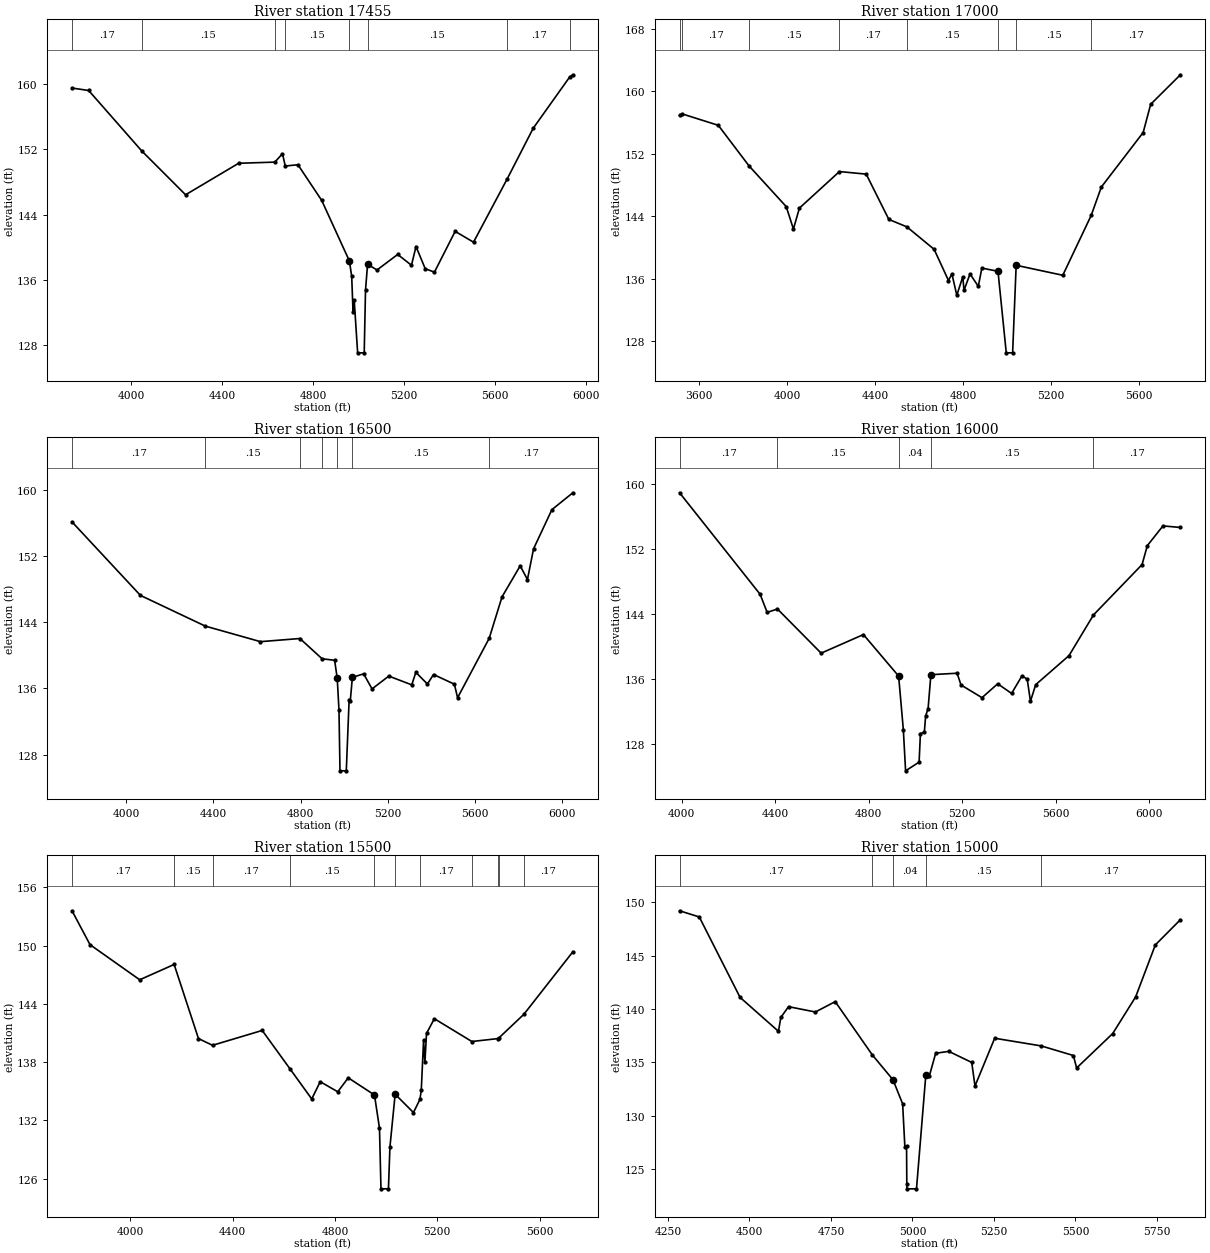
Type RM Length L Ch R = 1 ,17455   ,455,455,455
BEGIN DESCRIPTION:
STEWARTS CREEK 34.0
END DESCRIPTION:
XS GIS Cut Line= 3
      3842170.03     10098191.09      3840927.39      10097982.1
      3839995.81     10097849.94
#Sta/Elev= 30
  3739.9  159.45  3813.1  159.15  4045.9  151.78    4239  146.41  4472.2  150.26
  4631.3   150.4  4664.9  151.43  4677.1  149.92  4732.8  150.08  4837.3  145.72
    4959  138.32  4969.1  136.44  4975.1  132.03  4980.2  133.51  4995.2   127.1
  5024.1   127.1  5029.8  134.77  5038.9  137.92  5080.3  137.22  5171.2  139.12
  5231.8   137.8  5251.7  140.09  5292.4  137.37  5332.8  136.96  5423.7  141.94
  5504.5  140.62  5652.5  148.35  5767.1  154.55  5927.9  160.83  5940.9  161.07
#Mann= 8 ,-1 , 0
  3739.9     .17       0  4045.9     .15       0  4631.3     .17       0
  4677.1     .15       0    4959     .04       0  5038.9     .15       0
  5652.5     .17       0  5927.9     .11       0
Bank Sta=4959,5038.9
XS Rating Curve= 0 ,0
Exp/Cntr=0.3,0.1

Type RM Length L Ch R = 1 ,17000   ,500,500,500
BEGIN DESCRIPTION:
STEWARTS CREEK 33.0
END DESCRIPTION:
XS GIS Cut Line= 3
      3842170.04     10098048.51       3840747.7     10097606.94
      3839975.39     10097758.28
#Sta/Elev= 30
  3510.7  156.93  3523.6  157.12  3686.7  155.67  3826.5  150.47  3995.5  145.26
  4028.1  142.39  4055.4  145.07  4237.3  149.75    4359  149.42  4461.9  143.62
  4543.8  142.67  4667.8  139.79    4733   135.8  4748.5  136.65  4770.8  133.91
  4798.1  136.29  4803.4  134.53  4830.7  136.64  4868.5  135.06  4884.7  137.39
    4958  136.98  4995.6  126.54  5024.5  126.54  5040.6  137.75  5252.5  136.47
  5381.6  144.13  5427.8  147.77  5617.9  154.75    5652  158.36    5787  162.14
#Mann= 8 ,-1 , 0
  3510.7     .15       0  3523.6     .17       0  3826.5     .15       0
  4237.3     .17       0  4543.8     .15       0    4958     .04       0
  5040.6     .15       0  5381.6     .17       0
Bank Sta=4958,5040.6
XS Rating Curve= 0 ,0
Exp/Cntr=0.3,0.1

Type RM Length L Ch R = 1 ,16500   ,500,500,500
BEGIN DESCRIPTION:
STEWARTS CREEK 32.0
END DESCRIPTION:
XS GIS Cut Line= 3
      3842241.37     10097417.12      3840994.81     10097319.23
      3839985.55     10097615.72
#Sta/Elev= 30
  3749.6  156.11  4064.1  147.23  4362.2  143.52  4615.8  141.64  4797.3  142.02
  4899.3  139.57  4956.8  139.39  4968.8137.2337  4976.9  133.37  4981.5  126.03
  5010.5  126.03  5023.6  134.65  5028.8  134.46  5038.5  137.33  5090.3  137.75
  5128.9  135.93  5206.1  137.48  5311.4  136.42  5330.3  137.93  5383.4  136.52
  5411.5  137.67  5507.5   136.5  5522.1  134.86  5667.4  142.04  5726.4  147.05
  5809.9   150.8  5843.3  149.15  5871.4  152.86  5955.7  157.59  6051.9  159.63
#Mann= 7 ,-1 , 0
  3749.6     .17       0  4362.2     .15       0  4797.3     .17       0
  4899.3     .15       0  4968.8     .04       0  5038.5     .15       0
  5667.4     .17       0
Bank Sta=4968.8,5038.5
XS Rating Curve= 0 ,0
Exp/Cntr=0.3,0.1

Type RM Length L Ch R = 1 ,16000   ,500,500,500
BEGIN DESCRIPTION:
STEWARTS CREEK 31.0
END DESCRIPTION:
XS GIS Cut Line= 3
      3841940.91     10096887.55      3840936.63     10096978.59
      3839921.16     10097482.44
#Sta/Elev= 30
  3991.6  158.97  4336.1  146.47  4366.2  144.24  4410.2  144.66  4597.1  139.22
  4777.9  141.51  4928.5   136.4  4948.6  129.82  4958.3  124.73  5016.1   125.8
  5021.7  129.32  5038.5  129.49  5044.1   131.5  5054.5  132.38  5066.5  136.57
  5178.6  136.75  5195.4   135.3  5285.1  133.74  5352.3  135.45  5411.7  134.26
  5456.3  136.44  5478.7     136  5492.3  133.29  5514.8  135.34  5657.3  138.92
    5762  143.93  5969.8  150.13  5992.2  152.46  6059.1  154.89  6133.6   154.7
#Mann= 5 ,-1 , 0
  3991.6     .17       0  4410.2     .15       0  4928.5     .04       0
  5066.5     .15       0    5762     .17       0
Bank Sta=4928.5,5066.5
XS Rating Curve= 0 ,0
Exp/Cntr=0.3,0.1

Type RM Length L Ch R = 1 ,15500   ,500,500,500
BEGIN DESCRIPTION:
STEWARTS CREEK 30.0
END DESCRIPTION:
XS GIS Cut Line= 3
      3841757.58     10096571.85      3840552.63     10096805.54
      3839837.93     10096953.74
#Sta/Elev= 30
  3772.6  153.59  3842.9   150.1  4037.2  146.48  4171.7  148.06  4266.9  140.42
  4321.9  139.73  4515.9  141.26  4625.7  137.26  4709.5   134.2  4742.7  135.98
  4811.3  134.94  4852.1  136.38  4954.7  134.61  4974.3  131.19  4980.1  124.94
  5009.3  124.94  5015.1  129.25  5035.5  134.69    5107   132.8  5132.3  134.15
  5137.6  135.09  5146.6  140.27  5151.7  137.96  5158.1  140.95  5188.7  142.47
  5335.4  140.12  5436.9  140.42  5442.2  140.52  5538.5  142.92  5729.9  149.36
#Mann= 11 ,-1 , 0
  3772.6     .17       0  4171.7     .15       0  4321.9     .17       0
  4625.7     .15       0  4954.7     .04       0  5035.5     .15       0
  5132.3     .17       0  5335.4     .15       0  5436.9     .17       0
  5442.2     .11       0  5538.5     .17       0
Bank Sta=4954.7,5035.5
XS Rating Curve= 0 ,0
Exp/Cntr=0.3,0.1

Type RM Length L Ch R = 1 ,15000   ,500,500,500
BEGIN DESCRIPTION:
STEWARTS CREEK 29.0
END DESCRIPTION:
XS GIS Cut Line= 3
      3841472.42     10096301.98      3840778.75     10096471.15
      3839961.49     10096556.43
#Sta/Elev= 30
    4286  149.21  4346.4  148.63  4471.5  141.09  4589.2  137.91  4596.5  139.21
  4620.1  140.22  4702.4  139.72  4763.3  140.69  4876.7  135.71  4940.3  133.37
    4970  131.11  4976.9  127.05    4982  127.17  4982.8  123.64  4983.3  123.14
  5012.5  123.14  5041.1  133.81  5051.8  133.71  5071.3  135.85  5111.5  136.03
  5181.9  134.99  5191.9  132.78  5252.3  137.26    5395  136.54  5493.6  135.64
  5503.6  134.47  5614.2   137.7  5684.6  141.14  5744.9  146.01  5821.7  148.37
#Mann= 5 ,-1 , 0
    4286     .17       0  4876.7     .15       0  4940.3     .04       0
  5041.1     .15       0    5395     .17       0
Bank Sta=4940.3,5041.1
XS Rating Curve= 0 ,0
Exp/Cntr=0.3,0.1

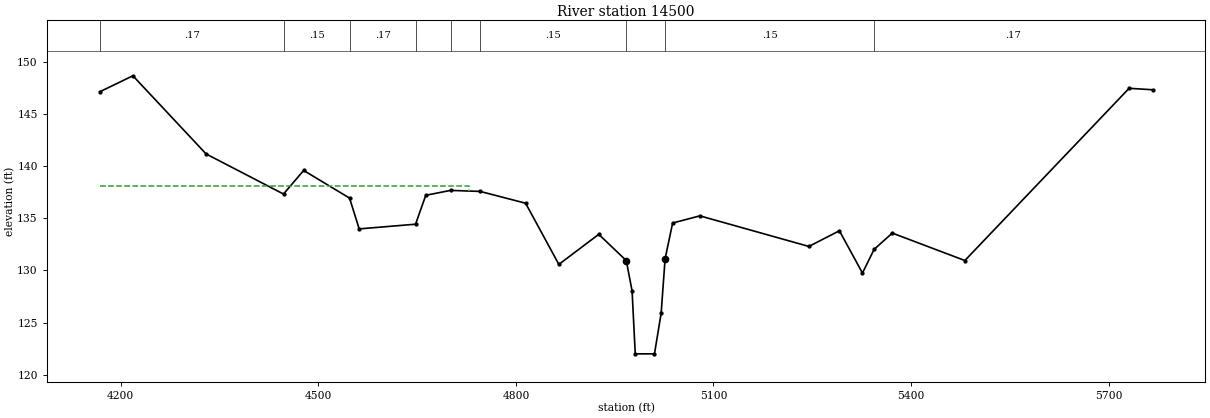
Type RM Length L Ch R = 1 ,14500   ,570,570,570
BEGIN DESCRIPTION:
STEWARTS CREEK 28.0
END DESCRIPTION:
XS GIS Cut Line= 3
      3841417.82     10096061.08      3840594.45     10096181.28
       3839853.2     10096378.35
#Sta/Elev= 30
  4167.9  147.11  4218.4  148.65  4329.6  141.16  4447.1  137.32  4477.7  139.58
  4547.4  136.93    4562  133.98  4647.6  134.43  4663.1   137.2  4700.8  137.67
  4745.8  137.57  4814.7  136.44  4865.2  130.58  4925.8  133.46  4967.6  130.94
  4976.4  128.03  4981.2  122.01  5010.4  122.01  5020.5  125.89  5026.5131.1014
  5037.9  134.54  5079.3  135.23  5244.8   132.3  5291.2   133.8  5326.2  129.75
  5343.9  132.02  5371.5  133.58  5481.7  130.95  5731.1  147.45    5767  147.31
#Mann= 9 ,-1 , 0
  4167.9     .17       0  4447.1     .15       0  4547.4     .17       0
  4647.6     .15       0  4700.8     .17       0  4745.8     .15       0
  4967.6     .04       0  5026.5     .15       0  5343.9     .17       0
#XS Ineff= 2 , 0
         4728.18  138.07
Permanent Ineff=
       F       F
Bank Sta=4967.6,5026.5
XS Rating Curve= 0 ,0
Exp/Cntr=0.3,0.1