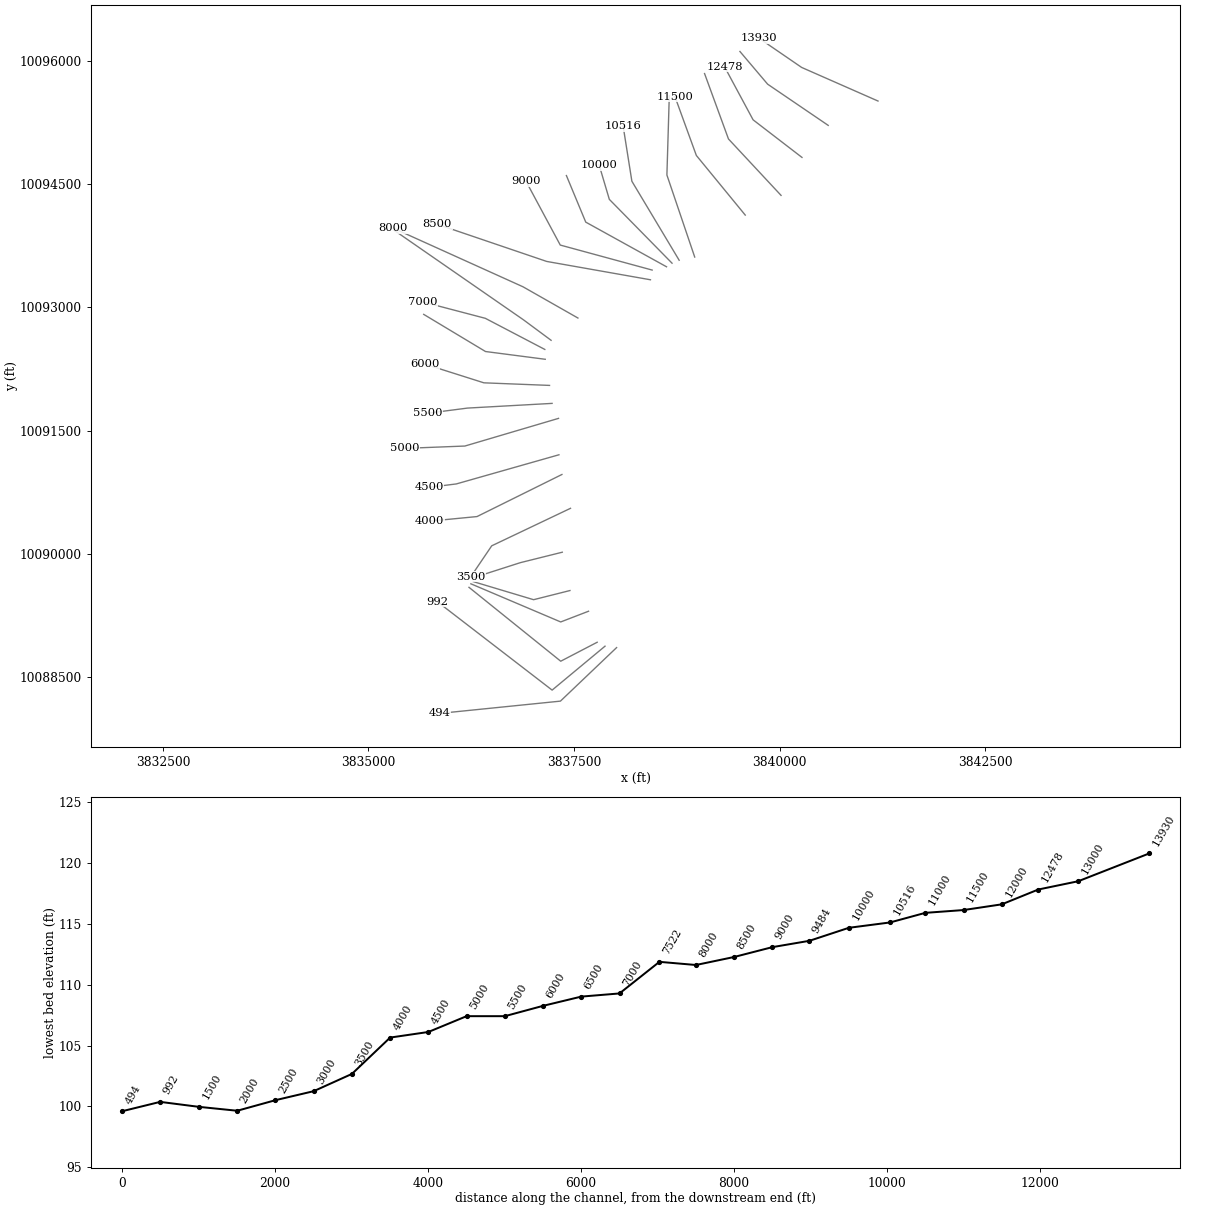
HEC-RAS study STEWARTS CREEK.prj: STEWARTS CREEK Base Level Engineering

--- STEWARTS CREEK.g01 (geometry) --- (continued)

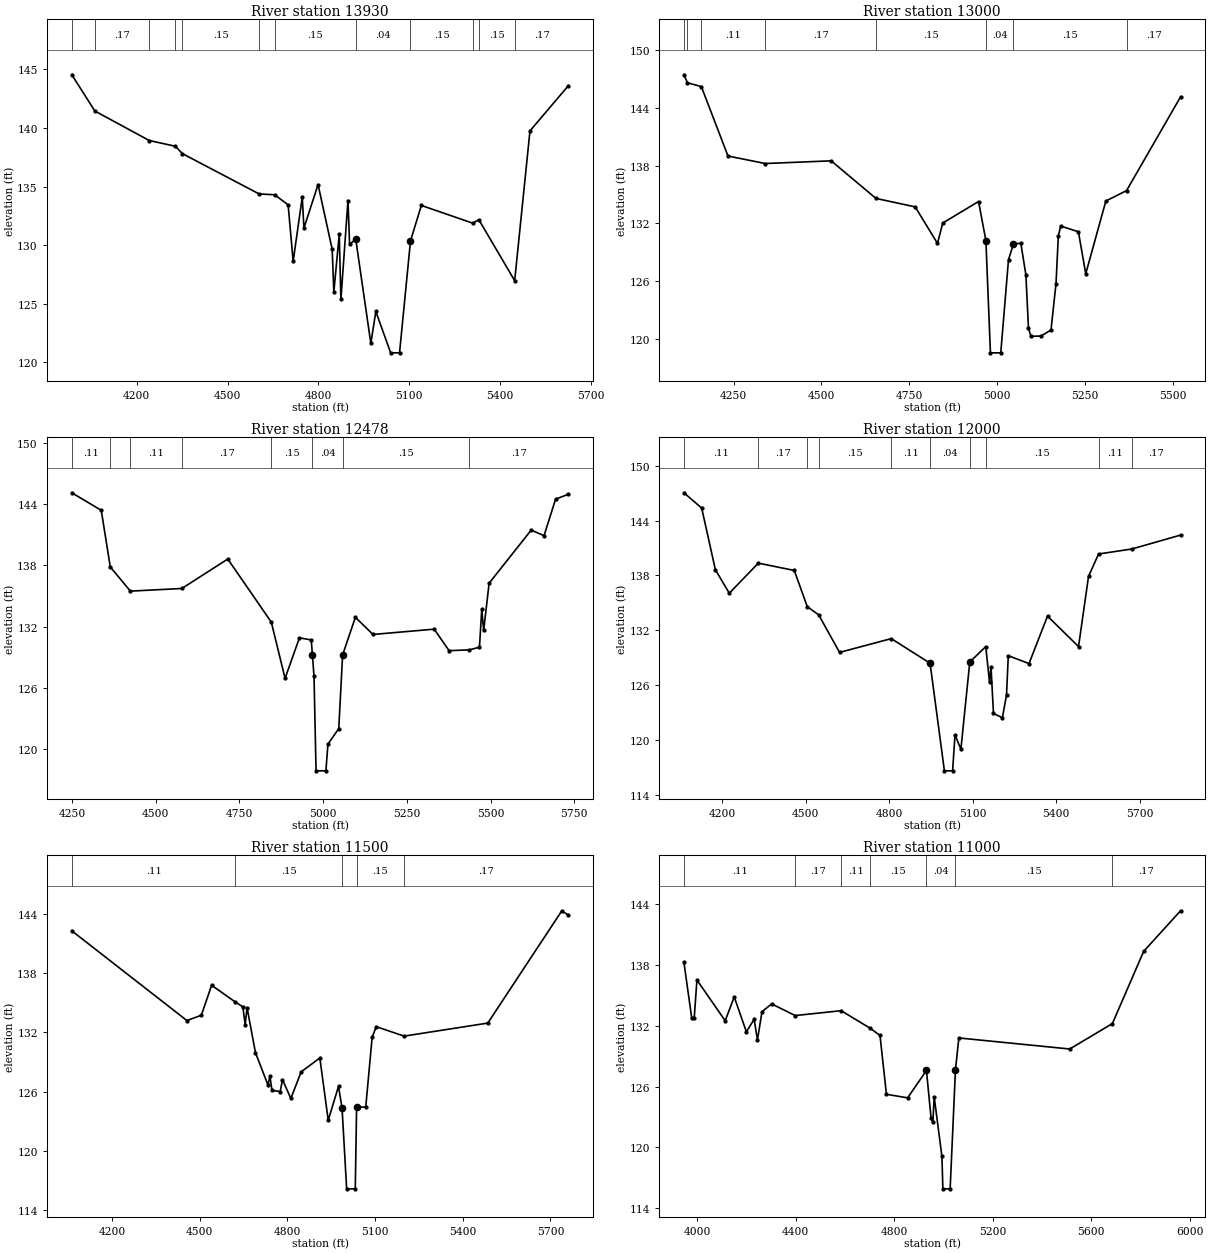
Type RM Length L Ch R = 1 ,13930   ,930,930,930
BEGIN DESCRIPTION:
STEWARTS CREEK 27.0
END DESCRIPTION:
XS GIS Cut Line= 3
      3841197.03     10095508.34      3840268.55     10095916.92
      3839752.12      10096270.9
#Sta/Elev= 30
  3985.6  144.54  4061.6  141.45  4241.4  138.93  4327.7  138.44    4351  137.81
  4604.4  134.37  4655.7   134.3  4700.1  133.44  4716.7  128.62  4746.8   134.1
  4752.3  131.46    4799  135.17  4845.6  129.65  4851.1     126    4869  130.94
  4874.4  125.37  4897.8  133.81  4903.2  130.06  4923.4130.5205  4973.3  121.62
  4989.8  124.34  5038.8  120.81  5068.1  120.81  5104.3  130.36  5140.1  133.39
  5309.5  131.88  5330.1  132.17  5448.4  126.97  5498.9  139.75  5626.1  143.62
#Mann= 12 ,-1 , 0
  3985.6     .11       0  4061.6     .17       0  4241.4     .11       0
  4327.7     .17       0    4351     .15       0  4604.4     .17       0
  4655.7     .15       0  4923.4     .04       0  5104.3     .15       0
  5309.5     .17       0  5330.1     .15       0  5448.4     .17       0
Bank Sta=4923.4,5104.3
XS Rating Curve= 0 ,0
Exp/Cntr=0.3,0.1

Type RM Length L Ch R = 1 ,13000   ,522,522,522
BEGIN DESCRIPTION:
STEWARTS CREEK 26.0
END DESCRIPTION:
XS GIS Cut Line= 3
      3840591.55     10095212.27      3839854.75     10095713.46
      3839517.88     10096111.03
#Sta/Elev= 30
  4108.9  147.44  4118.9  146.61  4158.4  146.21  4234.2  138.99  4340.1  138.21
  4527.6  138.49    4655  134.58  4766.5   133.7  4829.9   129.9  4844.8  132.02
  4946.6  134.26  4967.5   130.2  4980.4  118.52  5009.8  118.52  5031.8  128.21
    5046  129.85  5066.9  129.91  5081.2  126.64  5088.6   121.1  5095.5  120.24
    5124  120.27  5152.6  120.89  5166.9  125.73  5173.5  130.69  5180.4  131.71
  5230.6  131.11  5251.4  126.74  5308.6  134.31  5367.4  135.39  5521.1  145.15
#Mann= 8 ,-1 , 0
  4108.9     .11       0  4118.9     .17       0  4158.4     .11       0
  4340.1     .17       0    4655     .15       0  4967.5     .04       0
    5046     .15       0  5367.4     .17       0
Bank Sta=4967.5,5046
XS Rating Curve= 0 ,0
Exp/Cntr=0.3,0.1

Type RM Length L Ch R = 1 ,12478   ,478,478,478
BEGIN DESCRIPTION:
STEWARTS CREEK 25.0
END DESCRIPTION:
XS GIS Cut Line= 3
      3840272.57     10094822.58      3839677.87     10095279.88
      3839330.74     10095925.02
#Sta/Elev= 30
  4249.8  145.12  4337.7   143.4  4364.6  137.85  4424.7  135.47  4578.4  135.73
  4715.5  138.62  4845.4  132.43  4886.5  126.91  4929.4  130.89  4964.7  130.68
 4968.04  129.23  4972.9  127.12    4979  117.84  5008.4  117.84  5014.5  120.46
  5046.8  121.99  5058.3  129.21  5096.4   132.9    5149  131.22  5331.7  131.74
  5376.1  129.63  5436.8  129.71  5466.9  129.97  5473.7  133.67  5479.4  131.62
  5495.7  136.25  5621.4  141.46  5659.6  140.91  5694.1  144.49  5732.6  144.98
#Mann= 8 ,-1 , 0
  4249.8     .11       0  4364.6     .17       0  4424.7     .11       0
  4578.4     .17       0  4845.4     .15       0 4968.04     .04       0
  5058.3     .15       0  5436.8     .17       0
Bank Sta=4968.04,5058.3
XS Rating Curve= 0 ,0
Exp/Cntr=0.3,0.1

Type RM Length L Ch R = 1 ,12000   ,500,500,500
BEGIN DESCRIPTION:
STEWARTS CREEK 24.0
END DESCRIPTION:
XS GIS Cut Line= 3
      3840017.86     10094361.06      3839378.44     10095047.07
      3839087.71      10095842.5
#Sta/Elev= 30
  4062.2  147.05    4126  145.38  4175.3  138.62  4225.2  136.06  4329.6  139.35
  4458.7  138.55  4505.4  134.59  4546.8  133.68  4621.4  129.58  4807.1  131.09
  4946.7   128.4  4998.2  116.62  5027.7  116.62  5036.2  120.55  5057.5  118.99
  5089.4  128.53  5146.9  130.22  5160.3  126.31  5165.6  128.02  5174.6   122.9
  5206.6  122.43  5221.4  124.93  5227.8  129.22  5302.3  128.36  5368.7  133.55
  5480.2  130.22  5516.1   137.9  5552.2  140.35    5672   140.9  5846.9  142.42
#Mann= 10 ,-1 , 0
  4062.2     .11       0  4329.6     .17       0  4505.4     .11       0
  4546.8     .15       0  4807.1     .11       0  4946.7     .04       0
  5089.4     .11       0  5146.9     .15       0  5552.2     .11       0
    5672     .17       0
Bank Sta=4946.7,5089.4
XS Rating Curve= 0 ,0
Exp/Cntr=0.3,0.1

Type RM Length L Ch R = 1 ,11500   ,500,500,500
BEGIN DESCRIPTION:
STEWARTS CREEK 23.0
END DESCRIPTION:
XS GIS Cut Line= 3
      3839582.35     10094121.46      3838987.75     10094846.53
      3838727.31     10095562.43
#Sta/Elev= 30
  4062.3  142.27    4456  133.19  4505.5  133.72  4540.7  136.76    4622  135.06
  4647.6  134.57  4655.5  132.78    4662  134.48  4690.7  129.94  4733.7  126.65
  4740.2  127.57  4747.2  126.12  4775.4     126  4783.2   127.2  4811.9   125.3
  4847.1  127.99    4911   129.4  4939.7   123.1  4974.9  126.52    4987124.3358
  5002.8  116.15  5032.3  116.15  5036.8  124.41  5068.1  124.44    5090  131.49
    5104  132.57  5199.3  131.61  5485.7  132.93  5739.1   144.3  5761.8  143.85
#Mann= 5 ,-1 , 0
  4062.3     .11       0    4622     .15       0    4987     .04       0
  5036.8     .15       0  5199.3     .17       0
Bank Sta=4987,5036.8
XS Rating Curve= 0 ,0
Exp/Cntr=0.3,0.1

Type RM Length L Ch R = 1 ,11000   ,461,461,461
BEGIN DESCRIPTION:
STEWARTS CREEK 22.0
END DESCRIPTION:
XS GIS Cut Line= 3
      3838967.85     10093611.07      3838629.73     10094608.73
      3838658.68      10095570.7
#Sta/Elev= 30
  3946.6  138.28  3978.3  132.76  3988.4  132.78  3999.4  136.53  4114.1  132.51
  4150.8  134.86    4200  131.42  4231.7  132.65    4245   130.6  4263.4   133.4
  4302.6  134.17  4398.3  133.02  4584.7   133.5  4701.8  131.78  4742.4  131.06
  4768.5  125.25  4854.6   124.9  4930.9   127.6  4949.7  122.91    4957  122.48
  4962.3  125.01  4993.7  119.12  4997.6  115.92  5027.1  115.92  5048.6127.6343
  5062.4  130.81  5512.6  129.72  5685.6  132.23  5812.7  139.36  5962.4  143.36
#Mann= 7 ,-1 , 0
  3946.6     .11       0  4398.3     .17       0  4584.7     .11       0
  4701.8     .15       0  4930.9     .04       0  5048.6     .15       0
  5685.6     .17       0
Bank Sta=4930.9,5048.6
XS Rating Curve= 0 ,0
Exp/Cntr=0.3,0.1

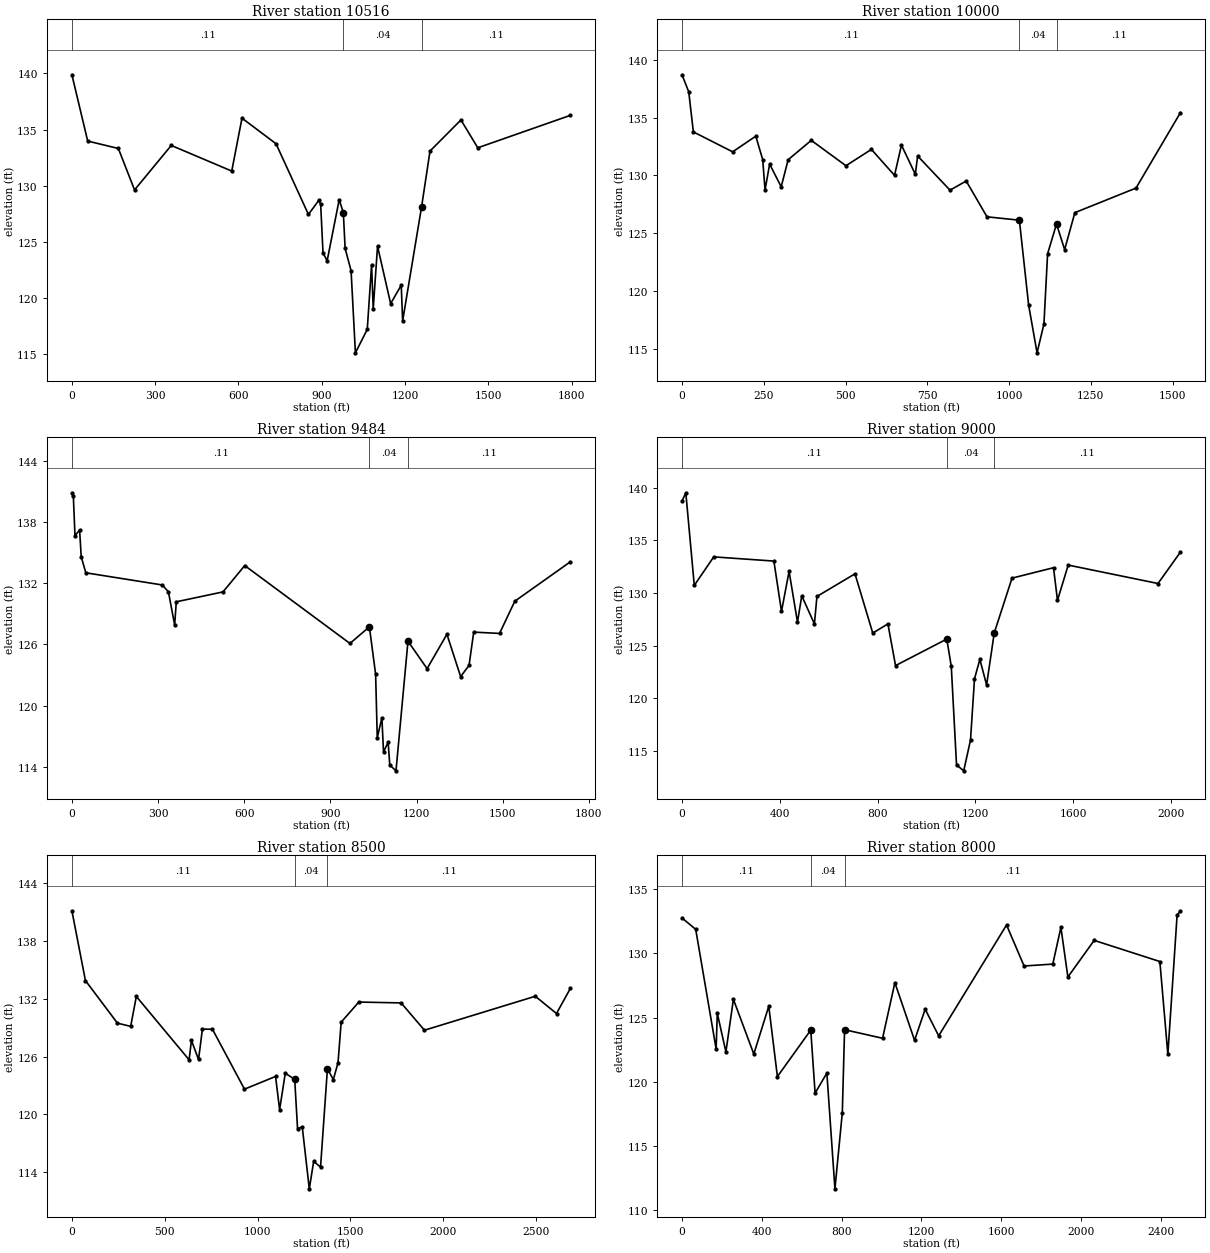
Type RM Length L Ch R = 1 ,10516   ,539,539,539
XS GIS Cut Line= 3
       3838778.6     10093572.27      3838203.73     10094532.82
      3838097.77     10095200.41
#Sta/Elev= 30
       0  139.88    56.9  133.98   167.3  133.32   225.6  129.63   357.9  133.59
   575.7  131.31   612.6  136.02   735.2  133.74   851.9  127.45   888.8  128.69
     896  128.35   904.4  124.03   919.3  123.32   962.7  128.76   977.6  127.61
   984.1  124.42  1005.5  122.44  1021.1  115.13  1063.8  117.22  1079.4  122.98
  1085.2  119.03  1100.8  124.62    1148  119.51  1186.2  121.15  1191.2  117.97
  1259.4  128.12  1289.8  133.09  1401.2  135.86  1461.9  133.38  1795.4  136.27
#Mann= 3 , 0 , 0
       0     .11       0   977.6     .04       0  1259.4     .11       0
Bank Sta=977.6,1259.4
XS Rating Curve= 0 ,0
Exp/Cntr=0.3,0.1

Type RM Length L Ch R = 1 ,10000   ,516,516,516
XS GIS Cut Line= 3
       3838692.1      10093536.3      3837929.44     10094312.54
      3837805.36     10094730.74
#Sta/Elev= 30
       0  138.69    20.6  137.22    34.7  133.76   154.9  132.04   225.6  133.39
   246.8  131.37   253.9  128.75     268  130.98   303.3  129.02   324.6  131.36
   395.3  133.03   501.3  130.84   579.2  132.25   649.9  130.01   671.1  132.62
   713.5   130.1   720.6  131.68   819.6  128.73   869.1  129.52   932.7  126.43
  1031.7  126.14    1060  118.81  1085.8  114.69  1106.8  117.18    1118  123.24
  1145.3  125.81  1170.1   123.6  1201.4  126.79  1388.3  128.91  1524.4  135.43
#Mann= 3 , 0 , 0
       0     .11       0  1031.7     .04       0  1145.3     .11       0
Bank Sta=1031.7,1145.3
XS Rating Curve= 0 ,0
Exp/Cntr=0.3,0.1

Type RM Length L Ch R = 1 ,9484    ,484,484,484
XS GIS Cut Line= 3
      3838625.14     10093492.49      3837642.62     10094035.74
      3837407.43     10094601.93
#Sta/Elev= 30
       0  140.86       5  140.55    10.7  136.65    26.8  137.21    32.5  134.58
    48.5  133.02   314.3  131.83     336  131.17   357.8  127.91   363.5  130.18
   526.2  131.15   601.8  133.73   968.2   126.1  1035.9  127.73  1057.6  123.07
  1063.3  116.86  1079.4  118.81  1085.1  115.48  1101.2  116.42  1106.9  114.19
  1128.5  113.62  1170.3  126.32  1236.8  123.63  1305.9     127  1353.6  122.85
  1382.9  123.95  1399.2  127.21  1489.1  127.08  1542.3  130.24  1735.8   134.1
#Mann= 3 , 0 , 0
       0     .11       0  1035.9     .04       0  1170.3     .11       0
Bank Sta=1035.9,1170.3
XS Rating Curve= 0 ,0
Exp/Cntr=0.3,0.1

Type RM Length L Ch R = 1 ,9000    ,500,500,500
XS GIS Cut Line= 3
      3838450.34     10093452.62      3837332.79     10093756.64
      3836916.49     10094532.12
#Sta/Elev= 30
       0  138.73    15.6  139.52    50.2  130.72   129.8  133.43   375.7  133.03
   406.8  128.25   437.8  132.05   472.2  127.23   489.7  129.73   541.4  127.06
   551.8  129.67   707.3  131.82     780  126.19     842  127.06   873.1   123.1
  1082.7  125.62  1101.1  123.02  1122.5  113.66  1151.9   113.1  1179.7  116.03
    1196  121.84  1217.9  123.69  1245.5  121.26  1276.7   126.2  1349.4  131.41
  1519.1   132.4  1535.3   129.3  1579.2  132.65  1946.3   130.9  2038.3  133.89
#Mann= 3 , 0 , 0
       0     .11       0  1082.7     .04       0  1276.7     .11       0
Bank Sta=1082.7,1276.7
XS Rating Curve= 0 ,0
Exp/Cntr=0.3,0.1

Type RM Length L Ch R = 1 ,8500    ,500,500,500
XS GIS Cut Line= 3
      3838429.51     10093334.56      3837167.91      10093557.5
      3835838.85     10094009.09
#Sta/Elev= 30
       0  141.11    72.8  133.88   245.4  129.46   316.5  129.13     347  132.23
   631.3  125.66   643.7  127.67   682.1   125.7   702.9  128.85     757  128.83
   929.5  122.62  1096.9  123.94  1118.7   120.5  1149.2  124.27    1200  123.64
  1215.3  118.52  1240.6  118.71  1278.6  112.29  1302.3  115.15  1339.1  114.53
  1376.3  124.75  1407.9  123.61  1433.2  125.35  1450.2  129.56  1545.2  131.65
  1773.2  131.56  1898.7  128.73  2495.8  132.25    2610  130.46  2684.8  133.07
#Mann= 3 , 0 , 0
       0     .11       0    1200     .04       0  1376.3     .11       0
Bank Sta=1200,1376.3
XS Rating Curve= 0 ,0
Exp/Cntr=0.3,0.1

Type RM Length L Ch R = 1 ,8000    ,478,478,478
XS GIS Cut Line= 3
      3837547.57     10092869.29      3836880.12     10093248.95
       3835303.6     10093961.41
#Sta/Elev= 30
       0  132.77    68.7  131.88     171  122.55   176.8  125.33     220  122.32
   257.5  126.42   359.8  122.15   434.8  125.88     478  120.39   645.2  124.02
   666.9   119.1   725.9  120.66   766.3  111.63   803.3  117.57   814.6  124.05
    1005  123.38  1066.7  127.72  1165.4  123.22  1218.5  125.65  1286.1  123.57
  1626.3  132.22  1714.1  129.02  1857.9  129.17  1898.7  132.03  1933.6  128.16
  2065.3  131.02  2394.5  129.37  2434.6  122.13  2480.9  132.99  2497.9  133.33
#Mann= 3 , 0 , 0
       0     .11       0   645.2     .04       0   814.6     .11       0
Bank Sta=645.2,814.6
XS Rating Curve= 0 ,0
Exp/Cntr=0.3,0.1

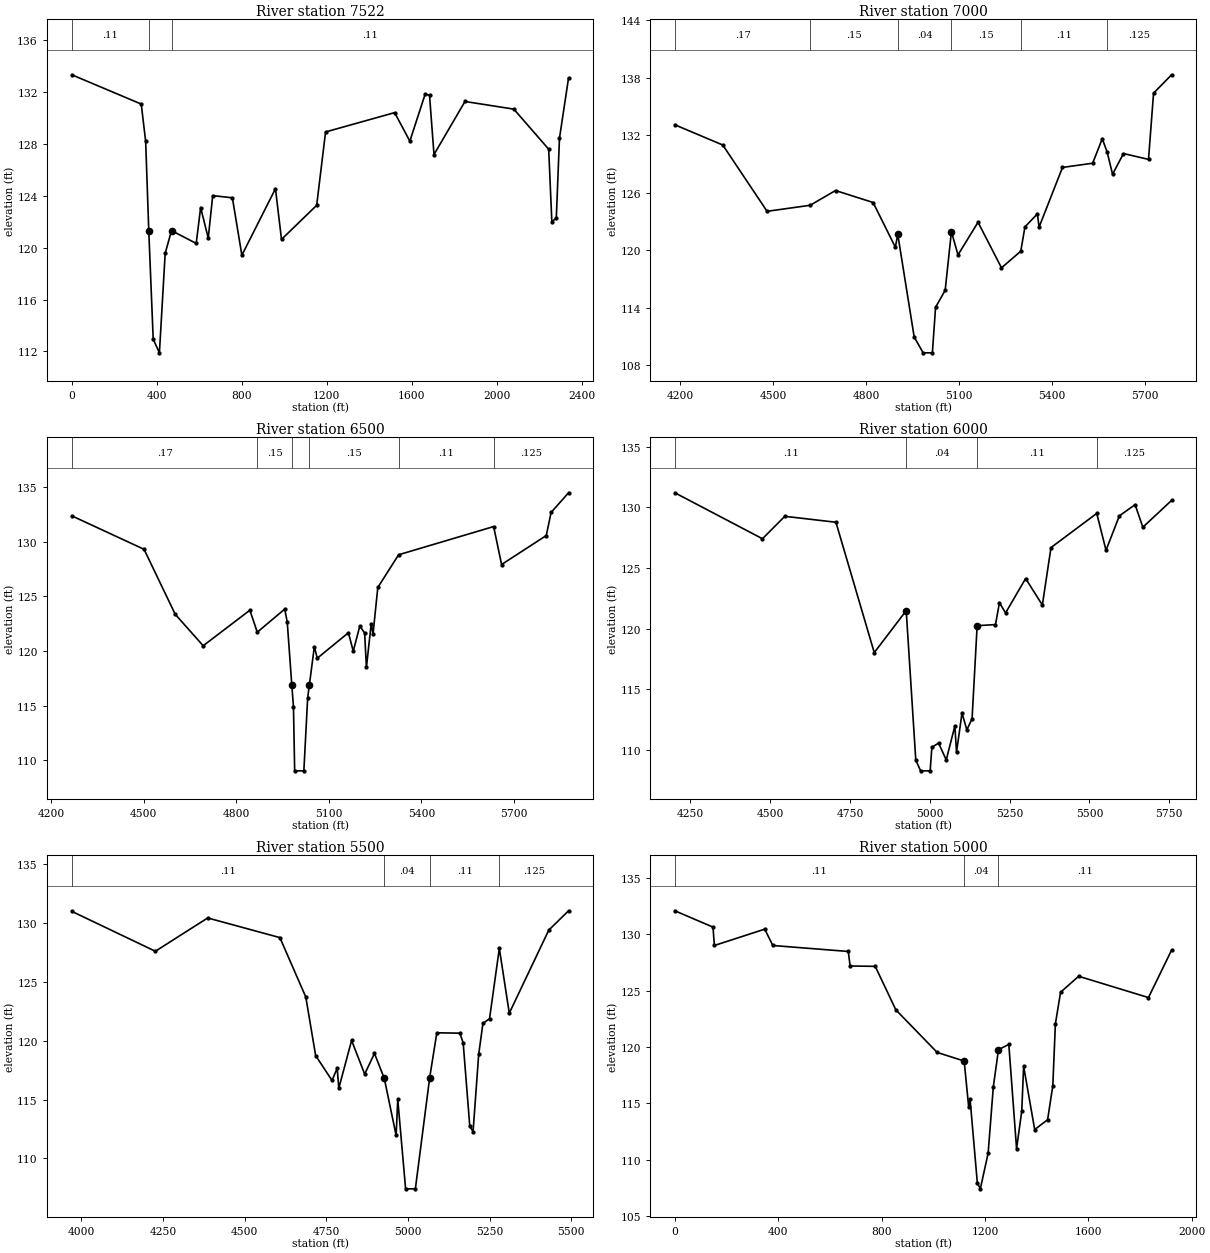
Type RM Length L Ch R = 1 ,7522    ,522,522,522
XS GIS Cut Line= 3
      3837221.18     10092598.45      3836887.34     10092845.98
      3835307.34     10093940.15
#Sta/Elev= 30
       0  133.34   326.7  131.08   347.5   128.2   362.2  121.27     383  112.94
   412.2  111.89   439.3  119.56   469.1  121.32   585.3  120.33   606.2   123.1
     642  120.74     663  124.02   755.6  123.85   800.2  119.42   958.3  124.55
   986.7  120.64  1152.2  123.27  1194.1  128.93  1519.1  130.42  1590.7  128.22
  1662.3  131.83  1683.2  131.77  1704.3  127.19  1850.1  131.28  2079.9  130.69
    2244   127.6  2258.9  121.98  2279.9  122.31  2294.7  128.44  2337.5   133.1
#Mann= 3 , 0 , 0
       0     .11       0   362.2     .04       0   469.1     .11       0
Bank Sta=362.2,469.1
XS Rating Curve= 0 ,0
Exp/Cntr=0.3,0.1

Type RM Length L Ch R = 1 ,7000    ,500,500,500
BEGIN DESCRIPTION:
STEWARTS CREEK 14.0
END DESCRIPTION:
XS GIS Cut Line= 3
      3837144.82     10092487.32      3836421.43     10092865.76
      3835661.66     10093065.14
#Sta/Elev= 30
  4183.6  133.09  4338.2  130.98  4481.1  124.06    4620  124.69  4701.8  126.23
    4823  124.98  4894.8  120.31  4902.5  121.66  4955.4  110.95  4984.3  109.29
  5014.1  109.29  5024.4  114.04  5055.4  115.82  5075.5  121.94  5096.7  119.51
  5161.4  122.92    5237  118.16  5299.2   119.9  5312.6  122.43  5352.9   123.8
  5358.1   122.4  5433.7  128.64    5531  129.08    5562  131.64  5577.9  130.22
  5595.2  127.93  5630.4  130.09  5711.1  129.48  5727.4  136.39  5785.5  138.31
#Mann= 6 ,-1 , 0
  4183.6     .17       0    4620     .15       0  4902.5     .04       0
  5075.5     .15       0  5299.2     .11       0  5577.9    .125       0
Bank Sta=4902.5,5075.5
XS Rating Curve= 0 ,0
Exp/Cntr=0.3,0.1

Type RM Length L Ch R = 1 ,6500    ,500,500,500
BEGIN DESCRIPTION:
STEWARTS CREEK 13.0
END DESCRIPTION:
XS GIS Cut Line= 3
      3837150.02     10092367.55      3836423.43     10092461.98
      3835671.88     10092913.79
#Sta/Elev= 30
  4267.3  132.35  4501.4  129.29  4602.3  123.35    4693  120.47  4844.3  123.72
  4868.2  121.71  4957.2  123.82  4965.3  122.65  4980.2116.8358  4985.5  114.91
  4989.4  109.03  5019.2  109.03  5031.5   115.7  5037.1 116.895  5053.2  120.39
  5062.6  119.33  5163.6  121.66  5179.2  119.97  5200.5  122.28  5216.1  121.63
  5221.9  118.49  5237.4  122.48  5243.3  121.54  5258.8   125.8  5326.2  128.79
  5634.1  131.37  5659.9   127.9  5804.7  130.55  5820.3  132.66  5876.9  134.46
#Mann= 6 ,-1 , 0
  4267.3     .17       0  4868.2     .15       0  4980.2     .04       0
  5037.1     .15       0  5326.2     .11       0  5634.1    .125       0
Bank Sta=4980.2,5037.1
XS Rating Curve= 0 ,0
Exp/Cntr=0.3,0.1

Type RM Length L Ch R = 1 ,6000    ,500,500,500
BEGIN DESCRIPTION:
STEWARTS CREEK 12.0
END DESCRIPTION:
XS GIS Cut Line= 3
      3837202.11     10092049.84      3836403.92     10092081.22
      3835682.01     10092310.02
#Sta/Elev= 30
  4201.2   131.2  4475.7  127.41  4545.7  129.26  4705.8  128.77  4825.9  118.02
    4926  121.48    4956  109.15  4971.2  108.27    5001  108.27  5006.4  110.21
  5027.4  110.56  5051.4  109.17  5078.4  111.97  5083.6   109.8  5100.8  113.04
  5115.9  111.65  5132.3  112.56  5148.2  120.24  5205.7  120.33    5218  122.14
  5237.2  121.29  5300.1  124.13  5352.5  121.94  5379.5  126.68  5522.9   129.5
  5551.9  126.46  5593.8   129.3    5643  130.22  5667.3  128.36  5757.3  130.57
#Mann= 4 ,-1 , 0
  4201.2     .11       0    4926     .04       0  5148.2     .11       0
  5522.9    .125       0
Bank Sta=4926,5148.2
XS Rating Curve= 0 ,0
Exp/Cntr=0.3,0.1

Type RM Length L Ch R = 1 ,5500    ,500,500,500
BEGIN DESCRIPTION:
STEWARTS CREEK 11.0
END DESCRIPTION:
XS GIS Cut Line= 3
      3837233.28     10091831.09      3836205.76     10091774.14
      3835717.82     10091711.07
#Sta/Elev= 30
  3970.9     131  4226.7  127.61    4387  130.44    4608  128.77  4687.4  123.72
  4717.5  118.75  4767.6  116.63  4783.5  117.66  4788.5  115.97  4827.6  120.03
  4867.7  117.17  4897.7  118.93  4927.8   116.8    4964  111.96    4969  115.02
    4993  107.42  5022.9  107.42  5066.8116.8799  5088.6  120.68  5159.2  120.65
  5169.3  119.82  5189.5  112.75  5199.6  112.28  5216.8  118.85  5229.8  121.48
    5250  121.88    5280  127.85  5310.5  122.35  5431.5  129.41    5492  131.05
#Mann= 4 ,-1 , 0
  3970.9     .11       0  4927.8     .04       0  5066.8     .11       0
    5280    .125       0
Bank Sta=4927.8,5066.8
XS Rating Curve= 0 ,0
Exp/Cntr=0.3,0.1

Type RM Length L Ch R = 1 ,5000    ,500,500,500
XS GIS Cut Line= 3
      3837311.46      10091648.8      3836172.99     10091312.48
      3835438.51     10091283.87
#Sta/Elev= 30
       0  132.09   147.7  130.64   152.9  129.01   347.9  130.46   379.1  129.01
   671.1  128.48   678.3  127.19   775.4  127.16   855.2   123.3  1015.2  119.52
  1119.5  118.76  1137.1  114.66  1142.3   115.4  1170.4  107.96    1182  107.42
  1212.3  110.58  1232.3  116.47  1252.3  119.77  1292.3  120.23  1322.3  110.99
  1342.4  114.32  1349.6   118.3  1392.4  112.68  1442.4  113.55  1462.5  116.56
  1472.5  122.05  1492.5  124.86  1562.5  126.28  1832.7  124.39  1922.1   128.6
#Mann= 3 , 0 , 0
       0     .11       0  1119.5     .04       0  1252.3     .11       0
Bank Sta=1119.5,1252.3
XS Rating Curve= 0 ,0
Exp/Cntr=0.3,0.1

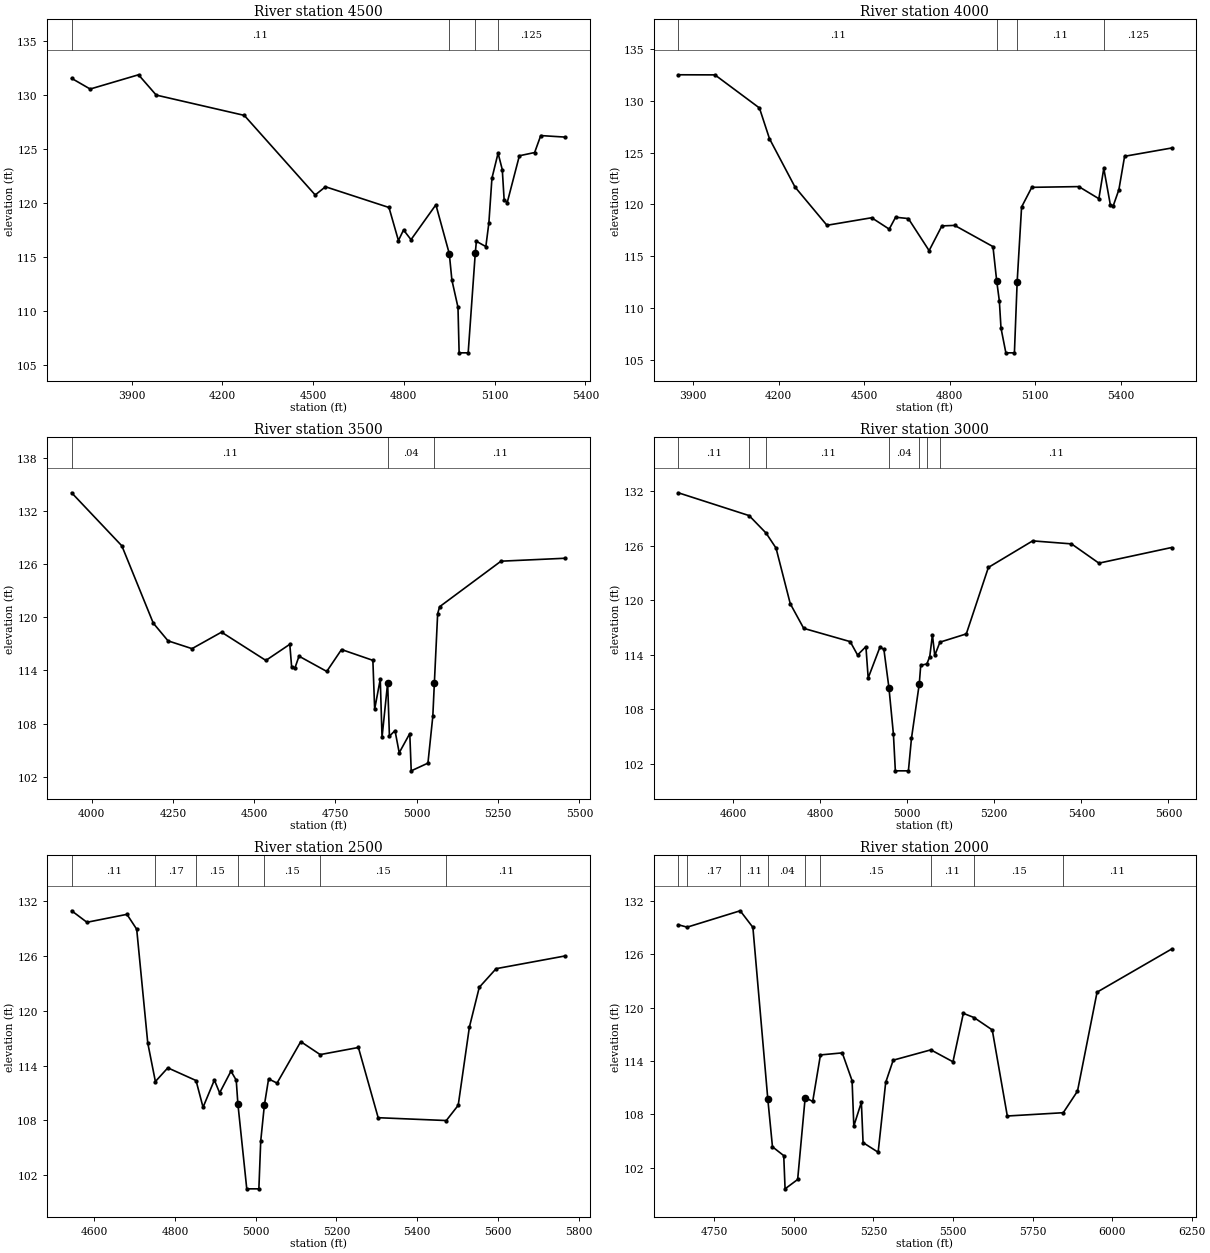
Type RM Length L Ch R = 1 ,4500    ,500,500,500
BEGIN DESCRIPTION:
STEWARTS CREEK 9.0
END DESCRIPTION:
XS GIS Cut Line= 3
      3837316.68      10091206.1      3836068.16     10090851.48
      3835738.53     10090810.26
#Sta/Elev= 30
  3702.1  131.54  3763.3  130.55  3923.1  131.87  3981.6  129.99  4272.6  128.11
    4507  120.74  4540.9   121.5  4750.8  119.58    4782  116.52  4798.9   117.5
  4823.6   116.6  4905.8  119.83  4950.1   115.3  4958.7  112.86  4978.8  110.34
  4982.6  106.12  5012.5  106.12 5035.97 115.361  5039.6  116.45  5070.9  115.96
  5080.9  118.15    5091  122.29  5111.3  124.61  5125.2  123.09  5131.3  120.31
  5141.4  120.02  5181.7  124.37  5232.1  124.67  5252.3  126.24  5332.2   126.1
#Mann= 4 ,-1 , 0
  3702.1     .11       0  4950.1     .04       0 5035.97     .11       0
  5111.3    .125       0
Bank Sta=4950.1,5035.97
XS Rating Curve= 0 ,0
Exp/Cntr=0.3,0.1

Type RM Length L Ch R = 1 ,4000    ,500,500,500
BEGIN DESCRIPTION:
STEWARTS CREEK 8.0
END DESCRIPTION:
XS GIS Cut Line= 3
      3837353.15     10090966.52      3836320.21     10090454.67
      3835743.71      10090398.8
#Sta/Elev= 30
  3847.2  132.54  3975.9  132.53  4132.1  129.33  4167.4  126.36    4257  121.69
  4369.1  117.99  4526.1  118.72  4587.8  117.62  4610.2  118.77    4655  118.64
  4727.9  115.54  4772.7  117.93  4817.6  117.98  4952.1  115.93  4965.3112.5833
  4974.5  110.68  4980.3  108.05  4997.4  105.66  5027.4  105.66  5037.1112.5532
  5052.6  119.76  5088.4  121.66  5253.5  121.73  5323.9  120.56  5341.2  123.49
  5364.1  119.99  5374.1  119.85  5394.2  121.43  5414.3  124.66  5579.2  125.46
#Mann= 4 ,-1 , 0
  3847.2     .11       0  4965.3     .04       0  5037.1     .11       0
  5341.2    .125       0
Bank Sta=4965.3,5037.1
XS Rating Curve= 0 ,0
Exp/Cntr=0.3,0.1

Type RM Length L Ch R = 1 ,3500    ,500,500,500
BEGIN DESCRIPTION:
STEWARTS CREEK 7.0
END DESCRIPTION:
XS GIS Cut Line= 3
      3837457.25     10090555.03      3836499.08      10090098.9
      3836243.74      10089721.7
#Sta/Elev= 30
  3938.8  134.05  4093.2  128.06  4189.8  119.34  4235.2  117.34  4308.9  116.46
  4399.7  118.32    4536  115.13  4609.6  116.95  4615.2   114.4  4624.8  114.22
  4637.9  115.61  4723.2  113.89  4768.6  116.36    4865  115.14  4870.5  109.63
  4887.7  113.01  4893.2  106.46  4910.4  112.59  4915.9  106.58  4933.1  107.21
    4946  104.71  4978.5  106.88  4982.9  102.67  5034.3  103.54  5049.3  108.82
 5054.13112.6272  5064.2   120.4  5070.2  121.19  5258.9  126.33  5455.5  126.66
#Mann= 3 , 0 , 0
  3938.8     .11       0  4910.4     .04       0 5054.13     .11       0
Bank Sta=4910.4,5054.13
XS Rating Curve= 0 ,0
Exp/Cntr=0.3,0.1

Type RM Length L Ch R = 1 ,3000    ,500,500,500
BEGIN DESCRIPTION:
STEWARTS CREEK 6.0
END DESCRIPTION:
XS GIS Cut Line= 3
      3837357.42     10090021.19      3836847.12     10089894.04
       3836268.9     10089708.69
#Sta/Elev= 30
  4474.1  131.83  4636.8  129.32  4675.7   127.4  4698.6  125.75  4731.3  119.63
  4762.2  116.92    4869  115.46  4885.9  113.99  4905.1  114.91  4910.3  111.46
  4937.4  114.87  4946.4   114.6    4958  110.38  4968.3  105.27  4972.7  101.25
  5002.7  101.25  5009.7  104.81 5027.64110.8083    5031  112.85  5045.1  113.01
  5051.7  113.81  5057.9   116.2  5063.2  113.94  5075.1   115.4  5135.7  116.31
  5186.4  123.62  5288.1  126.54  5377.3  126.21  5440.3  124.09  5607.2  125.81
#Mann= 7 ,-1 , 0
  4474.1     .11       0  4636.8     .15       0  4675.7     .11       0
    4958     .04       0 5027.64     .11       0  5045.1     .15       0
  5075.1     .11       0
Bank Sta=4958,5027.64
XS Rating Curve= 0 ,0
Exp/Cntr=0.3,0.1

Type RM Length L Ch R = 1 ,2500    ,500,500,500
BEGIN DESCRIPTION:
STEWARTS CREEK 5.0
END DESCRIPTION:
XS GIS Cut Line= 3
      3837450.74     10089555.04      3837008.35     10089443.65
      3836274.59     10089663.55
#Sta/Elev= 30
  4543.8  130.96  4581.7   129.7  4680.8  130.57    4705  128.94  4732.4  116.48
  4751.3  112.26  4782.1  113.76    4852  112.37  4869.4  109.44  4897.4  112.42
  4910.5  111.02  4938.6   113.4  4951.6  112.41 4955.64109.8442  4977.7  100.51
  5007.7  100.51  5012.3  105.75  5021.4   109.7  5031.8  112.55  5052.7  112.09
  5111.5  116.63  5159.6  115.21  5254.3  115.99  5303.3   108.3  5472.1  107.99
  5501.6  109.66  5529.3  118.22  5553.8  122.58  5595.5  124.62    5766  126.01
#Mann= 7 ,-1 , 0
  4543.8     .11       0  4751.3     .17       0    4852     .15       0
 4955.64     .04       0  5021.4     .15       0  5159.6     .15       0
  5472.1     .11       0
Bank Sta=4955.64,5021.4
XS Rating Curve= 0 ,0
Exp/Cntr=0.3,0.1

Type RM Length L Ch R = 1 ,2000    ,500,500,500
BEGIN DESCRIPTION:
STEWARTS CREEK 4.0
END DESCRIPTION:
XS GIS Cut Line= 3
      3837676.52     10089303.33      3837338.16     10089172.98
      3836245.85     10089636.81
#Sta/Elev= 30
  4637.4   129.3  4665.2  129.03  4831.8  130.87  4871.7  129.01 4918.56109.7205
  4933.2  104.36  4968.6  103.37  4972.8   99.64  5012.3  100.69  5035.9  109.88
  5059.6  109.46  5083.9  114.68  5152.4  114.91  5183.3  111.78  5188.7  106.69
  5212.4  109.36  5217.8  104.83  5265.1  103.75  5288.8  111.59  5312.4  114.09
  5430.7  115.25  5500.1  113.91  5532.7  119.35  5566.2  118.88  5623.5  117.49
  5670.8  107.82  5846.5  108.19  5891.2  110.61  5952.7  121.73  6186.7  126.57
#Mann= 9 ,-1 , 0
  4637.4     .11       0  4665.2     .17       0  4831.8     .11       0
 4918.56     .04       0  5035.9     .11       0  5083.9     .15       0
  5430.7     .11       0  5566.2     .15       0  5846.5     .11       0
Bank Sta=4918.56,5035.9
XS Rating Curve= 0 ,0
Exp/Cntr=0.3,0.1

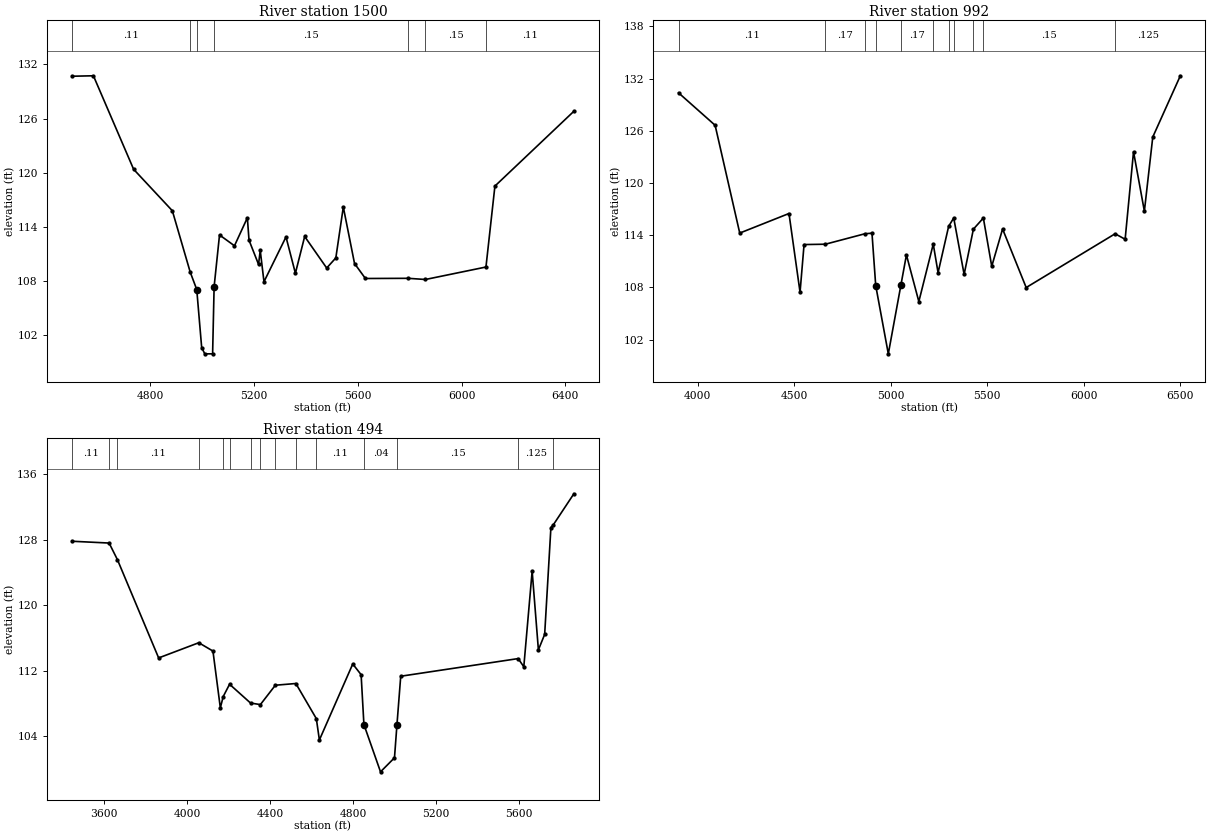
Type RM Length L Ch R = 1 ,1500    ,508,508,508
BEGIN DESCRIPTION:
STEWARTS CREEK 3.0
END DESCRIPTION:
XS GIS Cut Line= 3
      3837781.74     10088926.15      3837338.37     10088695.46
      3836222.68     10089593.96
#Sta/Elev= 30
  4500.2  130.69  4582.4  130.74  4737.2  120.39  4886.3   115.8  4955.1  109.01
  4980.3  107.08  4999.3  100.65  5011.3   99.96  5041.4   99.96  5047.2  107.39
    5068  113.12  5125.6  111.92  5175.2  115.02  5181.6  112.54  5218.3  109.86
  5224.8  111.41  5239.2  107.94    5324   112.9  5360.2  108.88  5395.9  112.95
  5480.7  109.46  5515.9  110.58  5544.7  116.21  5587.9  109.96  5629.8   108.3
  5794.6  108.32  5860.9  108.19    6094  109.57  6128.5  118.53  6432.5  126.81
#Mann= 7 ,-1 , 0
  4500.2     .11       0  4955.1     .15       0  4980.3     .04       0
  5047.2     .15       0  5794.6     .11       0  5860.9     .15       0
    6094     .11       0
Bank Sta=4980.3,5047.2
XS Rating Curve= 0 ,0
Exp/Cntr=0.3,0.1

Type RM Length L Ch R = 1 ,992     ,498,498,498
BEGIN DESCRIPTION:
STEWARTS CREEK 2.0
END DESCRIPTION:
XS GIS Cut Line= 3
       3837877.2      10088878.4      3837233.76     10088344.11
      3835836.18     10089420.51
#Sta/Elev= 30
    3901  130.37  4090.6  126.64  4218.2  114.25  4473.4   116.5  4530.7  107.45
  4551.5  112.93  4661.8  112.97  4866.5  114.17  4903.5  114.24 4922.81108.2242
  4988.1  100.37    5053  108.23    5082  111.74  5146.3  106.38    5221  112.98
    5246   109.7  5300.7  115.02  5327.1  115.99    5381   109.5    5429   114.7
  5480.7  115.98  5524.1  110.43  5580.3  114.72  5702.6  107.99  6163.4  114.17
  6215.4  113.54  6258.9   123.6  6315.1  116.77  6358.6  125.29  6501.4  132.33
#Mann= 11 ,-1 , 0
    3901     .11       0  4661.8     .17       0  4866.5     .15       0
 4922.81     .04       0    5053     .17       0    5221     .15       0
  5300.7     .17       0  5327.1     .15       0    5429     .17       0
  5480.7     .15       0  6163.4    .125       0
Bank Sta=4922.81,5053
XS Rating Curve= 0 ,0
Exp/Cntr=0.3,0.1

Type RM Length L Ch R = 1 ,494     ,0,0,0
BEGIN DESCRIPTION:
STEWARTS CREEK 1.0
END DESCRIPTION:
XS GIS Cut Line= 3
      3838017.85     10088861.07      3837334.68       10088210.
      3835867.85     10088061.07
#Sta/Elev= 30
  3446.6  127.82  3625.1   127.6  3665.3  125.56  3863.8  113.54  4057.2   115.4
  4125.5  114.38  4161.1  107.43  4175.1  108.82  4205.6  110.32  4306.6  108.02
  4354.1  107.83  4426.2   110.2    4525  110.41  4623.7  106.11  4638.4   103.5
  4799.2   112.8  4839.5  111.49 4852.98105.3905    4933    99.6  5000.3  101.32
 5012.18105.3616  5030.4   111.3  5596.3  113.46  5623.5  112.46  5663.7  124.16
  5693.8  114.53    5724  116.42  5754.1   129.5  5766.2  129.85  5864.7  133.63
#Mann= 15 ,-1 , 0
  3446.6     .11       0  3625.1     .17       0  3665.3     .11       0
  4057.2     .17       0  4175.1     .11       0  4205.6     .15       0
  4306.6     .11       0  4354.1     .17       0  4426.2     .11       0
    4525     .17       0  4623.7     .11       0 4852.98     .04       0
 5012.18     .15       0  5596.3    .125       0  5766.2     .15       0
Bank Sta=4852.98,5012.18
XS Rating Curve= 0 ,0
Exp/Cntr=0.3,0.1

Chan Stop Cuts=-1
Use User Specified Reach Order=0
Composite Channel Slope=5

--- STEWARTS CREEK.g10 (geometry) ---

Geom Title=Existing Conditions
Program Version=4.10

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
River Reach=STEWARTS CREEK  ,Reach-1

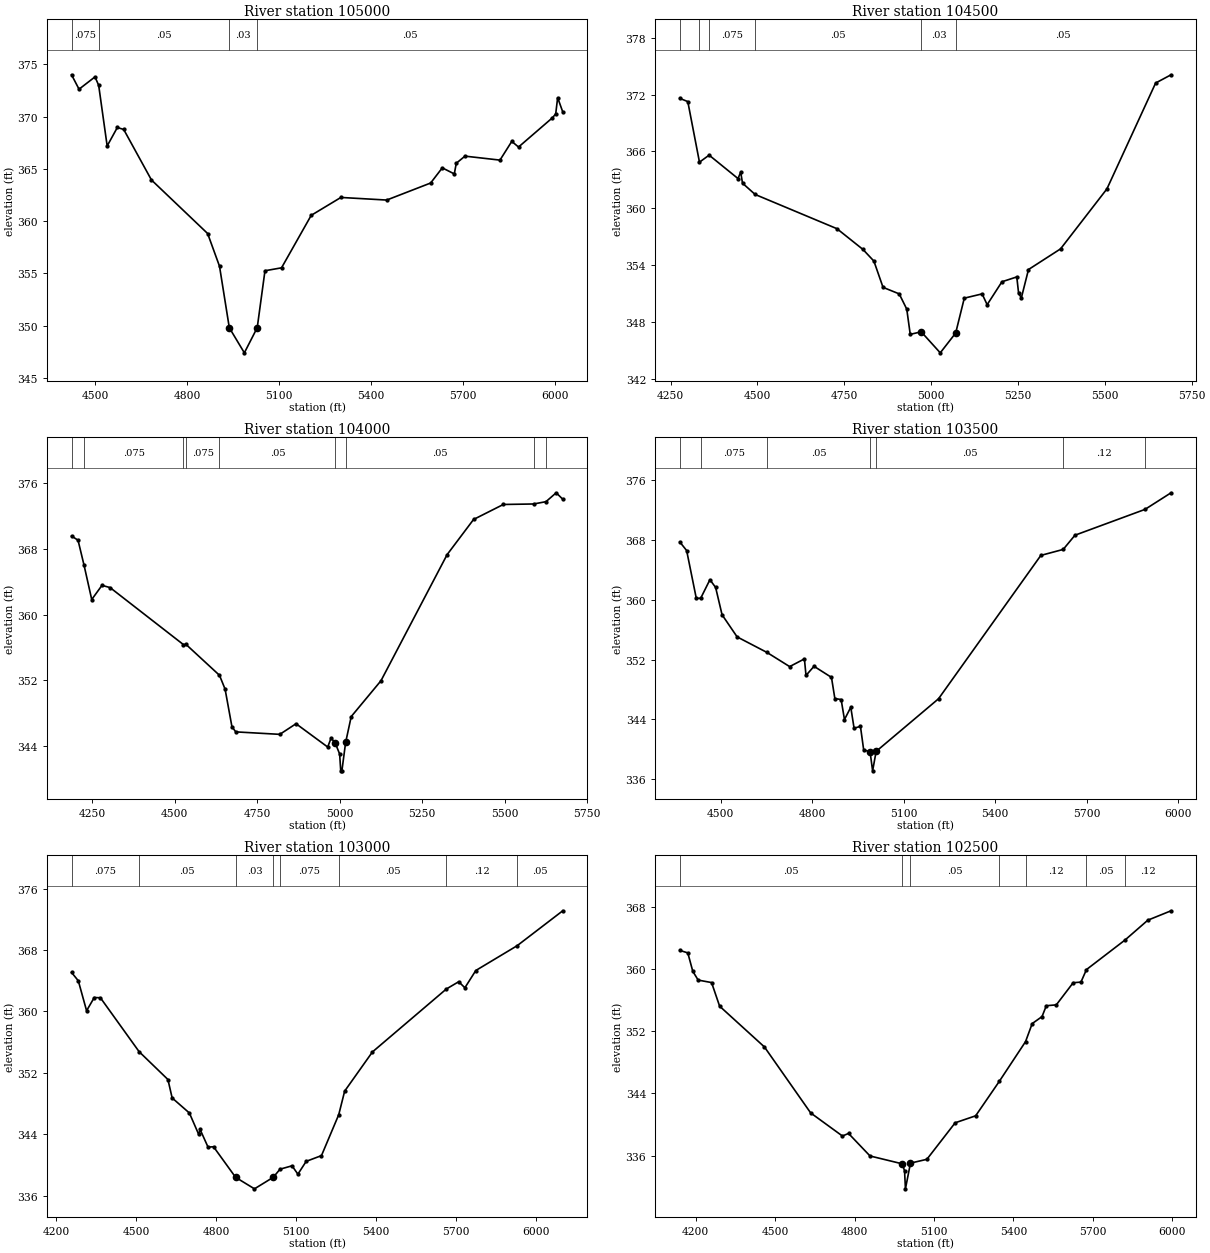
Type RM Length L Ch R = 1 ,105000  ,500,500,500
BEGIN DESCRIPTION:
STEWARTS CREEK 207.0
END DESCRIPTION:
XS GIS Cut Line= 3
      3821291.42     10152679.38       3820736.9     10152518.42
      3819807.06     10152952.79
#Sta/Elev= 30
  4422.6  373.99  4447.1  372.61  4499.2  373.79  4511.2  372.98  4538.9  367.18
  4572.1  368.95  4592.9  368.76  4683.5  363.93  4866.9  358.81  4905.7  355.68
 4937.68 349.799  4986.8   347.4 5028.84 349.807  5054.1  355.25  5108.2  355.53
  5205.1  360.55    5302  362.26  5451.5  362.01    5595  363.64    5633  365.09
  5672.2  364.51  5678.7  365.53  5707.1  366.21  5821.3  365.83  5859.9  367.62
  5881.9  367.08  5992.3  369.87  6003.3  370.25  6009.6   371.8  6026.3  370.44
#Mann= 4 ,-1 , 0
  4422.6    .075       0  4511.2     .05       0 4937.68     .03       0
 5028.84     .05       0
Bank Sta=4937.68,5028.84
XS Rating Curve= 0 ,0
Exp/Cntr=0.3,0.1

Type RM Length L Ch R = 1 ,104500  ,500,500,500
BEGIN DESCRIPTION:
STEWARTS CREEK 206.0
END DESCRIPTION:
XS GIS Cut Line= 3
      3821356.48      10152262.7      3820670.88     10152032.23
      3819997.98     10151876.42
#Sta/Elev= 30
  4276.7   371.6  4299.6  371.26  4333.2  364.87    4361  365.61  4444.1  363.14
  4451.9  363.81  4457.1  362.65  4493.5  361.46  4728.9  357.85  4803.8  355.66
  4835.3  354.43  4861.6  351.66  4908.2  350.97  4929.9  349.36  4939.9   346.7
  4971.5  346.97  5026.3  344.75  5070.7  346.84  5095.5  350.52  5146.8  350.97
  5161.3  349.83  5203.9  352.25  5246.6  352.76  5251.8  351.06  5259.7  350.54
  5280.3  353.54  5372.6  355.72  5506.1  362.05  5646.3  373.22  5690.7  374.09
#Mann= 6 ,-1 , 0
  4276.7    .075       0  4333.2     .05       0    4361    .075       0
  4493.5     .05       0  4971.5     .03       0  5070.7     .05       0
Bank Sta=4971.5,5070.7
XS Rating Curve= 0 ,0
Exp/Cntr=0.3,0.1

Type RM Length L Ch R = 1 ,104000  ,500,500,500
BEGIN DESCRIPTION:
STEWARTS CREEK 205.0
END DESCRIPTION:
XS GIS Cut Line= 3
      3821496.85     10151806.53      3820712.92     10151591.83
        3820038.     10151547.01
#Sta/Elev= 30
  4187.2  369.54  4206.9  369.03  4225.1     366  4248.4  361.83  4279.5  363.55
    4304  363.28  4526.3  356.36  4534.5  356.37  4635.7  352.63  4652.7  350.95
  4673.5  346.38  4685.1  345.76  4818.6  345.46  4867.8  346.75  4963.8  343.92
  4974.1  345.01  4986.8  344.39    5000  343.07  5003.3  341.03  5006.8  341.03
  5018.1 344.471  5035.1  347.62  5125.3  351.97  5325.8  367.28    5406  371.55
  5496.2  373.37  5587.9  373.43  5625.5  373.71  5656.5  374.79  5676.4  374.01
#Mann= 9 ,-1 , 0
  4187.2     .05       0  4225.1    .075       0  4526.3     .05       0
  4534.5    .075       0  4635.7     .05       0  4986.8     .07       0
  5018.1     .05       0  5587.9     .12       0  5625.5     .05       0
Bank Sta=4986.8,5018.1
XS Rating Curve= 0 ,0
Exp/Cntr=0.3,0.1

Type RM Length L Ch R = 1 ,103500  ,500,500,500
BEGIN DESCRIPTION:
STEWARTS CREEK 204.0
END DESCRIPTION:
XS GIS Cut Line= 3
      3821599.03     10151456.57      3820993.88       10151253.
      3820038.02     10151429.05
#Sta/Elev= 30
  4366.4  367.71  4388.7  366.57  4420.4  360.17  4434.8   360.2    4465  362.67
  4483.7  361.64  4504.8  357.99  4554.2  355.03  4652.2  352.95  4726.4  351.06
  4774.8  352.09    4780  349.88  4806.3   351.1  4863.5  349.62  4874.6  346.79
  4895.2  346.66  4906.1  343.98  4926.8  345.63  4937.6  342.83  4958.5  343.07
  4969.1  339.92    4990  339.68  4998.4  337.13 5009.94 339.729  5214.4  346.76
  5549.9  365.92  5623.2  366.72  5661.8  368.62  5891.4  372.07  5976.8  374.29
#Mann= 7 ,-1 , 0
  4366.4     .05       0  4434.8    .075       0  4652.2     .05       0
    4990     .07       0 5009.94     .05       0  5623.2     .12       0
  5891.4     .05       0
Bank Sta=4990,5009.94
XS Rating Curve= 0 ,0
Exp/Cntr=0.3,0.1

Type RM Length L Ch R = 1 ,103000  ,500,500,500
BEGIN DESCRIPTION:
STEWARTS CREEK 203.0
END DESCRIPTION:
XS GIS Cut Line= 3
      3821752.42     10150988.67      3821034.92     10150798.39
      3820031.48      10151247.6
#Sta/Elev= 30
  4257.7  365.07  4283.1  363.98  4314.1  360.08  4342.9   361.8  4365.9  361.77
    4511  354.75  4619.1  351.12  4634.9  348.72  4699.5  346.76  4734.6  343.96
  4739.7  344.61  4769.4  342.32  4790.1  342.36  4872.8  338.38  4943.5  336.88
 5013.95 338.383  5039.4  339.44  5084.4  339.88  5106.3  338.79  5137.5  340.46
  5194.8  341.21  5259.4  346.53  5281.7  349.61  5385.8  354.71  5662.9  362.91
  5709.3  363.86  5732.4  363.07  5773.4  365.32  5928.4  368.55  6099.4   373.1
#Mann= 8 ,-1 , 0
  4257.7    .075       0    4511     .05       0  4872.8     .03       0
 5013.95     .05       0  5039.4    .075       0  5259.4     .05       0
  5662.9     .12       0  5928.4     .05       0
Bank Sta=4872.8,5013.95
XS Rating Curve= 0 ,0
Exp/Cntr=0.3,0.1

Type RM Length L Ch R = 1 ,102500  ,500,500,500
BEGIN DESCRIPTION:
STEWARTS CREEK 202.0
END DESCRIPTION:
XS GIS Cut Line= 3
      3821776.01     10150241.58      3820928.35     10150387.32
      3820006.55     10150764.56
#Sta/Elev= 30
  4139.9   362.4    4170  362.08  4188.8  359.71  4209.1  358.58  4259.8  358.26
  4290.2  355.22  4459.6  349.97  4634.3  341.48  4754.2  338.51  4777.3  338.84
  4858.5  335.94  4980.2  334.93    4989  334.03  4992.3  331.71  5011.3  335.02
  5073.3  335.51  5180.2  340.21  5257.6  341.11  5347.5  345.57  5446.2  350.66
  5471.3  352.98  5508.4  353.88  5524.7  355.28  5562.4  355.39  5626.1  358.24
  5655.5  358.32  5676.3  359.93  5822.2  363.74  5908.2  366.29    5996   367.5
#Mann= 7 ,-1 , 0
  4139.9     .05       0  4980.2     .07       0  5011.3     .05       0
  5347.5    .075       0  5446.2     .12       0  5676.3     .05       0
  5822.2     .12       0
Bank Sta=4980.2,5011.3
XS Rating Curve= 0 ,0
Exp/Cntr=0.3,0.1