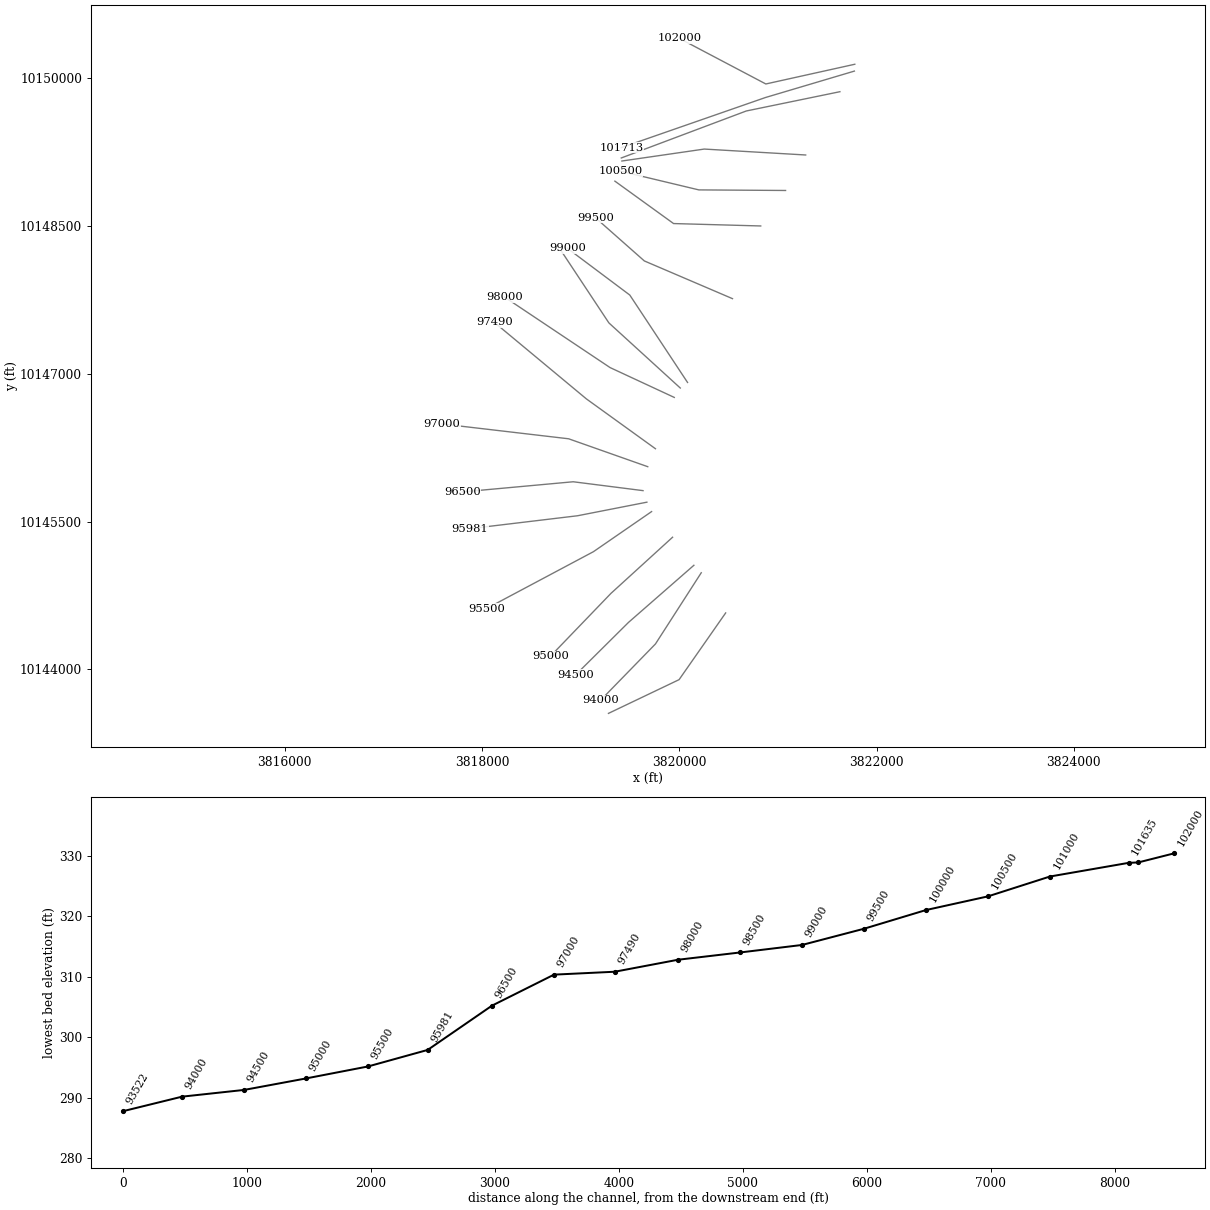
HEC-RAS study STEWARTS CREEK.prj: STEWARTS CREEK Base Level Engineering

--- STEWARTS CREEK.g10 (geometry) --- (continued)

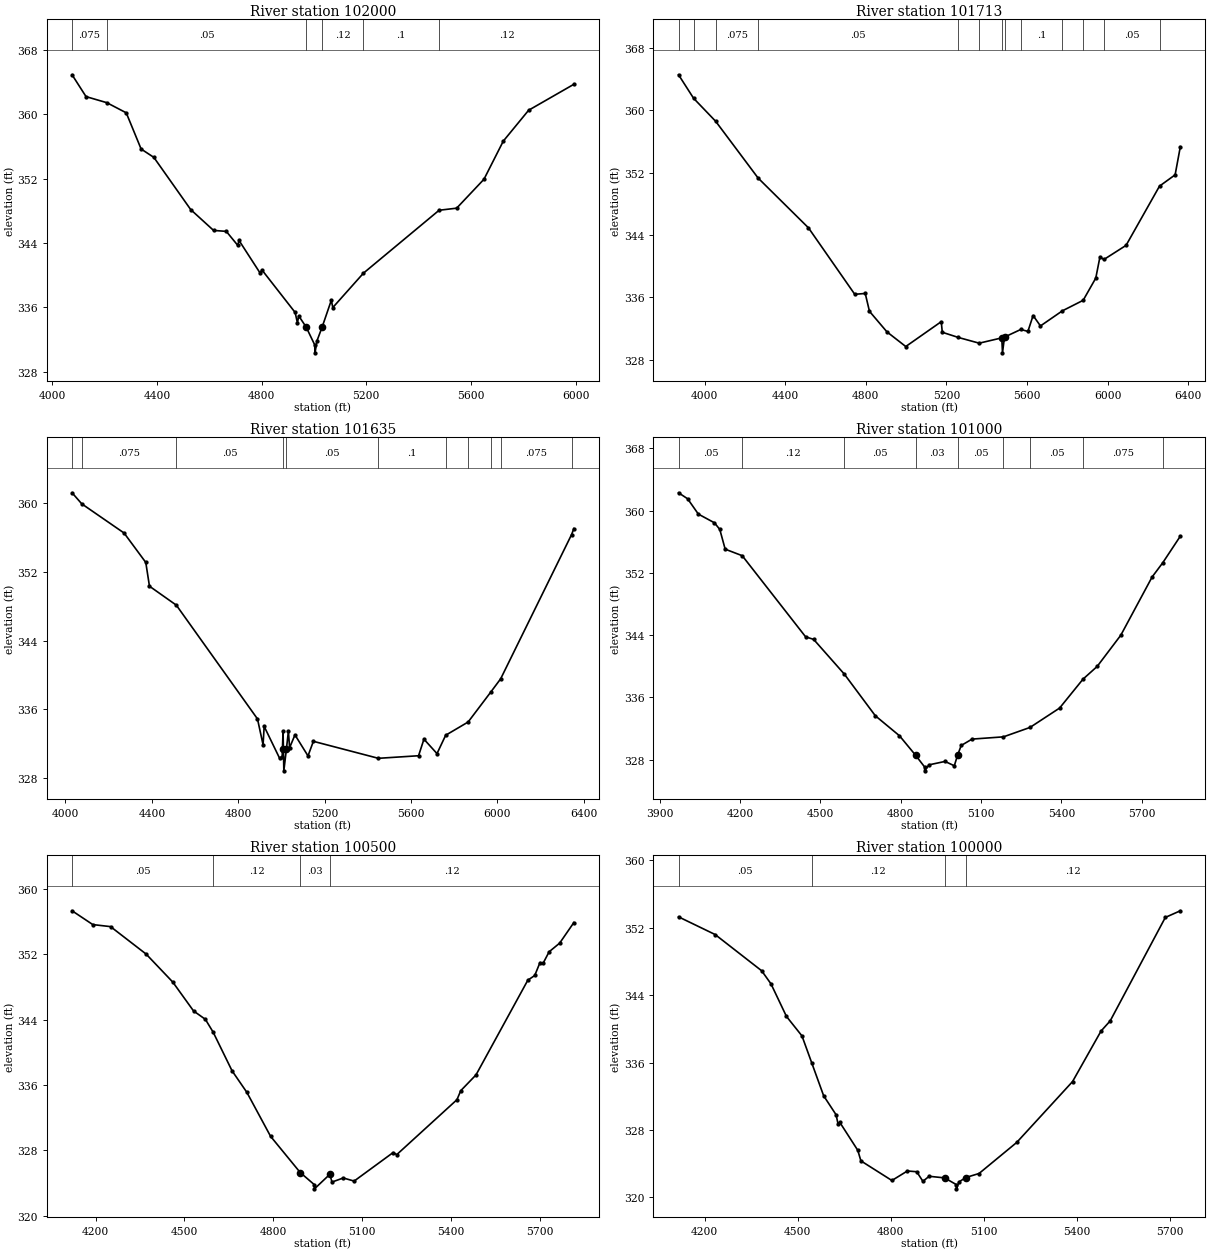
Type RM Length L Ch R = 1 ,102000  ,287,287,287
BEGIN DESCRIPTION:
STEWARTS CREEK 201.0
END DESCRIPTION:
XS GIS Cut Line= 3
      3821779.96     10150143.29      3820877.69     10149943.14
      3819999.37     10150406.39
#Sta/Elev= 30
  4075.8  364.87  4129.2  362.16  4208.4  361.41  4282.8  360.15  4339.6  355.66
  4388.3  354.62  4529.2  348.14  4616.4  345.56  4665.1  345.44  4708.7  343.71
  4713.8  344.31    4795  340.23  4800.9  340.67  4928.1  335.38  4936.8  334.09
  4941.9  334.95 4970.13  333.57  5002.7  331.37  5004.1  330.37  5011.5  331.86
 5031.34 333.575  5066.3  336.89    5072  335.99  5189.2  340.26  5478.1  348.06
  5545.2  348.32  5649.6  351.91  5723.4  356.64  5820.2  360.47    5993  363.69
#Mann= 6 ,-1 , 0
  4075.8    .075       0  4208.4     .05       0 4970.13     .07       0
 5031.34     .12       0  5189.2      .1       0  5478.1     .12       0
Bank Sta=4970.13,5031.34
XS Rating Curve= 0 ,0
Exp/Cntr=0.3,0.1

Type RM Length L Ch R = 1 ,101713  ,78,78,78
BEGIN DESCRIPTION:
Mapping XS 54c76c93
END DESCRIPTION:
XS GIS Cut Line= 3
      3821775.58     10150073.83      3820873.69     10149805.61
       3819411.5     10149296.53
#Sta/Elev= 30
  3870.8  364.56  3945.6  361.54  4054.7   358.6  4265.5  351.31  4515.3  344.92
    4745  336.39    4797   336.5  4817.9  334.21  4904.7  331.57    4998  329.69
    5174  332.88  5179.2  331.52  5259.3  330.85  5362.3  330.12  5474.3   330.8
  5477.8  328.88 5487.81 330.903  5568.7  331.88  5603.9  331.63  5629.7  333.67
  5666.1  332.33  5774.9  334.27    5878  335.62  5940.6  338.47  5961.1  341.17
  5981.2  340.86  6090.8  342.67  6256.7  350.27  6334.2  351.72    6360  355.33
#Mann= 13 ,-1 , 0
  3870.8    .075       0  3945.6      .1       0  4054.7    .075       0
  4265.5     .05       0  5259.3     .12       0  5362.3     .05       0
  5474.3     .07       0 5487.81     .05       0  5568.7      .1       0
  5774.9     .05       0    5878    .075       0  5981.2     .05       0
  6256.7    .075       0
Bank Sta=5474.3,5487.81
XS Rating Curve= 0 ,0
Exp/Cntr=0.3,0.1

Type RM Length L Ch R = 1 ,101635  ,635,635,635
BEGIN DESCRIPTION:
STEWARTS CREEK 200.0
END DESCRIPTION:
XS GIS Cut Line= 3
      3821628.91     10149864.64      3820679.56     10149669.01
      3819411.81     10149192.05
#Sta/Elev= 30
  4030.7  361.22  4075.6  359.93  4271.5  356.53  4372.1   353.1  4389.1  350.33
  4513.6  348.12  4889.4  334.86  4915.2  331.85  4920.3  333.99  4991.5  330.29
  5003.6  330.41  5007.8  333.45  5009.5 331.317  5011.4  328.81  5023.2  331.32
  5032.6  333.45    5038   331.5  5062.9     333  5123.3  330.55  5148.2  332.25
  5449.1  330.27  5635.3  330.57  5660.2   332.5  5720.7  330.82  5760.9  332.96
  5864.8   334.5  5968.8  337.96  6015.6  339.54    6344  356.35  6354.5  357.05
#Mann= 11 ,-1 , 0
  4030.7      .1       0  4075.6    .075       0  4513.6     .05       0
  5009.5     .05       0  5023.2     .05       0  5449.1      .1       0
  5760.9     .05       0  5864.8    .075       0  5968.8     .05       0
  6015.6    .075       0    6344     .05       0
Bank Sta=5009.5,5023.2
XS Rating Curve= 0 ,0
Exp/Cntr=0.3,0.1

Type RM Length L Ch R = 1 ,101000  ,500,500,500
BEGIN DESCRIPTION:
STEWARTS CREEK 199.0
END DESCRIPTION:
XS GIS Cut Line= 3
      3821281.71     10149222.27      3820253.37     10149282.39
      3819417.83     10149161.07
#Sta/Elev= 30
  3969.9   362.3  4003.8  361.53  4043.9  359.56    4104  358.44    4124  357.59
  4144.1  355.05  4207.8  354.21  4444.6  343.78  4474.6  343.45  4589.1  338.99
    4705  333.63  4795.2  331.06  4855.3  328.56    4889  327.05  4889.2  326.55
  4905.4  327.32  4965.5  327.76    5000   327.2 5012.21 328.554  5025.8  329.81
  5066.2  330.63  5183.6  330.92  5282.8  332.13  5393.3  334.62  5481.1  338.35
  5533.6  339.97    5622  343.99    5739  351.48  5778.6   353.3  5844.3  356.72
#Mann= 9 ,-1 , 0
  3969.9     .05       0  4207.8     .12       0  4589.1     .05       0
  4855.3     .03       0 5012.21     .05       0  5183.6     .12       0
  5282.8     .05       0  5481.1    .075       0  5778.6     .05       0
Bank Sta=4855.3,5012.21
XS Rating Curve= 0 ,0
Exp/Cntr=0.3,0.1

Type RM Length L Ch R = 1 ,100500  ,500,500,500
BEGIN DESCRIPTION:
STEWARTS CREEK 198.0
END DESCRIPTION:
XS GIS Cut Line= 3
      3821077.72     10148862.03      3820198.34     10148867.91
      3819406.69     10149057.34
#Sta/Elev= 30
  4120.6  357.31  4190.5  355.62  4250.5  355.37  4370.5  352.01  4460.5  348.58
  4530.5  345.05  4570.5  344.02  4596.7  342.45  4660.5  337.72  4710.5  335.08
  4790.5   329.7  4890.5  325.27  4938.5  323.77  4938.7  323.27  4990.5  325.05
  4997.7   324.1  5035.8   324.6  5072.5  324.22    5204  327.71  5216.4  327.46
  5419.4  334.18  5432.4  335.29  5483.8  337.22  5658.6  348.81    5682  349.39
  5699.7  350.97    5710  350.87  5730.5  352.29  5766.1  353.35    5814  355.87
#Mann= 4 ,-1 , 0
  4120.6     .05       0  4596.7     .12       0  4890.5     .03       0
  4990.5     .12       0
Bank Sta=4890.5,4990.5
XS Rating Curve= 0 ,0
Exp/Cntr=0.3,0.1

Type RM Length L Ch R = 1 ,100000  ,500,500,500
BEGIN DESCRIPTION:
STEWARTS CREEK 197.0
END DESCRIPTION:
XS GIS Cut Line= 3
      3820825.91     10148501.79      3819942.05     10148526.24
      3819346.87     10148956.82
#Sta/Elev= 30
  4115.8  353.29  4233.9  351.19    4384  346.89    4414  345.34    4464  341.47
    4514  339.16  4545.9  335.92    4584  332.05  4624.1   329.8  4630.7  328.65
  4635.7  328.92  4694.1  325.58  4704.1  324.33  4804.1     322  4854.1  323.13
  4884.2  323.04  4904.2   321.9  4924.2   322.5  4974.2  322.31  5012.1  321.51
  5012.3  321.01  5020.2  321.82  5042.2  322.35  5085.2  322.83  5206.6  326.51
  5386.9  333.74  5478.9  339.74  5508.3  340.94  5686.2  353.22  5734.6  354.01
#Mann= 4 ,-1 , 0
  4115.8     .05       0  4545.9     .12       0  4974.2     .03       0
  5042.2     .12       0
Bank Sta=4974.2,5042.2
XS Rating Curve= 0 ,0
Exp/Cntr=0.3,0.1

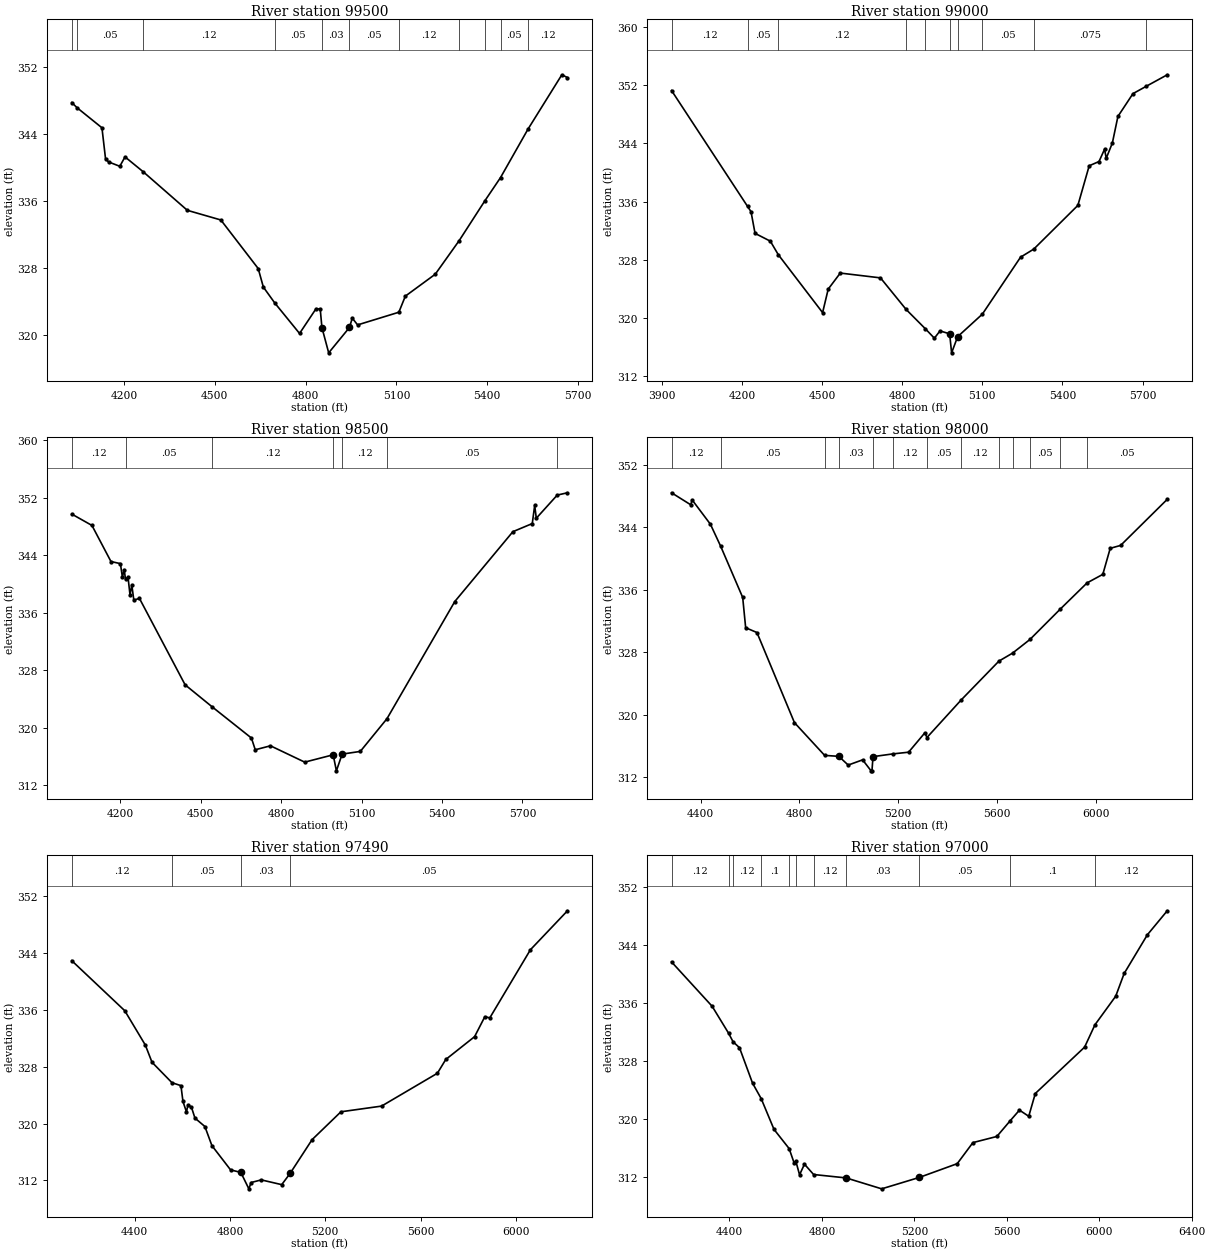
Type RM Length L Ch R = 1 ,99500   ,500,500,500
BEGIN DESCRIPTION:
STEWARTS CREEK 196.0
END DESCRIPTION:
XS GIS Cut Line= 3
      3820539.53     10147763.92      3819645.56     10148146.78
      3819147.69     10148587.33
#Sta/Elev= 30
  4027.5  347.76  4045.4  347.13  4127.2  344.75  4139.1  341.04    4149  340.68
  4186.2  340.16  4203.4  341.28  4263.7   339.5  4409.3  334.91  4519.9  333.76
  4643.3  327.97  4660.3  325.76  4698.1  323.86  4779.9  320.23  4834.3  323.18
  4848.2  323.13 4853.75 320.938  4876.1  317.92  4944.7 320.942    4954  322.06
  4971.6  321.25  5107.8  322.76  5129.3  324.68    5228  327.29  5307.3  331.31
  5392.2  336.06  5443.6  338.81  5534.4  344.59  5646.2  351.07  5664.8  350.74
#Mann= 11 ,-1 , 0
  4027.5     .12       0  4045.4     .05       0  4263.7     .12       0
  4698.1     .05       0 4853.75     .03       0  4944.7     .05       0
  5107.8     .12       0  5307.3    .075       0  5392.2     .12       0
  5443.6     .05       0  5534.4     .12       0
Bank Sta=4853.75,4944.7
XS Rating Curve= 0 ,0
Exp/Cntr=0.3,0.1

Type RM Length L Ch R = 1 ,99000   ,500,500,500
BEGIN DESCRIPTION:
STEWARTS CREEK 195.0
END DESCRIPTION:
XS GIS Cut Line= 3
      3820083.77     10146913.23      3819498.08     10147800.56
      3818864.12     10148276.11
#Sta/Elev= 30
  3936.8  351.25  4221.4  335.34  4234.3  334.62  4249.4  331.64  4306.6  330.57
  4336.3  328.72  4502.3  320.76  4523.3  323.99  4568.5  326.19    4719  325.53
  4815.1  321.19  4886.5  318.56  4920.7  317.25  4941.8  318.25  4977.9  317.85
  4985.2  315.24  5007.9  317.46  5100.3  320.55  5243.3  328.37  5292.8  329.48
  5457.9  335.48  5500.3  340.92    5537   341.5  5557.8  343.19  5564.1  341.95
    5587  344.04  5607.8  347.69  5664.1  350.82  5714.3  351.84  5792.5  353.41
#Mann= 10 ,-1 , 0
  3936.8     .12       0  4221.4     .05       0  4336.3     .12       0
  4815.1     .05       0  4886.5     .12       0  4977.9     .07       0
  5007.9     .12       0  5100.3     .05       0  5292.8    .075       0
  5714.3     .05       0
Bank Sta=4977.9,5007.9
XS Rating Curve= 0 ,0
Exp/Cntr=0.3,0.1

Type RM Length L Ch R = 1 ,98500   ,500,500,500
BEGIN DESCRIPTION:
STEWARTS CREEK 194.0
END DESCRIPTION:
XS GIS Cut Line= 3
      3820009.99     10146856.81      3819286.26     10147517.58
      3818807.71     10148241.38
#Sta/Elev= 30
    4020   349.7  4095.2  348.12  4166.1   343.1  4201.3  342.81  4208.7  340.94
  4215.5  341.97  4220.3  340.62  4229.7  340.92  4237.1  338.47  4243.8  339.83
  4251.3  337.74  4272.2  337.98  4442.5  325.96  4542.9  322.91  4689.7  318.56
  4703.9  316.93  4760.7  317.48  4888.3  315.21  4994.4  316.23  5006.4     314
 5027.84 316.327  5095.5   316.7  5194.9  321.25  5447.7  337.54  5664.2  347.25
  5736.5  348.38  5745.5  350.91  5751.5  349.12  5829.6  352.34  5867.7  352.66
#Mann= 7 ,-1 , 0
    4020     .12       0  4220.3     .05       0  4542.9     .12       0
  4994.4     .07       0 5027.84     .12       0  5194.9     .05       0
  5829.6     .12       0
Bank Sta=4994.4,5027.84
XS Rating Curve= 0 ,0
Exp/Cntr=0.3,0.1

Type RM Length L Ch R = 1 ,98000   ,510,510,510
BEGIN DESCRIPTION:
STEWARTS CREEK 193.0
END DESCRIPTION:
XS GIS Cut Line= 3
      3819949.19     10146761.34      3819298.11     10147064.26
      3818226.11      10147781.3
#Sta/Elev= 30
  4281.9  348.45  4359.7  346.91  4365.2  347.54  4439.3  344.42  4480.7  341.61
  4570.1  335.03  4582.1  331.15  4627.9  330.53  4779.7  318.98    4902  314.78
  4959.3  314.66  4997.4  313.54  5055.8  314.21  5090.1   312.8  5093.7   312.8
  5097.9  314.62  5177.9  314.97    5242  315.19  5308.1  317.68  5316.3  317.07
  5454.8  321.88    5608  326.87    5663  327.89  5733.5  329.64  5856.5  333.54
  5965.1   336.9  6028.7  337.99  6058.7  341.33  6100.8   341.7  6289.7  347.61
#Mann= 13 ,-1 , 0
  4281.9     .12       0  4480.7     .05       0    4902     .12       0
  4959.3     .03       0  5097.9     .05       0  5177.9     .12       0
  5316.3     .05       0  5454.8     .12       0    5608     .05       0
    5663     .12       0  5733.5     .05       0  5856.5     .12       0
  5965.1     .05       0
Bank Sta=4959.3,5097.9
XS Rating Curve= 0 ,0
Exp/Cntr=0.3,0.1

Type RM Length L Ch R = 1 ,97490   ,490,490,490
BEGIN DESCRIPTION:
STEWARTS CREEK 192.0
END DESCRIPTION:
XS GIS Cut Line= 3
       3819758.2     10146240.53      3819057.81     10146746.43
      3818122.42     10147524.83
#Sta/Elev= 30
    4136  342.92  4358.5  335.88  4444.8  331.05  4472.8  328.63  4556.7  325.75
  4594.3  325.34  4602.8  323.11  4617.5  321.64  4623.7  322.62  4638.4  322.31
  4653.1  320.77  4694.8  319.59  4724.3   316.9  4802.6  313.49  4845.7  313.13
  4879.4  310.82  4888.9  311.71  4931.6  312.08  5017.3  311.41  5052.4  312.98
  5144.8  317.74  5265.9  321.66  5436.5  322.46  5670.8  327.08    5706  329.02
    5827  332.23    5870  335.04  5890.8  334.87  6061.4  344.46  6216.9  349.94
#Mann= 4 ,-1 , 0
    4136     .12       0  4556.7     .05       0  4845.7     .03       0
  5052.4     .05       0
Bank Sta=4845.7,5052.4
XS Rating Curve= 0 ,0
Exp/Cntr=0.3,0.1

Type RM Length L Ch R = 1 ,97000   ,500,500,500
BEGIN DESCRIPTION:
STEWARTS CREEK 191.0
END DESCRIPTION:
XS GIS Cut Line= 3
      3819680.11     10146058.21      3818877.95     10146341.45
      3817592.66     10146492.21
#Sta/Elev= 30
  4149.3  341.71  4324.9  335.58    4396  331.86  4415.5  330.67  4443.3  329.85
  4499.8  324.95  4537.2  322.81  4592.6  318.56    4658  315.91  4680.1  313.88
  4686.9  314.19  4703.2  312.28  4724.4  313.75    4764  312.32  4904.7  311.85
  5058.5  310.34  5221.6  311.92  5385.4  313.82  5453.2  316.73  5556.8  317.58
    5615  319.77  5654.6  321.22  5694.8  320.37  5723.2  323.52  5936.5  329.93
  5981.3  333.02  6071.1  336.97  6107.6  340.11  6208.3  345.47  6294.1  348.78
#Mann= 11 ,-1 , 0
  4149.3     .12       0    4396     .05       0  4415.5     .12       0
  4537.2      .1       0    4658     .12       0  4686.9     .05       0
    4764     .12       0  4904.7     .03       0  5221.6     .05       0
    5615      .1       0  5981.3     .12       0
Bank Sta=4904.7,5221.6
XS Rating Curve= 0 ,0
Exp/Cntr=0.3,0.1

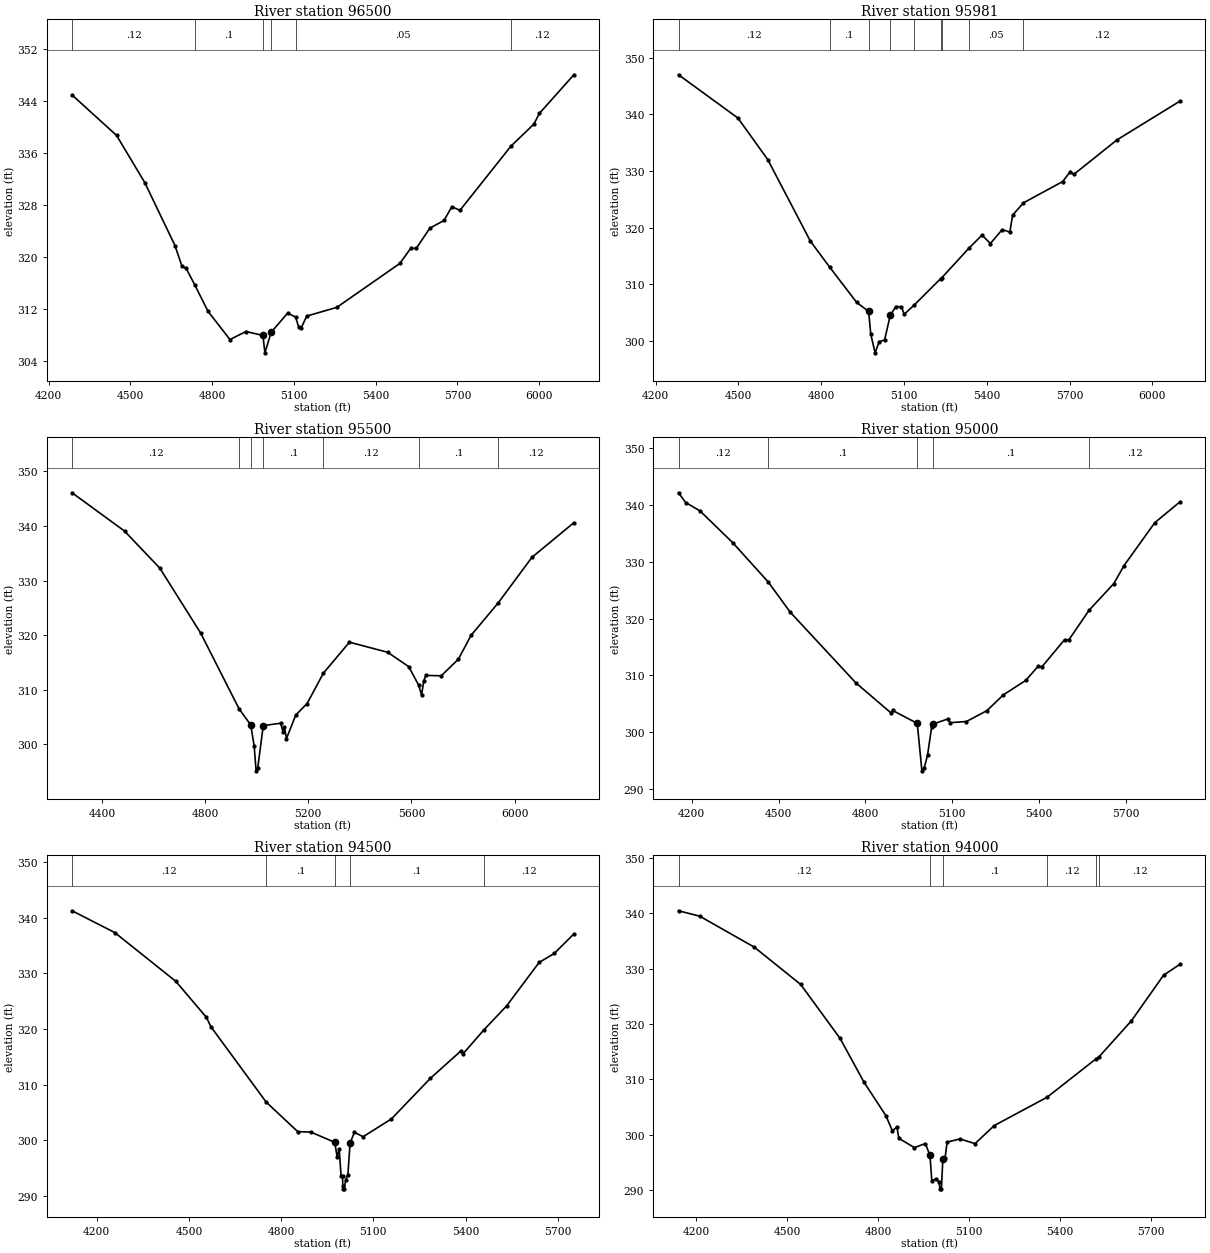
Type RM Length L Ch R = 1 ,96500   ,519,519,519
BEGIN DESCRIPTION:
STEWARTS CREEK 190.0
END DESCRIPTION:
XS GIS Cut Line= 3
      3819632.41     10145815.15      3818924.11     10145905.22
      3817801.83     10145802.23
#Sta/Elev= 30
    4286  344.98  4449.4  338.74  4552.7  331.48  4663.6  321.76  4689.2  318.57
  4703.9   318.3  4736.5  315.67  4784.5  311.64  4865.2  307.27  4924.1  308.51
  4986.2   307.9  4993.5  305.22  5016.3  308.38  5076.6  311.34  5106.1  310.74
  5116.8  309.27  5126.8  309.06  5146.9  310.89  5257.3  312.23  5488.3     319
  5528.5  321.34  5548.6  321.32  5598.8  324.45  5650.6  325.63  5679.1  327.75
  5709.2   327.2  5896.1  337.09  5980.5   340.5  6000.4  342.14    6127   348.1
#Mann= 6 ,-1 , 0
    4286     .12       0  4736.5      .1       0  4986.2     .07       0
  5016.3     .12       0  5106.1     .05       0  5896.1     .12       0
Bank Sta=4986.2,5016.3
XS Rating Curve= 0 ,0
Exp/Cntr=0.3,0.1

Type RM Length L Ch R = 1 ,95981   ,481,481,481
BEGIN DESCRIPTION:
STEWARTS CREEK 189.0
END DESCRIPTION:
XS GIS Cut Line= 3
      3819671.45     10145697.97      3818968.13     10145560.13
      3817874.58     10145428.87
#Sta/Elev= 30
  4283.3  346.99  4498.5  339.35  4606.5  332.02    4761  317.62  4831.3     313
  4928.9  306.79    4972  305.21  4979.9  301.17  4995.5   297.9  5010.3  299.89
  5029.8  300.15  5050.6  304.56  5070.8  306.08  5090.9  306.04    5101  304.71
  5137.2  306.34  5232.6  310.98  5236.1   311.1  5335.1  316.36    5383  318.68
  5413.2   317.2  5456.1  319.66  5483.7  319.22  5493.8  322.21    5533  324.38
  5675.1  328.14  5702.8   329.9  5715.4   329.4  5872.3  335.51  6101.4  342.38
#Mann= 9 ,-1 , 0
  4283.3     .12       0  4831.3      .1       0    4972     .07       0
  5050.6      .1       0  5137.2     .05       0  5232.6      .1       0
  5236.1     .12       0  5335.1     .05       0    5533     .12       0
Bank Sta=4972,5050.6
XS Rating Curve= 0 ,0
Exp/Cntr=0.3,0.1

Type RM Length L Ch R = 1 ,95500   ,500,500,500
BEGIN DESCRIPTION:
STEWARTS CREEK 188.0
END DESCRIPTION:
XS GIS Cut Line= 3
      3819719.15     10145602.46      3819129.54     10145195.52
      3818043.85     10144617.25
#Sta/Elev= 30
  4283.6  346.09  4487.1  339.08  4624.3  332.27  4782.5  320.39    4932  306.47
  4976.6  303.59  4989.9  299.76  4997.5  295.17  5003.8  295.67  5025.2  303.45
  5092.6  303.89  5101.7  302.36  5107.4  303.16  5115.2  301.07  5151.3  305.38
  5195.2  307.49  5258.5  313.06  5359.6  318.73  5507.7  316.88  5589.9  314.24
  5627.5   310.9  5639.5  309.04  5647.7  311.64  5655.8  312.64  5715.7  312.58
    5782  315.61  5831.6     320  5936.8  325.93  6067.5  334.27  6230.1  340.61
#Mann= 7 ,-1 , 0
  4283.6     .12       0    4932      .1       0  4976.6     .07       0
  5025.2      .1       0  5258.5     .12       0  5627.5      .1       0
  5936.8     .12       0
Bank Sta=4976.6,5025.2
XS Rating Curve= 0 ,0
Exp/Cntr=0.3,0.1

Type RM Length L Ch R = 1 ,95000   ,500,500,500
BEGIN DESCRIPTION:
STEWARTS CREEK 187.0
END DESCRIPTION:
XS GIS Cut Line= 3
      3819931.88     10145342.09      3819307.05     10144772.17
      3818691.71     10144132.36
#Sta/Elev= 30
  4154.3  342.17  4179.1  340.45  4228.4  338.98  4341.9  333.36  4464.3  326.45
  4539.9  321.15  4766.8  308.69  4887.1  303.44  4893.9  303.83    4979  301.55
    4995  293.19    5003  293.69  5014.5  295.97  5028.6  300.88 5032.23 301.404
    5085  302.34  5092.2  301.67  5148.8  301.88  5219.5  303.79  5276.1  306.56
  5353.8  309.12  5396.3   311.6  5410.4  311.56  5488.1  316.31  5502.2  316.23
  5572.7  321.49  5657.9  326.17  5693.4  329.36  5799.4   336.9  5887.7  340.62
#Mann= 5 ,-1 , 0
  4154.3     .12       0  4464.3      .1       0    4979     .07       0
 5032.23      .1       0  5572.7     .12       0
Bank Sta=4979,5032.23
XS Rating Curve= 0 ,0
Exp/Cntr=0.3,0.1

Type RM Length L Ch R = 1 ,94500   ,500,500,500
BEGIN DESCRIPTION:
STEWARTS CREEK 186.0
END DESCRIPTION:
XS GIS Cut Line= 3
      3820148.01     10145057.36      3819485.32      10144477.9
      3818951.44     10143947.59
#Sta/Elev= 30
  4119.7  341.22  4258.9   337.3  4457.3  328.55  4556.9  322.08  4571.2  320.42
  4751.3  306.87    4854  301.56  4896.7  301.48  4974.6  299.64  4982.1  297.04
  4988.8   298.5    4995  293.66    5000  293.66  5000.4  291.79  5000.8  291.29
  5005.3  291.29  5010.1   292.9  5017.2  293.83  5024.3  299.49  5038.4  301.44
  5066.7  300.65  5158.6  303.83  5285.9  311.15  5384.9  316.05  5391.9  315.54
  5458.9  319.78  5533.4  324.12  5639.4  331.94  5688.9  333.56  5752.5  337.06
#Mann= 5 ,-1 , 0
  4119.7     .12       0  4751.3      .1       0  4974.6     .07       0
  5024.3      .1       0  5458.9     .12       0
Bank Sta=4974.6,5024.3
XS Rating Curve= 0 ,0
Exp/Cntr=0.3,0.1

Type RM Length L Ch R = 1 ,94000   ,478,478,478
BEGIN DESCRIPTION:
STEWARTS CREEK 185.0
END DESCRIPTION:
XS GIS Cut Line= 3
      3820222.84     10144981.68      3819758.37     10144258.85
      3819202.83     10143688.22
#Sta/Elev= 30
  4140.8  340.47  4210.8  339.49  4391.1  333.88  4543.7  327.15  4673.9  317.38
  4752.5  309.49  4825.1   303.4  4846.3  300.67  4861.4  301.38  4867.4  299.32
  4918.9  297.64  4955.2  298.37  4970.4  296.23  4976.4  291.67  4991.6     292
    5000  291.48  5003.6  290.18  5008.1  290.18  5012.9   295.6    5020  295.69
    5027  298.64  5069.5   299.2  5119.1  298.36  5182.6  301.63  5356.6  306.74
  5518.2  313.69  5527.7  314.03  5635.3  320.59  5741.3  328.83  5796.4  330.83
#Mann= 6 ,-1 , 0
  4140.8     .12       0  4970.4     .07       0  5012.9      .1       0
  5356.6     .12       0  5518.2      .1       0  5527.7     .12       0
Bank Sta=4970.4,5012.9
XS Rating Curve= 0 ,0
Exp/Cntr=0.3,0.1

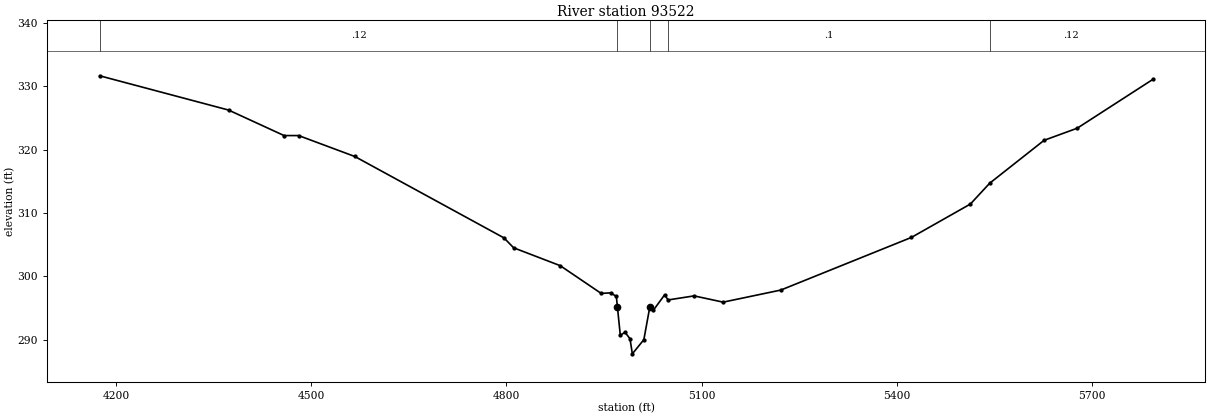
Type RM Length L Ch R = 1 ,93522   ,493,493,493
BEGIN DESCRIPTION:
STEWARTS CREEK 184.0
END DESCRIPTION:
XS GIS Cut Line= 3
      3820470.22     10144573.67      3819997.95     10143896.49
      3819281.88     10143554.13
#Sta/Elev= 30
  4174.4  331.67  4372.6  326.26    4458  322.23  4480.4  322.23  4566.7  318.93
  4796.2  306.07    4811  304.51  4882.6  301.69  4945.6  297.31  4960.2   297.4
  4968.9  296.83  4970.5 295.219    4975  290.69  4982.2  291.18  4989.9  290.15
  4993.5  287.77  5011.2  290.01  5020.4   295.2    5026  294.68  5043.1  297.08
  5048.5  296.28  5088.5  296.92  5133.1  295.93  5221.8  297.84  5422.6  306.15
  5513.3  311.42    5543  314.71  5626.6  321.48  5677.5  323.39  5793.7  331.09
#Mann= 5 ,-1 , 0
  4174.4     .12       0  4970.5     .07       0  5020.4     .12       0
  5048.5      .1       0    5543     .12       0
Bank Sta=4970.5,5020.4
XS Rating Curve= 0 ,0
Exp/Cntr=0.3,0.1