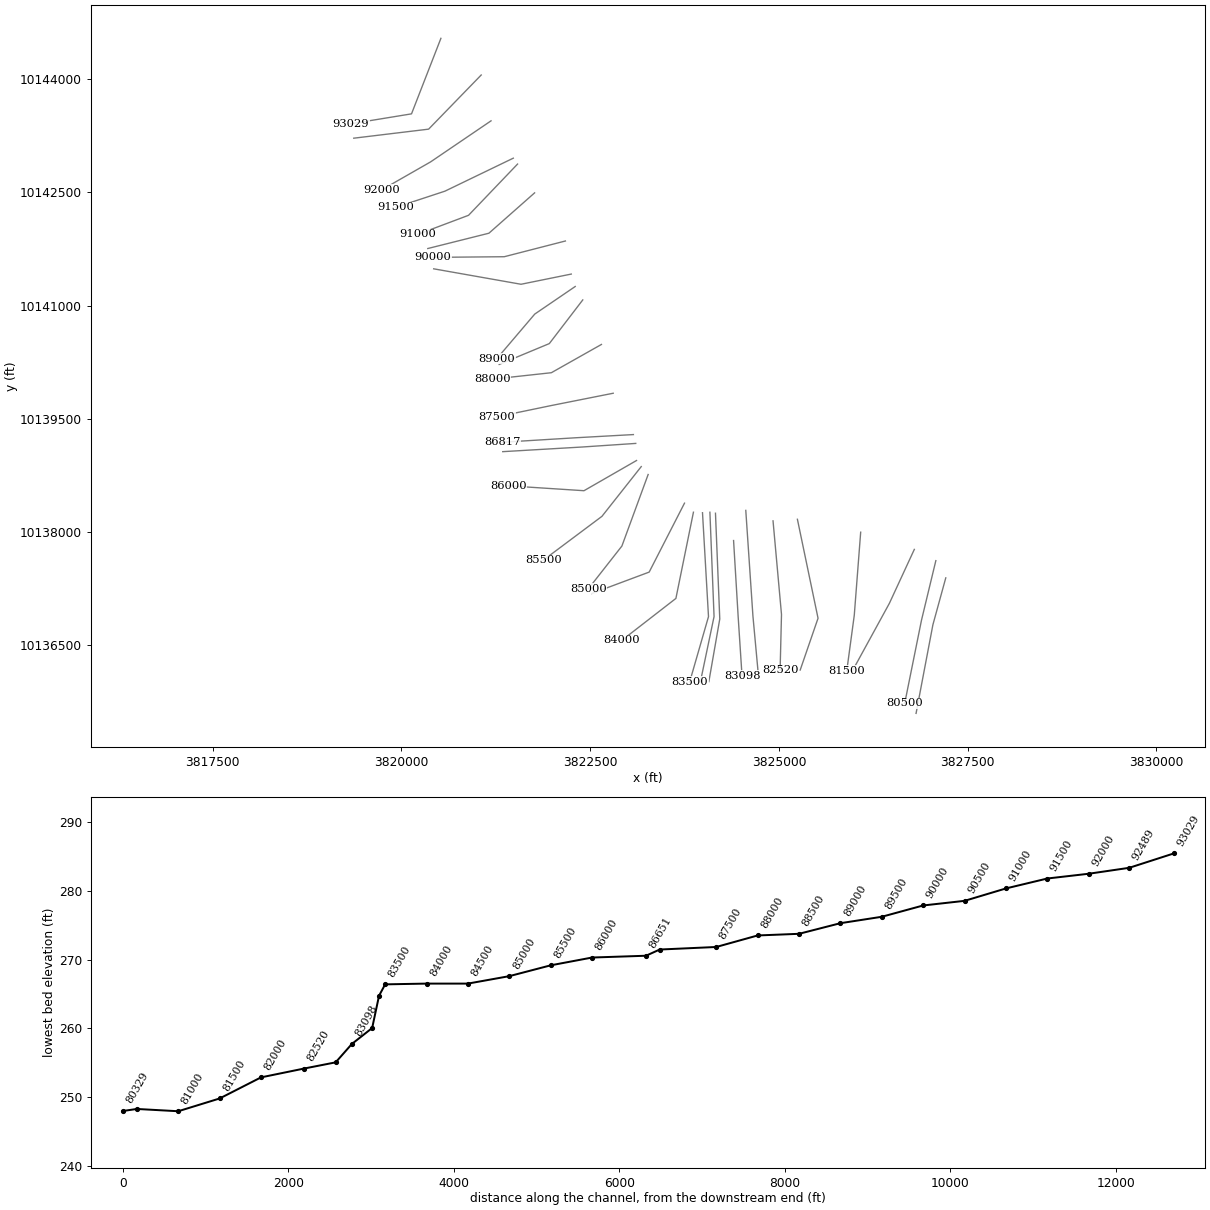
HEC-RAS study STEWARTS CREEK.prj: STEWARTS CREEK Base Level Engineering

--- STEWARTS CREEK.g10 (geometry) --- (continued)

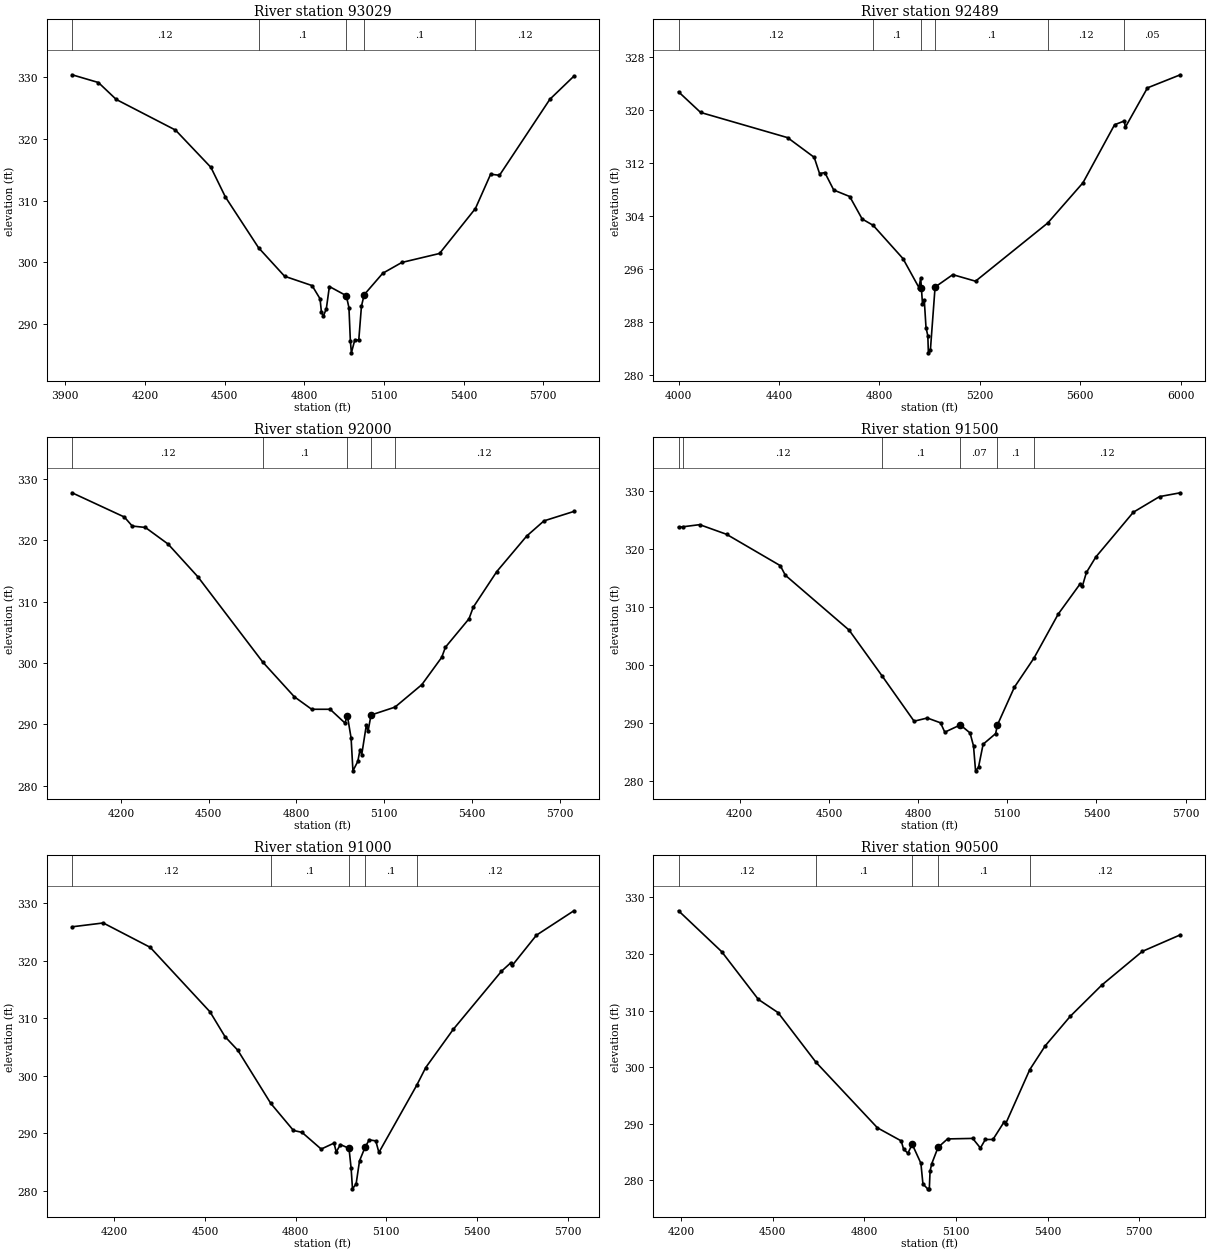
Type RM Length L Ch R = 1 ,93029   ,540,540,540
BEGIN DESCRIPTION:
STEWARTS CREEK 183.0
END DESCRIPTION:
XS GIS Cut Line= 3
      3820522.31     10144543.31      3820132.99     10143542.15
       3819328.7     10143410.46
#Sta/Elev= 30
  3925.8  330.34  4024.8  329.09  4092.2  326.35  4315.2   321.4  4448.6  315.37
    4503  310.59  4627.9  302.38    4726  297.77  4829.5  296.26  4859.4  294.13
  4864.7  291.93  4872.4  291.36  4883.1  292.53  4894.6  296.11  4958.2  294.63
  4968.2   292.7  4973.6  287.29  4977.4  285.39  4990.4  287.51  5005.2  287.44
  5015.3  292.93  5025.5  294.78  5095.4  298.25  5167.3     300  5309.2  301.45
  5444.4  308.72  5501.7  314.27    5535  314.09  5724.7  326.38    5815  330.11
#Mann= 5 ,-1 , 0
  3925.8     .12       0  4627.9      .1       0  4958.2     .07       0
  5025.5      .1       0  5444.4     .12       0
Bank Sta=4958.2,5025.5
XS Rating Curve= 0 ,0
Exp/Cntr=0.3,0.1

Type RM Length L Ch R = 1 ,92489   ,489,489,489
BEGIN DESCRIPTION:
STEWARTS CREEK 182.0
END DESCRIPTION:
XS GIS Cut Line= 3
      3821056.15     10144057.17      3820359.57     10143339.41
      3819367.79      10143219.5
#Sta/Elev= 30
  3999.8  322.79  4087.8  319.67  4434.3  315.86  4540.3  312.88  4561.6  310.43
  4582.7  310.57  4618.2  307.93  4681.8  306.95  4731.4  303.55  4775.2  302.59
    4894  297.56  4957.5  293.18  4964.7  294.61  4967.3 293.169  4971.7  290.73
  4978.9  291.28  4985.8   287.1    4993  285.88  4995.2   283.3  5003.4   283.8
  5021.9  293.25  5092.4  295.13    5183  294.14  5470.9  302.95  5611.1  309.03
    5737  317.81  5775.9  318.38    5780  317.44    5868  323.39    5999  325.37
#Mann= 6 ,-1 , 0
  3999.8     .12       0  4775.2      .1       0  4967.3     .07       0
  5021.9      .1       0  5470.9     .12       0  5775.9     .05       0
Bank Sta=4967.3,5021.9
XS Rating Curve= 0 ,0
Exp/Cntr=0.3,0.1

Type RM Length L Ch R = 1 ,92000   ,500,500,500
BEGIN DESCRIPTION:
STEWARTS CREEK 181.0
END DESCRIPTION:
XS GIS Cut Line= 3
      3821186.38     10143449.54      3820386.32     10142905.69
      3819736.68     10142533.72
#Sta/Elev= 30
  4032.6  327.74  4211.4  323.79  4238.4  322.32  4283.3  322.09  4361.1  319.38
  4462.9  314.05  4684.9  300.15  4792.6  294.51    4852  292.47    4915  292.47
  4965.8  290.23    4974  291.45  4986.8  287.79  4993.1  282.44  5009.8  283.99
  5017.4   285.9  5023.2  285.08    5039  289.93  5044.8  288.89  5054.9  291.53
  5136.9  292.82  5228.7  296.48  5296.6  300.92  5309.4  302.58    5390  307.21
  5404.5  309.09  5485.1  314.91  5587.3  320.69  5646.3  323.16  5748.6   324.7
#Mann= 5 ,-1 , 0
  4032.6     .12       0  4684.9      .1       0    4974     .07       0
  5054.9      .1       0  5136.9     .12       0
Bank Sta=4974,5054.9
XS Rating Curve= 0 ,0
Exp/Cntr=0.3,0.1

Type RM Length L Ch R = 1 ,91500   ,500,500,500
BEGIN DESCRIPTION:
STEWARTS CREEK 180.0
END DESCRIPTION:
XS GIS Cut Line= 3
      3821481.49     10142954.73      3820575.64     10142517.18
       3819927.7      10142303.7
#Sta/Elev= 30
    3994  323.69  4009.6  323.79  4065.1  324.15  4155.5  322.49  4336.3  317.09
  4353.3  315.44  4567.8  305.99  4678.4  298.13  4786.5   290.3    4831  290.85
  4875.4  290.02  4889.8  288.41    4942  289.66  4974.7  288.28  4986.4  286.04
  4993.3  281.75  5003.2  282.37  5018.7  286.33  5060.8  288.16  5066.8  289.65
    5124  296.16  5189.7  301.16  5271.4  308.75  5345.1  313.95  5352.7  313.57
  5366.2  315.91  5397.8  318.57  5524.1  326.29  5612.2  328.98  5682.2  329.64
#Mann= 6 ,-1 , 0
    3994     .05       0  4009.6     .12       0  4678.4      .1       0
    4942     .07       0  5066.8      .1       0  5189.7     .12       0
Bank Sta=4942,5066.8
XS Rating Curve= 0 ,0
Exp/Cntr=0.3,0.1

Type RM Length L Ch R = 1 ,91000   ,500,500,500
BEGIN DESCRIPTION:
STEWARTS CREEK 179.0
END DESCRIPTION:
XS GIS Cut Line= 3
      3821537.94     10142876.63      3820888.41     10142197.27
       3820214.1     10141943.44
#Sta/Elev= 30
  4060.1  325.91  4163.2  326.58  4318.6  322.34  4516.7   311.1  4566.1   306.8
  4608.6  304.42  4717.6  295.18  4792.6  290.47  4820.9  290.14  4884.4  287.23
  4926.9  288.27  4934.1  286.74  4948.2  288.01  4976.5  287.36  4983.5  283.88
    4988  280.31    5000  281.16  5011.3  285.19  5029.6  287.54  5043.3  288.84
  5065.1  288.65  5075.4  286.64  5200.4  298.32  5230.4  301.42  5321.1  308.04
    5481  318.18  5511.2  319.62  5516.6  319.19  5596.6  324.45  5720.5   328.7
#Mann= 5 ,-1 , 0
  4060.1     .12       0  4717.6      .1       0  4976.5     .07       0
  5029.6      .1       0  5200.4     .12       0
Bank Sta=4976.5,5029.6
XS Rating Curve= 0 ,0
Exp/Cntr=0.3,0.1

Type RM Length L Ch R = 1 ,90500   ,500,500,500
BEGIN DESCRIPTION:
STEWARTS CREEK 178.0
END DESCRIPTION:
XS GIS Cut Line= 3
      3821763.64     10142494.69      3821158.25      10141959.7
      3820348.68     10141756.82
#Sta/Elev= 30
  4192.1  327.64  4333.3  320.42  4453.4  311.98  4517.8  309.65  4641.9  300.88
  4843.2  289.29    4921  286.98  4928.6  285.54  4942.8   284.8    4957  286.38
  4985.4  283.03  4992.1  279.37  5007.5  278.51    5013  278.51  5015.4  281.65
    5021  282.96  5041.6  285.84  5072.6  287.33    5155  287.42  5180.2  285.72
  5196.3  287.23  5221.3  287.23  5257.4   290.3  5262.5  289.96  5341.9  299.58
  5392.2  303.77  5474.6  309.01  5577.7  314.52  5710.4  320.47  5834.6  323.39
#Mann= 5 ,-1 , 0
  4192.1     .12       0  4641.9      .1       0    4957     .07       0
  5041.6      .1       0  5341.9     .12       0
Bank Sta=4957,5041.6
XS Rating Curve= 0 ,0
Exp/Cntr=0.3,0.1

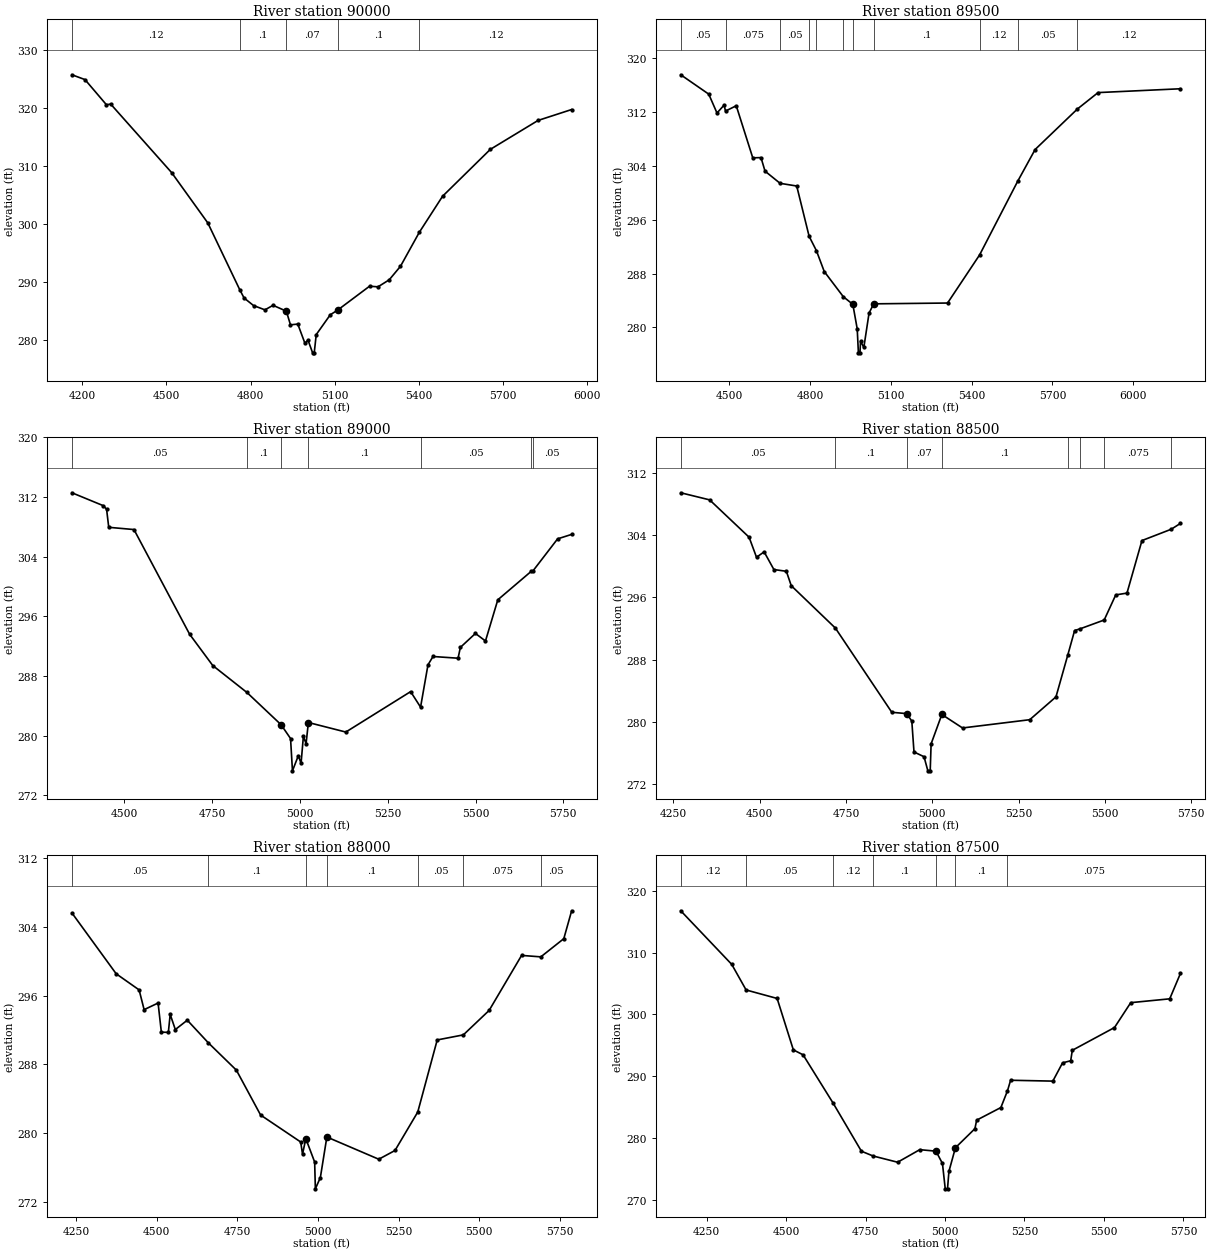
Type RM Length L Ch R = 1 ,90000   ,500,500,500
BEGIN DESCRIPTION:
STEWARTS CREEK 177.0
END DESCRIPTION:
XS GIS Cut Line= 3
      3822171.59     10141856.64      3821361.68      10141648.2
      3820418.12     10141639.63
#Sta/Elev= 30
  4163.7   325.7  4210.1  324.87  4286.3  320.55  4301.8  320.65  4518.6  308.87
  4647.6   300.2  4761.2  288.72  4776.8  287.28  4810.4  285.98  4851.1  285.24
    4880  286.02  4927.4  285.01    4942  282.66  4968.1  282.79  4993.6  279.48
  5004.4  280.04  5020.9  277.84  5026.7  277.84  5033.8  280.98  5083.8  284.39
  5109.6 285.178  5223.8  289.31  5253.8   289.2  5293.8  290.41  5333.8  292.73
  5400.9  298.58  5483.8  304.79  5653.9  312.86  5823.9  317.84  5943.6  319.72
#Mann= 5 ,-1 , 0
  4163.7     .12       0  4761.2      .1       0  4927.4     .07       0
  5109.6      .1       0  5400.9     .12       0
Bank Sta=4927.4,5109.6
XS Rating Curve= 0 ,0
Exp/Cntr=0.3,0.1

Type RM Length L Ch R = 1 ,89500   ,500,500,500
BEGIN DESCRIPTION:
STEWARTS CREEK 176.0
END DESCRIPTION:
XS GIS Cut Line= 3
      3822249.68     10141418.27      3821583.78     10141283.04
      3820426.84     10141487.72
#Sta/Elev= 30
  4320.5  317.57  4424.4  314.69    4455  311.88  4481.4  313.06  4486.6  312.17
  4526.5  312.96  4587.8  305.21  4618.3  305.25  4633.3  303.23  4689.2  301.42
  4750.9  301.02  4796.9  293.54  4824.1  291.39    4853   288.3    4924  284.54
  4959.1 283.422  4975.4  279.77  4979.8   276.2  4985.6   276.2  4987.8  277.92
    5000  277.01  5019.3  282.11  5036.5  283.49  5310.7  283.61  5429.6  290.77
  5571.1  301.74  5635.6  306.45  5792.6  312.48  5869.2  314.92  6174.9  315.49
#Mann= 11 ,-1 , 0
  4320.5     .05       0  4486.6    .075       0  4689.2     .05       0
  4796.9     .12       0  4824.1      .1       0    4924     .12       0
  4959.1     .07       0  5036.5      .1       0  5429.6     .12       0
  5571.1     .05       0  5792.6     .12       0
Bank Sta=4959.1,5036.5
XS Rating Curve= 0 ,0
Exp/Cntr=0.3,0.1

Type RM Length L Ch R = 1 ,89000   ,500,500,500
BEGIN DESCRIPTION:
STEWARTS CREEK 175.0
END DESCRIPTION:
XS GIS Cut Line= 3
       3822301.8     10141253.34      3821765.66      10140887.8
      3821264.49     10140298.49
#Sta/Elev= 30
  4351.1  312.55  4440.8  310.81  4449.7  310.33  4455.8  307.92  4527.6  307.62
  4686.1  293.58  4751.9  289.39  4849.1  285.78  4946.3  281.46  4973.4   279.6
  4978.8  275.27  4995.6  277.31  5003.3  276.27  5009.9  279.88  5017.6  278.92
  5024.1  281.75  5130.7  280.47  5315.2  285.89  5343.5  283.81  5364.6  289.48
  5378.9   290.6  5450.3  290.37  5456.8  291.82  5499.7  293.69  5528.3  292.68
  5563.4   298.2  5658.6  302.02  5663.4  302.07  5733.6  306.37  5773.6  306.97
#Mann= 7 ,-1 , 0
  4351.1     .05       0  4849.1      .1       0  4946.3     .07       0
  5024.1      .1       0  5343.5     .05       0  5658.6    .075       0
  5663.4     .05       0
Bank Sta=4946.3,5024.1
XS Rating Curve= 0 ,0
Exp/Cntr=0.3,0.1

Type RM Length L Ch R = 1 ,88500   ,500,500,500
BEGIN DESCRIPTION:
STEWARTS CREEK 174.0
END DESCRIPTION:
XS GIS Cut Line= 3
      3822401.62     10141075.37      3821958.61     10140496.54
      3821294.88     10140220.37
#Sta/Elev= 30
  4271.1   309.4  4354.8  308.49  4469.1   303.7  4490.6  301.13  4512.7  301.82
    4541  299.55  4577.1  299.33  4591.3  297.48  4719.2  292.04  4882.6  281.24
  4926.1  281.07  4940.6   280.1  4946.9  276.15    4976  275.54  4987.1  273.73
  4993.9  273.73  4996.5  277.19  5027.6  280.96  5087.5  279.23  5282.3  280.29
  5358.3  283.22  5392.8  288.63  5412.3  291.73  5428.3  291.95    5498  293.08
  5531.5   296.3    5564  296.53  5607.4  303.27  5692.1  304.72  5718.9  305.47
#Mann= 8 ,-1 , 0
  4271.1     .05       0  4719.2      .1       0  4926.1     .07       0
  5027.6      .1       0  5392.8     .05       0  5428.3      .1       0
    5498    .075       0  5692.1     .05       0
Bank Sta=4926.1,5027.6
XS Rating Curve= 0 ,0
Exp/Cntr=0.3,0.1

Type RM Length L Ch R = 1 ,88000   ,500,500,500
BEGIN DESCRIPTION:
STEWARTS CREEK 173.0
END DESCRIPTION:
XS GIS Cut Line= 3
      3822649.06     10140485.14      3821985.56     10140110.42
      3821203.71     10140025.05
#Sta/Elev= 30
    4238  305.63    4375  298.55  4446.1  296.67  4461.6  294.37  4504.9  295.14
    4515  291.75  4536.7  291.72  4542.4  293.82  4558.3  292.05  4595.4  293.14
  4660.7   290.5  4747.5  287.32  4822.6  282.09  4946.8  278.95  4952.5  277.53
  4962.7  279.34  4990.1  276.61  4992.3  273.49  5007.8  274.81  5027.9  279.53
  5188.8  276.94  5239.1  277.96  5309.6  282.44  5369.9  290.84  5450.9  291.43
  5530.8  294.28  5631.4  300.69    5691  300.52  5762.2  302.64  5786.5  305.89
#Mann= 7 ,-1 , 0
    4238     .05       0  4660.7      .1       0  4962.7     .07       0
  5027.9      .1       0  5309.6     .05       0  5450.9    .075       0
    5691     .05       0
Bank Sta=4962.7,5027.9
XS Rating Curve= 0 ,0
Exp/Cntr=0.3,0.1

Type RM Length L Ch R = 1 ,87500   ,683,683,683
BEGIN DESCRIPTION:
STEWARTS CREEK 172.0
END DESCRIPTION:
XS GIS Cut Line= 3
      3822805.24     10139838.41      3821989.89     10139676.35
      3821264.82     10139525.99
#Sta/Elev= 30
  4168.7  316.76  4329.2  308.09  4374.3  303.96  4471.9  302.59  4522.9  294.28
  4553.5  293.48  4648.5  285.63    4737   277.9  4773.7  277.13  4850.9  276.12
  4920.5  278.15  4971.5  277.91  4991.9  275.92  5000.7  271.82  5007.8  271.82
  5012.3  274.64  5032.7  278.46    5094  281.54  5099.5  282.92  5175.7  284.96
  5196.5  287.67  5206.3  289.37  5339.1  289.23  5369.7  292.18  5395.3  292.52
  5400.4  294.21  5533.1  297.89  5584.2  301.91  5706.8  302.53  5740.5  306.63
#Mann= 7 ,-1 , 0
  4168.7     .12       0  4374.3     .05       0  4648.5     .12       0
  4773.7      .1       0  4971.5     .07       0  5032.7      .1       0
  5196.5    .075       0
Bank Sta=4971.5,5032.7
XS Rating Curve= 0 ,0
Exp/Cntr=0.3,0.1

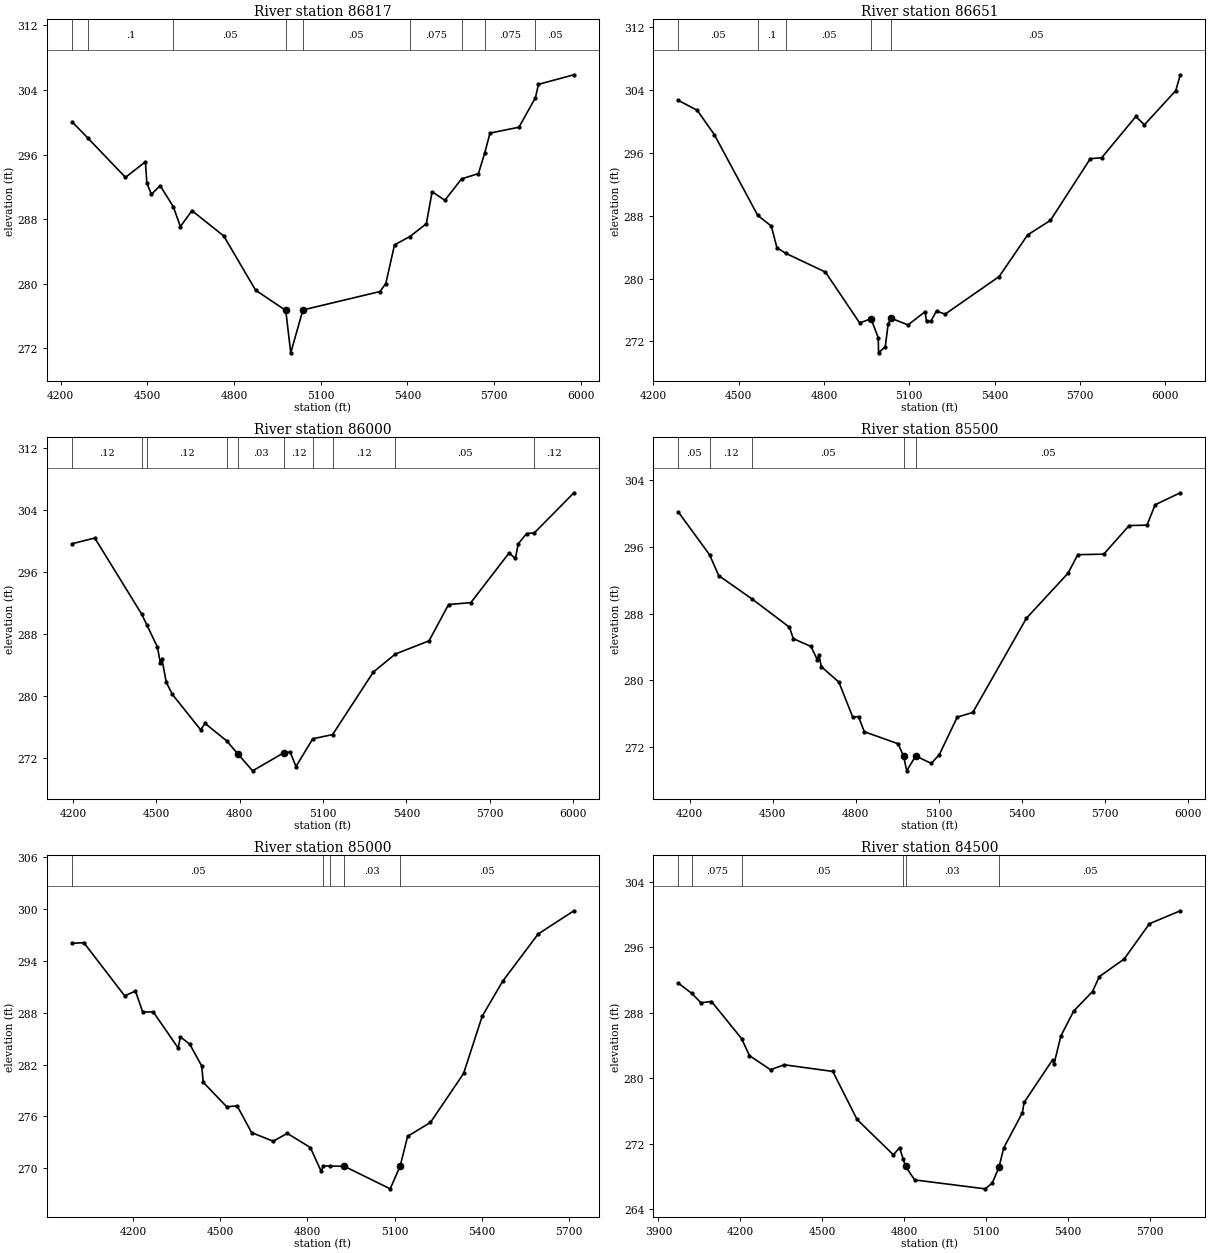
Type RM Length L Ch R = 1 ,86817   ,166,166,166
BEGIN DESCRIPTION:
STEWARTS CREEK 171.0
END DESCRIPTION:
XS GIS Cut Line= 3
      3823072.32     10139290.31      3822312.68     10139248.33
       3821337.9     10139188.74
#Sta/Elev= 30
  4239.2  300.05  4293.8  298.04    4424  293.17  4493.1   295.1  4498.1  292.43
  4514.1  291.08  4544.1  292.15  4589.6  289.54  4614.2  287.08  4654.3  289.05
  4764.5  285.91  4874.6   279.2 4978.88 276.703  4996.3  271.45  5038.4  276.76
  5305.4  279.04  5325.4  280.03  5355.5  284.82  5408.5  285.84  5465.7  287.43
  5485.7   291.4  5529.7  290.33  5587.5  292.98    5646  293.64  5667.4  296.14
  5686.1  298.65  5786.3  299.38  5843.2  303.02  5853.9  304.69  5976.6  305.87
#Mann= 9 ,-1 , 0
  4239.2     .05       0  4293.8      .1       0  4589.6     .05       0
 4978.88     .07       0  5038.4     .05       0  5408.5    .075       0
  5587.5     .05       0  5667.4    .075       0  5843.2     .05       0
Bank Sta=4978.88,5038.4
XS Rating Curve= 0 ,0
Exp/Cntr=0.3,0.1

Type RM Length L Ch R = 1 ,86651   ,651,651,651
BEGIN DESCRIPTION:
STEWARTS CREEK 170.0
END DESCRIPTION:
XS GIS Cut Line= 3
      3823103.59     10139173.12      3822393.09     10139125.45
       3821341.7     10139063.81
#Sta/Elev= 30
  4287.9  302.67  4353.8  301.42  4413.9  298.33  4566.6  288.05  4614.4  286.68
  4634.4  283.92  4665.2  283.22  4804.8  280.83  4925.1  274.36  4965.2  274.88
  4990.5  272.49  4991.8  270.55  5015.3  271.33  5025.3  274.19  5035.3  274.96
  5095.4   274.1  5155.4  275.79  5160.4  274.55  5175.5  274.57  5195.6  275.88
  5225.6  275.47    5416  280.26  5516.1  285.56  5596.3  287.41  5736.5  295.26
  5776.6  295.38  5896.8  300.63  5926.8  299.57    6037  303.92  6053.2  305.94
#Mann= 5 ,-1 , 0
  4287.9     .05       0  4566.6      .1       0  4665.2     .05       0
  4965.2     .07       0  5035.3     .05       0
Bank Sta=4965.2,5035.3
XS Rating Curve= 0 ,0
Exp/Cntr=0.3,0.1

Type RM Length L Ch R = 1 ,86000   ,500,500,500
BEGIN DESCRIPTION:
STEWARTS CREEK 169.0
END DESCRIPTION:
XS GIS Cut Line= 3
      3823113.93     10138946.54      3822417.97     10138546.19
      3821417.87     10138611.07
#Sta/Elev= 30
  4197.1  299.62  4278.7  300.36  4447.4  290.53  4466.4  289.12  4504.3  286.25
  4514.4  284.24  4520.1  284.78  4535.9  281.73  4557.5  280.18  4659.6  275.59
  4675.3  276.42  4753.5  274.15  4792.5  272.51  4846.5  270.29  4959.9  272.65
  4981.5  272.71  5002.6  270.85  5062.9  274.43  5134.2  274.97  5280.7  283.05
  5360.2  285.38  5481.1  287.08  5551.3  291.77  5631.4  292.01  5768.6  298.41
  5791.8  297.72  5801.8   299.6  5831.9  300.93  5860.1  301.03  6002.2   306.2
#Mann= 10 ,-1 , 0
  4197.1     .12       0  4447.4     .05       0  4466.4     .12       0
  4753.5     .05       0  4792.5     .03       0  4959.9     .12       0
  5062.9     .05       0  5134.2     .12       0  5360.2     .05       0
  5860.1     .12       0
Bank Sta=4792.5,4959.9
XS Rating Curve= 0 ,0
Exp/Cntr=0.3,0.1

Type RM Length L Ch R = 1 ,85500   ,500,500,500
BEGIN DESCRIPTION:
STEWARTS CREEK 168.0
END DESCRIPTION:
XS GIS Cut Line= 3
      3823176.46     10138865.82      3822655.93     10138206.54
      3821876.99     10137623.64
#Sta/Elev= 30
    4160  300.17  4272.3  295.07  4305.4  292.57  4426.9  289.74    4561  286.38
  4574.7  285.01  4638.8  284.07  4661.3  282.49  4667.7   283.1  4675.7  281.66
  4739.4   279.8  4789.6   275.6  4810.4  275.67  4831.2  273.85  4953.1  272.41
  4973.3  270.92  4984.5  269.16  5016.9  270.95  5073.2  270.05  5102.3   271.1
    5167   275.6  5223.2  276.16    5417  287.46  5567.1  292.85  5602.5  295.08
  5696.3  295.14    5788  298.57  5852.6  298.62  5881.8  301.06  5972.9   302.5
#Mann= 5 ,-1 , 0
    4160     .05       0  4272.3     .12       0  4426.9     .05       0
  4973.3     .07       0  5016.9     .05       0
Bank Sta=4973.3,5016.9
XS Rating Curve= 0 ,0
Exp/Cntr=0.3,0.1

Type RM Length L Ch R = 1 ,85000   ,500,500,500
BEGIN DESCRIPTION:
STEWARTS CREEK 167.0
END DESCRIPTION:
XS GIS Cut Line= 3
      3823267.86      10138761.1      3822920.17     10137812.62
      3822477.67      10137248.2
#Sta/Elev= 30
  3989.8  296.05  4030.3  296.12  4170.9  289.96    4208  290.51  4233.1  288.07
    4269  288.11  4355.1  283.91  4362.6   285.2  4394.6  284.37    4436  281.84
  4441.3  279.94  4522.2   277.1    4558  277.21  4607.6  274.11  4682.1  273.11
  4730.4  274.02  4809.9  272.38  4847.1  269.63  4854.6  270.27  4877.3  270.23
  4927.1   270.2  5084.8  267.59 5119.47 270.269  5144.8  273.68  5223.5  275.29
  5337.4  280.96  5401.5   287.6  5472.1  291.66  5594.1  297.13  5717.2  299.82
#Mann= 5 ,-1 , 0
  3989.8     .05       0  4854.6     .12       0  4877.3      .1       0
  4927.1     .03       0 5119.47     .05       0
Bank Sta=4927.1,5119.47
XS Rating Curve= 0 ,0
Exp/Cntr=0.3,0.1

Type RM Length L Ch R = 1 ,84500   ,500,500,500
BEGIN DESCRIPTION:
STEWARTS CREEK 166.0
END DESCRIPTION:
XS GIS Cut Line= 3
      3823749.38     10138381.01      3823281.29     10137467.22
      3822521.99     10137183.44
#Sta/Elev= 30
  3973.3  291.62    4022  290.38  4055.5  289.24  4094.2  289.39  4204.4  284.86
  4233.1  282.78  4310.3  281.06  4360.7  281.66  4538.3  280.85  4627.1  274.98
  4760.3  270.66  4782.5  271.54  4796.2  270.14  4804.7  269.25  4837.9   267.6
  5095.8  266.51    5122  267.21  5146.9  269.17  5163.8  271.49  5232.5  275.81
  5238.5  277.06    5343  282.27  5348.3  281.78  5373.3  285.18    5420  288.21
  5489.1  290.61  5514.1  292.43    5605  294.58  5697.6  298.89  5810.6  300.47
#Mann= 6 ,-1 , 0
  3973.3     .05       0    4022    .075       0  4204.4     .05       0
  4796.2      .1       0  4804.7     .03       0  5146.9     .05       0
Bank Sta=4804.7,5146.9
XS Rating Curve= 0 ,0
Exp/Cntr=0.3,0.1

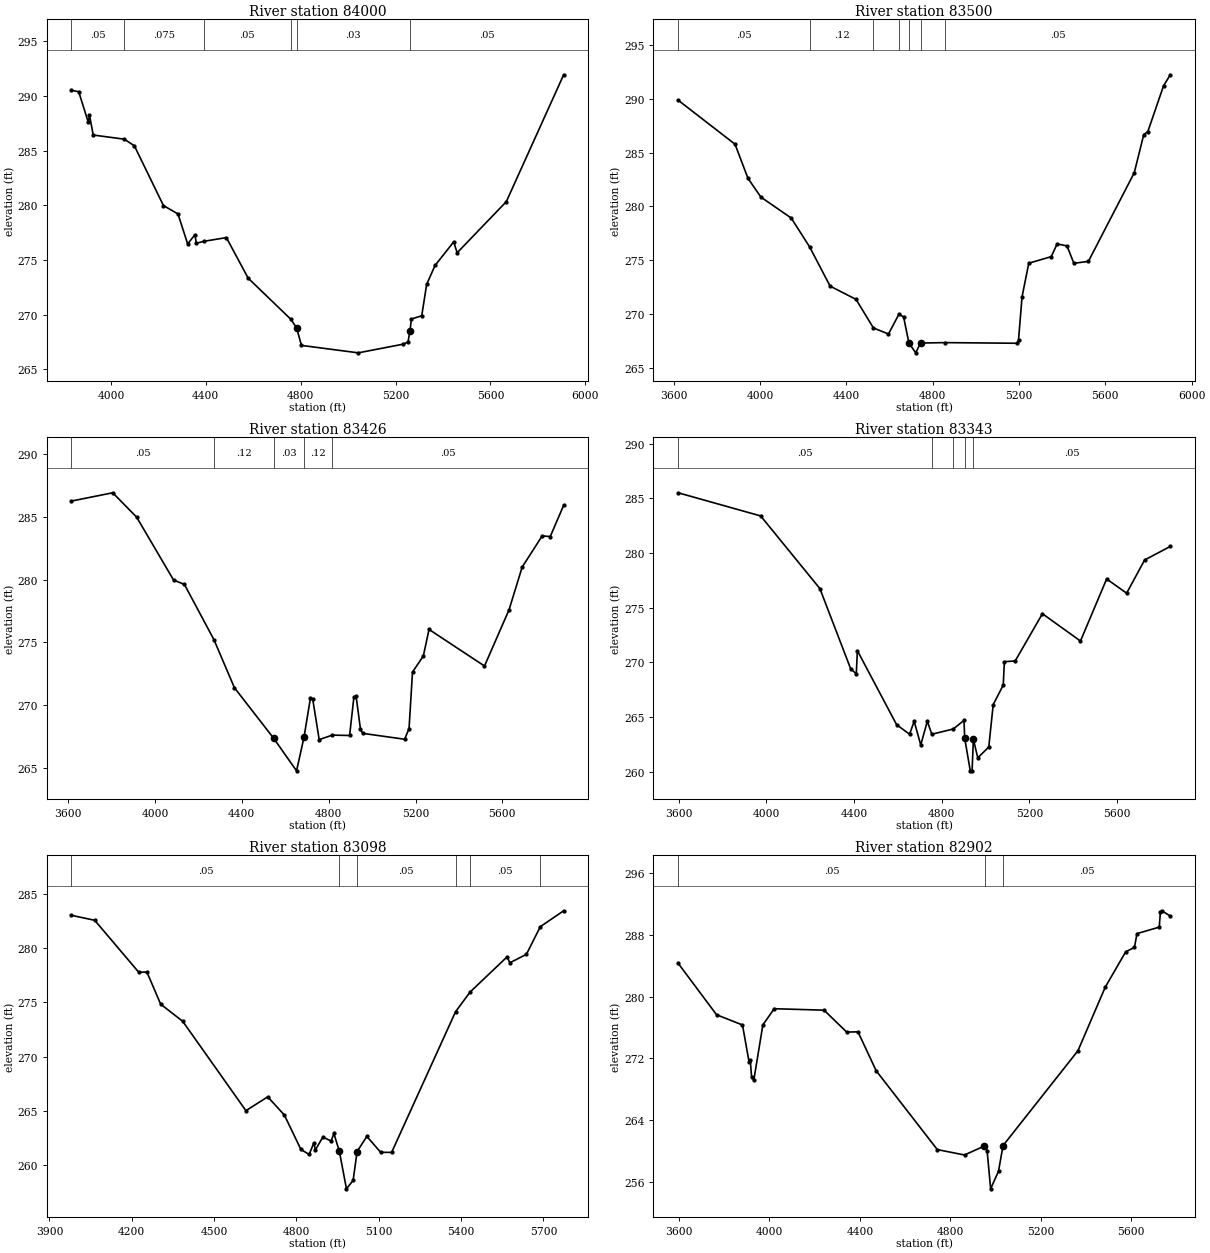
Type RM Length L Ch R = 1 ,84000   ,500,500,500
BEGIN DESCRIPTION:
STEWARTS CREEK 165.0
END DESCRIPTION:
XS GIS Cut Line= 3
      3823867.84     10138261.03      3823635.51     10137118.11
      3822917.83     10136561.06
#Sta/Elev= 30
  3833.7  290.52  3864.3  290.39  3904.5   287.6  3909.6  288.24  3925.5  286.43
  4056.4  286.05    4099  285.44  4221.4  279.98  4282.7  279.21  4323.5  276.47
  4354.1  277.31    4360  276.53    4392  276.71  4486.7  277.05  4578.6  273.34
  4758.4  269.58  4782.7   268.8  4803.1  267.19  5042.8  266.51  5231.4   267.3
  5252.3   267.5  5260.4  268.49  5266.7   269.6  5310.2   269.9    5331  272.77
  5366.3   274.5    5445  276.66  5459.5  275.66  5666.8  280.34  5908.5  291.94
#Mann= 6 ,-1 , 0
  3833.7     .05       0  4056.4    .075       0    4392     .05       0
  4758.4      .1       0  4782.7     .03       0  5260.4     .05       0
Bank Sta=4782.7,5260.4
XS Rating Curve= 0 ,0
Exp/Cntr=0.3,0.1

Type RM Length L Ch R = 1 ,83500   ,74,74,74
BEGIN DESCRIPTION:
STEWARTS CREEK 164.0
END DESCRIPTION:
XS GIS Cut Line= 3
      3823987.95     10138254.22      3824067.41     10136876.81
      3823817.85     10136011.06
#Sta/Elev= 30
  3620.3  289.88    3884  285.79    3944  282.62  4004.1  280.87  4144.3  278.93
  4229.6  276.25  4324.6   272.6  4444.8  271.37  4525.4  268.71  4595.1  268.15
  4643.5  269.99  4665.2  269.74  4689.7 267.325  4721.1   266.4  4743.7  267.31
  4856.7  267.35  5192.5  267.29  5197.7  267.59  5214.1  271.61  5245.3  274.73
  5349.4  275.34  5376.5  276.52  5422.3  276.34  5454.2  274.72  5521.5   274.9
  5733.9  283.13    5778  286.68  5796.9  286.96  5869.8  291.22    5901  292.24
#Mann= 7 ,-1 , 0
  3620.3     .05       0  4229.6     .12       0  4525.4     .05       0
  4643.5     .12       0  4689.7     .03       0  4743.7     .12       0
  4856.7     .05       0
Bank Sta=4689.7,4743.7
XS Rating Curve= 0 ,0
Exp/Cntr=0.3,0.1

Type RM Length L Ch R = 1 ,83426   ,83,83,83
BEGIN DESCRIPTION:
Mapping XS 5d8391e6
END DESCRIPTION:
XS GIS Cut Line= 3
      3824086.04     10138260.79      3824141.05     10136877.79
      3823960.54     10136014.25
#Sta/Elev= 30
  3615.9  286.27  3805.8  286.93  3915.9  284.99    4086  279.97    4136  279.62
    4272  275.21  4366.2  271.38  4546.8  267.35  4652.3  264.75  4686.5  267.42
  4716.5  270.58  4726.5   270.5  4756.5  267.24    4817   267.6  4896.6  267.57
  4916.6  270.67  4926.7  270.68  4946.7  268.06  4956.7  267.74  5149.9  267.27
  5170.3  268.12  5186.2  272.63  5236.1  273.91  5262.3  276.03  5517.7  273.11
  5630.8   277.6  5691.3  281.01  5783.3  283.49  5820.5  283.44  5882.2  285.93
#Mann= 5 ,-1 , 0
  3615.9     .05       0    4272     .12       0  4546.8     .03       0
  4686.5     .12       0    4817     .05       0
Bank Sta=4546.8,4686.5
XS Rating Curve= 0 ,0
Exp/Cntr=0.3,0.1

Type RM Length L Ch R = 1 ,83343   ,245,245,245
BEGIN DESCRIPTION:
STEWARTS CREEK 163.0
END DESCRIPTION:
XS GIS Cut Line= 3
      3824159.83     10138247.71      3824216.75     10136845.56
      3824072.06     10136014.77
#Sta/Elev= 30
  3596.7  285.52  3973.6   283.4  4243.9  276.75    4384  269.43    4410  268.94
    4415  271.07  4594.2  264.29  4653.3  263.42  4674.2  264.61  4704.2  262.44
  4734.3  264.61  4754.8  263.42    4853   263.9  4901.7  264.69  4904.8  263.06
  4930.3  260.07  4938.6  260.07  4944.4  262.97  4964.5  261.26  5014.7  262.25
    5035  266.13  5080.8  267.92  5085.9  270.06  5135.4  270.13  5259.6  274.45
  5433.3  271.95  5552.7  277.63    5644  276.33  5726.2  279.37  5843.3  280.61
#Mann= 5 ,-1 , 0
  3596.7     .05       0  4754.8     .12       0    4853     .05       0
  4904.8     .07       0  4944.4     .05       0
Bank Sta=4904.8,4944.4
XS Rating Curve= 0 ,0
Exp/Cntr=0.3,0.1

Type RM Length L Ch R = 1 ,83098   ,196,196,196
BEGIN DESCRIPTION:
Mapping XS 729ab2d8
END DESCRIPTION:
XS GIS Cut Line= 3
      3824399.53     10137885.62        3824461.     10136866.35
      3824511.35     10136095.52
#Sta/Elev= 30
  3980.3  283.06    4065   282.6  4225.3   277.8  4255.3  277.81  4305.4  274.84
  4385.6  273.26    4616  264.99  4695.5  266.27  4756.3  264.58  4816.4   261.4
  4846.4  260.94  4863.8  262.02  4868.8  261.35  4896.5  262.55  4926.6  262.18
  4936.6  262.88  4956.6  261.22  4982.4  257.76  5006.7  258.54 5021.19 261.213
  5056.8  262.61  5106.9  261.14    5147  261.13  5379.9  274.14  5433.2  275.97
  5567.9  279.22  5577.9  278.67  5638.1  279.45  5688.9  282.01  5773.9  283.48
#Mann= 6 ,-1 , 0
  3980.3     .05       0  4956.6     .07       0 5021.19     .05       0
  5379.9    .075       0  5433.2     .05       0  5688.9    .075       0
Bank Sta=4956.6,5021.19
XS Rating Curve= 0 ,0
Exp/Cntr=0.3,0.1

Type RM Length L Ch R = 1 ,82902   ,382,382,382
BEGIN DESCRIPTION:
STEWARTS CREEK 162.0
END DESCRIPTION:
XS GIS Cut Line= 3
      3824561.34      10138285.2      3824656.06      10136884.1
      3824727.04     10136114.26
#Sta/Elev= 30
  3595.7  284.35  3765.8  277.67  3880.5  276.34  3910.1  271.48  3915.1  271.75
  3920.6  269.65  3930.6  269.19  3970.7  276.35  4020.8  278.45  4241.3  278.26
  4341.5  275.42  4391.6  275.45  4471.8  270.41  4742.4  260.18  4862.7  259.48
  4950.2  260.64  4955.2  260.55  4962.9  259.96  4978.4  255.09  5013.1  257.37
  5033.2   260.7  5364.6     273  5485.1  281.23  5575.5  285.82  5614.6  286.41
  5625.7  288.19  5724.3  289.03  5729.3  291.03  5736.1  291.15  5773.1  290.46
#Mann= 3 ,-1 , 0
  3595.7     .05       0  4955.2     .07       0  5033.2     .05       0
Bank Sta=4950.2,5033.2
XS Rating Curve= 0 ,0
Exp/Cntr=0.3,0.1

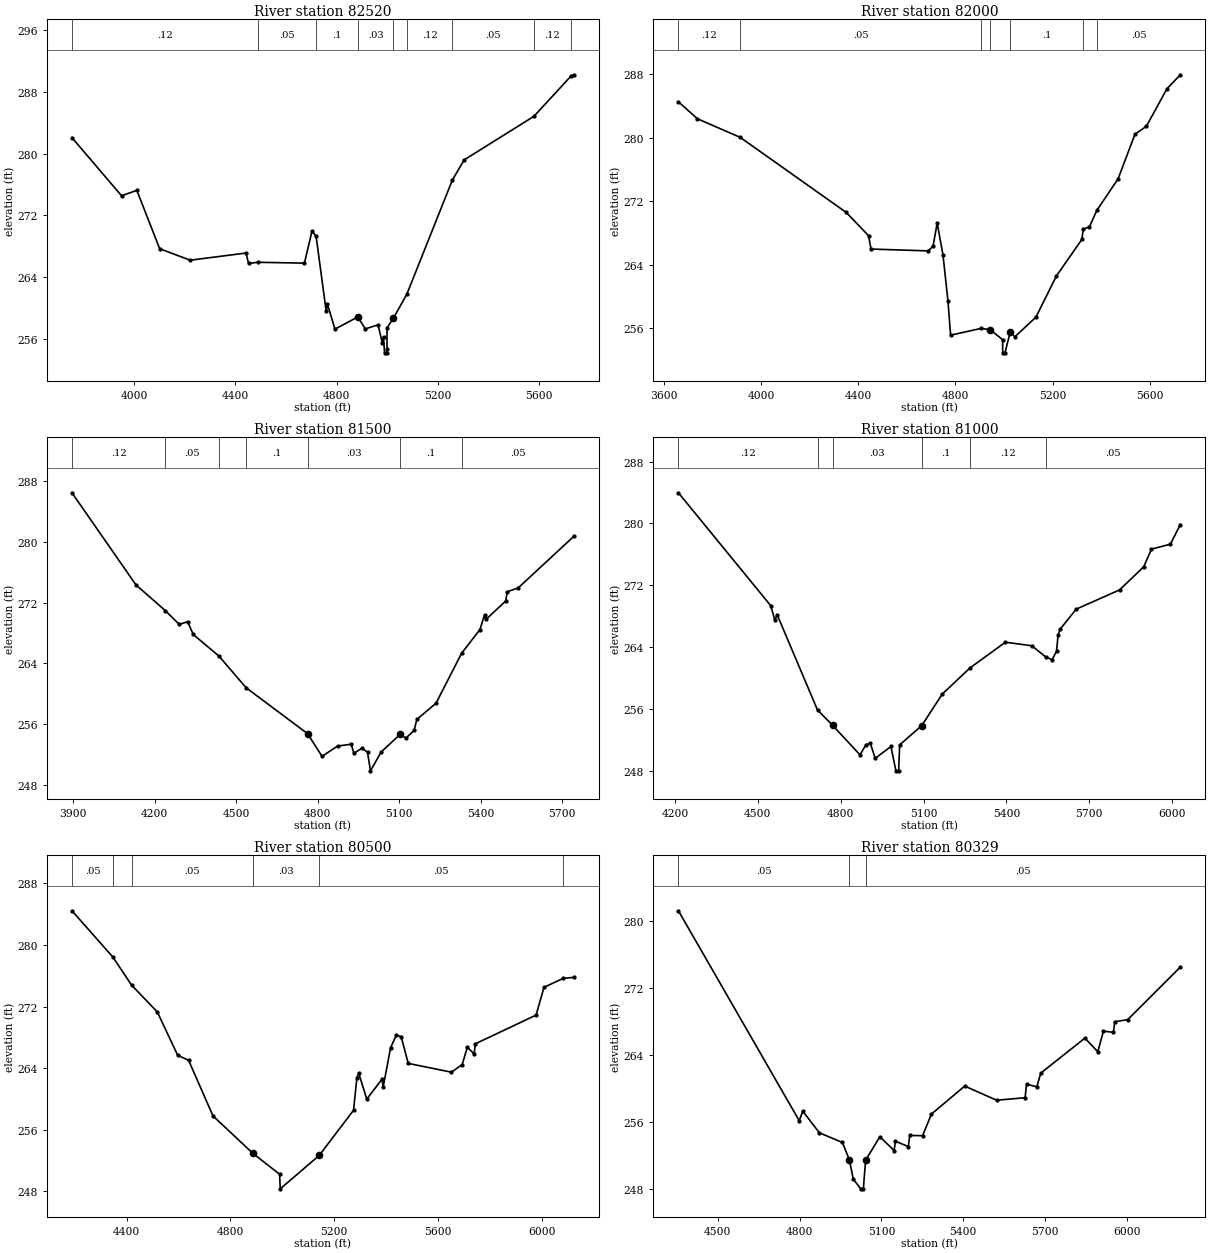
Type RM Length L Ch R = 1 ,82520   ,520,520,520
BEGIN DESCRIPTION:
Mapping XS 95122248
END DESCRIPTION:
XS GIS Cut Line= 3
       3824922.3      10138146.5      3825034.45     10136905.46
      3825016.06     10136167.29
#Sta/Elev= 30
  3753.9  282.09  3950.1  274.55  4010.4  275.26  4100.7  267.69  4221.2   266.2
  4442.1  267.13  4452.2  265.78    4488  265.93  4673.1  265.82  4703.2     270
  4719.3   269.3  4759.2  259.57  4764.2  260.51  4793.6  257.26  4883.9  258.84
    4914   257.3  4964.2  257.82  4980.8   255.5  4985.8  256.28  4989.8  254.19
    4999  254.19  4999.5  254.69  4999.7  257.44  5024.4  258.65  5078.3  261.81
    5258  276.59  5304.5   279.2  5580.3  284.85  5726.3  290.04  5738.4  290.24
#Mann= 9 ,-1 , 0
  3753.9     .12       0    4488     .05       0  4719.3      .1       0
  4883.9     .03       0  5024.4      .1       0  5078.3     .12       0
    5258     .05       0  5580.3     .12       0  5726.3     .05       0
Bank Sta=4883.9,5024.4
XS Rating Curve= 0 ,0
Exp/Cntr=0.3,0.1

Type RM Length L Ch R = 1 ,82000   ,500,500,500
BEGIN DESCRIPTION:
STEWARTS CREEK 161.0
END DESCRIPTION:
XS GIS Cut Line= 3
      3825245.22     10138167.32       3825518.6     10136855.41
      3825282.25     10136168.96
#Sta/Elev= 30
  3659.9   284.5  3737.8  282.37  3913.9  280.03  4350.7  270.58  4442.6  267.65
  4452.8  265.97  4687.8  265.74  4708.2  266.33  4725.1  269.24  4749.1  265.21
  4769.5  259.42  4780.3  255.13  4905.2  255.98  4943.1  255.83  4994.2  254.57
    4995  252.91  5004.3  252.91  5025.7  255.54    5045  254.93  5131.5   257.4
  5216.1  262.59  5320.7  267.18  5326.4  268.46  5351.9  268.78  5382.8  270.86
  5469.9  274.81  5539.3  280.42  5586.3  281.42  5670.9  286.14    5726   287.9
#Mann= 7 ,-1 , 0
  3659.9     .12       0  3913.9     .05       0  4905.2      .1       0
  4943.1     .03       0  5025.7      .1       0  5326.4     .12       0
  5382.8     .05       0
Bank Sta=4943.1,5025.7
XS Rating Curve= 0 ,0
Exp/Cntr=0.3,0.1

Type RM Length L Ch R = 1 ,81500   ,500,500,500
BEGIN DESCRIPTION:
STEWARTS CREEK 160.0
END DESCRIPTION:
XS GIS Cut Line= 3
      3826083.49      10137996.1      3825998.57     10136894.97
      3825899.25     10136158.14
#Sta/Elev= 30
  3895.6  286.46  4131.3  274.33  4239.9  270.93  4290.4  269.14  4321.9  269.48
    4342  267.81  4436.8  264.96  4536.6   260.8  4763.2  254.74  4816.3  251.76
  4873.5  253.11  4923.7  253.36  4933.7  252.15  4963.8  252.84  4983.9  252.29
  4994.7  249.85  5034.2  252.34  5104.8  254.68    5125  254.15  5155.3  255.17
  5165.4  256.62    5236  258.75  5330.4  265.34  5397.5  268.44  5414.9  270.37
  5419.9  269.78  5492.6  272.21  5498.4  273.43  5538.7  273.94  5743.5  280.73
#Mann= 7 ,-1 , 0
  3895.6     .12       0  4239.9     .05       0  4436.8     .12       0
  4536.6      .1       0  4763.2     .03       0  5104.8      .1       0
  5330.4     .05       0
Bank Sta=4763.2,5104.8
XS Rating Curve= 0 ,0
Exp/Cntr=0.3,0.1

Type RM Length L Ch R = 1 ,81000   ,500,500,500
BEGIN DESCRIPTION:
STEWARTS CREEK 159.0
END DESCRIPTION:
XS GIS Cut Line= 3
      3826794.12     10137768.04      3826463.67       10137053.
      3825969.46     10136149.42
#Sta/Elev= 30
  4212.3  283.97    4547  269.35  4561.5  267.48  4569.9  268.19    4716  255.87
  4770.8  253.88  4869.9  250.07    4892   251.4  4907.5  251.54    4925  249.61
  4981.9  251.15  4999.9     248  5009.8     248  5013.6  251.36  5093.4  253.85
  5167.9  257.93  5268.5  261.32  5396.5  264.64  5492.3  264.18  5542.5  262.73
  5565.4  262.38  5581.5  263.45  5587.2  265.58  5594.9  266.33  5652.7  268.91
  5810.1  271.41  5897.4   274.4  5925.4  276.68  5993.8  277.32  6029.9  279.86
#Mann= 6 ,-1 , 0
  4212.3     .12       0    4716      .1       0  4770.8     .03       0
  5093.4      .1       0  5268.5     .12       0  5542.5     .05       0
Bank Sta=4770.8,5093.4
XS Rating Curve= 0 ,0
Exp/Cntr=0.3,0.1

Type RM Length L Ch R = 1 ,80500   ,171,171,171
BEGIN DESCRIPTION:
STEWARTS CREEK 158.0
END DESCRIPTION:
XS GIS Cut Line= 3
      3827079.24     10137618.91      3826889.25     10136830.17
       3826666.9     10135728.28
#Sta/Elev= 30
  4188.7  284.44  4346.3  278.44  4419.1  274.77  4517.8  271.31  4596.5  265.67
  4638.5  265.02  4732.6   257.8  4885.9  252.95  4989.3  250.23    4992  248.33
  5141.9  252.66  5274.5  258.53  5287.5  262.76  5294.9  263.32  5325.5  259.97
  5383.9  262.56    5389  261.57  5417.3  266.64  5439.8  268.32  5458.2   268.1
  5485.5  264.62    5652  263.48  5693.7  264.47  5713.2  266.72  5739.4  265.86
  5744.5  267.17  5978.4  270.89    6009   274.5  6082.9  275.66  6124.1  275.79
#Mann= 6 ,-1 , 0
  4188.7     .05       0  4346.3     .12       0  4419.1     .05       0
  4885.9     .03       0  5141.9     .05       0  6082.9    .075       0
Bank Sta=4885.9,5141.9
XS Rating Curve= 0 ,0
Exp/Cntr=0.3,0.1

Type RM Length L Ch R = 1 ,80329   ,829,829,829
BEGIN DESCRIPTION:
STEWARTS CREEK 157.0
END DESCRIPTION:
XS GIS Cut Line= 3
      3827210.83     10137390.79      3827040.28     10136769.37
      3826817.24     10135594.25
#Sta/Elev= 30
  4355.6  281.26  4798.7  256.17  4811.6  257.31  4872.8  254.72  4957.2  253.57
 4982.84 251.459  4996.5  249.23  5023.8  248.03  5033.8  248.03    5042  251.44
  5094.2  254.26  5146.5  252.61  5151.6  253.72  5198.7  253.08  5203.8  254.41
    5251  254.38  5283.3  256.96  5405.4  260.31  5522.5  258.62    5627  258.92
  5632.1  260.52  5670.1  260.23  5684.3  261.86  5846.2  266.04  5893.4  264.42
  5914.3  266.88  5950.7  266.73  5955.8     268    6003  268.25  6196.1  274.53
#Mann= 3 , 0 , 0
  4355.6     .05       0 4982.84     .07       0    5042     .05       0
Bank Sta=4982.84,5042
XS Rating Curve= 0 ,0
Exp/Cntr=0.3,0.1