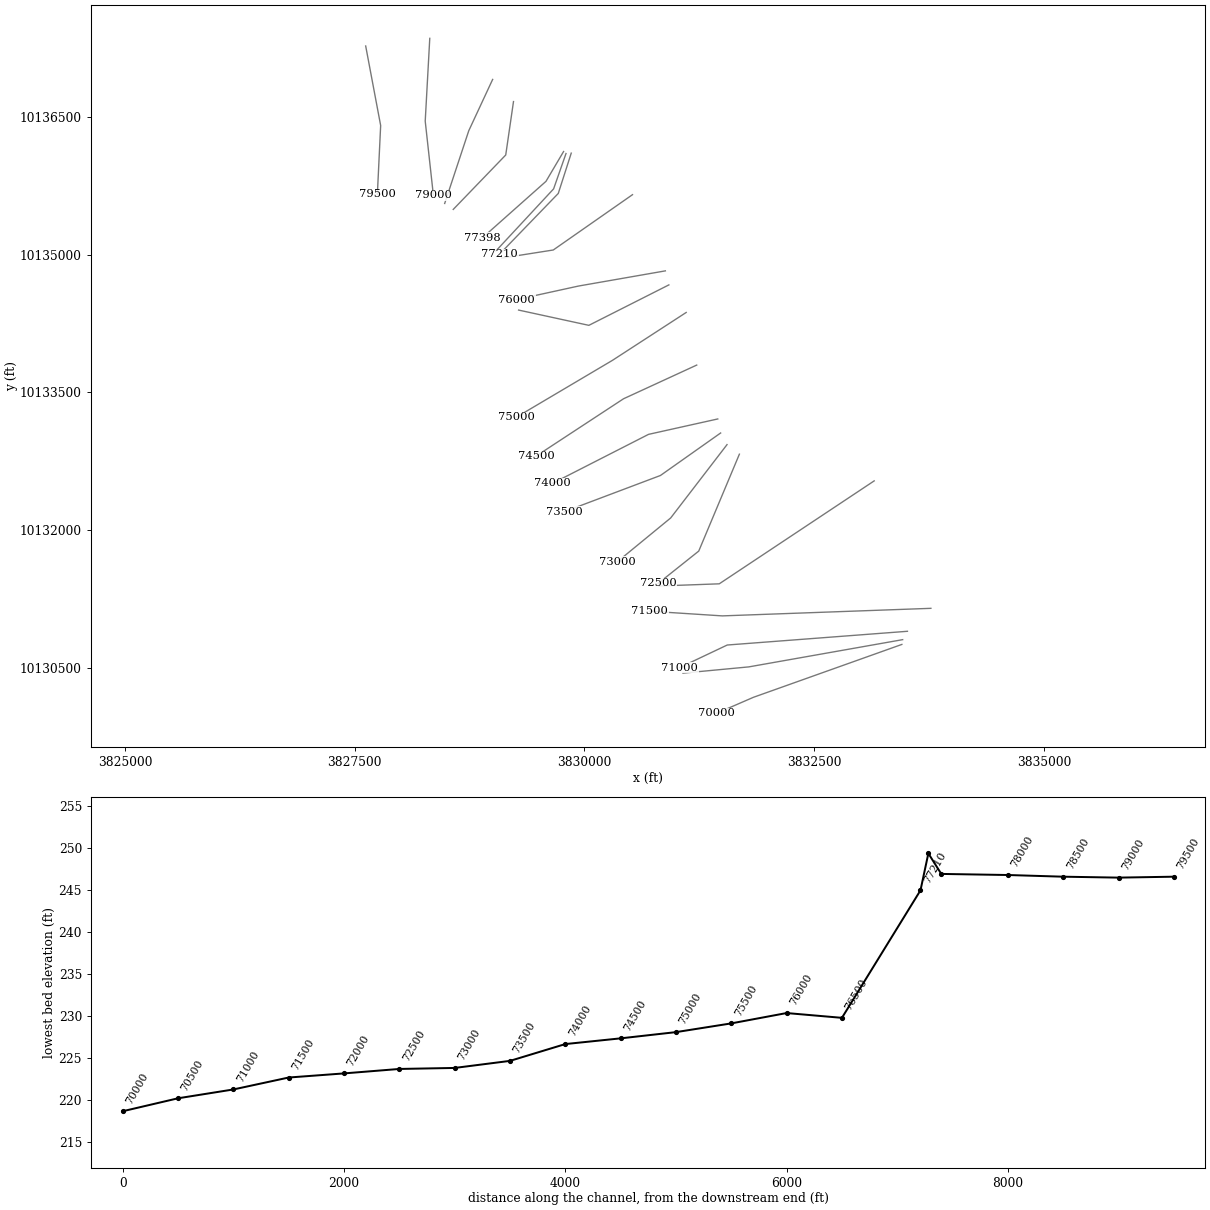
HEC-RAS study STEWARTS CREEK.prj: STEWARTS CREEK Base Level Engineering

--- STEWARTS CREEK.g10 (geometry) --- (continued)

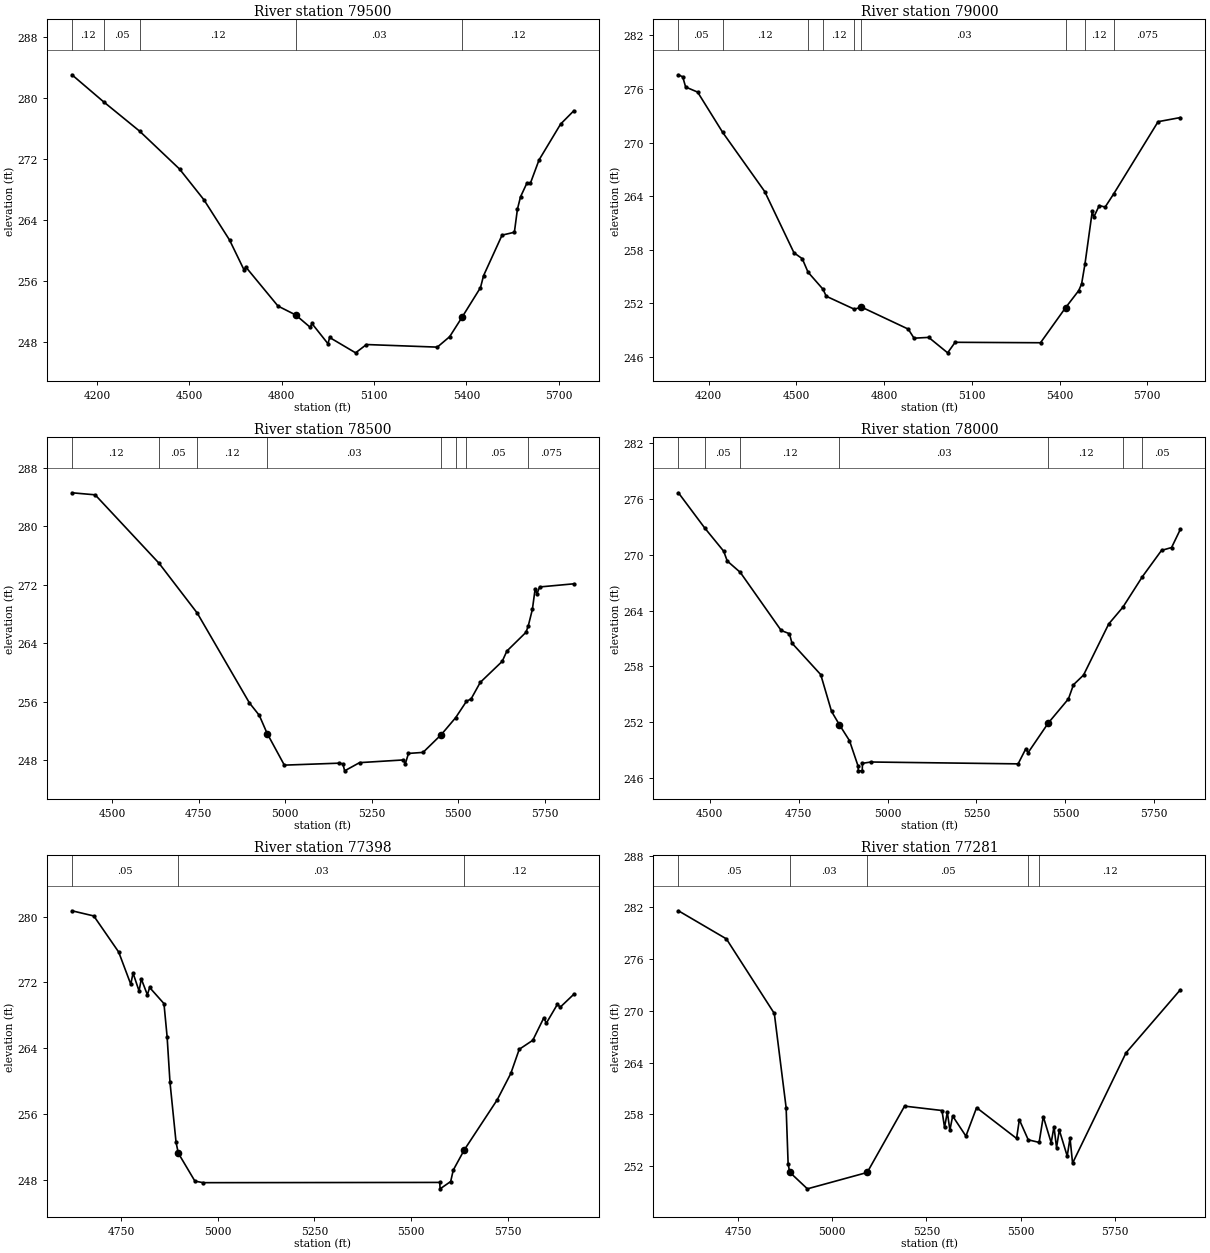
Type RM Length L Ch R = 1 ,79500   ,500,500,500
BEGIN DESCRIPTION:
STEWARTS CREEK 156.0
END DESCRIPTION:
XS GIS Cut Line= 3
      3827618.77     10137272.35      3827781.76     10136406.36
      3827745.98     10135658.11
#Sta/Elev= 30
  4118.8  283.07  4221.4  279.53  4338.6  275.67  4468.2   270.7  4547.5  266.66
  4630.7  261.38  4678.1  257.43  4683.2  257.85  4788.1  252.71  4845.7  251.54
  4893.1  249.91  4898.1  250.43  4950.6  247.76  4955.7  248.59  5040.2  246.57
  5075.4  247.66  5305.6  247.32  5345.7  248.69  5385.7  251.23  5445.8  255.13
  5455.8   256.7  5515.9  262.02  5555.9   262.4  5565.9  265.45  5575.9  267.05
    5596   268.8  5608.1  268.85    5636  271.89  5706.1   276.6  5749.1  278.35
#Mann= 5 ,-1 , 0
  4118.8     .12       0  4221.4     .05       0  4338.6     .12       0
  4845.7     .03       0  5385.7     .12       0
Bank Sta=4845.7,5385.7
XS Rating Curve= 0 ,0
Exp/Cntr=0.3,0.1

Type RM Length L Ch R = 1 ,79000   ,500,500,500
BEGIN DESCRIPTION:
STEWARTS CREEK 155.0
END DESCRIPTION:
XS GIS Cut Line= 3
      3828316.23     10137355.71      3828266.73     10136453.76
      3828355.64     10135645.54
#Sta/Elev= 30
  4096.7  277.59  4111.4  277.36  4121.4  276.22  4162.4  275.65  4248.3  271.13
  4391.8  264.52  4491.9  257.66  4520.2     257    4540  255.49  4591.2  253.58
  4602.1   252.8  4698.5  251.34  4722.3  251.59  4882.5  249.12  4902.5   248.1
  4952.6  248.19  5017.4  246.46  5042.9  247.64    5335  247.59    5421  251.53
  5465.5  253.42  5475.5  254.17    5487   256.4    5512  262.31    5517  261.65
  5535.9  262.95    5556  262.78  5585.5  264.27  5737.1  272.34  5813.1   272.8
#Mann= 9 ,-1 , 0
  4096.7     .05       0  4248.3     .12       0    4540     .05       0
  4591.2     .12       0  4698.5      .1       0  4722.3     .03       0
    5421     .05       0    5487     .12       0  5585.5    .075       0
Bank Sta=4722.3,5421
XS Rating Curve= 0 ,0
Exp/Cntr=0.3,0.1

Type RM Length L Ch R = 1 ,78500   ,500,500,500
BEGIN DESCRIPTION:
STEWARTS CREEK 154.0
END DESCRIPTION:
XS GIS Cut Line= 3
      3829000.52     10136908.24       3828740.5     10136349.03
      3828478.54     10135557.24
#Sta/Elev= 30
  4383.3  284.57  4450.4  284.29  4635.2  274.93  4745.6  268.12  4896.3  255.85
  4924.7  254.16  4947.6  251.67  4997.2  247.35  5156.4  247.62  5166.4  247.52
  5171.5  246.57  5214.6  247.69  5341.5  248.06  5346.7  247.51    5356  248.95
  5398.1  249.09  5450.8  251.52  5492.4  253.84  5523.7  256.08    5537   256.4
  5563.5  258.66  5626.9  261.53  5640.4  262.94  5695.6   265.5  5702.2  266.37
  5714.1  268.63  5722.1  271.43  5727.3  270.77  5735.2   271.7    5834  272.13
#Mann= 8 ,-1 , 0
  4383.3     .12       0  4635.2     .05       0  4745.6     .12       0
  4947.6     .03       0  5450.8     .05       0  5492.4     .12       0
  5523.7     .05       0  5702.2    .075       0
Bank Sta=4947.6,5450.8
XS Rating Curve= 0 ,0
Exp/Cntr=0.3,0.1

Type RM Length L Ch R = 1 ,78000   ,602,602,602
BEGIN DESCRIPTION:
STEWARTS CREEK 153.0
END DESCRIPTION:
XS GIS Cut Line= 3
      3829227.44     10136666.98      3829142.88      10136085.1
      3828571.74     10135492.54
#Sta/Elev= 30
    4412  276.68    4486  272.89  4539.2   270.4  4549.3  269.34  4585.9  268.12
  4700.9  261.87  4724.1  261.52  4731.2  260.51  4812.1  257.12  4842.4  253.17
  4864.4  251.74  4892.9  250.02  4917.2  247.27  4917.7  246.77  4928.7  246.77
  4929.5  247.58  4953.5  247.72    5367  247.52  5388.3  249.12  5395.3  248.74
  5451.9  251.92  5508.5  254.51  5522.6  256.03  5550.9  257.07  5621.7  262.57
  5661.3  264.36  5716.6  267.67  5770.1  270.48  5798.4  270.79    5823  272.74
#Mann= 7 ,-1 , 0
    4412     .12       0    4486     .05       0  4585.9     .12       0
  4864.4     .03       0  5451.9     .12       0  5661.3    .075       0
  5716.6     .05       0
Bank Sta=4864.4,5451.9
XS Rating Curve= 0 ,0
Exp/Cntr=0.3,0.1

Type RM Length L Ch R = 1 ,77398   ,117,117,117
BEGIN DESCRIPTION:
STEWARTS CREEK 152.0
END DESCRIPTION:
XS GIS Cut Line= 3
      3829772.57     10136123.08      3829580.89      10135798.1
      3828892.61     10135186.28
#Sta/Elev= 30
  4622.7  280.72  4679.2  280.09  4743.6   275.7  4774.9  271.78  4780.7  273.15
  4796.3  270.96  4802.1  272.43  4817.8   270.5  4823.6  271.39  4860.7  269.43
  4868.8  265.42  4876.3  259.85    4892  252.55  4897.8  251.24  4940.7  247.84
  4962.1  247.65  5573.9  247.68    5575   246.9  5602.3  247.79    5609  249.18
  5637.4  251.63  5722.7  257.73  5757.8  260.93  5779.6  263.87  5814.7  264.97
  5843.1  267.69  5849.8  267.06  5878.2  269.33  5885.8     269  5920.9  270.57
#Mann= 3 , 0 , 0
  4622.7     .05       0  4897.8     .03       0  5637.4     .12       0
Bank Sta=4897.8,5637.4
XS Rating Curve= 0 ,0
Exp/Cntr=0.3,0.1

Type RM Length L Ch R = 1 ,77281   ,71,71,71
BEGIN DESCRIPTION:
Mapping XS 2b0f7d15
END DESCRIPTION:
XS GIS Cut Line= 3
      3829798.88     10136101.16      3829664.05      10135716.3
      3829035.62     10135039.59
#Sta/Elev= 30
  4592.2  281.61  4719.4  278.35  4846.6  269.69  4877.9  258.76  4883.2  252.25
 4887.22  251.28  4934.3  249.34  5092.9  251.24  5192.1  258.94  5291.3  258.43
  5298.1  256.48  5305.5  258.23  5312.3  256.15  5319.6  257.79  5354.8  255.46
  5383.1  258.76  5489.2  255.19  5496.5  257.36  5520.1  255.03    5549  254.73
    5560  257.72    5581  254.69  5588.4  256.55  5595.2  254.12  5602.5  256.16
  5623.5  253.14  5630.9  255.24  5637.7  252.32  5779.4  265.12  5923.5  272.44
#Mann= 5 ,-1 , 0
  4592.2     .05       0 4887.22     .03       0  5092.9     .05       0
  5520.1      .1       0    5549     .12       0
Bank Sta=4887.22,5092.9
XS Rating Curve= 0 ,0
Exp/Cntr=0.3,0.1

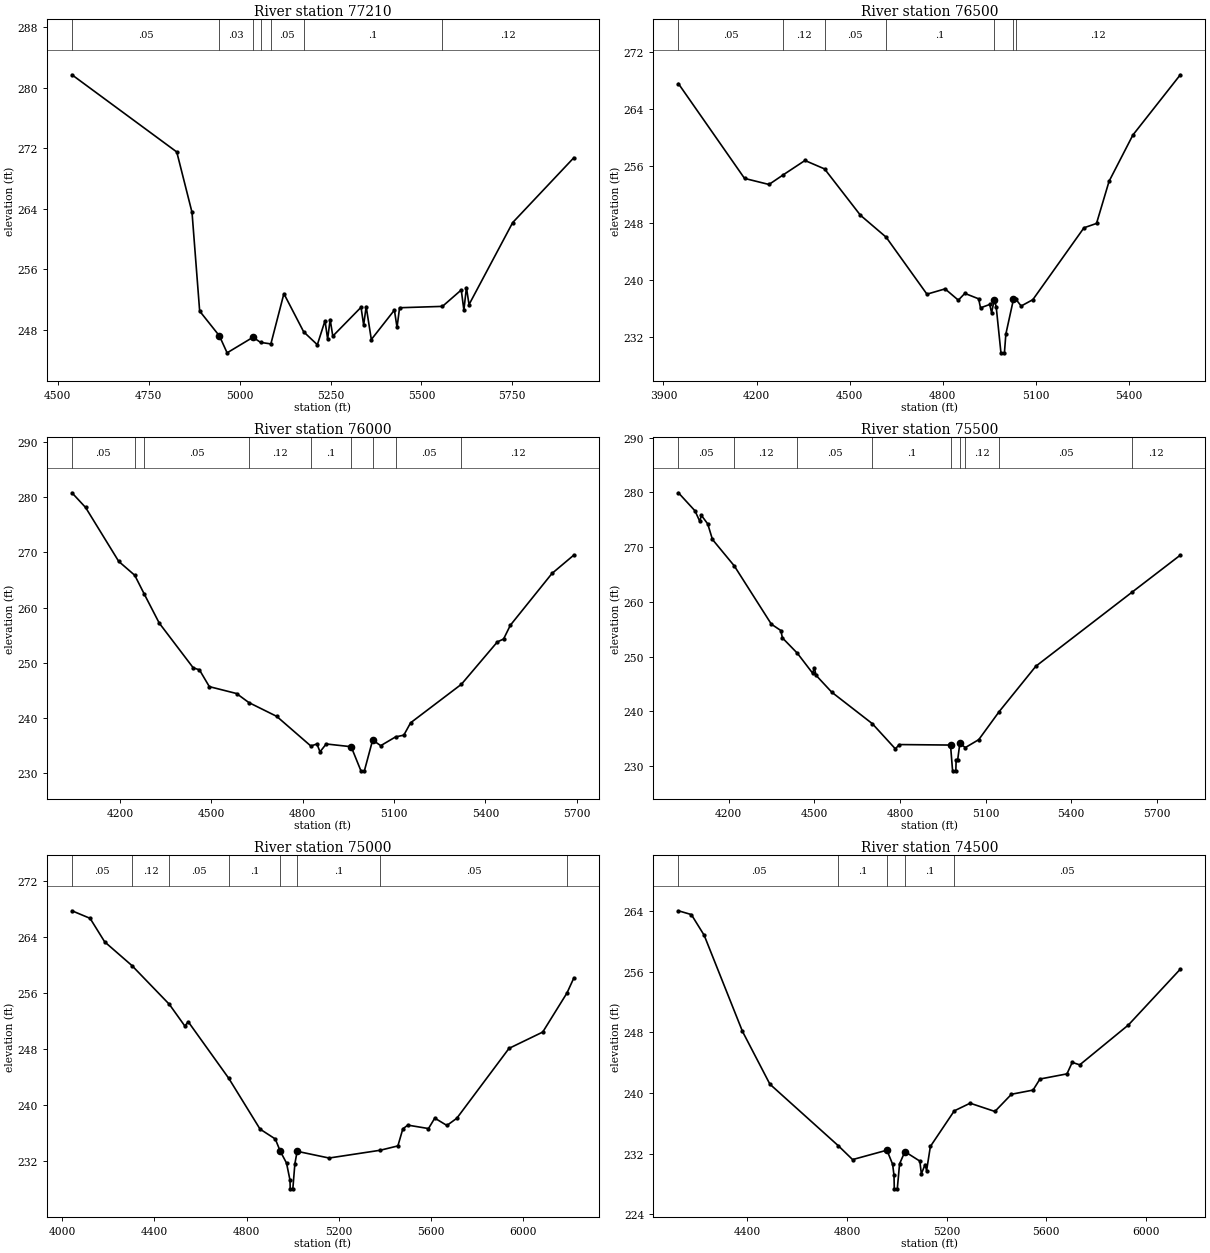
Type RM Length L Ch R = 1 ,77210   ,710,710,710
BEGIN DESCRIPTION:
STEWARTS CREEK 151.0
END DESCRIPTION:
XS GIS Cut Line= 3
      3829855.89     10136105.49      3829714.75     10135666.42
      3829075.85     10135005.28
#Sta/Elev= 30
  4538.8   281.7  4827.1   271.5  4869.1  263.51  4890.1  250.47  4944.4  247.19
  4965.6  244.95  5036.9  247.01  5057.6  246.33    5086  246.13  5121.8  252.77
  5176.3  247.72  5213.8  246.02  5234.9  249.19  5242.1  246.78  5249.1  249.35
  5256.3  247.16    5334  250.97  5341.2  248.62  5348.1  251.07  5362.3  246.71
  5425.8   250.6    5433   248.3    5440  250.91  5557.9  251.09  5609.7  253.26
  5616.9   250.6  5623.9  253.58  5631.1  251.33  5751.2  262.17  5919.4  270.74
#Mann= 7 ,-1 , 0
  4538.8     .05       0  4944.4     .03       0  5036.9     .05       0
  5057.6      .1       0    5086     .05       0  5176.3      .1       0
  5557.9     .12       0
Bank Sta=4944.4,5036.9
XS Rating Curve= 0 ,0
Exp/Cntr=0.3,0.1

Type RM Length L Ch R = 1 ,76500   ,500,500,500
BEGIN DESCRIPTION:
STEWARTS CREEK 150.0
END DESCRIPTION:
XS GIS Cut Line= 3
      3830522.57     10135653.07      3829660.33     10135050.55
      3829100.93     10134962.41
#Sta/Elev= 30
  3948.1   267.5  4161.3  254.22  4240.1  253.37  4285.7  254.71  4356.1  256.73
  4419.3  255.55  4534.9  249.06  4617.7  245.99  4749.4     238  4807.8  238.74
  4850.6  237.16  4871.5  238.11    4916  237.35  4922.1  236.08  4951.8  236.56
  4957.9  235.39  4966.4  237.24  4972.7  236.22    4988  229.78  4999.2  229.78
  5003.8  232.41  5028.3  237.27  5035.5  237.33  5053.1  236.34  5090.8  237.23
  5255.6   247.3  5296.1  247.91  5336.6  253.82  5413.4   260.3  5566.3  268.74
#Mann= 7 ,-1 , 0
  3948.1     .05       0  4285.7     .12       0  4419.3     .05       0
  4617.7      .1       0  4966.4     .07       0  5028.3      .1       0
  5035.5     .12       0
Bank Sta=4966.4,5028.3
XS Rating Curve= 0 ,0
Exp/Cntr=0.3,0.1

Type RM Length L Ch R = 1 ,76000   ,500,500,500
BEGIN DESCRIPTION:
STEWARTS CREEK 149.0
END DESCRIPTION:
XS GIS Cut Line= 3
      3830880.22     10134823.21      3829936.92     10134658.31
      3829262.47     10134510.78
#Sta/Elev= 30
  4042.4  280.84  4087.2  278.17    4196  268.38  4248.6  265.86  4279.9  262.44
    4329  257.18  4440.7  249.05    4461  248.69  4493.5  245.64  4582.8  244.39
  4623.2  242.75  4714.8  240.24  4826.8  234.86  4846.8  235.23  4856.9   233.8
  4877.2  235.23  4959.2  234.73  4991.3  230.35  5002.6  230.35  5029.8  235.95
  5056.3  234.92  5104.9  236.51  5132.1  236.83  5154.3  239.07  5321.2  246.07
  5439.2  253.76  5459.7  254.29  5481.9  256.79  5618.6  266.19  5690.4  269.53
#Mann= 9 ,-1 , 0
  4042.4     .05       0  4248.6     .12       0  4279.9     .05       0
  4623.2     .12       0  4826.8      .1       0  4959.2     .07       0
  5029.8      .1       0  5104.9     .05       0  5321.2     .12       0
Bank Sta=4959.2,5029.8
XS Rating Curve= 0 ,0
Exp/Cntr=0.3,0.1

Type RM Length L Ch R = 1 ,75500   ,500,500,500
BEGIN DESCRIPTION:
STEWARTS CREEK 148.0
END DESCRIPTION:
XS GIS Cut Line= 3
      3830918.38     10134670.42      3830047.66     10134229.92
      3829283.11      10134396.1
#Sta/Elev= 30
  4024.2  279.91  4082.3  276.61    4099   274.7  4104.6  275.79  4126.8  274.23
  4143.5  271.38    4220  266.55  4349.8  255.91    4383  254.75  4388.6   253.4
  4440.9   250.6  4494.5  246.95  4500.1  247.95  4506.7  246.55  4561.3  243.49
  4703.4  237.74  4784.1  233.14  4798.1  233.92  4977.4  233.83  4984.6  229.12
    4996  229.12  4997.1  231.15  5002.5  231.15    5010  234.14  5029.3  233.37
  5076.3  234.82  5147.7  239.93  5276.1  248.22  5614.7  261.81  5782.4  268.52
#Mann= 9 ,-1 , 0
  4024.2     .05       0    4220     .12       0  4440.9     .05       0
  4703.4      .1       0  4977.4     .07       0    5010      .1       0
  5029.3     .12       0  5147.7     .05       0  5614.7     .12       0
Bank Sta=4977.4,5010
XS Rating Curve= 0 ,0
Exp/Cntr=0.3,0.1

Type RM Length L Ch R = 1 ,75000   ,500,500,500
BEGIN DESCRIPTION:
STEWARTS CREEK 147.0
END DESCRIPTION:
XS GIS Cut Line= 3
      3831106.81     10134370.11      3830304.69     10133848.88
      3829256.06     10133227.71
#Sta/Elev= 30
  4043.4  267.79    4122  266.71  4185.3  263.35  4303.2  259.97  4465.5  254.43
  4532.5  251.34  4547.7  251.93  4723.1  243.86  4858.7  236.61  4924.7   235.2
  4946.3  233.45  4973.4  231.76  4988.5  229.32  4989.4  228.08  5000.8  228.08
  5009.6  231.65  5019.4  233.44  5157.9  232.48  5379.4  233.59  5456.1  234.21
  5477.5  236.64    5499  237.18  5588.7  236.69    5616  238.18  5668.6  237.13
  5711.5  238.16  5937.8  248.14  6083.9  250.47    6189  256.05  6218.8   258.2
#Mann= 8 ,-1 , 0
  4043.4     .05       0  4303.2     .12       0  4465.5     .05       0
  4723.1      .1       0  4946.3     .07       0  5019.4      .1       0
  5379.4     .05       0    6189     .12       0
Bank Sta=4946.3,5019.4
XS Rating Curve= 0 ,0
Exp/Cntr=0.3,0.1

Type RM Length L Ch R = 1 ,74500   ,500,500,500
BEGIN DESCRIPTION:
STEWARTS CREEK 146.0
END DESCRIPTION:
XS GIS Cut Line= 3
      3831221.39     10133797.18      3830424.81     10133430.09
      3829473.59     10132805.58
#Sta/Elev= 30
  4122.9  264.03  4174.8  263.53  4226.3   260.8    4380  248.12  4490.2  241.15
  4765.4  233.01  4822.2   231.2    4960  232.44  4982.9  230.58  4988.4  229.11
  4989.6  227.34  5001.6  227.34  5010.8  230.64  5032.2  232.25  5092.1     231
  5098.2  229.32  5113.3  230.54  5119.3  229.75  5134.4  232.93  5230.4  237.63
  5294.1  238.64  5393.5  237.55  5459.9  239.82  5546.6  240.37  5574.4  241.83
  5682.8  242.51  5703.9  244.03  5734.1   243.7  5929.4  248.96  6137.9  256.33
#Mann= 5 ,-1 , 0
  4122.9     .05       0  4765.4      .1       0    4960     .07       0
  5032.2      .1       0  5230.4     .05       0
Bank Sta=4960,5032.2
XS Rating Curve= 0 ,0
Exp/Cntr=0.3,0.1

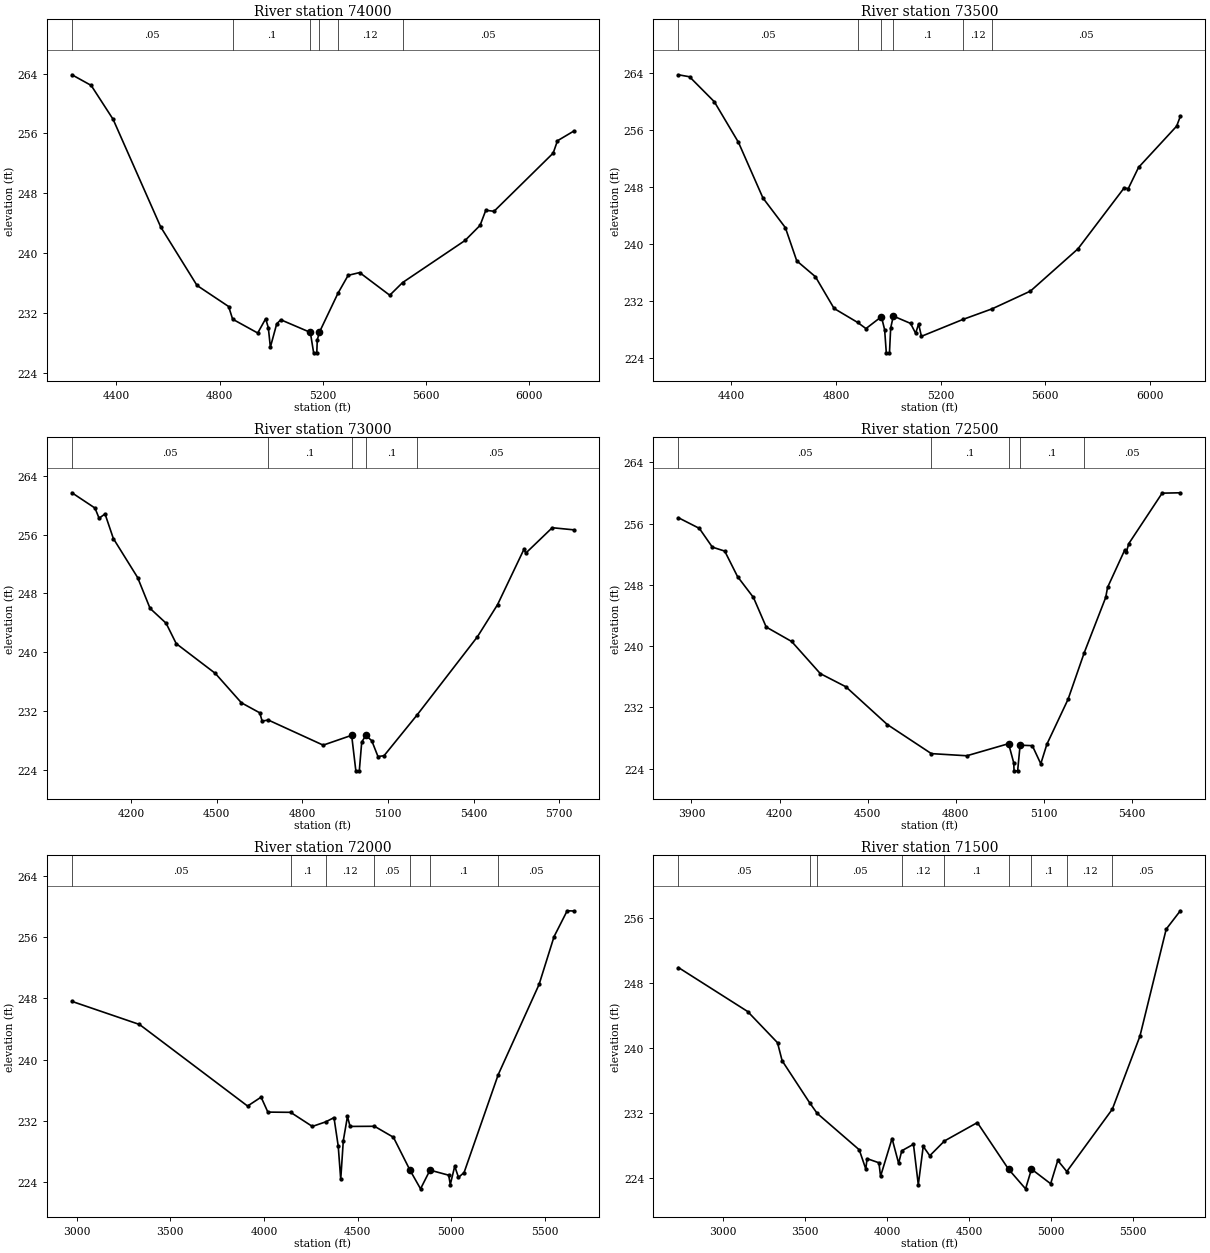
Type RM Length L Ch R = 1 ,74000   ,500,500,500
BEGIN DESCRIPTION:
STEWARTS CREEK 145.0
END DESCRIPTION:
XS GIS Cut Line= 3
      3831450.51     10133210.36      3830697.06     10133042.59
      3829652.35      10132509.2
#Sta/Elev= 30
  4228.1  263.83  4302.5  262.41  4387.7  257.87    4572  243.49  4712.7  235.67
  4835.3  232.85  4850.7  231.16    4948  229.31  4978.7  231.22    4989  230.03
    4997  227.42  5021.6  230.54  5037.4  231.08 5151.87 229.392  5164.7  226.66
  5176.8  226.66  5178.8   228.4  5187.3  229.44    5259  234.63  5298.4  237.02
  5342.9  237.39  5459.6  234.36  5509.2  236.05  5751.4  241.68  5809.6   243.7
  5831.8  245.72  5863.7  245.58  6092.9  253.36  6109.5  255.01    6173  256.31
#Mann= 6 ,-1 , 0
  4228.1     .05       0  4850.7      .1       0 5151.87     .07       0
  5187.3      .1       0    5259     .12       0  5509.2     .05       0
Bank Sta=5151.87,5187.3
XS Rating Curve= 0 ,0
Exp/Cntr=0.3,0.1

Type RM Length L Ch R = 1 ,73500   ,500,500,500
BEGIN DESCRIPTION:
STEWARTS CREEK 144.0
END DESCRIPTION:
XS GIS Cut Line= 3
      3831481.78     10133057.59      3830826.63     10132594.67
      3829781.63     10132200.41
#Sta/Elev= 30
  4197.8  263.75  4240.3  263.47  4335.1  259.96  4427.4  254.25    4521  246.43
  4606.7  242.26  4650.3  237.59  4721.7  235.36    4793   230.9  4883.2  228.93
  4914.9  228.07    4974  229.74  4986.3  227.91  4992.7  224.66  5004.8  224.66
  5009.4  228.14  5019.5  229.83  5085.3   228.8  5104.8  227.41  5116.3  228.72
  5126.9  226.98  5285.3  229.35  5397.5  230.85  5543.8  233.34  5725.5  239.28
  5902.2  247.85  5917.9  247.75  5957.2  250.73  6102.9  256.53  6116.9  257.91
#Mann= 6 ,-1 , 0
  4197.8     .05       0  4883.2      .1       0    4974     .07       0
  5019.5      .1       0  5285.3     .12       0  5397.5     .05       0
Bank Sta=4974,5019.5
XS Rating Curve= 0 ,0
Exp/Cntr=0.3,0.1

Type RM Length L Ch R = 1 ,73000   ,500,500,500
BEGIN DESCRIPTION:
STEWARTS CREEK 143.0
END DESCRIPTION:
XS GIS Cut Line= 3
      3831551.25     10132930.89      3830938.18     10132132.14
      3830357.51     10131655.41
#Sta/Elev= 30
  3993.1   261.7  4073.7  259.62  4088.2  258.23    4109  258.82  4138.1  255.47
  4223.2  250.15  4266.8  245.95  4322.9  243.93  4358.4  241.15  4495.2   237.1
  4586.7  233.09  4651.1  231.72  4659.3   230.6    4681  230.74  4873.2  227.32
  4972.9  228.66  4987.6  223.82  4999.7  223.82  5008.2  227.74  5022.6  228.65
  5043.4  227.92  5065.1  225.77  5086.4  225.88  5202.5  231.45  5413.6  242.09
    5484  246.46  5576.5     254    5583  253.48  5675.6  256.94  5751.3  256.65
#Mann= 5 ,-1 , 0
  3993.1     .05       0    4681      .1       0  4972.9     .07       0
  5022.6      .1       0  5202.5     .05       0
Bank Sta=4972.9,5022.6
XS Rating Curve= 0 ,0
Exp/Cntr=0.3,0.1

Type RM Length L Ch R = 1 ,72500   ,500,500,500
BEGIN DESCRIPTION:
STEWARTS CREEK 142.0
END DESCRIPTION:
XS GIS Cut Line= 3
      3831685.78     10132826.71      3831243.49     10131771.34
      3830802.05     10131419.36
#Sta/Elev= 30
  3855.7  256.77  3926.9  255.38  3971.2  252.93  4013.4  252.41    4057  249.08
  4111.2  246.35  4154.6  242.49  4241.3   240.6  4338.9   236.4  4425.6  234.69
  4566.9  229.75  4716.9  225.95  4837.7  225.67  4979.9  227.25  4997.4  224.74
  4998.5   223.7  5010.7   223.7  5019.1  227.05  5060.7  226.99  5089.5  224.62
  5110.3  227.18  5182.4  233.05  5237.6  239.15  5310.5  246.35  5316.9  247.67
  5374.6  252.49  5380.9  252.27    5389  253.38  5502.7  259.98  5564.6  260.03
#Mann= 5 ,-1 , 0
  3855.7     .05       0  4716.9      .1       0  4979.9     .07       0
  5019.1      .1       0  5237.6     .05       0
Bank Sta=4979.9,5019.1
XS Rating Curve= 0 ,0
Exp/Cntr=0.3,0.1

Type RM Length L Ch R = 1 ,72000   ,500,500,500
BEGIN DESCRIPTION:
STEWARTS CREEK 141.0
END DESCRIPTION:
XS GIS Cut Line= 3
      3833152.81     10132535.91      3831466.72     10131414.79
      3830812.25     10131390.94
#Sta/Elev= 30
  2975.2  247.62  3335.8  244.61  3912.9  233.97  3985.1  235.13  4021.2  233.18
  4142.7  233.15  4258.7  231.31  4330.5  231.91  4374.2  232.46  4396.9  228.74
  4410.2   224.4    4424  229.46  4446.2  232.61  4460.1  231.31  4590.5  231.33
  4691.5   229.9  4778.7  225.67  4778.8 225.656  4836.4  223.17  4886.9  225.61
  4986.6  224.95  4995.2  223.73  5018.9  226.12  5038.9  224.66  5068.9   225.3
  5251.2  238.07  5469.2  249.83  5549.2  256.07  5619.3  259.44  5654.9  259.41
#Mann= 7 ,-1 , 0
  2975.2     .05       0  4142.7      .1       0  4330.5     .12       0
  4590.5     .05       0  4778.7     .07       0  4886.9      .1       0
  5251.2     .05       0
Bank Sta=4778.8,4886.9
XS Rating Curve= 0 ,0
Exp/Cntr=0.3,0.1

Type RM Length L Ch R = 1 ,71500   ,500,500,500
BEGIN DESCRIPTION:
STEWARTS CREEK 140.0
END DESCRIPTION:
XS GIS Cut Line= 3
      3833769.99     10131147.86      3831499.58     10131065.53
      3830711.93     10131116.55
#Sta/Elev= 30
  2728.1  249.94  3150.5  244.52  3332.5  240.68  3360.7  238.46  3527.9   233.3
  3574.2  231.98    3831  227.49    3871  225.12  3878.7   226.4    3951  225.89
    3961  224.23  4031.1  228.88  4071.1  225.83  4090.4  227.37  4161.7  228.17
  4191.2  223.18  4221.2  227.91  4261.2  226.76  4350.9  228.58  4551.4  230.84
  4741.6   225.1  4845.5  222.68  4881.6  225.11  4998.4  223.31  5041.8  226.18
  5096.9  224.81  5374.6  232.49  5542.9  241.48  5703.2  254.67  5789.3  256.93
#Mann= 9 ,-1 , 0
  2728.1     .05       0  3527.9     .12       0  3574.2     .05       0
  4090.4     .12       0  4350.9      .1       0  4741.6     .07       0
  4881.6      .1       0  5096.9     .12       0  5374.6     .05       0
Bank Sta=4741.6,4881.6
XS Rating Curve= 0 ,0
Exp/Cntr=0.3,0.1

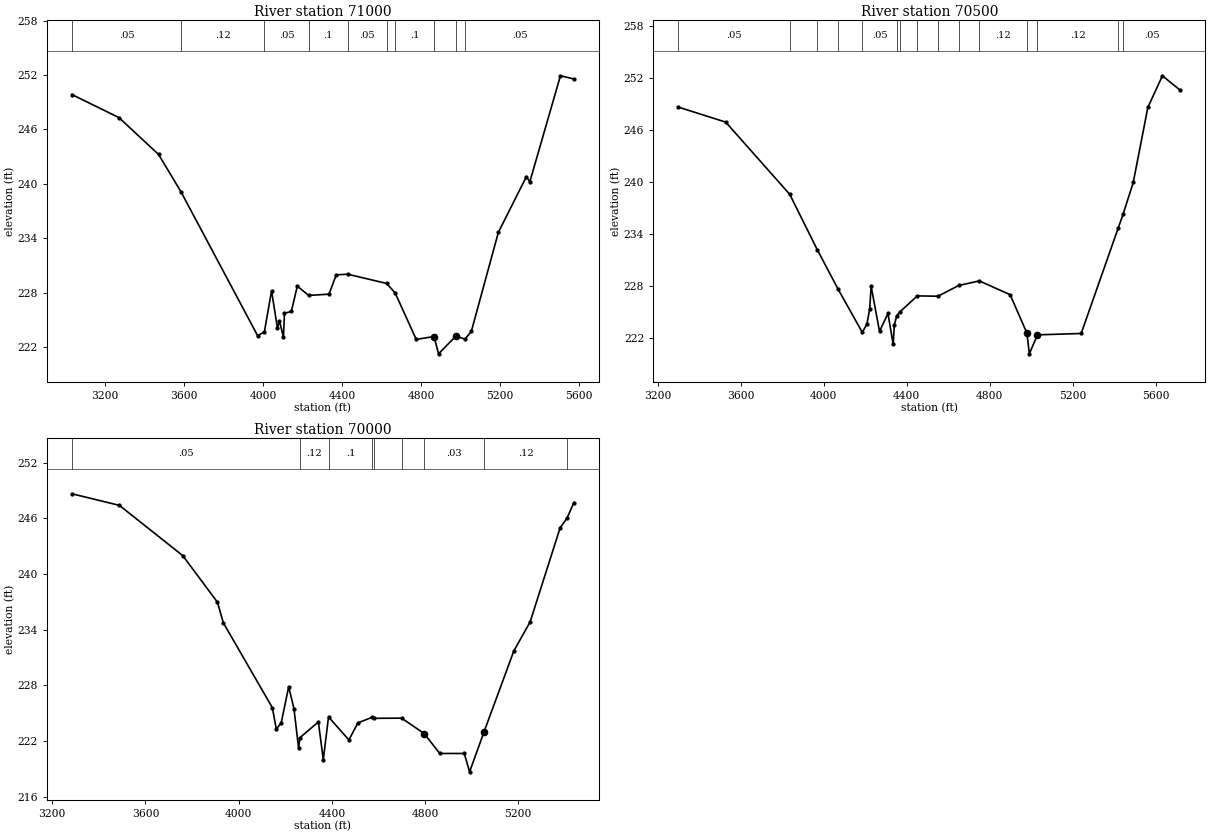
Type RM Length L Ch R = 1 ,71000   ,500,500,500
BEGIN DESCRIPTION:
STEWARTS CREEK 139.0
END DESCRIPTION:
XS GIS Cut Line= 3
      3833514.73     10130897.86      3831553.53     10130748.26
      3831036.48     10130502.91
#Sta/Elev= 30
  3033.1  249.85  3270.7  247.31  3471.2  243.25  3585.9  239.08  3972.3  223.27
  4006.5  223.66  4042.9  228.21    4073  224.07    4083  224.89  4103.1   223.1
  4108.3  225.73  4143.2  225.94  4173.3  228.73  4230.7   227.7  4333.7  227.84
  4370.1  229.97    4428  230.04  4625.4  229.02  4668.5  227.96    4775  222.85
  4865.3  223.17  4887.6  221.26  4975.6  223.22  5021.8  222.88  5053.9  223.75
  5190.3  234.65  5332.2   240.8  5349.4  240.22  5504.4  251.92  5572.3  251.57
#Mann= 10 ,-1 , 0
  3033.1     .05       0  3585.9     .12       0  4006.5     .05       0
  4230.7      .1       0    4428     .05       0  4625.4     .12       0
  4668.5      .1       0  4865.3     .07       0  4975.6     .12       0
  5021.8     .05       0
Bank Sta=4865.3,4975.6
XS Rating Curve= 0 ,0
Exp/Cntr=0.3,0.1

Type RM Length L Ch R = 1 ,70500   ,500,500,500
BEGIN DESCRIPTION:
STEWARTS CREEK 138.0
END DESCRIPTION:
XS GIS Cut Line= 3
       3833462.7     10130806.72      3831788.37      10130510.1
      3831071.98     10130442.21
#Sta/Elev= 30
  3299.6  248.69  3527.7  246.96  3836.4  238.62  3969.5  232.21  4068.1  227.74
  4186.2  222.69  4208.4  223.64  4222.1  225.42  4228.7  228.03  4269.3   222.8
  4309.9  224.87  4335.3   221.3  4340.4  223.51  4352.2  224.61  4366.8  225.04
  4451.7   226.9  4551.2  226.86  4650.8   228.1  4750.3  228.63    4899  227.04
  4980.2  222.59  4991.5  220.21  5030.7   222.4  5241.6  222.56  5419.5  234.69
  5443.6  236.32  5492.7     240    5563  248.66  5633.3  252.31  5719.6  250.63
#Mann= 15 ,-1 , 0
  3299.6     .05       0  3836.4     .12       0  3969.5     .05       0
  4068.1     .12       0  4186.2     .05       0  4352.2     .12       0
  4366.8     .05       0  4451.7      .1       0  4551.2     .05       0
  4650.8      .1       0  4750.3     .12       0  4980.2     .07       0
  5030.7     .12       0  5419.5      .1       0  5443.6     .05       0
Bank Sta=4980.2,5030.7
XS Rating Curve= 0 ,0
Exp/Cntr=0.3,0.1

Type RM Length L Ch R = 1 ,70000   ,500,500,500
BEGIN DESCRIPTION:
STEWARTS CREEK 137.0
END DESCRIPTION:
XS GIS Cut Line= 3
      3833454.04     10130754.65      3831838.22      10130178.7
      3831435.79     10130003.78
#Sta/Elev= 30
  3284.6  248.65  3488.2   247.4  3760.3  241.98    3909  236.96  3934.5  234.73
  4144.9  225.58  4161.7  223.27  4182.9  223.96  4214.8  227.85  4237.4  225.49
  4257.3  221.25    4263  222.35  4342.2  224.05  4363.4  219.99  4385.8  224.59
  4473.3  222.11    4512  223.95    4573  224.55  4582.9  224.44  4699.3  224.46
  4796.4   222.8  4863.3  220.65  4968.5  220.65  4991.3  218.67  5053.1  222.97
  5181.3  231.71  5251.2  234.84  5379.7  244.97  5409.4  246.02  5438.8  247.69
#Mann= 9 ,-1 , 0
  3284.6     .05       0    4263     .12       0  4385.8      .1       0
    4573     .05       0  4582.9      .1       0  4699.3     .12       0
  4796.4     .03       0  5053.1     .12       0  5409.4     .05       0
Bank Sta=4796.4,5053.1
XS Rating Curve= 0 ,0
Exp/Cntr=0.3,0.1