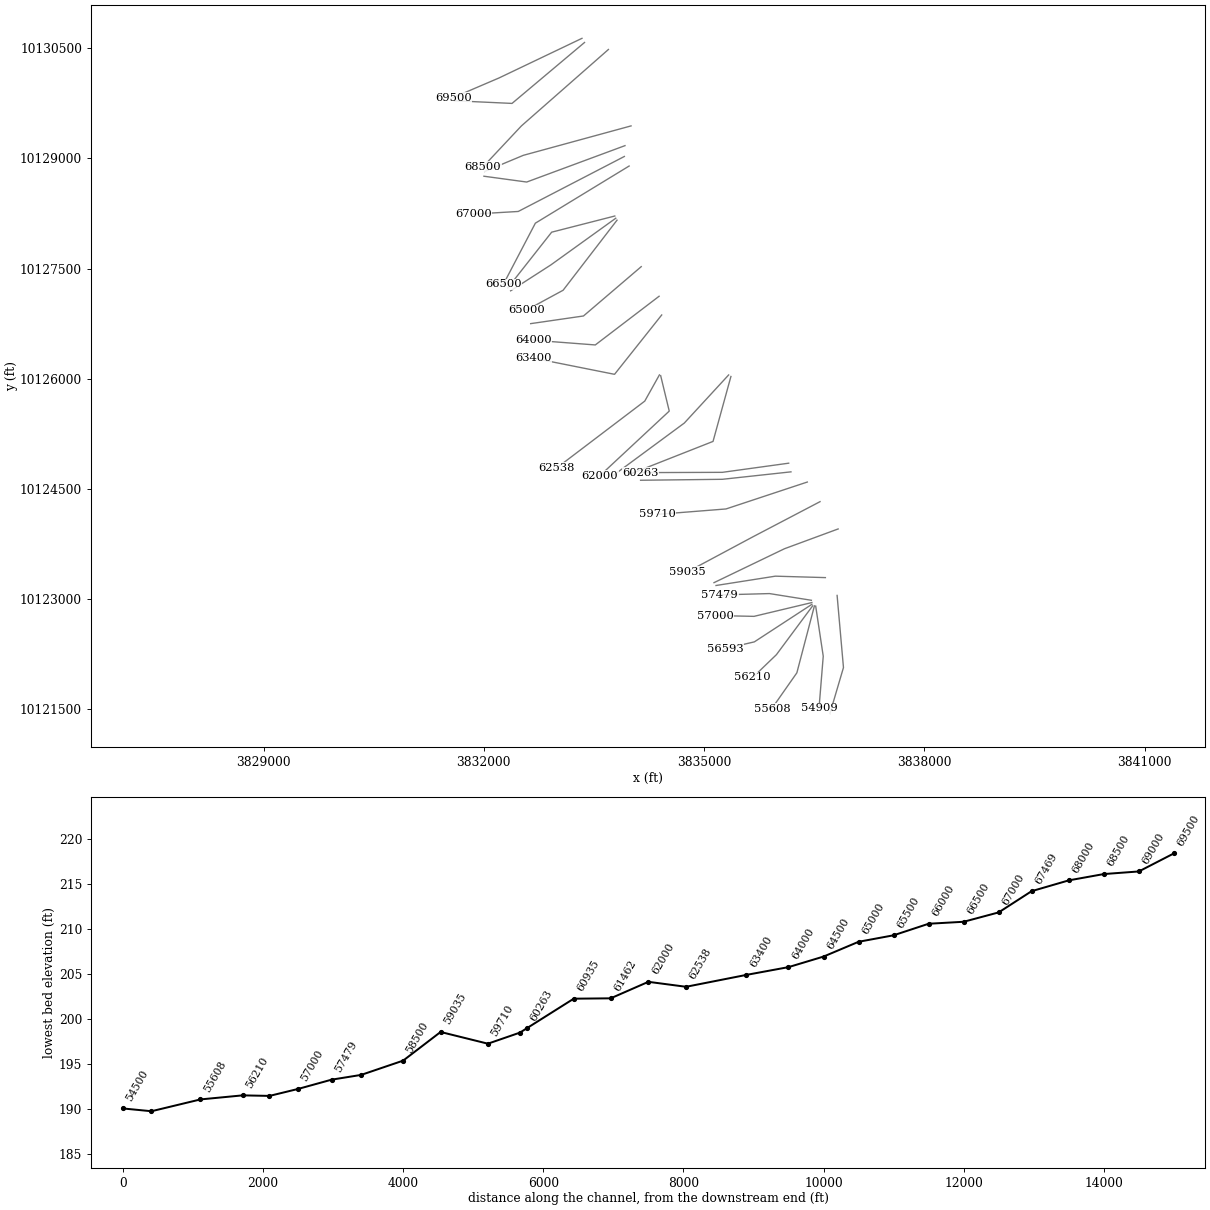
HEC-RAS study STEWARTS CREEK.prj: STEWARTS CREEK Base Level Engineering

--- STEWARTS CREEK.g10 (geometry) --- (continued)

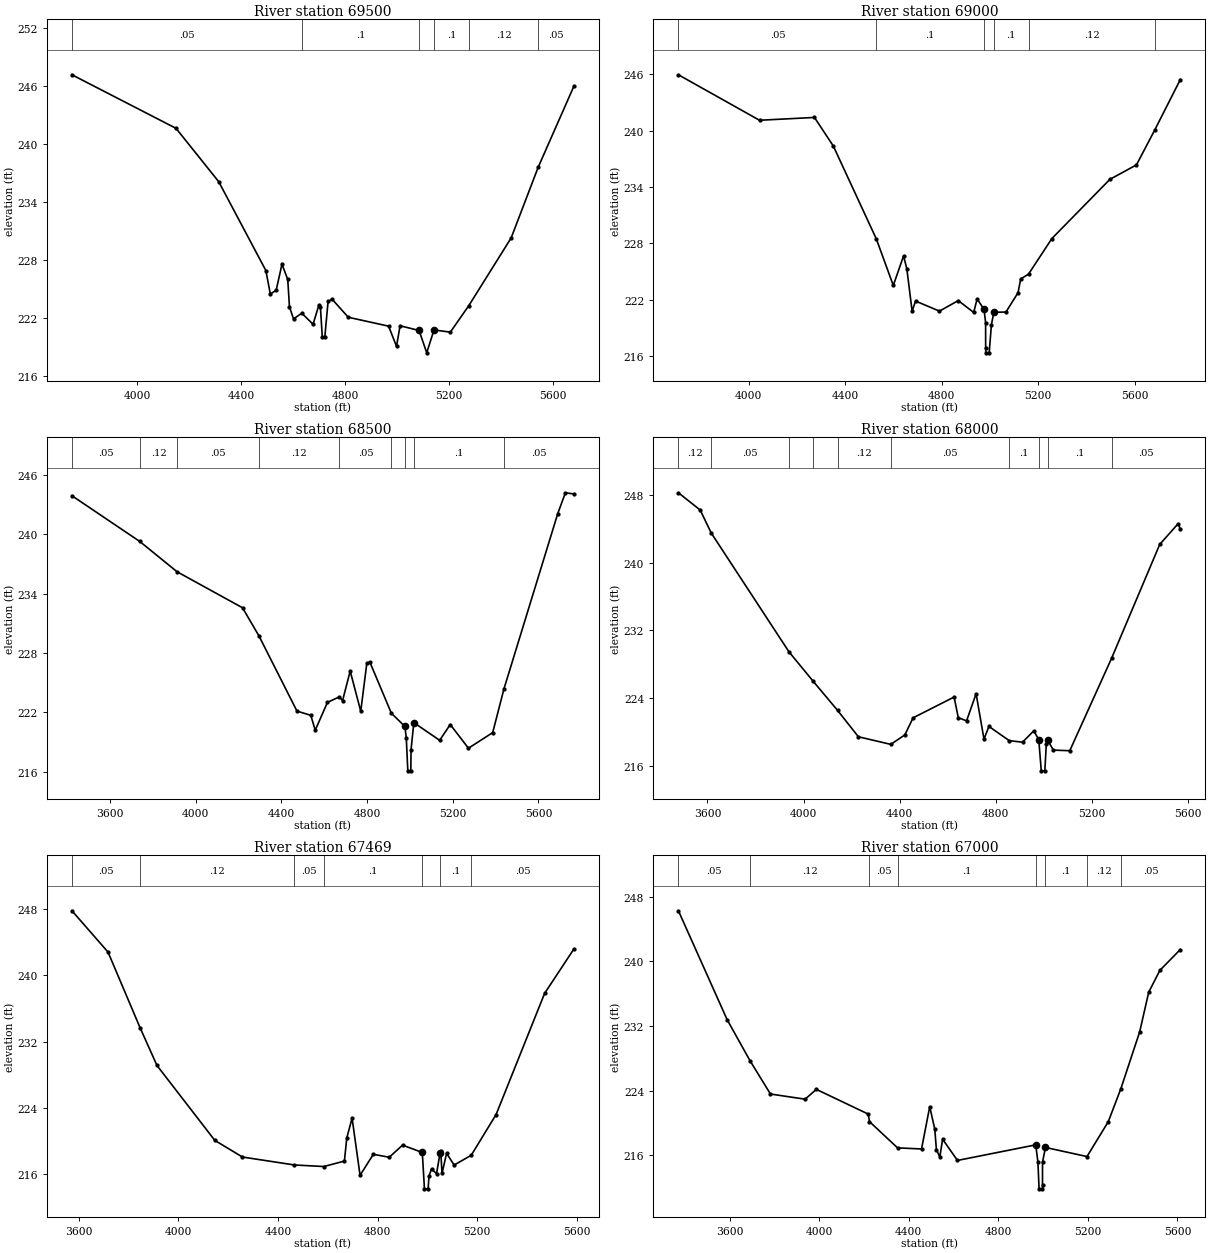
Type RM Length L Ch R = 1 ,69500   ,500,500,500
BEGIN DESCRIPTION:
STEWARTS CREEK 136.0
END DESCRIPTION:
XS GIS Cut Line= 3
      3833336.79     10130637.44      3832207.95     10130097.79
      3831583.37     10129830.17
#Sta/Elev= 30
  3748.8  247.12  4149.2  241.58  4313.4  236.06  4494.8  226.87    4512  224.43
  4534.6  224.85  4556.7  227.53  4578.9  225.95  4585.5  223.12  4601.1  221.87
  4633.1  222.46  4676.3  221.31  4698.9  223.33  4704.5  223.11  4711.9  219.97
  4721.6  220.03  4734.1  223.68  4749.8   223.9  4811.7  222.04  4966.9  221.12
  4997.3  219.03    5011  221.16 5084.14 220.673  5113.6  218.36  5141.5  220.73
  5204.4   220.5  5275.6  223.25  5438.4  230.25  5542.2  237.55  5679.5  245.93
#Mann= 6 ,-1 , 0
  3748.8     .05       0  4633.1      .1       0 5084.14     .07       0
  5141.5      .1       0  5275.6     .12       0  5542.2     .05       0
Bank Sta=5084.14,5141.5
XS Rating Curve= 0 ,0
Exp/Cntr=0.3,0.1

Type RM Length L Ch R = 1 ,69000   ,500,500,500
BEGIN DESCRIPTION:
STEWARTS CREEK 135.0
END DESCRIPTION:
XS GIS Cut Line= 3
       3833371.5       10130581.      3832383.98     10129750.38
      3831596.32     10129786.75
#Sta/Elev= 30
  3709.6  245.95  4045.5  241.11  4273.1  241.41  4351.2  238.37  4529.6  228.47
  4599.6  223.53  4642.1  226.67  4655.6  225.32  4677.6   220.8  4691.9  221.87
  4790.8   220.8  4868.8  221.92  4932.6  220.66  4946.9   222.1  4975.5  220.98
    4982  219.58  4982.2  216.86  4982.7  216.36  4996.8  216.36  5006.1  219.37
  5016.2  220.68  5066.2   220.7  5116.3  222.76  5127.4  224.22  5159.8  224.74
  5256.4  228.52  5496.7  234.82  5606.8  236.36  5682.9  240.09  5788.5  245.44
#Mann= 6 ,-1 , 0
  3709.6     .05       0  4529.6      .1       0  4975.5     .07       0
  5016.2      .1       0  5159.8     .12       0  5682.9     .05       0
Bank Sta=4975.5,5016.2
XS Rating Curve= 0 ,0
Exp/Cntr=0.3,0.1

Type RM Length L Ch R = 1 ,68500   ,500,500,500
BEGIN DESCRIPTION:
STEWARTS CREEK 134.0
END DESCRIPTION:
XS GIS Cut Line= 3
      3833697.02     10130485.51      3832511.42     10129443.25
      3831987.93     10128884.99
#Sta/Elev= 30
  3421.4  243.92  3738.2  239.29  3912.6  236.22  4217.9  232.58  4294.2  229.75
  4472.2  222.12  4536.7  221.69  4557.6  220.18  4614.5     223  4670.4  223.56
  4685.2  223.18  4720.8  226.17  4770.1   222.1  4798.6  226.99  4812.8  227.07
  4913.1   221.9    4976  220.57  4982.7  219.43  4989.9  216.07    5004  216.07
  5004.9  218.19    5018  220.95  5138.7  219.16    5188  220.76    5273  218.36
  5386.3  219.94  5438.9  224.37  5690.1  242.11  5725.8  244.22  5765.3   244.1
#Mann= 9 ,-1 , 0
  3421.4     .05       0  3738.2     .12       0  3912.6     .05       0
  4294.2     .12       0  4670.4     .05       0  4913.1      .1       0
    4976     .07       0    5018      .1       0  5438.9     .05       0
Bank Sta=4976,5018
XS Rating Curve= 0 ,0
Exp/Cntr=0.3,0.1

Type RM Length L Ch R = 1 ,68000   ,531,531,531
BEGIN DESCRIPTION:
STEWARTS CREEK 133.0
END DESCRIPTION:
XS GIS Cut Line= 3
      3834005.26     10129443.88      3832538.19     10129042.83
      3832013.06     10128823.22
#Sta/Elev= 30
  3479.1  248.26  3569.7  246.22    3616  243.49  3939.4  229.45  4040.7  225.95
  4141.9  222.52  4228.6   219.4  4363.5   218.5  4421.9  219.62  4456.4  221.64
  4627.1   224.1  4644.6  221.66    4679  221.28  4718.8  224.49  4751.5  219.13
  4772.3  220.62  4856.9  218.94  4912.1  218.76  4958.9   220.1  4979.6  219.07
  4990.2  215.37    5005  215.37  5011.2  218.56  5017.1  218.96  5040.9  217.82
  5108.8  217.75  5283.4  228.71  5483.4  242.15  5560.2  244.61  5569.2  243.96
#Mann= 10 ,-1 , 0
  3479.1     .12       0    3616     .05       0  3939.4     .12       0
  4040.7     .05       0  4141.9     .12       0  4363.5     .05       0
  4856.9      .1       0  4979.6     .07       0  5017.1      .1       0
  5283.4     .05       0
Bank Sta=4979.6,5017.1
XS Rating Curve= 0 ,0
Exp/Cntr=0.3,0.1

Type RM Length L Ch R = 1 ,67469   ,469,469,469
BEGIN DESCRIPTION:
STEWARTS CREEK 132.0
END DESCRIPTION:
XS GIS Cut Line= 3
      3833922.74     10129174.77       3832583.9     10128678.67
      3832001.46     10128757.91
#Sta/Elev= 30
  3572.2  247.82  3716.9  242.83  3846.3  233.63  3913.6   229.1    4146  220.03
  4256.9  218.02  4465.2  217.06  4583.7  216.87  4666.3  217.53  4675.9  220.32
  4697.2  222.73  4729.2  215.81  4782.5  218.35  4846.5  217.99  4899.8  219.46
  4979.2  218.57  4987.8  214.17  5002.6  214.17  5006.1  215.74  5016.2  216.57
  5036.4  216.01 5050.66 218.536  5053.2  218.76  5058.3  216.03  5076.7  218.47
    5107  217.05  5175.6  218.23  5275.5  223.16  5470.3  237.82  5587.8  243.19
#Mann= 7 ,-1 , 0
  3572.2     .05       0  3846.3     .12       0  4465.2     .05       0
  4583.7      .1       0  4979.2     .07       0 5050.66      .1       0
  5175.6     .05       0
Bank Sta=4979.2,5050.66
XS Rating Curve= 0 ,0
Exp/Cntr=0.3,0.1

Type RM Length L Ch R = 1 ,67000   ,500,500,500
BEGIN DESCRIPTION:
STEWARTS CREEK 131.0
END DESCRIPTION:
XS GIS Cut Line= 3
      3833914.06      10129027.2      3832468.61      10128277.5
      3831856.77     10128241.61
#Sta/Elev= 30
  3371.7  246.28  3589.2  232.79  3691.8  227.68  3782.7  223.57  3937.6  222.93
  3987.5  224.15  4219.6  221.08  4224.7  220.16  4350.1   216.9  4457.3  216.76
  4493.9     222  4516.5  219.21  4523.7  216.69    4539  215.76  4551.4  217.97
  4617.8  215.34  4967.1  217.27    4977  215.15  4982.2  211.82    4997  211.82
  4997.5  212.32  4997.6  215.14  5010.8  216.95  5196.1  215.82  5291.3  220.15
  5347.4  224.23  5431.5  231.28  5471.6  236.18  5521.7   238.9  5612.9  241.48
#Mann= 8 ,-1 , 0
  3371.7     .05       0  3691.8     .12       0  4224.7     .05       0
  4350.1      .1       0  4967.1     .07       0  5010.8      .1       0
  5196.1     .12       0  5347.4     .05       0
Bank Sta=4967.1,5010.8
XS Rating Curve= 0 ,0
Exp/Cntr=0.3,0.1

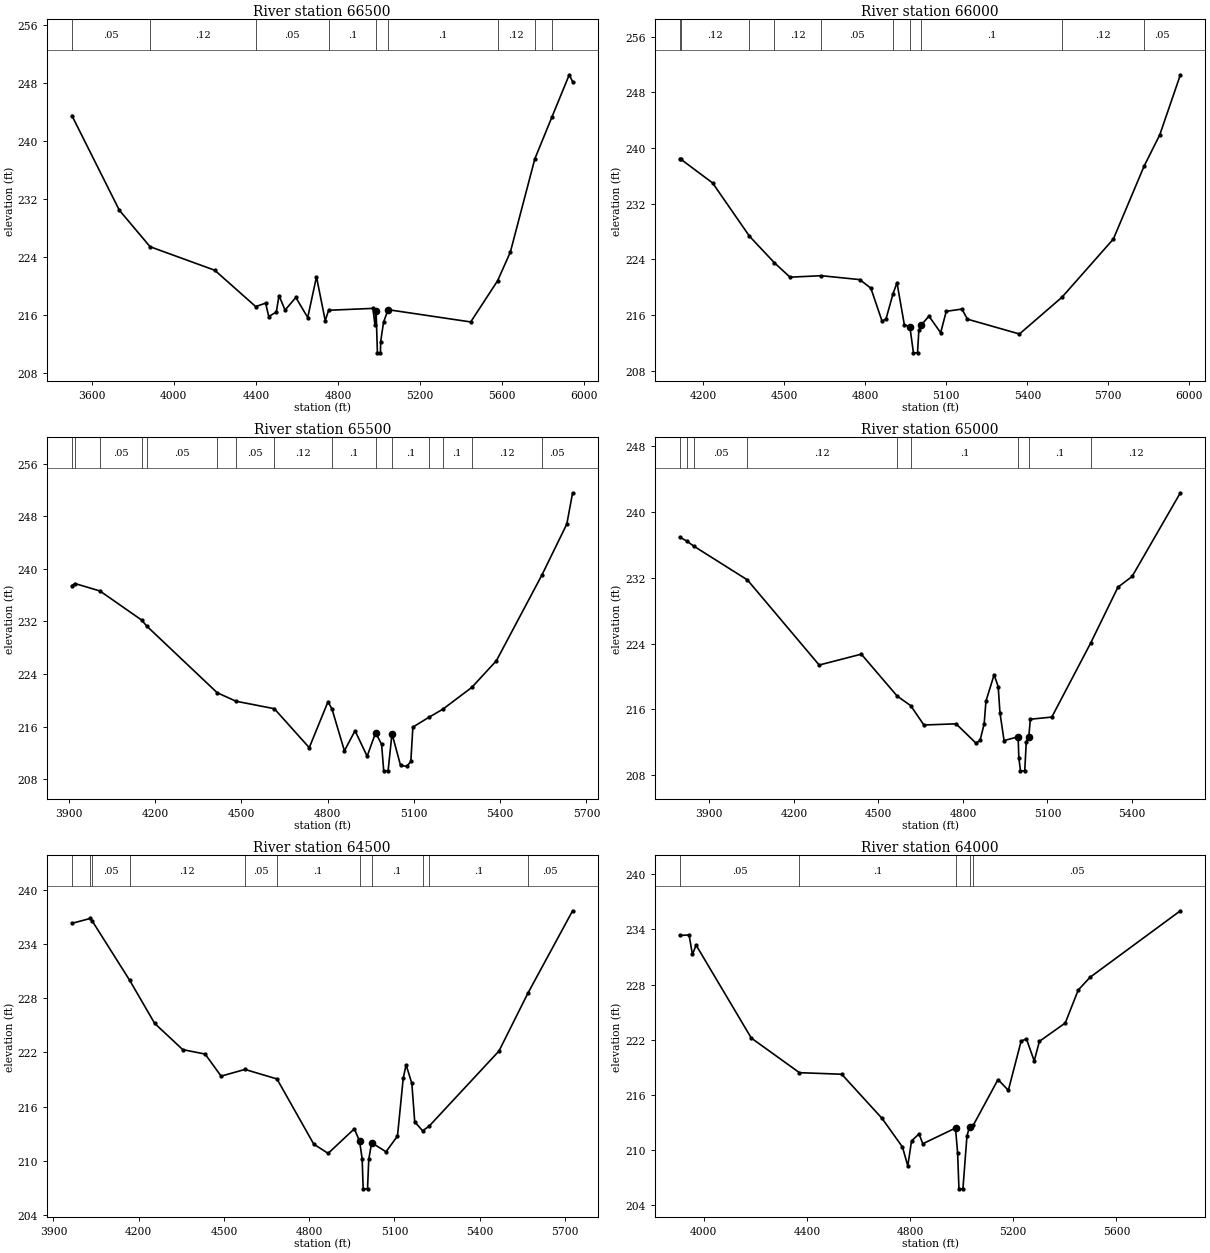
Type RM Length L Ch R = 1 ,66500   ,500,500,500
BEGIN DESCRIPTION:
STEWARTS CREEK 130.0
END DESCRIPTION:
XS GIS Cut Line= 3
      3833979.14     10128896.98       3832701.8     10128117.85
      3832264.78     10127282.46
#Sta/Elev= 30
  3503.8   243.5  3734.8  230.45  3884.8  225.41  4199.6  222.17  4399.2  217.16
  4447.4  217.63  4462.8  215.79  4499.6   216.4  4512.7  218.68  4542.2  216.67
  4594.5  218.42  4652.6  215.65  4695.2  221.26  4737.8  215.22  4754.3  216.65
  4970.2  216.91  4979.8  214.67  4985.6  216.53    4992  210.78  5006.8  210.78
  5007.7   212.3  5021.9  215.01    5044  216.73  5446.5  215.04  5577.3  220.71
  5639.5  224.67  5758.8  237.53  5841.3  243.24  5926.4  249.12  5942.8  248.17
#Mann= 9 ,-1 , 0
  3503.8     .05       0  3884.8     .12       0  4399.2     .05       0
  4754.3      .1       0  4985.6     .07       0    5044      .1       0
  5577.3     .12       0  5758.8     .05       0  5841.3     .12       0
Bank Sta=4985.6,5044
XS Rating Curve= 0 ,0
Exp/Cntr=0.3,0.1

Type RM Length L Ch R = 1 ,66000   ,500,500,500
BEGIN DESCRIPTION:
STEWARTS CREEK 129.0
END DESCRIPTION:
XS GIS Cut Line= 3
      3833783.83     10128215.57      3832923.92      10127995.2
       3832326.1      10127235.4
#Sta/Elev= 30
  4112.3  238.48  4116.9  238.39  4234.2  234.99  4370.8  227.33  4463.4   223.5
  4521.1  221.44  4636.7  221.65  4779.2  221.09  4820.4  219.86  4861.7  215.14
  4876.4  215.41    4902  218.99  4917.2  220.65  4944.3  214.62    4965  214.28
  4978.1  210.56  4993.2  210.56  4998.2  213.79  5006.7  214.54  5035.6  215.84
  5078.9  213.45  5099.7  216.53  5157.5  216.85  5178.3   215.4  5370.8  213.27
  5528.4  218.56  5718.7  226.93  5832.4   237.4  5890.4   241.9  5966.8  250.54
#Mann= 10 ,-1 , 0
  4112.3     .05       0  4116.9     .12       0  4370.8     .05       0
  4463.4     .12       0  4636.7     .05       0    4902      .1       0
    4965     .07       0  5006.7      .1       0  5528.4     .12       0
  5832.4     .05       0
Bank Sta=4965,5006.7
XS Rating Curve= 0 ,0
Exp/Cntr=0.3,0.1

Type RM Length L Ch R = 1 ,65500   ,500,500,500
BEGIN DESCRIPTION:
STEWARTS CREEK 128.0
END DESCRIPTION:
XS GIS Cut Line= 3
       3833796.9     10128185.21      3832912.89     10127548.91
      3832364.98     10127195.86
#Sta/Elev= 30
  3910.8  237.45  3921.1  237.77  4008.1  236.64  4153.4  232.21  4171.2  231.29
    4416  221.16  4481.2  219.87  4614.7  218.73  4736.1   212.8  4801.2  219.78
  4815.3  218.67  4858.4  212.32  4895.3  215.38  4937.4   211.5  4966.9  215.09
  4987.7   213.3    4995  209.28  5010.2  209.28  5023.8  214.93  5053.6   210.1
  5075.3  209.96  5089.3  210.71  5096.4  215.93  5152.3  217.43  5199.8  218.63
  5301.3  221.97  5386.7  226.02  5545.3  239.08  5631.7  246.82  5651.8  251.57
#Mann= 15 ,-1 , 0
  3910.8     .05       0  3921.1     .12       0  4008.1     .05       0
  4153.4     .12       0  4171.2     .05       0    4416     .12       0
  4481.2     .05       0  4614.7     .12       0  4815.3      .1       0
  4966.9     .07       0  5023.8      .1       0  5152.3     .12       0
  5199.8      .1       0  5301.3     .12       0  5545.3     .05       0
Bank Sta=4966.9,5023.8
XS Rating Curve= 0 ,0
Exp/Cntr=0.3,0.1

Type RM Length L Ch R = 1 ,65000   ,500,500,500
BEGIN DESCRIPTION:
STEWARTS CREEK 127.0
END DESCRIPTION:
XS GIS Cut Line= 3
      3833814.21     10128159.11      3833079.69     10127203.61
      3832577.25     10126930.85
#Sta/Elev= 30
  3794.8  236.91  3819.9  236.43    3844  235.83  4035.3  231.71  4289.9  221.39
  4439.4  222.71  4566.6  217.63  4614.8  216.46  4661.5  214.12  4775.7  214.26
  4846.3  211.92  4860.8  212.25  4875.4  214.26  4881.7  217.01  4910.7  220.21
  4925.2  218.78  4931.5  215.58    4946  212.23  4995.9  212.69  4998.4  210.17
  5004.2  208.56  5019.4  208.56  5024.8  212.07  5033.6  212.64  5039.3  214.82
  5115.4  215.08  5253.1  224.04  5350.1  230.83  5400.3  232.13  5571.7  242.28
#Mann= 9 ,-1 , 0
  3794.8     .05       0  3819.9     .12       0    3844     .05       0
  4035.3     .12       0  4566.6     .05       0  4614.8      .1       0
  4995.9     .07       0  5033.6      .1       0  5253.1     .12       0
Bank Sta=4995.9,5033.6
XS Rating Curve= 0 ,0
Exp/Cntr=0.3,0.1

Type RM Length L Ch R = 1 ,64500   ,500,500,500
BEGIN DESCRIPTION:
STEWARTS CREEK 126.0
END DESCRIPTION:
XS GIS Cut Line= 3
      3834144.09     10127525.46      3833357.43     10126853.02
      3832638.07     10126748.56
#Sta/Elev= 30
  3965.1  236.27  4029.5  236.81  4035.7  236.58  4168.1  229.99  4256.4  225.21
  4355.2  222.31  4433.8  221.82  4490.2  219.38  4574.1  220.12  4686.6  219.07
  4816.2  211.86  4866.7  210.84    4959  213.56  4977.5  212.17  4986.4  210.24
    4990  206.92  5005.3  206.92  5009.7  210.18  5019.8  212.02  5070.3  211.02
  5110.7  212.75  5130.9  219.15    5141  220.63  5161.2  218.58  5171.4  214.33
  5199.1  213.34  5221.5  213.83  5467.7  222.15  5569.8  228.56  5726.9  237.66
#Mann= 11 ,-1 , 0
  3965.1     .05       0  4029.5      .1       0  4035.7     .05       0
  4168.1     .12       0  4574.1     .05       0  4686.6      .1       0
  4977.5     .07       0  5019.8      .1       0  5199.1     .05       0
  5221.5      .1       0  5569.8     .05       0
Bank Sta=4977.5,5019.8
XS Rating Curve= 0 ,0
Exp/Cntr=0.3,0.1

Type RM Length L Ch R = 1 ,64000   ,600,600,600
BEGIN DESCRIPTION:
STEWARTS CREEK 125.0
END DESCRIPTION:
XS GIS Cut Line= 3
      3834387.18     10127121.84      3833518.15     10126458.13
      3832672.82     10126522.86
#Sta/Elev= 30
  3906.5  233.34    3943   233.4    3956  231.27  3970.2  232.29  4184.2  222.17
  4370.9   218.4  4534.8  218.23  4691.2  213.42  4770.2  210.31    4791  208.25
  4805.5  210.97  4834.6  211.73  4849.1  210.66    4976  212.37  4984.2  209.61
  4989.3  205.75  5004.7  205.75  5020.4  211.52  5030.4   212.5  5045.3   212.7
  5140.7  217.65  5180.8  216.48  5230.5  221.85    5251  222.07  5281.1  219.68
  5301.2  221.81  5401.5  223.81  5451.6  227.39  5496.8  228.77  5847.8  236.03
#Mann= 5 ,-1 , 0
  3906.5     .05       0  4370.9      .1       0    4976     .07       0
  5030.4      .1       0  5045.3     .05       0
Bank Sta=4976,5030.4
XS Rating Curve= 0 ,0
Exp/Cntr=0.3,0.1

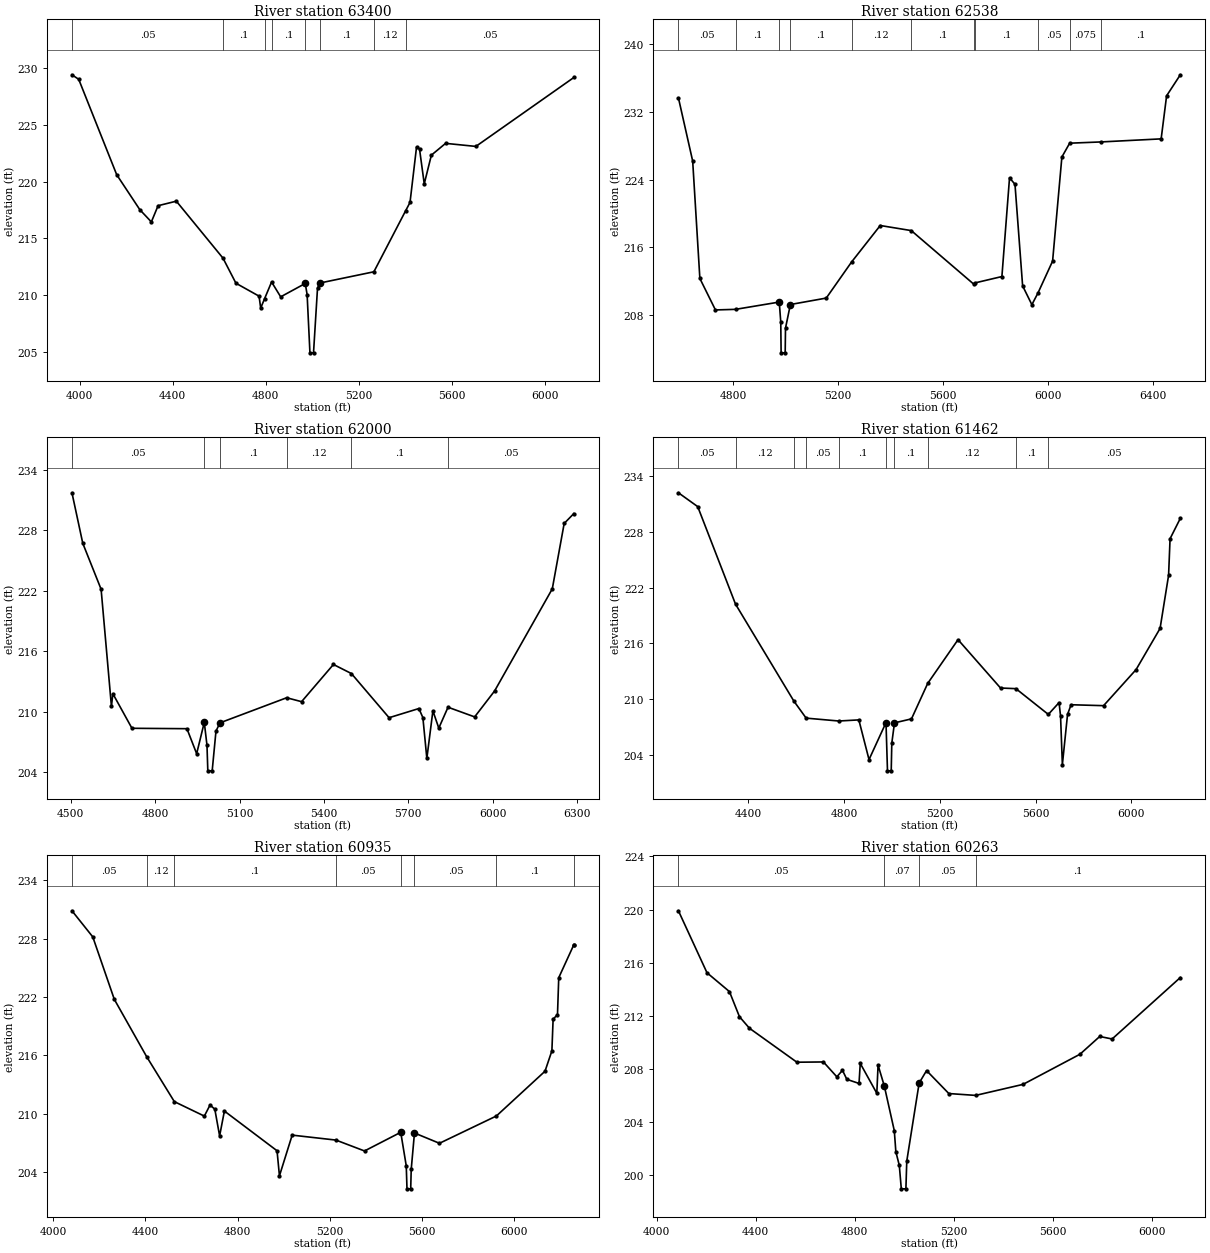
Type RM Length L Ch R = 1 ,63400   ,862,862,862
BEGIN DESCRIPTION:
STEWARTS CREEK 124.0
END DESCRIPTION:
XS GIS Cut Line= 3
      3834422.72     10126866.57      3833780.33     10126057.73
      3832677.12     10126278.07
#Sta/Elev= 30
  3967.1  229.42  3996.2  229.02  4159.6   220.6  4258.9  217.52  4308.5  216.44
  4337.4  217.87  4415.9  218.27  4616.6  213.24  4672.2  211.03  4771.6  209.89
  4778.6  208.84  4795.6  209.68  4825.4  211.14  4864.5  209.83  4970.2  211.01
  4978.2  210.03  4990.3  204.89  5005.7  204.89  5022.9   210.6  5033.1  211.05
  5265.2  212.04  5401.4  217.41  5420.6  218.16  5448.6  223.04  5461.4  222.88
  5481.8   219.8  5512.4  222.33  5573.6  223.37  5703.7   223.1    6125  229.18
#Mann= 8 ,-1 , 0
  3967.1     .05       0  4616.6      .1       0  4795.6     .05       0
  4825.4      .1       0  4970.2     .07       0  5033.1      .1       0
  5265.2     .12       0  5401.4     .05       0
Bank Sta=4970.2,5033.1
XS Rating Curve= 0 ,0
Exp/Cntr=0.3,0.1

Type RM Length L Ch R = 1 ,62538   ,538,538,538
BEGIN DESCRIPTION:
STEWARTS CREEK 123.0
END DESCRIPTION:
XS GIS Cut Line= 3
      3834391.48     10126049.74      3834191.87     10125692.41
      3832993.92      10124782.4
#Sta/Elev= 30
  4590.7  233.65  4645.1  226.19  4672.5  212.34  4731.9  208.63  4808.5   208.7
  4975.2  209.56  4980.9  207.22  4982.3  203.57  4997.8  203.57    4999  206.48
  5017.6  209.27  5154.4  210.03  5250.8  214.28  5360.3  218.59  5478.6  217.99
  5717.2  211.66  5720.3  211.81  5824.1  212.57  5853.2  224.22    5874  223.45
  5903.1  211.47  5938.4  209.25    5962  210.65  6017.4  214.39  6052.8  226.67
  6082.5   228.3  6202.9  228.45  6431.3  228.81  6452.1  233.89  6504.4  236.37
#Mann= 11 ,-1 , 0
  4590.7     .05       0  4808.5      .1       0  4975.2     .07       0
  5017.6      .1       0  5250.8     .12       0  5478.6      .1       0
  5717.2     .12       0  5720.3      .1       0    5962     .05       0
  6082.5    .075       0  6202.9      .1       0
Bank Sta=4975.2,5017.6
XS Rating Curve= 0 ,0
Exp/Cntr=0.3,0.1

Type RM Length L Ch R = 1 ,62000   ,538,538,538
BEGIN DESCRIPTION:
STEWARTS CREEK 122.0
END DESCRIPTION:
XS GIS Cut Line= 3
      3834408.85     10126038.51       3834525.5     10125556.52
      3833582.66     10124677.55
#Sta/Elev= 30
  4504.1   231.7  4542.6  226.69  4607.8  222.13  4644.5  210.52  4649.6  211.77
  4717.5  208.34    4913   208.3  4947.6  205.82  4974.7  208.93  4984.3  206.66
  4987.3  204.12  5002.8  204.12  5016.3  208.06  5030.5  208.88  5267.7  211.37
  5320.7  210.98    5434  214.67  5497.9  213.77  5631.9  209.39  5737.9   210.3
  5752.1   209.4  5766.2  205.35  5787.7  210.07  5808.7  208.36  5841.5  210.43
  5936.2  209.47  6007.1  212.04  6212.3  222.17  6254.6  228.66    6289  229.64
#Mann= 6 ,-1 , 0
  4504.1     .05       0  4974.7     .07       0  5030.5      .1       0
  5267.7     .12       0  5497.9      .1       0  5841.5     .05       0
Bank Sta=4974.7,5030.5
XS Rating Curve= 0 ,0
Exp/Cntr=0.3,0.1

Type RM Length L Ch R = 1 ,61462   ,527,527,527
BEGIN DESCRIPTION:
STEWARTS CREEK 121.0
END DESCRIPTION:
XS GIS Cut Line= 3
      3835334.19     10126048.89      3834730.81     10125393.56
      3833761.67      10124678.3
#Sta/Elev= 30
  4109.2   232.2  4189.8  230.71  4347.6  220.22    4591   209.8  4642.4  207.96
  4778.7  207.65  4862.4  207.77  4904.9   203.5  4975.8  207.48    4982  202.29
  4997.6  202.29    5000  205.27  5011.2  207.45  5082.2  207.88    5150   211.7
  5276.5   216.4  5453.9   211.2  5518.1  211.13  5653.4  208.36  5698.3  209.63
  5704.5  208.19  5712.1  202.96  5733.7  208.36  5748.4   209.4  5884.1   209.3
  6019.8  213.18    6120  217.61  6155.5  223.32  6161.7  227.26  6204.5  229.45
#Mann= 10 ,-1 , 0
  4109.2     .05       0  4347.6     .12       0    4591      .1       0
  4642.4     .05       0  4778.7      .1       0  4975.8     .07       0
  5011.2      .1       0    5150     .12       0  5518.1      .1       0
  5653.4     .05       0
Bank Sta=4975.8,5011.2
XS Rating Curve= 0 ,0
Exp/Cntr=0.3,0.1

Type RM Length L Ch R = 1 ,60935   ,672,672,672
BEGIN DESCRIPTION:
STEWARTS CREEK 120.0
END DESCRIPTION:
XS GIS Cut Line= 3
      3835365.47     10126028.12      3835121.89     10125143.13
       3833952.1       10124682.
#Sta/Elev= 30
  4082.1  230.88  4172.4  228.19  4265.7  221.76  4405.8  215.86  4525.8  211.23
  4655.9  209.74  4680.6  210.88  4701.3  210.45  4722.1   207.7  4742.8  210.26
    4971  206.17  4981.4  203.59  5036.6  207.78  5226.3  207.27  5350.1  206.15
  5507.1  208.07    5531  204.62  5534.2  202.25  5550.3  202.25  5552.5  204.25
  5566.6     208  5674.9  206.94  5921.6  209.75  6132.4  214.36  6162.2  216.46
  6167.5  219.71  6186.5   220.2  6191.9  223.99  6256.7  227.35  6257.4  227.37
#Mann= 8 ,-1 , 0
  4082.1     .05       0  4405.8     .12       0  4525.8      .1       0
  5226.3     .05       0  5507.1     .07       0  5566.6     .05       0
  5921.6      .1       0  6256.7     .05       0
Bank Sta=5507.1,5566.6
XS Rating Curve= 0 ,0
Exp/Cntr=0.3,0.1

Type RM Length L Ch R = 1 ,60263   ,95,95,95
BEGIN DESCRIPTION:
STEWARTS CREEK 118.0
END DESCRIPTION:
XS GIS Cut Line= 3
      3836152.25     10124846.32      3835248.31     10124721.65
      3834132.11     10124717.86
#Sta/Elev= 30
  4087.5  219.91    4203  215.24  4293.8  213.82  4334.2  211.93  4374.6  211.06
  4566.4   208.5  4673.6  208.52  4727.9   207.4  4750.6  207.89  4768.3  207.21
  4817.5   206.9  4822.5  208.41  4889.4  206.16  4894.5  208.28  4919.7  206.71
  4960.1  203.34  4966.4  201.75  4980.3  200.73  4988.4  198.96    5007  198.96
  5010.5  201.05  5060.5  206.93  5090.5  207.87  5180.5  206.14  5288.8     206
  5480.5  206.83  5710.5   209.1  5790.5  210.44  5840.5  210.25  6116.2  214.88
#Mann= 4 ,-1 , 0
  4087.5     .05       0  4919.7     .07       0  5060.5     .05       0
  5288.8      .1       0
Bank Sta=4919.7,5060.5
XS Rating Curve= 0 ,0
Exp/Cntr=0.3,0.1

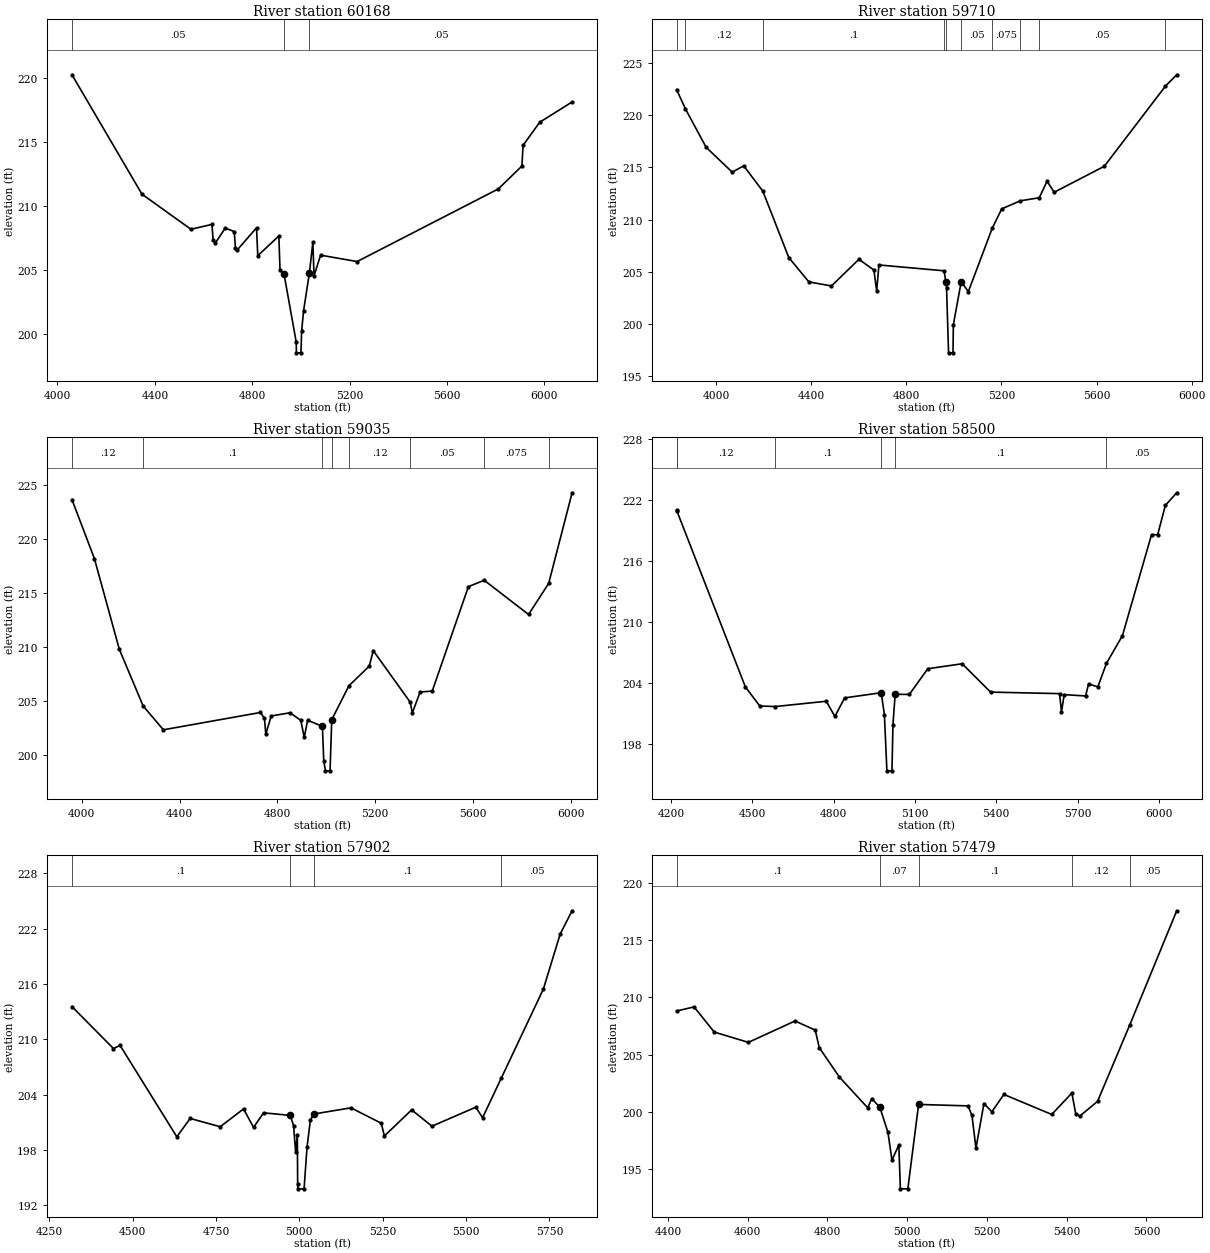
Type RM Length L Ch R = 1 ,60168   ,458,458,458
BEGIN DESCRIPTION:
STEWARTS CREEK 117.0
END DESCRIPTION:
XS GIS Cut Line= 3
      3836183.53     10124728.27      3835248.53     10124626.68
      3834134.91     10124613.69
#Sta/Elev= 30
  4059.5  220.27  4346.9  210.92    4548  208.17  4634.4  208.55  4639.4   207.3
  4648.6   207.1  4688.9  208.26    4726  207.99    4731  206.67  4739.2  206.57
  4817.5  208.28  4822.6   206.1  4909.1  207.64  4914.1  204.94  4930.3  204.68
  4980.6  199.33  4981.3  198.49  4999.9  198.49  5002.8  200.19  5010.7  201.78
 5034.88 204.768  5048.8  207.15  5053.8  204.53  5080.7  206.14  5230.7  205.64
  5810.7  211.33  5907.5  213.12  5912.5  214.75  5980.7  216.55  6113.7  218.14
#Mann= 3 , 0 , 0
  4059.5     .05       0  4930.3     .07       0 5034.88     .05       0
Bank Sta=4930.3,5034.88
XS Rating Curve= 0 ,0
Exp/Cntr=0.3,0.1

Type RM Length L Ch R = 1 ,59710   ,675,675,675
BEGIN DESCRIPTION:
Mapping XS 3ce9fcac
END DESCRIPTION:
XS GIS Cut Line= 3
       3836405.8     10124589.39      3835298.39     10124222.52
      3834364.12     10124148.41
#Sta/Elev= 30
  3833.4  222.45    3870  220.63  3957.6  216.93  4067.4  214.55  4115.7  215.16
  4196.2  212.73  4305.3  206.38  4389.7  204.05  4484.8  203.66  4600.3  206.21
  4663.5  205.18    4675  203.18  4684.5  205.67  4958.7  205.11    4966 204.029
    4969  203.46  4977.4  197.26  4996.1  197.26  4997.6  199.95  5030.6  204.06
  5060.7  203.12  5161.4   209.2  5201.2  211.04  5279.4  211.81  5358.8   212.1
  5391.8  213.68  5421.9  212.63  5632.5  215.11    5890  222.79  5937.2  223.87
#Mann= 10 ,-1 , 0
  3833.4     .05       0    3870     .12       0  4196.2      .1       0
  4958.7     .05       0    4966     .07       0  5030.6     .05       0
  5161.4    .075       0  5279.4      .1       0  5358.8     .05       0
    5890      .1       0
Bank Sta=4966,5030.6
XS Rating Curve= 0 ,0
Exp/Cntr=0.3,0.1

Type RM Length L Ch R = 1 ,59035   ,535,535,535
BEGIN DESCRIPTION:
STEWARTS CREEK 116.0
END DESCRIPTION:
XS GIS Cut Line= 3
      3836579.36     10124322.01      3835658.17      10123839.1
      3834771.58     10123364.35
#Sta/Elev= 30
  3959.9  223.61  4051.9  218.14  4153.6  209.78    4251  204.55  4333.7  202.35
  4730.8  203.95  4747.2  203.41  4752.8  201.94  4774.9  203.63  4851.8  203.92
    4896  203.22    4910  201.64  4923.7  203.23  4984.2  202.67  4989.8  199.48
  4996.9  198.56  5015.6  198.56  5022.5  203.28  5092.8  206.42    5176  208.23
  5192.3  209.66  5343.8  204.89    5352   203.9    5384  205.84  5433.6  205.93
  5581.5  215.57  5646.1  216.16  5827.7     213  5909.9  215.87  6005.7  224.24
#Mann= 8 ,-1 , 0
  3959.9     .12       0    4251      .1       0  4984.2     .07       0
  5022.5      .1       0  5092.8     .12       0  5343.8     .05       0
  5646.1    .075       0  5909.9     .05       0
Bank Sta=4984.2,5022.5
XS Rating Curve= 0 ,0
Exp/Cntr=0.3,0.1

Type RM Length L Ch R = 1 ,58500   ,598,598,598
BEGIN DESCRIPTION:
STEWARTS CREEK 115.0
END DESCRIPTION:
XS GIS Cut Line= 3
      3836825.73     10123949.98        3836095.     10123680.31
      3835134.97     10123217.87
#Sta/Elev= 30
  4221.1  221.05  4222.2  220.96  4474.7  203.64    4528  201.76  4585.6  201.71
  4773.1  202.23  4804.9  200.73  4840.7  202.56  4975.6  203.07  4987.5  200.91
  4996.7  195.38  5015.4  195.38    5019   199.9 5027.15 202.916  5079.5   202.9
  5147.4  205.43  5274.3  205.92  5379.1  203.13  5633.5  202.98  5640.6  201.18
  5650.6  202.88  5729.5  202.75  5740.5  203.93  5774.8  203.65  5806.6  205.97
  5865.3  208.68  5972.8  218.63  5995.4  218.62  6023.6  221.51  6065.6  222.75
#Mann= 6 ,-1 , 0
  4221.1     .05       0  4222.2     .12       0  4585.6      .1       0
  4975.6     .07       0 5027.15      .1       0  5806.6     .05       0
Bank Sta=4975.6,5027.15
XS Rating Curve= 0 ,0
Exp/Cntr=0.3,0.1

Type RM Length L Ch R = 1 ,57902   ,423,423,423
BEGIN DESCRIPTION:
STEWARTS CREEK 114.0
END DESCRIPTION:
XS GIS Cut Line= 3
      3836652.08     10123286.78      3835970.66     10123306.35
      3835162.71     10123179.17
#Sta/Elev= 30
  4318.3  213.55  4442.6  209.01  4462.6  209.34  4632.7  199.44  4672.7  201.43
  4762.7  200.53  4832.7  202.46  4862.8  200.46  4892.8  202.04  4972.8  201.76
  4982.8  200.64    4989  197.74    4994  199.68    4995   194.3  4995.5   193.8
  5014.2   193.8  5023.1  198.32  5033.2  201.26  5043.3  201.91  5154.7  202.58
  5245.8  200.91    5255  199.53  5336.9  202.36  5397.6  200.59  5529.2  202.65
  5549.5  201.51  5605.2  205.77  5731.7  215.45  5782.3  221.43  5817.9  223.94
#Mann= 4 ,-1 , 0
  4318.3      .1       0  4972.8     .07       0  5043.3      .1       0
  5605.2     .05       0
Bank Sta=4972.8,5043.3
XS Rating Curve= 0 ,0
Exp/Cntr=0.3,0.1

Type RM Length L Ch R = 1 ,57479   ,479,479,479
BEGIN DESCRIPTION:
STEWARTS CREEK 113.0
END DESCRIPTION:
XS GIS Cut Line= 3
      3836461.11     10122977.75      3835890.37     10123069.05
      3835214.62     10123050.67
#Sta/Elev= 30
    4422  208.81  4465.8  209.17  4516.4  206.97  4601.9  206.07    4719  207.94
  4769.6  207.14  4779.7  205.61  4830.4  203.03  4901.3  200.35  4911.4  201.16
  4931.7  200.39  4951.9  198.21    4962  195.78  4979.2   197.1  4983.1  193.27
  5001.8  193.27  5028.8 200.646  5152.6  200.52  5162.6  199.69  5172.6  196.82
  5192.6  200.72  5212.6  200.01  5242.6  201.52  5362.6  199.77  5413.1  201.64
  5422.7  199.84  5432.7  199.62  5477.4  200.91    5558  207.57    5676  217.57
#Mann= 5 ,-1 , 0
    4422      .1       0  4931.7     .07       0  5028.8      .1       0
  5413.1     .12       0    5558     .05       0
Bank Sta=4931.7,5028.8
XS Rating Curve= 0 ,0
Exp/Cntr=0.3,0.1

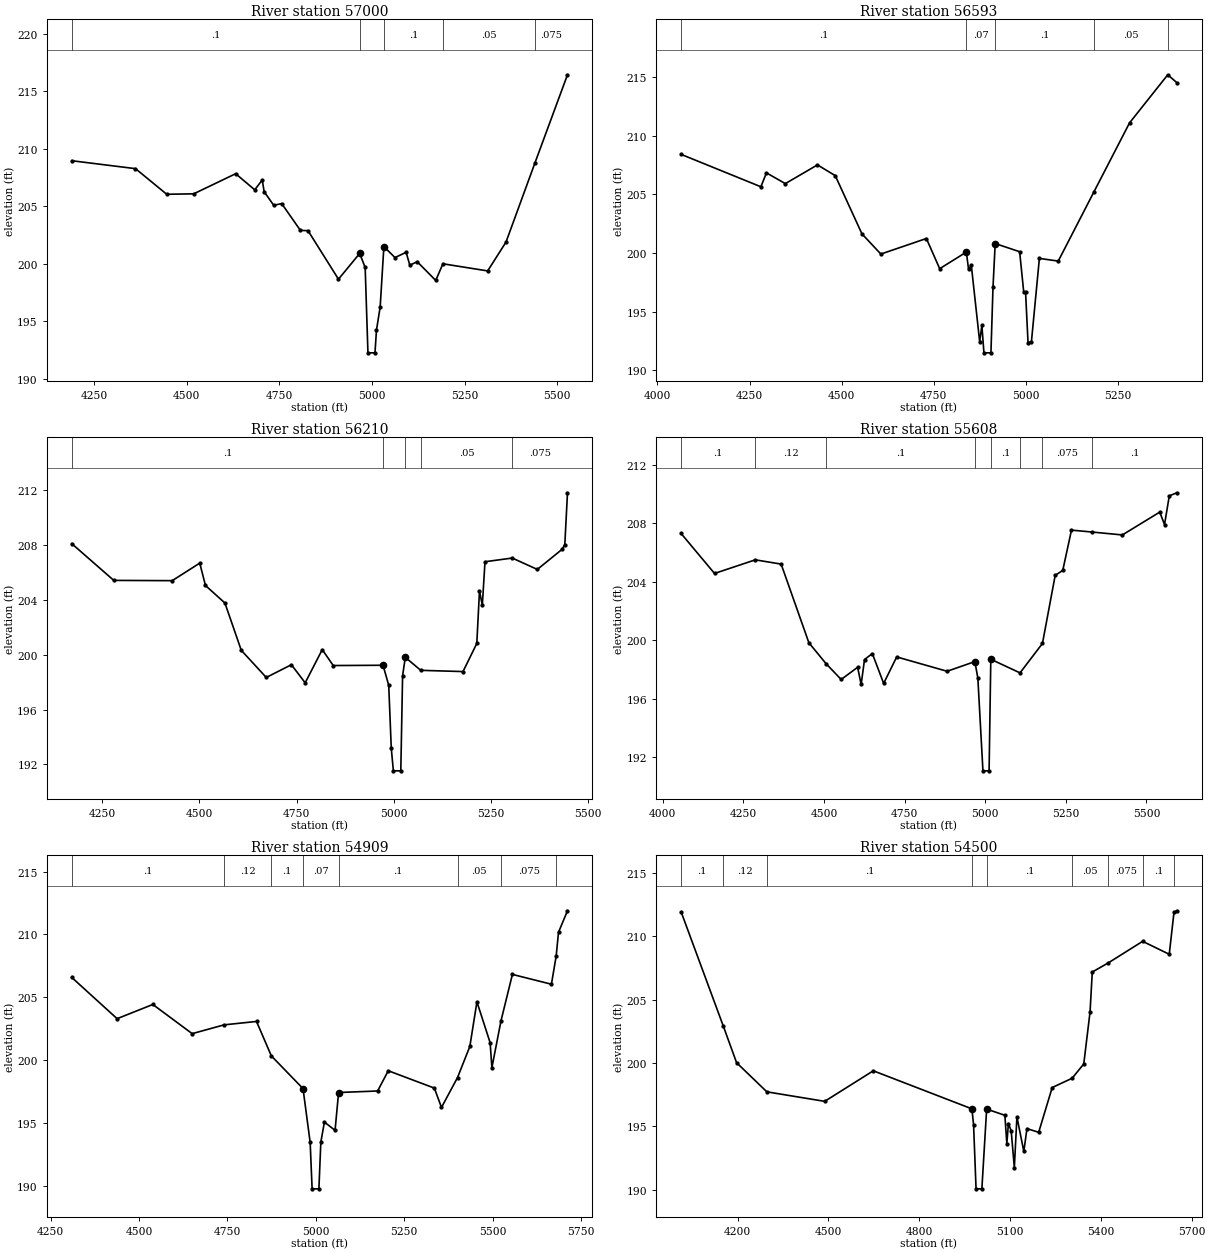
Type RM Length L Ch R = 1 ,57000   ,407,407,407
BEGIN DESCRIPTION:
STEWARTS CREEK 112.0
END DESCRIPTION:
XS GIS Cut Line= 3
      3836468.04     10122946.49      3835679.85      10122758.5
      3835152.46     10122769.41
#Sta/Elev= 30
  4189.7  208.96  4361.7  208.27    4446  206.04  4518.9  206.08    4632  207.83
  4683.4  206.43  4703.8  207.28  4708.9  206.26  4734.8  205.08  4756.2  205.23
  4806.7   202.9  4827.3  202.87  4909.5  198.65  4966.7  200.89  4981.5  199.67
    4989  192.24    5008  192.24    5012  194.21    5022  196.24    5032  201.49
    5062  200.53    5092  200.99    5102  199.87    5122  200.17    5172  198.54
  5191.3  199.99  5312.1  199.37  5361.6  201.88  5439.7  208.77  5527.5  216.44
#Mann= 5 ,-1 , 0
  4189.7      .1       0  4966.7     .07       0    5032      .1       0
  5191.3     .05       0  5439.7    .075       0
Bank Sta=4966.7,5032
XS Rating Curve= 0 ,0
Exp/Cntr=0.3,0.1

Type RM Length L Ch R = 1 ,56593   ,383,383,383
BEGIN DESCRIPTION:
STEWARTS CREEK 111.0
END DESCRIPTION:
XS GIS Cut Line= 3
      3836468.06     10122922.19      3835684.38     10122410.57
      3835284.04     10122318.03
#Sta/Elev= 30
  4064.1  208.43  4280.9  205.66    4296  206.85  4347.3  205.93  4434.6  207.53
    4483  206.61  4555.4  201.64  4606.8  199.91  4730.5  201.24  4766.7  198.66
  4839.1  200.08  4845.1  198.61  4852.5  198.98  4875.3  192.42  4881.3  193.81
  4886.9  191.47  4905.9  191.47  4911.5  197.06  4917.5  200.81  4983.9  200.11
    4995  196.66    5000  196.66  5006.7  192.33  5015.9  192.41  5037.5  199.54
  5088.8  199.31  5185.5  205.21  5282.5  211.12  5386.3  215.23  5410.9  214.56
#Mann= 5 ,-1 , 0
  4064.1      .1       0  4839.1     .07       0  4917.5      .1       0
  5185.5     .05       0  5386.3      .1       0
Bank Sta=4839.1,4917.5
XS Rating Curve= 0 ,0
Exp/Cntr=0.3,0.1

Type RM Length L Ch R = 1 ,56210   ,602,602,602
BEGIN DESCRIPTION:
STEWARTS CREEK 110.0
END DESCRIPTION:
XS GIS Cut Line= 3
      3836478.45     10122901.32      3835984.97     10122236.19
      3835662.92     10121926.06
#Sta/Elev= 30
  4171.8   208.1  4279.9  205.42  4430.2   205.4  4501.1  206.68  4515.7  205.05
  4565.8  203.77  4607.9  200.32  4672.2  198.34  4736.8  199.27  4772.3  197.95
  4816.2  200.37  4844.5  199.21  4972.6  199.23  4987.2  197.77  4993.8  193.16
  4999.2  191.53  5018.3  191.53  5022.9  198.47  5029.9  199.81  5069.6  198.86
  5178.3  198.77  5213.8  200.82  5220.7  204.65    5228  203.61  5234.9  206.78
    5305  207.05  5369.5  206.22    5433  207.68  5440.2  208.02  5447.1  211.81
#Mann= 5 ,-1 , 0
  4171.8      .1       0  4972.6     .07       0  5029.9      .1       0
  5069.6     .05       0    5305    .075       0
Bank Sta=4972.6,5029.9
XS Rating Curve= 0 ,0
Exp/Cntr=0.3,0.1

Type RM Length L Ch R = 1 ,55608   ,699,699,699
BEGIN DESCRIPTION:
STEWARTS CREEK 109.0
END DESCRIPTION:
XS GIS Cut Line= 3
      3836502.78     10122901.37      3836263.62     10121988.79
      3835922.94     10121502.08
#Sta/Elev= 30
  4056.6  207.29  4160.3  204.56  4286.7  205.49  4366.9   205.2  4452.9  199.83
  4505.8  198.41  4553.1  197.32  4604.1  198.15  4615.1  196.98  4625.5  198.68
  4649.7  199.09  4684.9  197.05  4725.3  198.86  4881.7  197.88  4967.7  198.54
    4977  197.42  4992.8  191.08  5011.9  191.08  5017.2   198.7  5107.8  197.77
  5177.4  199.78  5216.9  204.43  5240.4  204.77  5267.4  207.52  5330.7  207.39
  5425.2  207.19  5541.2  208.75    5556   207.9  5570.8  209.86  5594.1  210.07
#Mann= 8 ,-1 , 0
  4056.6      .1       0  4286.7     .12       0  4505.8      .1       0
  4967.7     .07       0  5017.2      .1       0  5107.8     .05       0
  5177.4    .075       0  5330.7      .1       0
Bank Sta=4967.7,5017.2
XS Rating Curve= 0 ,0
Exp/Cntr=0.3,0.1

Type RM Length L Ch R = 1 ,54909   ,409,409,409
BEGIN DESCRIPTION:
STEWARTS CREEK 108.0
END DESCRIPTION:
XS GIS Cut Line= 3
      3836520.15     10122897.85        3836623.     10122215.36
       3836565.3      10121505.8
#Sta/Elev= 30
  4309.8  206.58    4438   203.3  4539.1  204.43  4650.4  202.11  4740.8  202.81
  4832.4  203.08  4874.3  200.34  4963.9  197.74  4984.1  193.46  4989.6  189.77
  5008.8  189.77  5014.3  193.49  5024.4  195.08  5054.5  194.42  5064.5  197.43
  5174.9  197.55    5205  199.16  5335.4  197.78  5355.5  196.24  5400.9  198.62
  5435.7  201.09  5455.8  204.64  5493.1  201.39  5498.1  199.41    5524  203.15
  5556.1  206.82  5666.5  206.04    5680   208.3  5686.5  210.17  5711.9  211.88
#Mann= 8 ,-1 , 0
  4309.8      .1       0  4740.8     .12       0  4874.3      .1       0
  4963.9     .07       0  5064.5      .1       0  5400.9     .05       0
    5524    .075       0    5680      .1       0
Bank Sta=4963.9,5064.5
XS Rating Curve= 0 ,0
Exp/Cntr=0.3,0.1

Type RM Length L Ch R = 1 ,54500   ,574,574,574
BEGIN DESCRIPTION:
STEWARTS CREEK 107.0
END DESCRIPTION:
XS GIS Cut Line= 3
      3836811.81     10123043.71      3836898.44     10122060.62
       3836714.6     10121436.12
#Sta/Elev= 30
  4013.1  211.93  4152.5  202.92  4196.4  200.03  4296.5  197.73  4487.6  196.98
  4648.2  199.39    4974 196.388  4979.5  195.13  4987.7  190.08  5006.9  190.08
  5022.7  196.37  5082.9  195.88  5089.4  193.65  5094.6  195.23  5103.8  194.65
  5114.2  191.75  5122.7  195.76  5145.5  193.03  5155.9  194.83  5194.6  194.54
  5239.3  198.07    5305   198.8  5343.6  199.93  5364.4  204.05  5371.7  207.18
  5425.3  207.91  5538.1   209.6    5626  208.58  5641.8  211.91    5651  212.01
#Mann= 9 ,-1 , 0
  4013.1      .1       0  4152.5     .12       0  4296.5      .1       0
    4974     .07       0  5022.7      .1       0    5305     .05       0
  5425.3    .075       0  5538.1      .1       0  5641.8    .075       0
Bank Sta=4974,5022.7
XS Rating Curve= 0 ,0
Exp/Cntr=0.3,0.1