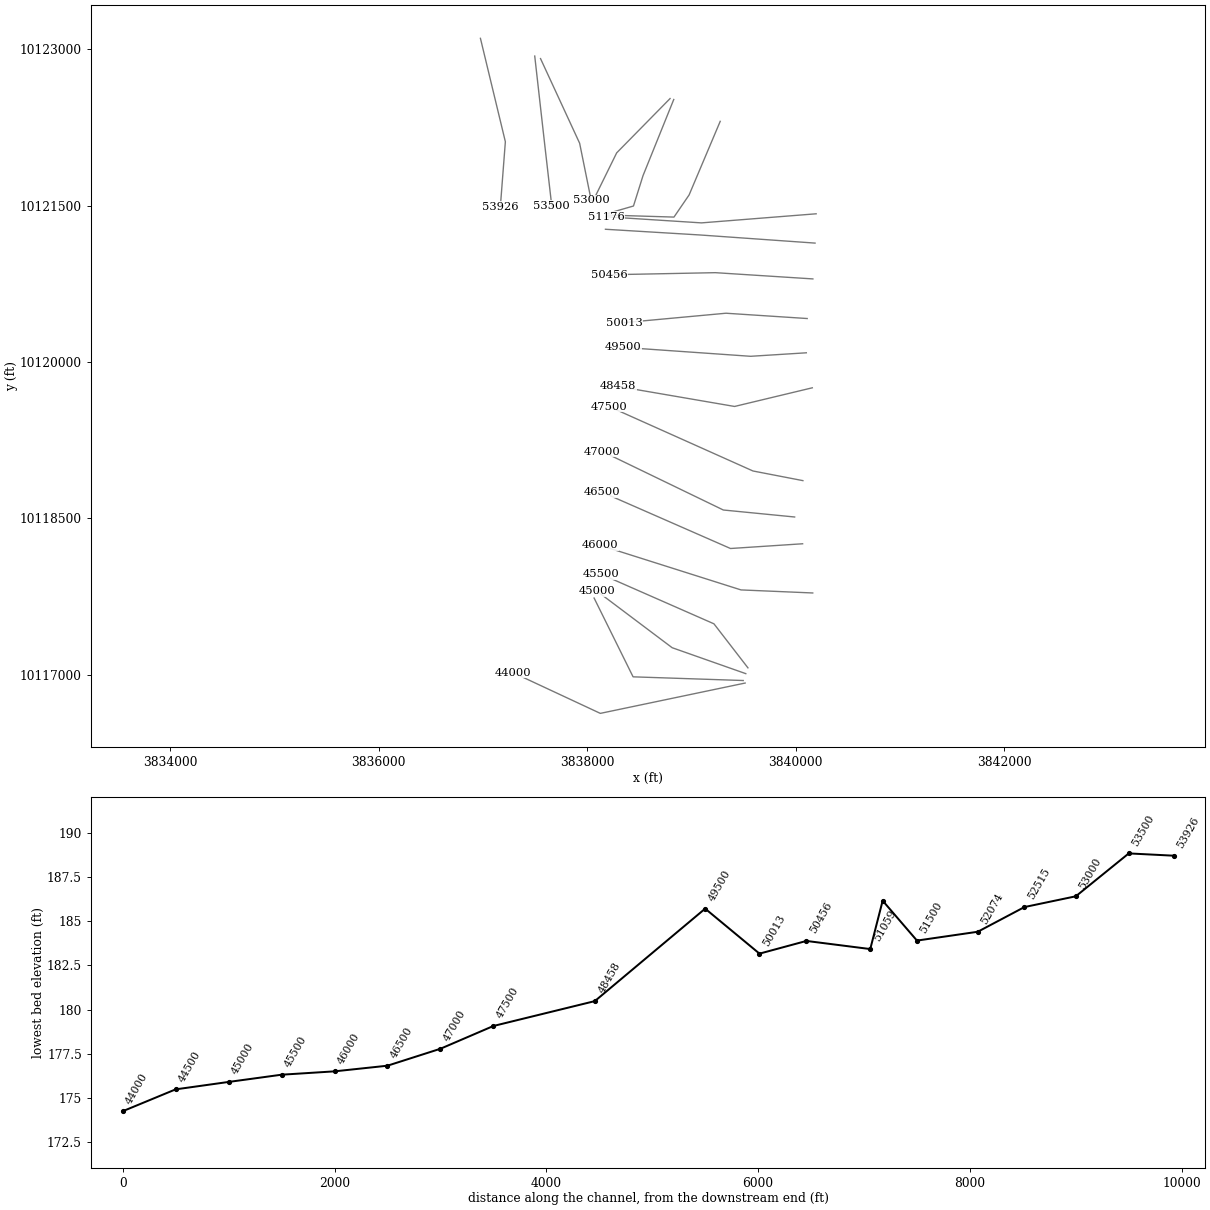
HEC-RAS study STEWARTS CREEK.prj: STEWARTS CREEK Base Level Engineering

--- STEWARTS CREEK.g10 (geometry) --- (continued)

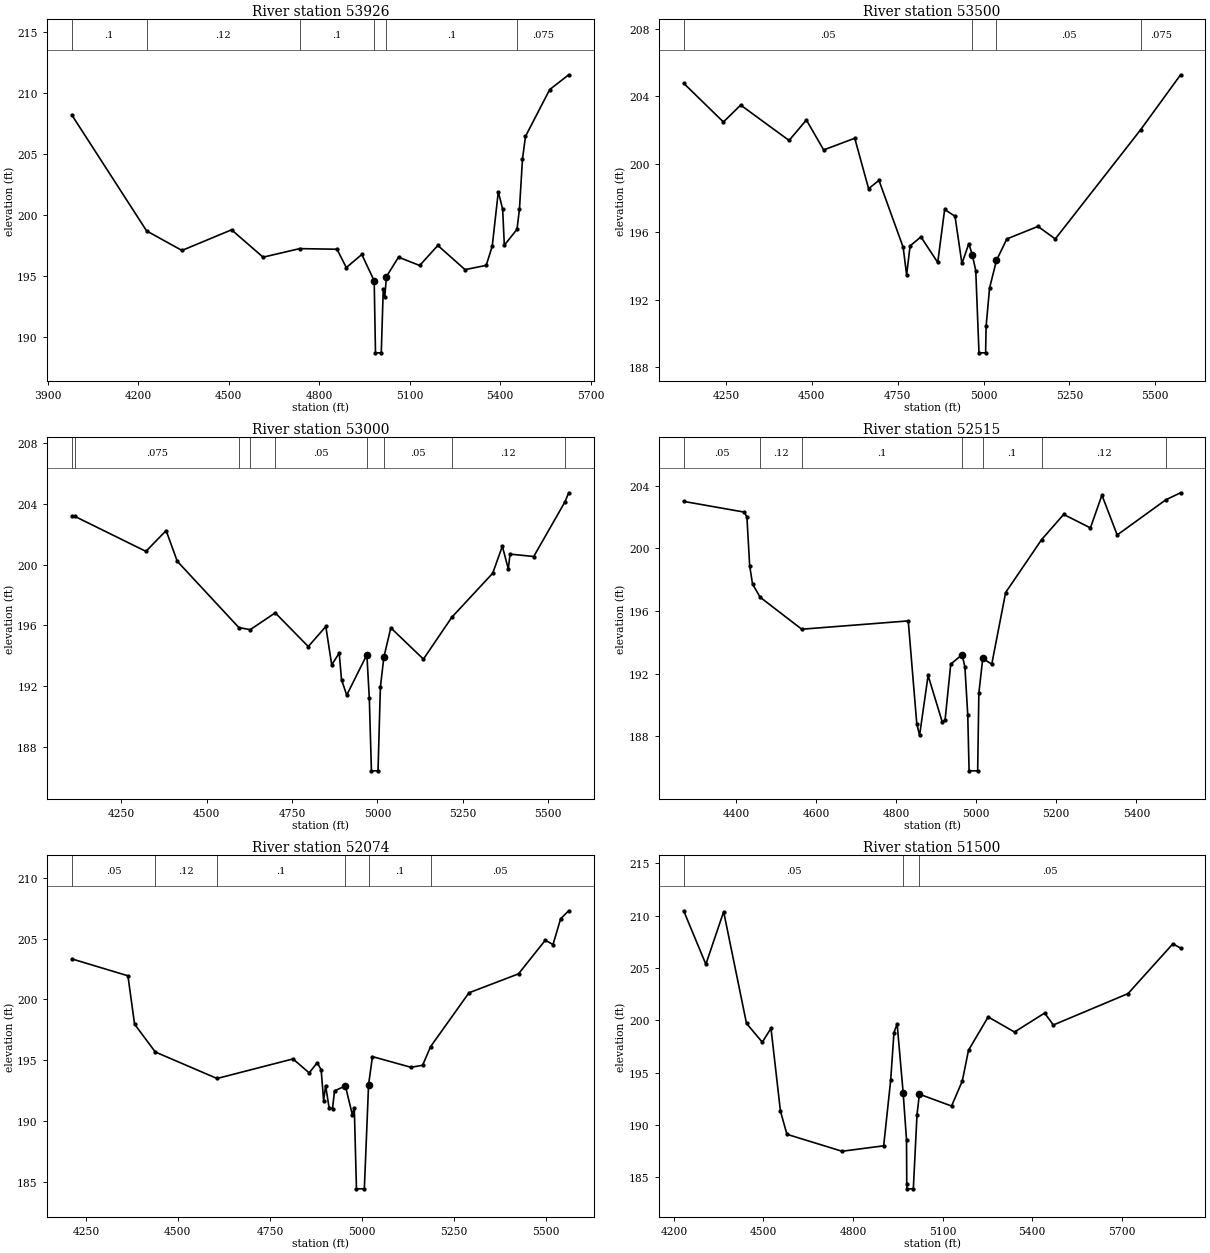
Type RM Length L Ch R = 1 ,53926   ,426,426,426
BEGIN DESCRIPTION:
STEWARTS CREEK 106.0
END DESCRIPTION:
XS GIS Cut Line= 3
      3836975.01     10123106.19      3837214.14     10122113.79
      3837165.97     10121488.14
#Sta/Elev= 30
  3979.2  208.19  4227.3   198.7  4344.5   197.1  4509.1  198.79  4613.7  196.55
  4735.1  197.25  4858.8   197.2  4889.7   195.7  4941.1  196.77  4982.2  194.62
  4986.5  188.72  5005.7  188.72  5012.3  193.97  5017.3  193.28  5022.8  194.96
  5062.9  196.55  5133.1  195.87  5193.3  197.51  5283.6  195.53  5353.8  195.88
  5373.8  197.45  5393.9  201.91  5408.3  200.48  5413.9  197.53  5455.9  198.83
  5464.1  200.49  5474.1  204.59  5484.1  206.44  5564.4  210.27  5627.5  211.48
#Mann= 6 ,-1 , 0
  3979.2      .1       0  4227.3     .12       0  4735.1      .1       0
  4982.2     .07       0  5022.8      .1       0  5455.9    .075       0
Bank Sta=4982.2,5022.8
XS Rating Curve= 0 ,0
Exp/Cntr=0.3,0.1

Type RM Length L Ch R = 1 ,53500   ,500,500,500
BEGIN DESCRIPTION:
STEWARTS CREEK 105.0
END DESCRIPTION:
XS GIS Cut Line= 3
      3837495.84     10122936.07      3837593.67     10122068.47
      3837659.03     10121498.61
#Sta/Elev= 30
  4126.9  204.78  4242.6  202.49  4292.9  203.49  4433.8   201.4  4484.2  202.61
  4534.5  200.84    4625  201.53  4665.3  198.55  4695.5  199.04  4765.9  195.09
    4776  193.45  4786.1  195.17  4817.7   195.7  4866.6  194.19  4886.7  197.32
  4916.9  196.92    4937  194.13  4957.1   195.3  4967.2  194.64  4977.3  193.71
  4986.7  188.85    5006  188.85  5007.4  190.41  5017.5  192.68  5037.6  194.31
  5067.8  195.58  5158.4  196.32  5208.8  195.58  5457.2  202.03  5573.6  205.28
#Mann= 4 ,-1 , 0
  4126.9     .05       0  4967.2     .07       0  5037.6     .05       0
  5457.2    .075       0
Bank Sta=4967.2,5037.6
XS Rating Curve= 0 ,0
Exp/Cntr=0.3,0.1

Type RM Length L Ch R = 1 ,53000   ,485,485,485
BEGIN DESCRIPTION:
STEWARTS CREEK 104.0
END DESCRIPTION:
XS GIS Cut Line= 3
      3837551.39     10122911.78      3837926.51      10122099.4
      3838037.51     10121550.62
#Sta/Elev= 30
  4105.2  203.18  4114.5  203.18  4322.1  200.88  4381.3  202.25  4413.8  200.23
  4594.2  195.86  4627.5  195.72  4700.7  196.83  4797.4  194.61  4848.8  195.93
    4866   193.4    4888  194.18  4894.7  192.43    4910  191.41    4969  194.07
  4976.1  191.21  4982.3  186.42  5001.6  186.42  5008.5  191.92  5018.7  193.91
  5039.1  195.84  5134.5  193.78  5217.7  196.54  5337.4  199.44  5365.6  201.22
    5383  199.72  5388.1   200.7  5457.4  200.54  5548.6  204.13  5559.9  204.74
#Mann= 9 ,-1 , 0
  4105.2     .05       0  4114.5    .075       0  4594.2     .05       0
  4627.5    .075       0  4700.7     .05       0    4969     .07       0
  5018.7     .05       0  5217.7     .12       0  5548.6     .05       0
Bank Sta=4969,5018.7
XS Rating Curve= 0 ,0
Exp/Cntr=0.3,0.1

Type RM Length L Ch R = 1 ,52515   ,441,441,441
BEGIN DESCRIPTION:
STEWARTS CREEK 103.0
END DESCRIPTION:
XS GIS Cut Line= 3
      3838793.92     10122528.28      3838281.85     10122007.02
      3838056.61     10121549.01
#Sta/Elev= 30
  4269.3  202.99  4420.1  202.31  4427.2  202.01  4434.2  198.88  4441.3  197.72
  4460.3  196.88  4564.2  194.84  4830.2  195.37  4851.5  188.82  4858.5  188.07
  4879.8  191.89  4915.1  188.93  4922.2  189.05  4936.4  192.62  4964.7  193.21
  4971.7  192.44  4978.8   189.4  4982.2  185.81  5003.6  185.81  5006.6  190.76
  5016.3  192.98  5038.8  192.61  5073.5  197.18  5163.2  200.55  5218.4  202.16
  5285.2   201.3    5314  203.39  5352.1  200.85  5473.5  203.09  5510.4  203.54
#Mann= 7 ,-1 , 0
  4269.3     .05       0  4460.3     .12       0  4564.2      .1       0
  4964.7     .07       0  5016.3      .1       0  5163.2     .12       0
  5473.5     .05       0
Bank Sta=4964.7,5016.3
XS Rating Curve= 0 ,0
Exp/Cntr=0.3,0.1

Type RM Length L Ch R = 1 ,52074   ,574,574,574
BEGIN DESCRIPTION:
STEWARTS CREEK 102.0
END DESCRIPTION:
XS GIS Cut Line= 4
      3838829.18     10122519.08      3838534.45     10121788.27
      3838442.88      10121496.9      3838196.81     10121425.67
#Sta/Elev= 30
    4212  203.33  4364.4  201.94  4382.4  197.96  4438.7  195.67  4606.4  193.49
  4812.7   195.1  4856.8  193.95  4878.4  194.79  4889.2  194.21  4895.9  191.66
  4901.3   192.9  4910.7  191.09  4920.1  191.02  4925.5  192.47    4955  192.88
  4973.8  190.52  4979.2  191.08  4985.1  184.41  5006.5  184.41    5018  192.98
  5028.5  195.29  5133.3  194.41  5164.8  194.58  5186.4  196.11  5290.6  200.54
  5425.2   202.1    5498  204.87  5518.9  204.51  5539.7  206.64  5561.6  207.29
#Mann= 6 ,-1 , 0
    4212     .05       0  4438.7     .12       0  4606.4      .1       0
    4955     .07       0    5018      .1       0  5186.4     .05       0
Bank Sta=4955,5018
XS Rating Curve= 0 ,0
Exp/Cntr=0.3,0.1

Type RM Length L Ch R = 1 ,51500   ,324,324,324
BEGIN DESCRIPTION:
STEWARTS CREEK 101.0
END DESCRIPTION:
XS GIS Cut Line= 4
      3839274.86     10122309.56      3838976.44     10121602.99
      3838831.34     10121390.56      3838191.99     10121410.07
#Sta/Elev= 30
    4233  210.47  4307.3  205.36  4366.9  210.38  4443.4  199.71  4496.2  197.92
  4525.4  199.24    4557  191.34  4578.7  189.12  4763.3   187.5  4902.7  188.02
  4926.1  194.26  4937.2  198.84  4947.8  199.67 4967.88 193.102  4979.2   188.6
    4980  184.41  4980.5  183.91    5002  183.91  5014.4  191.01  5022.3  192.95
    5130  191.82  5165.9   194.2  5186.8  197.15  5252.6  200.33  5340.8  198.89
  5441.8   200.7  5470.8  199.56    5721  202.56    5871  207.31  5896.9  206.91
#Mann= 3 , 0 , 0
    4233     .05       0 4967.88     .07       0  5022.3     .05       0
Bank Sta=4967.88,5022.3
XS Rating Curve= 0 ,0
Exp/Cntr=0.3,0.1

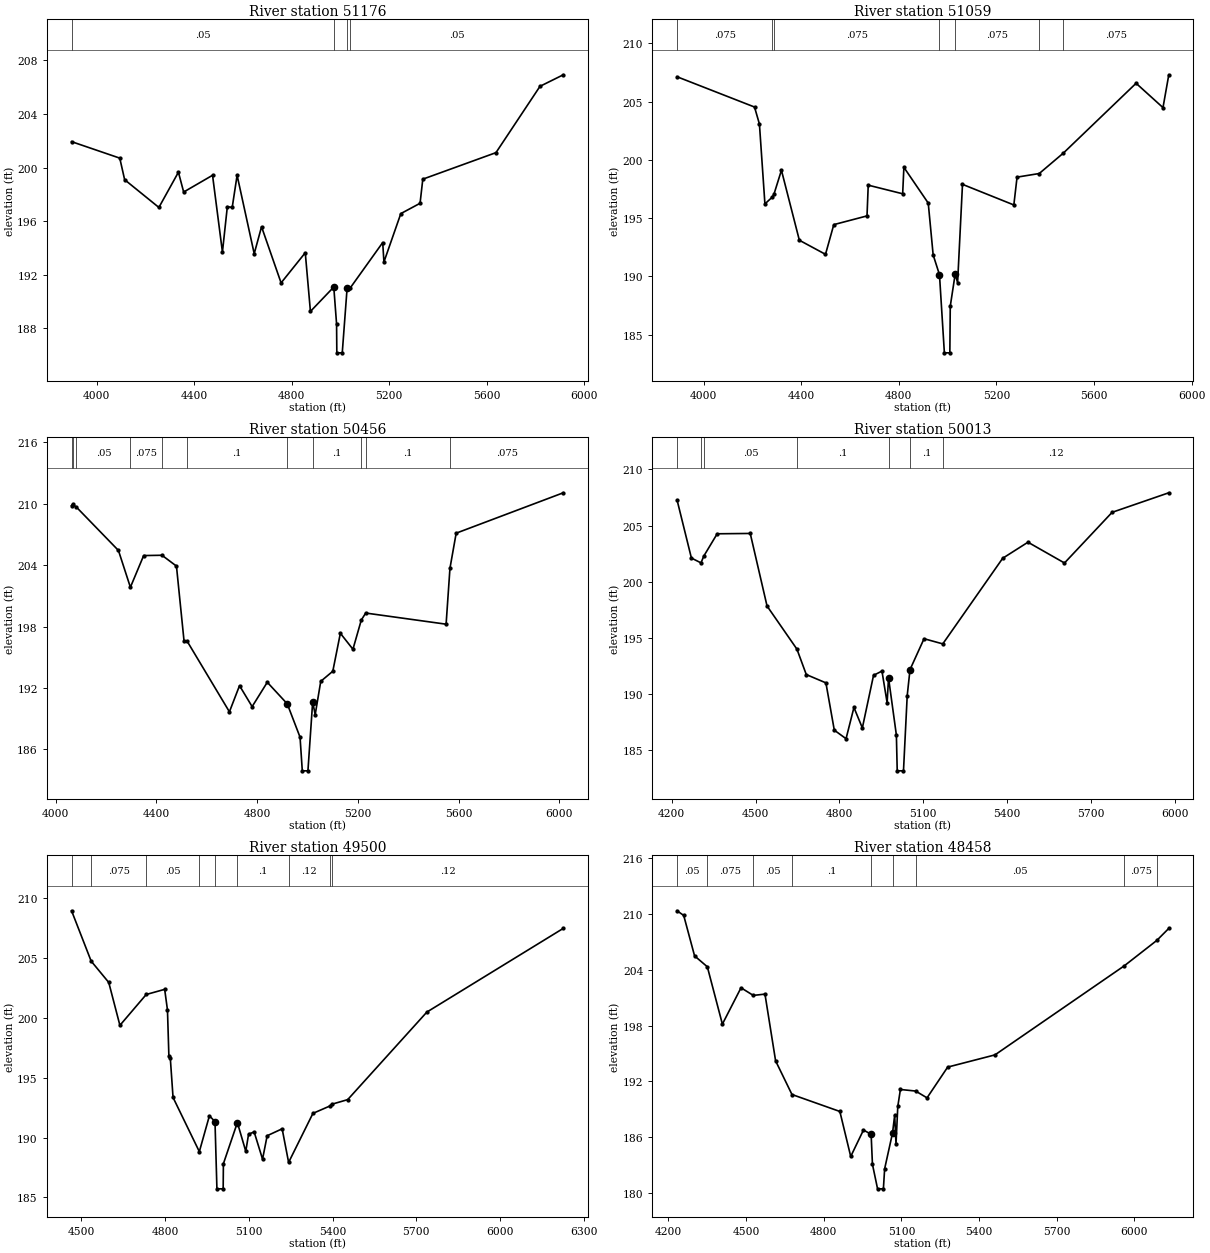
Type RM Length L Ch R = 1 ,51176   ,117,117,117
BEGIN DESCRIPTION:
STEWARTS CREEK 100.0
END DESCRIPTION:
XS GIS Cut Line= 3
      3840195.01     10121422.13      3839094.76     10121334.94
      3838182.43     10121393.45
#Sta/Elev= 30
  3896.3  201.93  4094.1   200.7  4114.1  199.09  4254.6  197.02  4334.8  199.65
  4356.3  198.17  4474.8  199.42  4515.4  193.69  4535.5  197.08  4555.5  197.02
  4575.6  199.42  4645.8  193.57  4675.9  195.58  4756.1  191.39  4855.3  193.64
  4876.5  189.26 4972.31 191.081  4983.8  188.32  4984.8  186.17  5007.1  186.17
    5027     191  5040.1  191.02  5173.1   194.4  5178.1  192.95  5247.4  196.56
  5326.4  197.33  5337.6  199.13  5637.9  201.11  5818.6  206.06  5914.2  206.92
#Mann= 4 ,-1 , 0
  3896.3     .05       0 4972.31     .07       0    5027     .05       0
  5040.1     .05       0
Bank Sta=4972.31,5027
XS Rating Curve= 0 ,0
Exp/Cntr=0.3,0.1

Type RM Length L Ch R = 1 ,51059   ,603,603,603
BEGIN DESCRIPTION:
STEWARTS CREEK 99.0
END DESCRIPTION:
XS GIS Cut Line= 3
      3840184.51     10121140.88      3839078.77     10121219.02
      3838174.12     10121273.69
#Sta/Elev= 30
  3891.5  207.14  4208.9  204.54    4229  203.08  4251.5  196.22  4281.9  196.81
  4288.5  197.05  4319.2  199.11  4392.6   193.1  4499.7  191.89  4533.7  194.44
  4669.8  195.19  4674.8  197.83  4815.9  197.09  4820.9  199.36  4920.7  196.29
  4940.8  191.84 4966.72 190.141  4986.8  183.43  5009.2  183.43  5010.9  187.43
    5031  190.19    5041  189.46    5061   197.9  5271.4  196.13  5284.6  198.52
  5375.5  198.83  5474.6  200.59  5772.3  206.58  5882.5  204.49  5906.3  207.31
#Mann= 7 ,-1 , 0
  3891.5    .075       0  4281.9     .05       0  4288.5    .075       0
 4966.72     .07       0    5031    .075       0  5375.5     .05       0
  5474.6    .075       0
Bank Sta=4966.72,5031
XS Rating Curve= 0 ,0
Exp/Cntr=0.3,0.1

Type RM Length L Ch R = 1 ,50456   ,443,443,443
BEGIN DESCRIPTION:
Mapping XS a3c352fb
END DESCRIPTION:
XS GIS Cut Line= 3
      3840163.71     10120797.12      3839228.23     10120857.05
      3838212.33     10120836.99
#Sta/Elev= 30
  4062.6  209.83    4067  209.95  4082.1  209.67  4248.8  205.44  4296.3  201.84
    4349  204.94  4421.8  204.97  4479.3  203.91  4509.4  196.59  4520.9   196.6
  4689.7  189.66  4729.8  192.22  4779.9  190.17  4840.1  192.55  4919.4 190.444
  4970.3  187.18  4979.2  183.89  5001.6  183.89  5020.4  190.64  5030.4  189.38
  5052.5  192.64  5100.4  193.63  5130.4  197.34  5180.4  195.78  5213.5  198.63
  5231.1  199.32  5550.5  198.23  5565.8   203.7  5590.5  207.13  6016.1  211.08
#Mann= 11 ,-1 , 0
  4062.6     .05       0    4067    .075       0  4082.1     .05       0
  4296.3    .075       0  4421.8     .05       0  4520.9      .1       0
  4919.4     .07       0  5020.4      .1       0  5213.5    .075       0
  5231.1      .1       0  5565.8    .075       0
Bank Sta=4919.4,5020.4
XS Rating Curve= 0 ,0
Exp/Cntr=0.3,0.1

Type RM Length L Ch R = 1 ,50013   ,513,513,513
BEGIN DESCRIPTION:
STEWARTS CREEK 98.0
END DESCRIPTION:
XS GIS Cut Line= 3
        3840109.     10120416.92      3839329.96     10120467.77
       3838356.4     10120377.85
#Sta/Elev= 30
  4219.3  207.28  4270.6  202.11  4304.9  201.68    4315  202.29  4362.8  204.27
    4481   204.3  4541.1  197.84    4648     194  4681.4  191.74  4751.6     191
  4781.6  186.79  4823.6  186.03  4851.8  188.81  4881.9  186.99  4921.9  191.67
    4952  192.05  4970.5  189.23  4975.5  191.45  5003.6  186.35  5006.6  183.17
    5029  183.17  5042.3  189.86  5052.3  192.18  5102.5  194.93  5169.5  194.47
  5383.7  202.09  5474.1  203.52  5604.7  201.67    5775  206.18  5977.7  207.92
#Mann= 7 ,-1 , 0
  4219.3     .05       0  4304.9    .075       0    4315     .05       0
    4648      .1       0  4975.5     .07       0  5052.3      .1       0
  5169.5     .12       0
Bank Sta=4975.5,5052.3
XS Rating Curve= 0 ,0
Exp/Cntr=0.3,0.1

Type RM Length L Ch R = 1 ,49500   ,1042,1042,1042
BEGIN DESCRIPTION:
STEWARTS CREEK 97.0
END DESCRIPTION:
XS GIS Cut Line= 3
      3840100.75     10120087.94       3839566.8      10120054.4
      3838342.89     10120140.03
#Sta/Elev= 30
    4465  208.97  4535.2  204.76  4598.2  202.98  4638.2  199.39  4732.5  201.97
  4798.6   202.4  4808.6  200.68  4813.7  196.82  4818.7  196.68  4828.6  193.36
  4922.8  188.83  4958.9  191.83  4978.9  191.34  4985.8  185.72  5008.2  185.72
    5009  187.82  5059.1  191.26  5089.2  188.86  5099.2  190.29  5119.2  190.48
  5149.3   188.2  5165.8  190.16  5219.5  190.74  5242.7  187.93  5329.8  192.03
  5390.9  192.65    5397  192.79  5454.4  193.18    5738   200.5  6226.9   207.5
#Mann= 9 ,-1 , 0
    4465     .05       0  4535.2    .075       0  4732.5     .05       0
  4922.8      .1       0  4978.9     .07       0  5059.1      .1       0
  5242.7     .12       0  5390.9      .1       0    5397     .12       0
Bank Sta=4978.9,5059.1
XS Rating Curve= 0 ,0
Exp/Cntr=0.3,0.1

Type RM Length L Ch R = 1 ,48458   ,958,958,958
BEGIN DESCRIPTION:
STEWARTS CREEK 95.0
END DESCRIPTION:
XS GIS Cut Line= 3
      3840158.07     10119752.01      3839412.47     10119572.98
      3838296.07     10119765.03
#Sta/Elev= 30
  4233.2  210.31  4258.9  209.81  4300.9  205.47  4350.2   204.3  4408.3  198.15
  4480.3  202.05  4527.7  201.23  4572.8  201.37  4613.9  194.21  4677.1   190.6
  4862.1  188.78  4904.1  183.95  4953.3  186.79  4982.9  186.33    4988  183.11
  5007.8  180.48  5030.3  180.48  5035.1  182.63  5065.6  186.47  5073.9  188.38
    5079  185.28  5085.9  189.32    5096  191.14  5154.9  190.97  5198.9  190.24
  5278.6  193.54  5461.3  194.85  5961.1  204.41  6086.5  207.13  6132.8  208.42
#Mann= 9 ,-1 , 0
  4233.2     .05       0  4350.2    .075       0  4527.7     .05       0
  4677.1      .1       0  4982.9     .07       0  5065.6      .1       0
  5154.9     .05       0  5961.1    .075       0  6086.5      .1       0
Bank Sta=4982.9,5065.6
XS Rating Curve= 0 ,0
Exp/Cntr=0.3,0.1

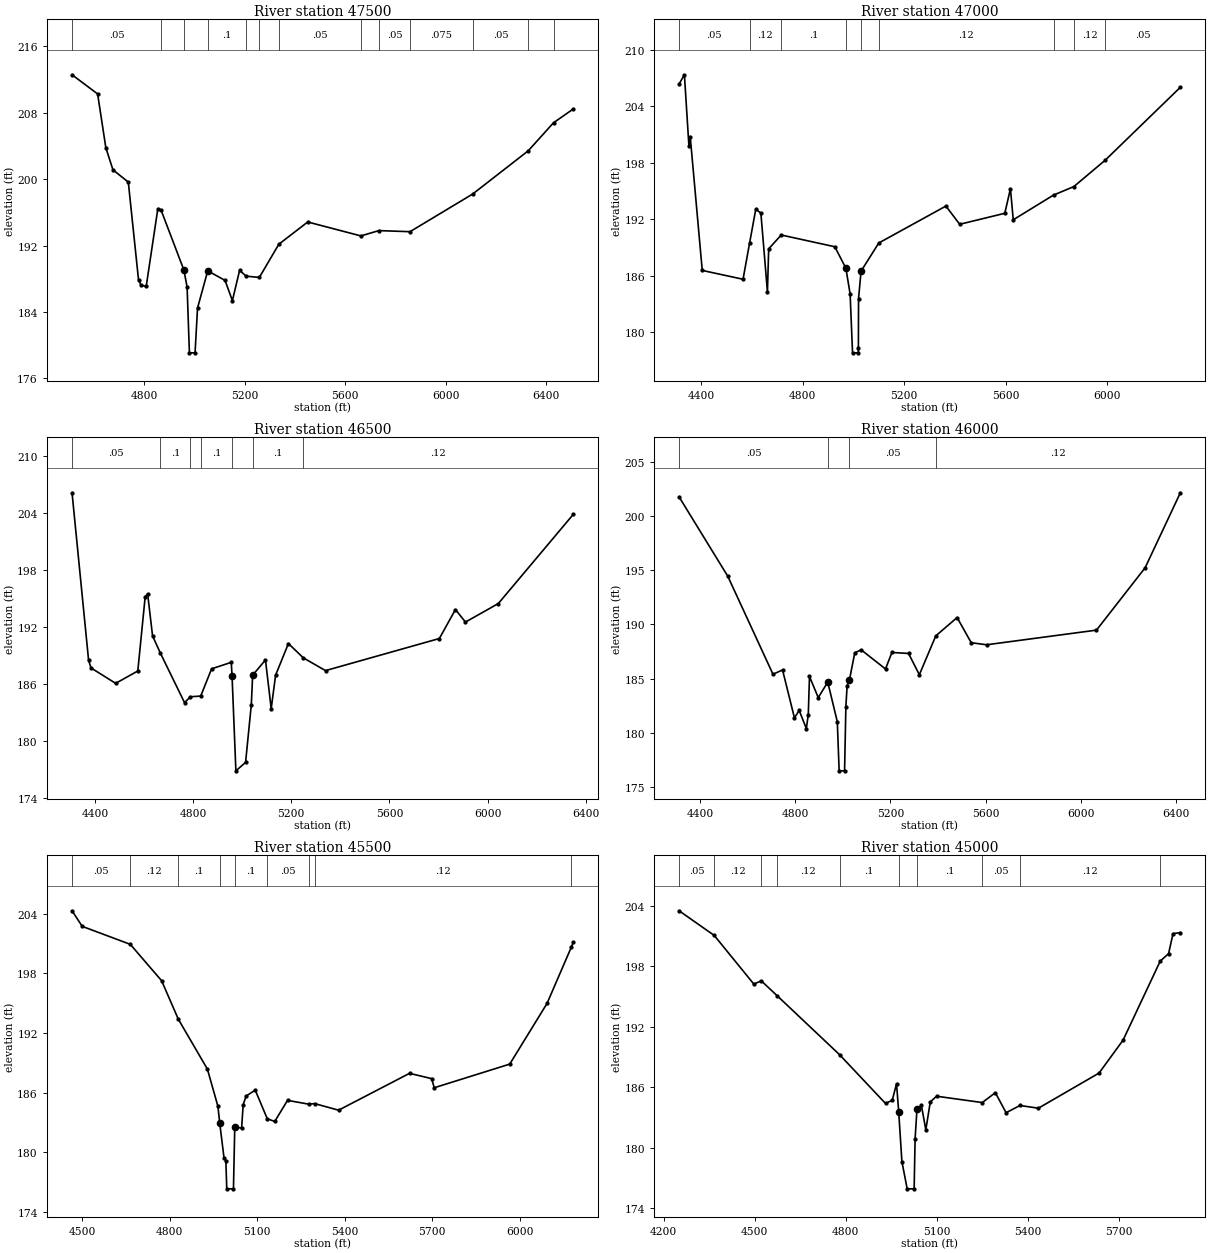
Type RM Length L Ch R = 1 ,47500   ,500,500,500
BEGIN DESCRIPTION:
STEWARTS CREEK 93.0
END DESCRIPTION:
XS GIS Cut Line= 3
      3840067.86     10118861.07      3839588.83     10118953.69
      3838211.92      10119570.6
#Sta/Elev= 30
  4512.1  212.58    4614  210.27  4646.7  203.79  4675.1  201.12  4736.2  199.65
  4776.9  187.87  4787.1  187.22  4807.5  187.07  4853.9  196.45  4866.5  196.29
  4957.5  189.06  4970.4     187  4979.6  179.07  5002.1  179.07    5012  184.47
  5052.6  188.95  5121.6   187.8  5150.8  185.36  5179.5  189.01  5205.6  188.31
  5258.1  188.16  5335.9  192.16  5450.9  194.84  5662.7  193.16  5734.2   193.8
  5858.3  193.67    6108  198.21  6329.3  203.42    6430   206.8  6508.8  208.46
#Mann= 13 ,-1 , 0
  4512.1     .05       0  4866.5      .1       0  4957.5     .07       0
  5052.6      .1       0  5205.6     .12       0  5258.1      .1       0
  5335.9     .05       0  5662.7    .075       0  5734.2     .05       0
  5858.3    .075       0    6108     .05       0  6329.3    .075       0
    6430      .1       0
Bank Sta=4957.5,5052.6
XS Rating Curve= 0 ,0
Exp/Cntr=0.3,0.1

Type RM Length L Ch R = 1 ,47000   ,500,500,500
BEGIN DESCRIPTION:
STEWARTS CREEK 92.0
END DESCRIPTION:
XS GIS Cut Line= 3
      3839988.74     10118511.99      3839304.82     10118579.13
      3838145.02     10119140.46
#Sta/Elev= 30
  4312.8  206.39  4333.8  207.37  4351.7  199.74  4356.7  200.79  4404.1  186.55
  4564.9  185.61  4590.6  189.45  4615.1  193.07  4635.2  192.65    4661  184.28
    4666  188.85  4715.4  190.32  4926.6  189.07  4970.3  186.78  4986.9  184.05
  4996.5  177.78    5019  177.78  5019.5  178.28  5020.2  183.56    5030  186.47
  5099.9  189.47  5364.5   193.4  5418.8  191.46  5596.6  192.63  5618.8  195.25
  5629.9  191.94  5788.7  194.57  5868.7  195.47  5992.3  198.28  6288.5  206.04
#Mann= 9 ,-1 , 0
  4312.8     .05       0  4590.6     .12       0  4715.4      .1       0
  4970.3     .07       0    5030      .1       0  5099.9     .12       0
  5788.7     .05       0  5868.7     .12       0  5992.3     .05       0
Bank Sta=4970.3,5030
XS Rating Curve= 0 ,0
Exp/Cntr=0.3,0.1

Type RM Length L Ch R = 1 ,46500   ,500,500,500
BEGIN DESCRIPTION:
STEWARTS CREEK 91.0
END DESCRIPTION:
XS GIS Cut Line= 3
      3840065.19     10118255.04      3839373.58     10118209.61
      3838138.12     10118751.55
#Sta/Elev= 30
  4306.9  206.09  4374.4  188.44  4384.4  187.65  4484.6  186.03  4574.8  187.33
  4604.9  195.15  4614.9  195.45  4634.9  191.03  4666.3  189.24  4765.2     184
  4789.3  184.62  4831.1  184.69  4875.5  187.56  4955.6  188.24 4958.83 186.807
  4974.4  176.82  5013.9  177.71  5037.3  183.79  5042.7  186.89  5094.9  188.49
  5118.3  183.37  5136.2  186.89  5188.4  190.22  5249.3  188.71  5339.5  187.37
  5803.4  190.75  5868.9   193.8  5909.7  192.48  6043.6  194.43  6349.1  203.82
#Mann= 7 ,-1 , 0
  4306.9     .05       0  4666.3      .1       0  4789.3     .12       0
  4831.1      .1       0 4958.83     .07       0  5042.7      .1       0
  5249.3     .12       0
Bank Sta=4958.83,5042.7
XS Rating Curve= 0 ,0
Exp/Cntr=0.3,0.1

Type RM Length L Ch R = 1 ,46000   ,500,500,500
BEGIN DESCRIPTION:
STEWARTS CREEK 90.0
END DESCRIPTION:
XS GIS Cut Line= 3
      3840162.41     10117782.82      3839474.34     10117812.12
      3838121.75     10118240.83
#Sta/Elev= 30
  4311.3  201.75    4516  194.44  4706.2   185.4  4746.3   185.8  4796.3  181.38
  4816.3  182.07  4846.3   180.4  4854.5  181.68  4859.6   185.2  4896.4  183.25
  4936.4  184.68  4976.5  181.03  4984.3   176.5  5007.1   176.5  5012.6  182.42
  5017.8  184.33  5027.8  184.91  5050.1  187.39  5077.1  187.65  5179.2  185.89
  5206.1  187.41  5276.1  187.32  5321.5  185.36  5390.6  188.94  5480.3  190.63
  5539.6  188.31  5604.2  188.12  6066.3  189.47  6270.8  195.22  6418.9  202.13
#Mann= 4 ,-1 , 0
  4311.3     .05       0  4936.4     .07       0  5027.8     .05       0
  5390.6     .12       0
Bank Sta=4936.4,5027.8
XS Rating Curve= 0 ,0
Exp/Cntr=0.3,0.1

Type RM Length L Ch R = 1 ,45500   ,500,500,500
BEGIN DESCRIPTION:
STEWARTS CREEK 89.0
END DESCRIPTION:
XS GIS Cut Line= 3
      3839540.84      10117064.1      3839214.68     10117486.79
      3838131.98     10117963.01
#Sta/Elev= 30
  4466.1  204.31    4501  202.74  4665.6  200.93  4772.8  197.27  4830.1  193.39
  4929.6  188.37  4965.7  184.62    4972  182.89  4986.5  179.45  4992.9  179.07
    4996  176.31  5018.9  176.31  5023.4  182.58  5046.8  182.41  5052.2  184.78
  5062.1  185.65  5093.5  186.25  5134.8  183.36  5160.4   183.1  5204.1  185.22
  5275.9  184.84  5297.4  184.89  5378.9  184.23  5621.9  187.94  5697.4  187.41
  5706.6  186.49  5965.1  188.87  6092.8  194.98  6175.9  200.64  6182.8  201.15
#Mann= 9 ,-1 , 0
  4466.1     .05       0  4665.6     .12       0  4830.1      .1       0
    4972     .07       0  5023.4      .1       0  5134.8     .05       0
  5275.9      .1       0  5297.4     .12       0  6175.9     .05       0
Bank Sta=4972,5023.4
XS Rating Curve= 0 ,0
Exp/Cntr=0.3,0.1

Type RM Length L Ch R = 1 ,45000   ,500,500,500
BEGIN DESCRIPTION:
STEWARTS CREEK 88.0
END DESCRIPTION:
XS GIS Cut Line= 3
      3839520.06      10117008.5      3838813.86     10117257.48
      3838092.91     10117800.21
#Sta/Elev= 30
  4251.2  203.52    4367  201.07  4497.4  196.24    4522  196.56  4574.3  195.08
    4780  189.22  4931.2  184.38  4953.4   184.7  4967.5  186.34  4974.6  183.57
  4985.2   178.6  5002.6   175.9  5025.5   175.9  5028.6  180.84  5034.9  183.85
  5049.4  184.18    5064  181.76  5078.6  184.53  5099.4   185.1  5249.9  184.47
    5293  185.45  5328.4  183.46  5374.2  184.18  5434.7  183.91  5634.6   187.4
  5713.7  190.67  5836.1  198.52  5863.6  199.26  5878.2  201.25  5902.4  201.35
#Mann= 10 ,-1 , 0
  4251.2     .05       0    4367     .12       0    4522     .05       0
  4574.3     .12       0    4780      .1       0  4974.6     .07       0
  5034.9      .1       0  5249.9     .05       0  5374.2     .12       0
  5836.1     .05       0
Bank Sta=4974.6,5034.9
XS Rating Curve= 0 ,0
Exp/Cntr=0.3,0.1

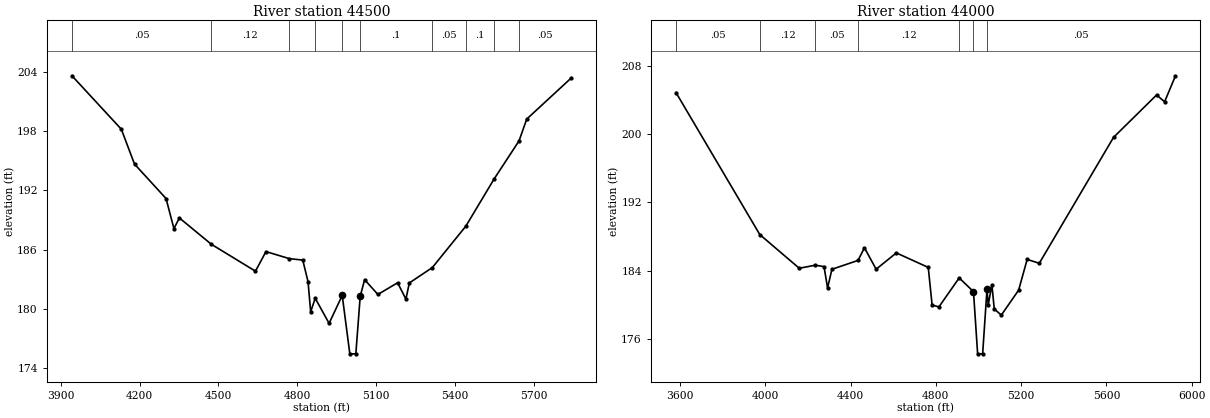
Type RM Length L Ch R = 1 ,44500   ,500,500,500
BEGIN DESCRIPTION:
STEWARTS CREEK 87.0
END DESCRIPTION:
XS GIS Cut Line= 3
      3839495.67     10116942.54      3838439.16     10116977.91
      3838065.18     10117734.19
#Sta/Elev= 30
  3942.9  203.57  4130.8  198.17  4180.9  194.65  4300.9  191.17  4330.9  188.13
  4351.6  189.21  4473.2  186.55  4641.1  183.83  4681.1  185.81  4769.7   185.1
  4821.2  184.95  4841.2  182.77  4851.2  179.73  4868.6  181.09  4921.3  178.56
  4971.3  181.38  5000.2  175.48  5023.1  175.48  5039.7  181.29  5056.5  182.97
    5107  181.48    5182  182.66  5213.6  181.01  5226.6  182.64  5314.3   184.2
  5441.7  188.38  5549.3  193.15    5644  196.99  5673.5   199.2  5843.7  203.37
#Mann= 10 ,-1 , 0
  3942.9     .05       0  4473.2     .12       0  4769.7     .05       0
  4868.6      .1       0  4971.3     .07       0  5039.7      .1       0
  5314.3     .05       0  5441.7      .1       0  5549.3     .12       0
    5644     .05       0
Bank Sta=4971.3,5039.7
XS Rating Curve= 0 ,0
Exp/Cntr=0.3,0.1

Type RM Length L Ch R = 1 ,44000   ,500,500,500
BEGIN DESCRIPTION:
STEWARTS CREEK 86.0
END DESCRIPTION:
XS GIS Cut Line= 3
      3839514.02     10116918.31       3838124.9     10116627.18
      3837287.46     10117018.14
#Sta/Elev= 30
  3580.7  204.87    3974  188.22  4159.2  184.27  4234.9  184.63  4275.4  184.46
    4292  181.96  4312.4  184.15  4434.9  185.19  4464.9  186.67  4519.9  184.16
  4614.6  186.07  4764.4  184.37  4782.4  179.96  4814.3  179.74  4909.5  183.14
  4976.5  181.53    4996  174.24  5019.5  174.24    5040  181.84  5045.5  179.95
  5062.9  182.33    5074   179.5  5107.1  178.78  5188.2   181.7  5228.4  185.31
  5285.1  184.85  5633.5  199.61  5835.5  204.58  5873.1  203.78  5924.2  206.83
#Mann= 7 ,-1 , 0
  3580.7     .05       0    3974     .12       0  4234.9     .05       0
  4434.9     .12       0  4909.5     .05       0  4976.5     .07       0
    5040     .05       0
Bank Sta=4976.5,5040
XS Rating Curve= 0 ,0
Exp/Cntr=0.3,0.1