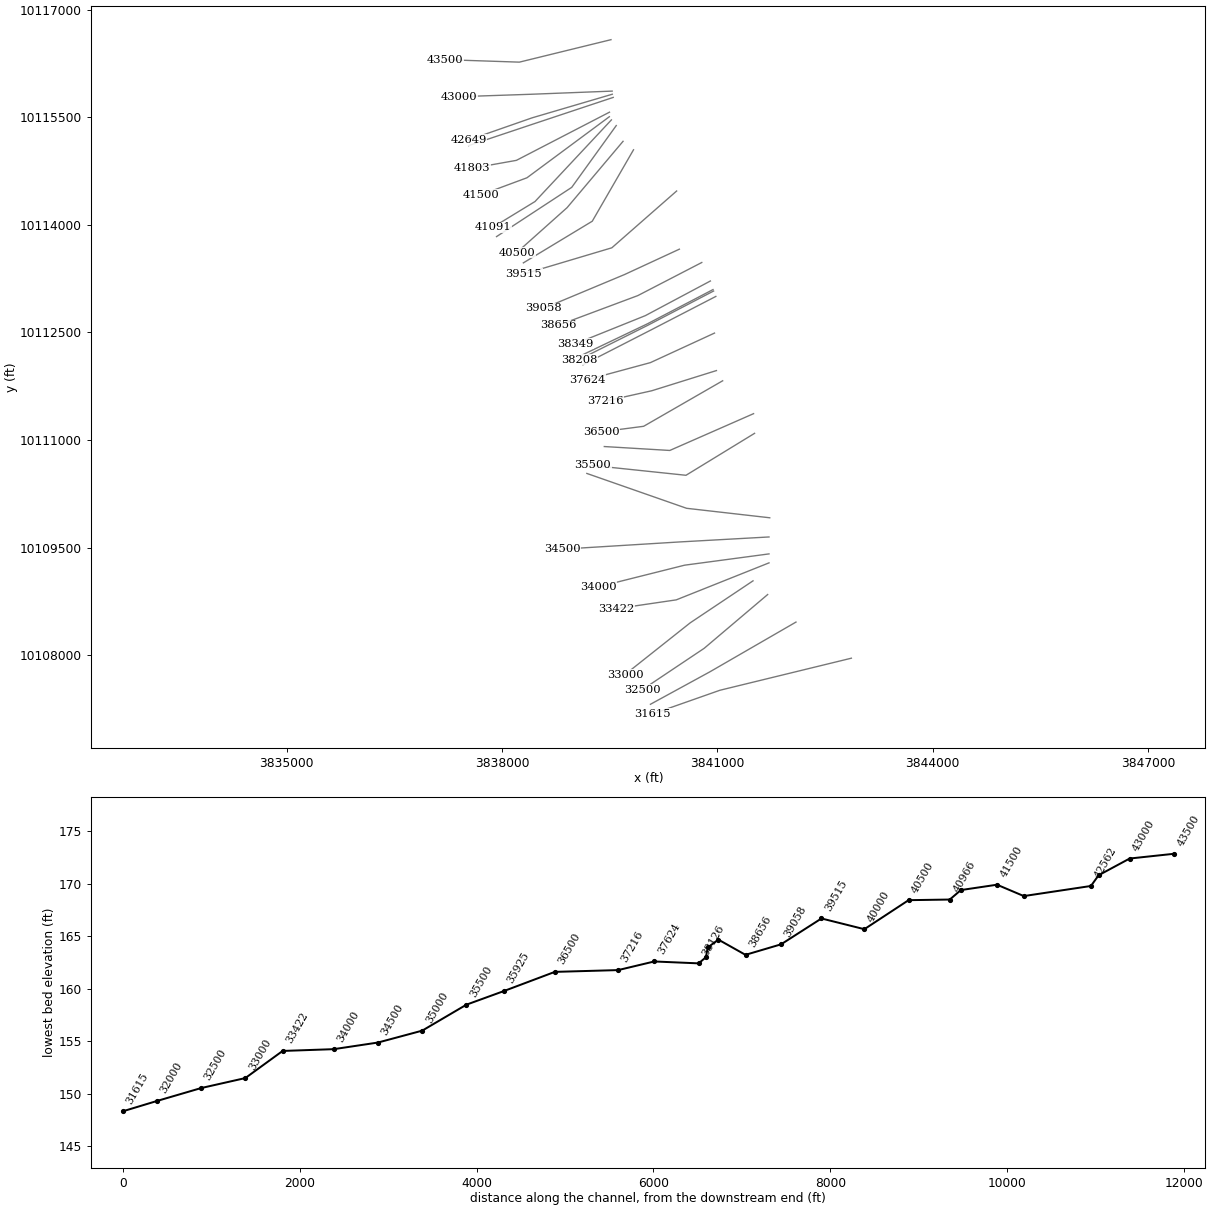
HEC-RAS study STEWARTS CREEK.prj: STEWARTS CREEK Base Level Engineering

--- STEWARTS CREEK.g10 (geometry) --- (continued)

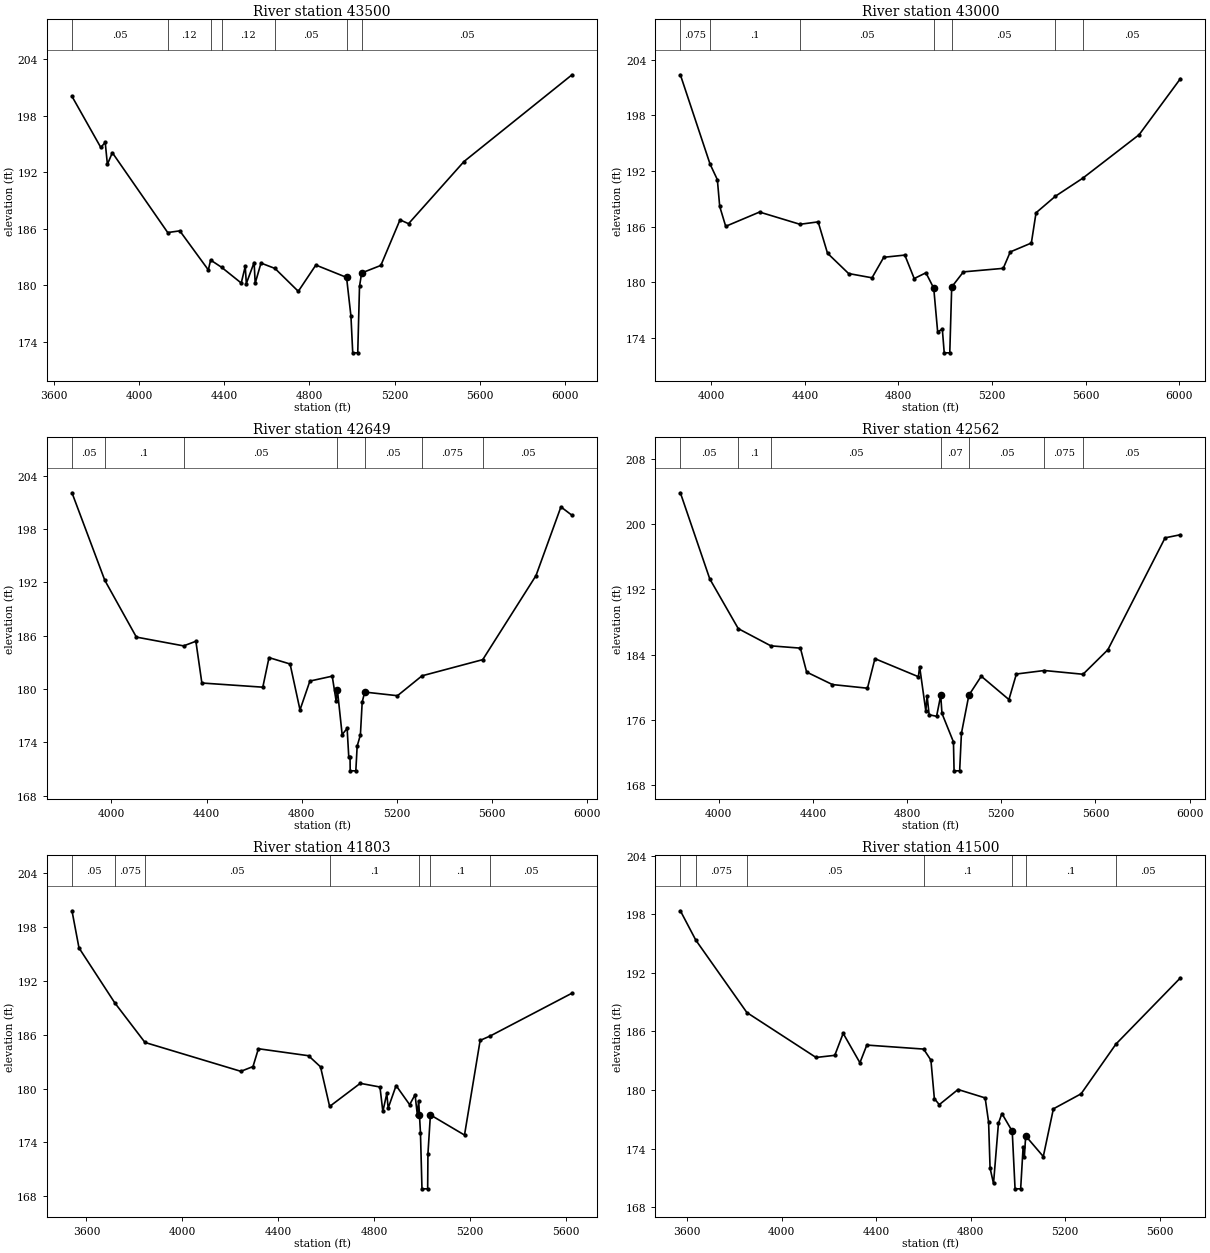
Type RM Length L Ch R = 1 ,43500   ,500,500,500
BEGIN DESCRIPTION:
STEWARTS CREEK 85.0
END DESCRIPTION:
XS GIS Cut Line= 3
      3839519.28     10116580.57      3838242.63     10116267.42
       3837211.1     10116301.93
#Sta/Elev= 30
  3685.5  200.06  3820.8  194.63  3841.4  195.18  3851.7  192.84  3874.9  194.08
  4134.8   185.6  4191.5  185.78  4325.4  181.63  4336.1  182.68  4387.7  181.91
  4479.8  180.24  4498.6  182.01  4503.7  180.19  4540.2  182.42  4545.3  180.22
  4572.5  182.36  4638.1  181.79  4747.5  179.36  4829.9  182.15    4974  180.84
  4994.6  176.73    5003  172.83  5026.5  172.83  5034.8  179.88  5044.8  181.31
  5134.9  182.11  5224.9  186.95  5264.9  186.54  5525.1  193.14  6032.1  202.35
#Mann= 7 ,-1 , 0
  3685.5     .05       0  4134.8     .12       0  4336.1     .05       0
  4387.7     .12       0  4638.1     .05       0    4974     .07       0
  5044.8     .05       0
Bank Sta=4974,5044.8
XS Rating Curve= 0 ,0
Exp/Cntr=0.3,0.1

Type RM Length L Ch R = 1 ,43000   ,351,351,351
BEGIN DESCRIPTION:
STEWARTS CREEK 84.0
END DESCRIPTION:
XS GIS Cut Line= 3
      3839535.77     10115863.63      3838405.13     10115819.57
       3837401.6     10115785.54
#Sta/Elev= 30
  3868.5  202.36  3995.3  192.73  4026.5  191.05  4036.5  188.17  4062.1  186.02
  4206.7  187.56  4379.2  186.24  4456.9   186.5  4496.9  183.12    4587  180.93
    4687  180.47  4737.1  182.68  4827.1  182.92  4867.2  180.39  4917.2  181.01
 4950.61 179.353  4967.3  174.65  4987.3  174.93  4995.4  172.38  5019.1  172.38
  5027.3  179.48  5077.3  181.11  5247.4  181.49  5277.4  183.26  5367.5  184.22
  5387.5  187.48  5470.4  189.27  5587.1  191.21  5827.8   195.9  6004.1  201.94
#Mann= 7 ,-1 , 0
  3868.5    .075       0  3995.3      .1       0  4379.2     .05       0
 4950.61     .07       0  5027.3     .05       0  5470.4    .075       0
  5587.1     .05       0
Bank Sta=4950.61,5027.3
XS Rating Curve= 0 ,0
Exp/Cntr=0.3,0.1

Type RM Length L Ch R = 1 ,42649   ,87,87,87
BEGIN DESCRIPTION:
Mapping XS cf581715
END DESCRIPTION:
XS GIS Cut Line= 3
      3839537.51     10115820.06      3838419.28      10115490.8
      3837534.92     10115182.05
#Sta/Elev= 30
  3834.3   202.1  3972.2  192.25    4105  185.85  4303.6  184.86  4355.2  185.38
  4380.4  180.68  4636.6  180.21  4662.7  183.54  4751.3  182.82    4793  177.65
  4834.6   180.9  4928.5  181.45    4945  178.63  4950.3  179.87  4970.2  174.87
  4991.1  175.57  4998.1  172.33  5003.4  172.33    5004  170.79  5027.7  170.79
  5033.3  173.57  5046.9  174.83  5054.5  178.54  5065.1  179.66  5202.8  179.25
    5306  181.49  5561.3  183.31  5785.3  192.78    5890  200.51  5936.7  199.56
#Mann= 7 ,-1 , 0
  3834.3     .05       0  3972.2      .1       0  4303.6     .05       0
  4950.3     .07       0  5065.1     .05       0    5306    .075       0
  5561.3     .05       0
Bank Sta=4950.3,5065.1
XS Rating Curve= 0 ,0
Exp/Cntr=0.3,0.1

Type RM Length L Ch R = 1 ,42562   ,759,759,759
BEGIN DESCRIPTION:
STEWARTS CREEK 83.0
END DESCRIPTION:
XS GIS Cut Line= 3
      3839550.53     10115775.79      3838446.92     10115408.58
       3837535.6     10115103.93
#Sta/Elev= 30
  3836.9  203.83  3961.8  193.28  4082.8  187.19  4221.3  185.08  4346.8   184.8
  4373.2  181.87  4482.6  180.34  4631.6  179.89  4663.3  183.51  4847.9   181.3
  4853.2  182.54  4879.5  177.09  4884.8  178.98  4893.6  176.64  4925.2  176.45
  4942.8  179.01  4948.1   176.8  4996.9  173.31  4999.5  169.77  5023.2  169.77
  5030.7  174.36  5062.3  179.03    5115  181.36  5232.5   178.5  5264.1  181.63
  5382.7  182.06  5547.2   181.6  5652.7   184.6  5895.8  198.31  5960.9  198.69
#Mann= 7 ,-1 , 0
  3836.9     .05       0  4082.8      .1       0  4221.3     .05       0
  4942.8     .07       0  5062.3     .05       0  5382.7    .075       0
  5547.2     .05       0
Bank Sta=4942.8,5062.3
XS Rating Curve= 0 ,0
Exp/Cntr=0.3,0.1

Type RM Length L Ch R = 1 ,41803   ,303,303,303
BEGIN DESCRIPTION:
STEWARTS CREEK 82.0
END DESCRIPTION:
XS GIS Cut Line= 3
      3839498.04     10115569.86       3838201.1      10114898.3
      3837586.51     10114788.59
#Sta/Elev= 30
  3539.5  199.83  3568.7  195.69  3717.9  189.56  3843.9  185.14  4243.6  181.92
  4294.2  182.45  4316.7  184.44  4525.7  183.66  4575.7  182.42  4613.7     178
  4741.4  180.58  4823.5  180.17  4835.6  177.44  4852.1  179.45  4857.7  177.81
  4890.8  180.33  4947.3   178.2  4969.9  179.31  4979.3  177.08  4984.9  178.63
  4988.3 177.012  4992.4  175.06  4998.7  168.81  5022.4  168.81  5023.6  172.73
  5033.8  177.06    5176  174.81  5241.2  185.37  5283.9  185.87  5624.3  190.64
#Mann= 7 ,-1 , 0
  3539.5     .05       0  3717.9    .075       0  3843.9     .05       0
  4613.7      .1       0  4988.3     .07       0  5033.8      .1       0
  5283.9     .05       0
Bank Sta=4988.3,5033.8
XS Rating Curve= 0 ,0
Exp/Cntr=0.3,0.1

Type RM Length L Ch R = 1 ,41500   ,409,409,409
BEGIN DESCRIPTION:
STEWARTS CREEK 81.0
END DESCRIPTION:
XS GIS Cut Line= 3
       3839496.3      10115506.5      3838348.19     10114655.34
      3837703.73      10114416.2
#Sta/Elev= 30
  3570.8  198.36    3636  195.36  3852.3  187.94  4145.1  183.34  4224.4  183.56
  4259.9  185.81  4330.8   182.8    4360  184.61  4600.5   184.2  4631.3  183.07
  4645.9  179.13  4666.7  178.51  4746.1  180.06  4860.9   179.2  4875.5  176.73
  4881.7  172.01  4896.3  170.44  4917.2  176.61  4931.8   177.6  4975.5  175.79
  4987.5  169.89  5011.2  169.89  5021.5  174.14  5026.8   173.1  5032.4  175.31
    5107   173.2  5149.7  178.08    5267  179.62  5414.8  184.72  5687.4  191.49
#Mann= 7 ,-1 , 0
  3570.8     .05       0    3636    .075       0  3852.3     .05       0
  4600.5      .1       0  4975.5     .07       0  5032.4      .1       0
  5414.8     .05       0
Bank Sta=4975.5,5032.4
XS Rating Curve= 0 ,0
Exp/Cntr=0.3,0.1

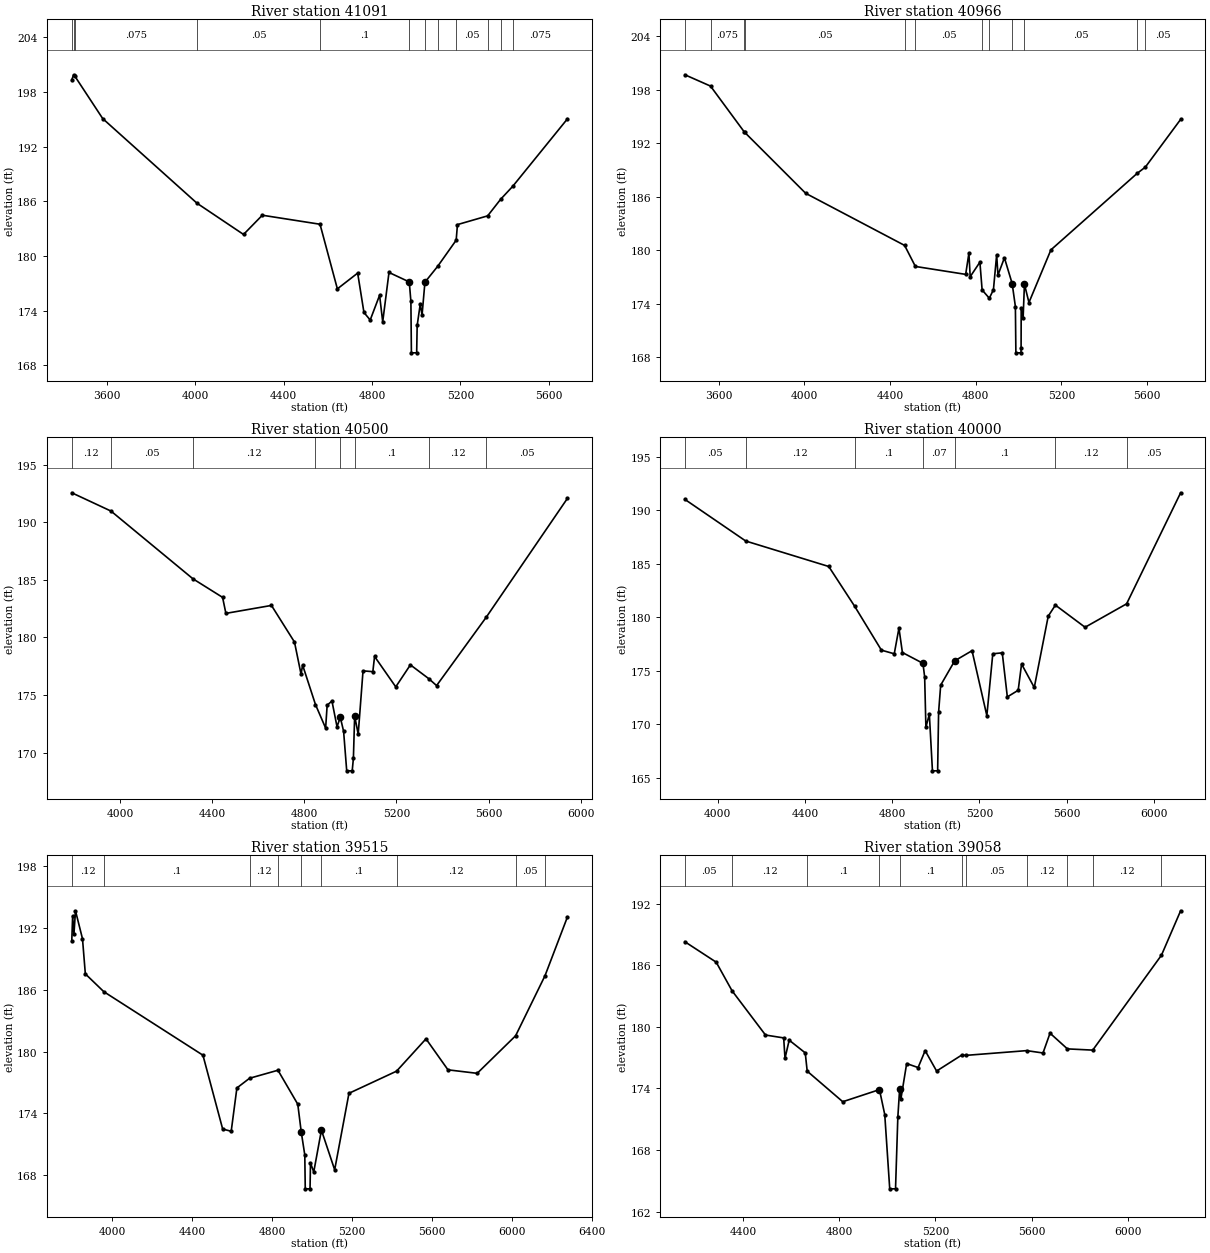
Type RM Length L Ch R = 1 ,41091   ,125,125,125
BEGIN DESCRIPTION:
STEWARTS CREEK 80.0
END DESCRIPTION:
XS GIS Cut Line= 3
      3839524.94     10115462.23      3838460.57     10114324.35
      3837876.49     10113967.42
#Sta/Elev= 30
  3441.9  199.33  3450.3  199.89  3454.4  199.79    3582  195.08  4008.8  185.79
    4219  182.37    4304  184.48    4565  183.49  4643.5   176.4  4735.3  178.13
  4763.7  173.81    4792  172.98  4834.5   175.7  4848.6  172.78    4877   178.2
  4968.8  177.16  4976.1  175.02  4978.4  169.38  5002.2  169.38  5004.5  172.38
  5018.3  174.71  5026.6  173.53  5039.6  177.13  5097.5  178.88    5181  181.74
  5186.7  183.45  5323.4  184.41  5382.1  186.23  5436.4  187.64  5684.5  195.06
#Mann= 12 ,-1 , 0
  3441.9    .075       0  3450.3     .05       0  3454.4    .075       0
  4008.8     .05       0    4565      .1       0  4968.8     .07       0
  5039.6      .1       0  5097.5      .1       0    5181     .05       0
  5323.4     .12       0  5382.1     .05       0  5436.4    .075       0
Bank Sta=4968.8,5039.6
XS Rating Curve= 0 ,0
Exp/Cntr=0.3,0.1

Type RM Length L Ch R = 1 ,40966   ,466,466,466
BEGIN DESCRIPTION:
Mapping XS c4c9fd89
END DESCRIPTION:
XS GIS Cut Line= 3
      3839592.63     10115383.37      3838971.97     10114521.81
       3837924.5     10113835.35
#Sta/Elev= 30
  3442.1   199.7  3561.6  198.43  3720.2  193.25  3721.9  193.22    4006  186.39
  4467.8  180.54    4518  178.18  4752.8  177.29  4767.9  179.67  4773.9  177.03
  4819.2  178.66  4829.6  175.54  4863.2  174.61  4882.4  175.57  4897.5   179.5
  4903.5  177.21  4933.7  179.15  4969.8  176.26  4984.9  173.68  4987.2  168.48
    5011  168.48  5011.5  168.98    5012  173.47  5021.1  172.44  5027.1  176.19
  5048.2  174.13  5150.7  180.04  5553.8  188.64  5591.5  189.33  5756.3  194.69
#Mann= 12 ,-1 , 0
  3442.1     .05       0  3561.6    .075       0  3720.2     .12       0
  3721.9     .05       0  4467.8     .12       0    4518     .05       0
  4829.6      .1       0  4863.2     .05       0  4969.8     .07       0
  5027.1     .05       0  5553.8    .075       0  5591.5     .05       0
Bank Sta=4969.8,5027.1
XS Rating Curve= 0 ,0
Exp/Cntr=0.3,0.1

Type RM Length L Ch R = 1 ,40500   ,500,500,500
BEGIN DESCRIPTION:
STEWARTS CREEK 79.0
END DESCRIPTION:
XS GIS Cut Line= 3
      3839687.27     10115163.77       3838907.6      10114239.1
      3838204.59     10113611.64
#Sta/Elev= 30
  3790.5  192.56  3960.9  190.97  4316.6  185.09  4445.2  183.48  4459.5  182.09
  4657.3  182.78  4757.3   179.6  4785.9   176.8  4792.4  177.61  4848.5  174.17
  4892.5  172.13  4899.1  174.12  4919.9  174.48  4941.9  172.25  4956.2  173.07
  4970.5  171.85    4984  168.42  5007.8  168.42    5013   169.5 5018.43 173.179
  5033.9  171.61  5054.8   177.1  5097.4  177.03  5104.9  178.35  5196.9  175.71
  5260.4  177.62    5341  176.41  5374.1  175.82  5590.5  181.78  5942.3  192.08
#Mann= 8 ,-1 , 0
  3790.5     .12       0  3960.9     .05       0  4316.6     .12       0
  4848.5      .1       0  4956.2     .07       0 5018.43      .1       0
    5341     .12       0  5590.5     .05       0
Bank Sta=4956.2,5018.43
XS Rating Curve= 0 ,0
Exp/Cntr=0.3,0.1

Type RM Length L Ch R = 1 ,40000   ,485,485,485
BEGIN DESCRIPTION:
STEWARTS CREEK 78.0
END DESCRIPTION:
XS GIS Cut Line= 3
      3839833.08     10115045.68      3839258.29     10114049.86
      3838298.39     10113469.32
#Sta/Elev= 30
  3850.2  191.03    4129  187.14  4509.3  184.76  4628.4  181.03  4750.6  176.94
  4809.5   176.6    4831     179  4846.8  176.72  4940.9  175.71  4948.8  174.44
  4954.5  169.74  4970.3  170.95  4984.5  165.66  5008.3  165.66  5012.7  171.14
  5022.3  173.67  5086.4  175.94  5165.9  176.89  5233.8  170.82    5261   176.6
  5304.4  176.69  5327.7  172.57  5377.4  173.19  5392.9  175.64  5451.1  173.45
  5515.1  180.12  5547.9  181.15  5683.9  179.08  5874.2  181.27  6121.8  191.65
#Mann= 7 ,-1 , 0
  3850.2     .05       0    4129     .12       0  4628.4      .1       0
  4940.9     .07       0  5086.4      .1       0  5547.9     .12       0
  5874.2     .05       0
Bank Sta=4940.9,5086.4
XS Rating Curve= 0 ,0
Exp/Cntr=0.3,0.1

Type RM Length L Ch R = 1 ,39515   ,457,457,457
BEGIN DESCRIPTION:
STEWARTS CREEK 77.0
END DESCRIPTION:
XS GIS Cut Line= 3
      3840433.76     10114471.02      3839531.14      10113679.4
      3838304.92      10113313.6
#Sta/Elev= 30
  3797.4  190.72  3801.8  193.19  3808.4  191.45    3816  193.69  3851.1  190.97
  3865.3  187.56  3957.8  185.83  4453.7  179.66  4552.4  172.49  4595.1  172.27
  4623.6  176.48  4686.9  177.42    4829   178.2  4928.2   174.9 4945.51 172.208
  4963.3  169.97  4965.6  166.68  4989.5  166.68  4991.8  169.19  5008.1  168.32
  5046.5  172.38  5112.8  168.53  5184.3  175.96  5422.4  178.11  5569.7  181.25
  5679.7  178.24  5825.8   177.9  6018.1  181.55  6165.1  187.38  6277.6   193.1
#Mann= 9 ,-1 , 0
  3797.4     .12       0  3957.8      .1       0  4686.9     .12       0
    4829      .1       0 4945.51     .07       0  5046.5      .1       0
  5422.4     .12       0  6018.1     .05       0  6165.1    .075       0
Bank Sta=4945.51,5046.5
XS Rating Curve= 0 ,0
Exp/Cntr=0.3,0.1

Type RM Length L Ch R = 1 ,39058   ,402,402,402
BEGIN DESCRIPTION:
STEWARTS CREEK 76.0
END DESCRIPTION:
XS GIS Cut Line= 3
      3840471.97     10113660.27      3839708.06     10113306.61
      3838582.89     10112836.07
#Sta/Elev= 30
  4158.2   188.3  4288.3  186.31  4354.3  183.52  4493.3  179.21  4568.9  178.93
  4574.4  176.94  4591.8  178.71  4658.6  177.47  4666.7  175.69  4814.6  172.71
  4967.2  173.89  4989.2  171.46  5009.9  164.22    5034  164.22  5043.6   171.2
  5051.1  173.94  5056.5     173  5080.3  176.43  5127.9  176.04  5157.2  177.69
  5204.8   175.7  5308.8  177.25  5327.7  177.23  5579.1  177.69  5647.3  177.46
  5676.5  179.39  5748.8  177.86  5854.1  177.74  6139.9  186.99  6219.6  191.32
#Mann= 11 ,-1 , 0
  4158.2     .05       0  4354.3     .12       0  4666.7      .1       0
  4967.2     .07       0  5051.1      .1       0  5308.8      .1       0
  5327.7     .05       0  5579.1     .12       0  5748.8     .05       0
  5854.1     .12       0  6139.9     .05       0
Bank Sta=4967.2,5051.1
XS Rating Curve= 0 ,0
Exp/Cntr=0.3,0.1

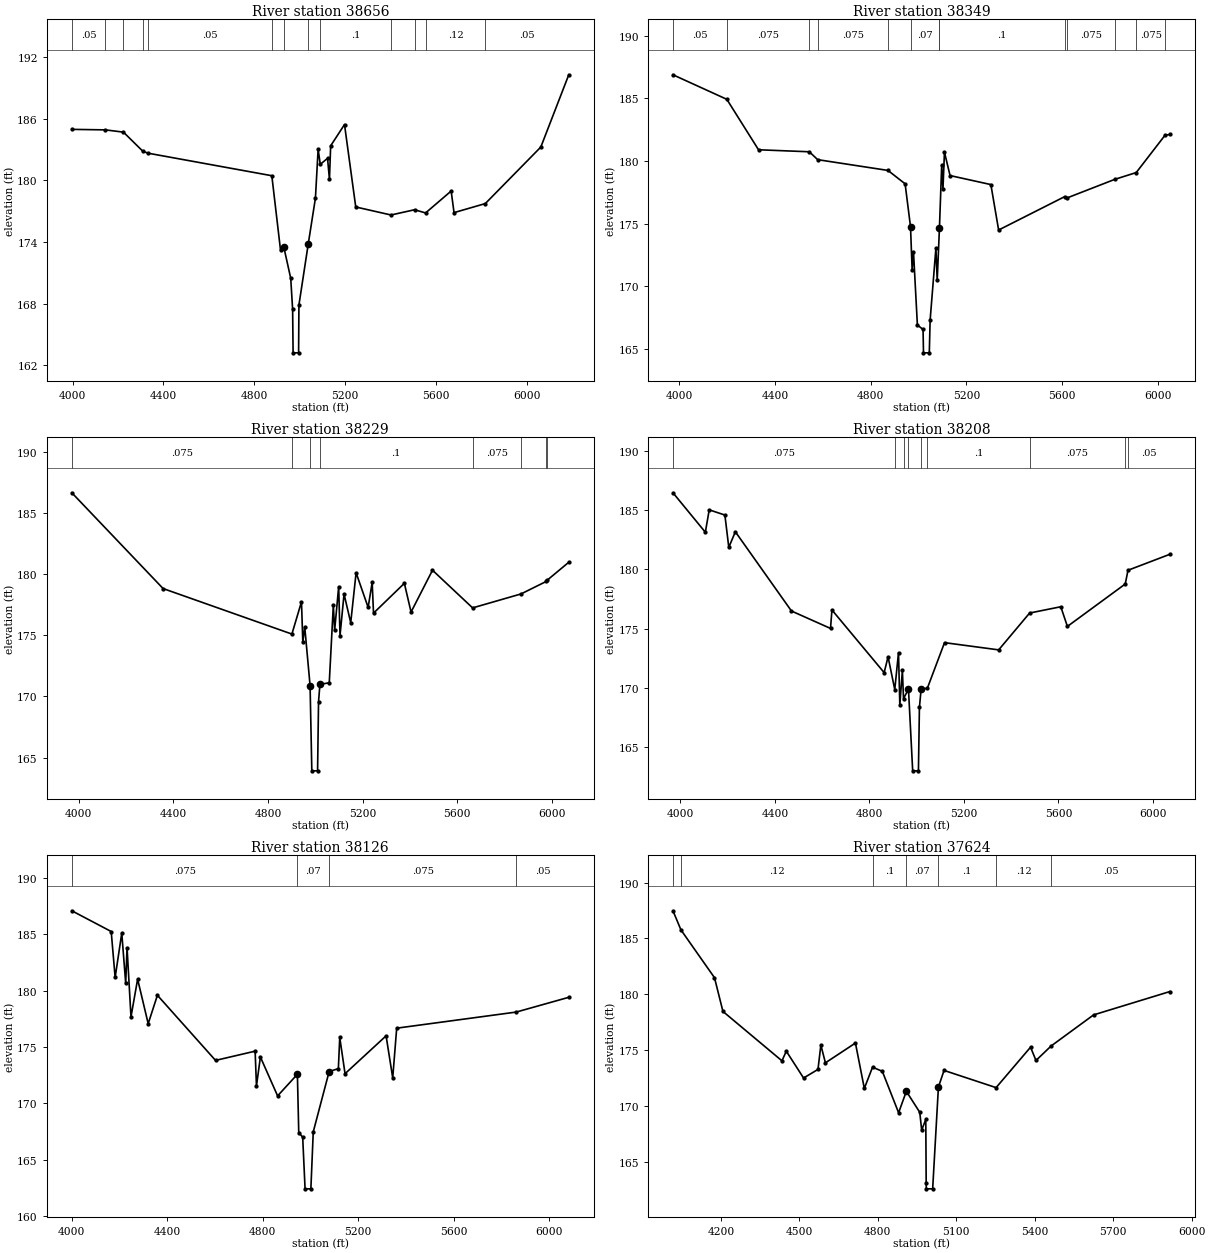
Type RM Length L Ch R = 1 ,38656   ,307,307,307
BEGIN DESCRIPTION:
STEWARTS CREEK 75.0
END DESCRIPTION:
XS GIS Cut Line= 3
      3840784.23      10113474.5      3839892.98      10113013.1
      3838782.55     10112597.96
#Sta/Elev= 30
  3996.4  184.96  4144.2  184.91  4223.7  184.69  4309.3  182.83  4332.6  182.64
  4877.4  180.45  4915.7  173.22  4930.4  173.49  4960.7  170.47  4969.1  167.44
  4971.1  163.22  4995.4  163.22  4996.8  167.87  5037.5  173.76  5069.5  178.27
  5081.4  183.03  5090.8  181.56  5122.9  182.14  5131.3  180.09  5136.6  183.36
  5197.6  185.43  5247.1  177.41  5402.4  176.63  5506.2  177.14  5554.8  176.83
  5667.4  178.96  5680.1  176.86  5817.8  177.74  6062.4  183.24  6185.5  190.27
#Mann= 13 ,-1 , 0
  3996.4     .05       0  4144.2      .1       0  4223.7     .05       0
  4309.3      .1       0  4332.6     .05       0  4877.4      .1       0
  4930.4     .07       0  5037.5    .075       0  5090.8      .1       0
  5402.4    .075       0  5506.2     .05       0  5554.8     .12       0
  5817.8     .05       0
Bank Sta=4930.4,5037.5
XS Rating Curve= 0 ,0
Exp/Cntr=0.3,0.1

Type RM Length L Ch R = 1 ,38349   ,120,120,120
BEGIN DESCRIPTION:
Mapping XS c63de7b3
END DESCRIPTION:
XS GIS Cut Line= 3
        3840904.     10113216.67      3839998.14     10112733.85
       3839023.8     10112341.68
#Sta/Elev= 30
  3973.5  186.88  4198.6  184.92  4331.1  180.89  4543.3  180.73  4578.3   180.1
  4872.1  179.24  4943.7  178.17  4966.3  174.74    4973  171.32  4978.7  172.75
    4995  166.89  5018.7  166.54  5020.5  164.67  5044.8  164.67  5048.2  167.27
  5072.4  173.03  5077.8  170.45  5087.2  174.65  5096.6  179.66  5101.9  177.78
  5108.1   180.7  5131.5  178.83  5302.1  178.11  5334.5  174.48  5610.9  177.15
  5618.8  177.03  5820.4  178.53  5909.6  179.07  6029.9  182.05  6050.3  182.11
#Mann= 13 ,-1 , 0
  3973.5     .05       0  4198.6    .075       0  4543.3     .05       0
  4578.3    .075       0  4872.1     .05       0  4966.3     .07       0
  5087.2    .075       0  5087.2      .1       0  5610.9     .05       0
  5618.8    .075       0  5820.4     .05       0  5909.6    .075       0
  6029.9     .05       0
Bank Sta=4966.3,5087.2
XS Rating Curve= 0 ,0
Exp/Cntr=0.3,0.1

Type RM Length L Ch R = 1 ,38229   ,21,21,21
BEGIN DESCRIPTION:
STEWARTS CREEK 74.0
END DESCRIPTION:
XS GIS Cut Line= 3
      3840940.48     10113096.89      3840028.18     10112620.47
      3839061.86     10112158.21
#Sta/Elev= 30
  3970.8  186.65  4356.6  178.82    4901   175.1  4941.5  177.74  4947.1  174.43
  4955.2  175.69  4977.8  170.89  4985.2  163.92  5009.5  163.92  5013.6  169.58
 5019.45 170.986  5058.9  171.12  5076.1  177.46  5081.6   175.4  5098.7  178.98
  5104.3  174.98  5121.4  178.37  5149.6  176.03  5172.3  180.11  5223.2  177.28
  5240.3  179.33  5245.9  176.81  5376.3  179.25  5404.6   176.9  5495.2  180.32
  5664.8  177.24  5869.3  178.38  5976.7  179.41    5981  179.52  6071.2  180.97
#Mann= 8 ,-1 , 0
  3970.8    .075       0    4901     .05       0  4977.8     .07       0
 5019.45      .1       0  5664.8    .075       0  5869.3      .1       0
  5976.7    .075       0    5981     .05       0
Bank Sta=4977.8,5019.45
XS Rating Curve= 0 ,0
Exp/Cntr=0.3,0.1

Type RM Length L Ch R = 1 ,38208   ,82,82,82
BEGIN DESCRIPTION:
STEWARTS CREEK 73.0
END DESCRIPTION:
XS GIS Cut Line= 3
      3840948.88       10113077.      3840034.66     10112600.59
      3839076.56     10112121.31
#Sta/Elev= 30
  3969.1  186.46  4106.1  183.13  4122.5  185.02  4188.8  184.58  4205.3  181.85
    4233  183.17  4470.4  176.48  4635.6  175.01  4641.6  176.57  4862.5  171.28
    4879  172.62  4907.4  169.85  4923.2  172.97  4928.8  168.55  4939.6  171.46
  4944.4  169.09 4965.41 169.882  4983.2  162.99  5007.5  162.99  5011.7  168.34
  5018.8  169.88  5045.2  169.96  5117.9  173.81    5347   173.2  5477.9  176.31
  5609.7  176.84  5637.7  175.18  5882.4  178.76    5894  179.92  6071.3  181.27
#Mann= 9 ,-1 , 0
  3969.1    .075       0  4907.4     .05       0  4944.4    .075       0
 4965.41     .07       0  5018.8    .075       0  5045.2      .1       0
  5477.9    .075       0  5882.4      .1       0    5894     .05       0
Bank Sta=4965.41,5018.8
XS Rating Curve= 0 ,0
Exp/Cntr=0.3,0.1

Type RM Length L Ch R = 1 ,38126   ,502,502,502
BEGIN DESCRIPTION:
Mapping XS 742eab2f
END DESCRIPTION:
XS GIS Cut Line= 3
      3840980.13     10113001.48      3840092.33     10112542.34
      3839128.64     10112048.39
#Sta/Elev= 30
  4000.5  187.09  4165.5  185.25    4182  181.17  4209.8  185.11  4226.3  180.64
  4231.9  183.82  4248.4  177.67  4276.2  181.02  4320.5  177.07  4359.1  179.59
  4602.7  173.81  4768.6  174.63  4774.2  171.55  4790.7  174.11  4862.8  170.66
  4945.7  172.58  4951.4  167.41  4967.9  166.99  4977.9  162.41  5002.2  162.41
  5012.2  167.47  5078.8  172.82  5117.4  173.08  5123.2  175.85  5145.4  172.63
  5317.4  175.99  5345.2  172.26  5361.8  176.67  5862.8   178.1  6082.9  179.41
#Mann= 4 ,-1 , 0
  4000.5    .075       0  4945.7     .07       0  5078.8    .075       0
  5862.8     .05       0
Bank Sta=4945.7,5078.8
XS Rating Curve= 0 ,0
Exp/Cntr=0.3,0.1

Type RM Length L Ch R = 1 ,37624   ,408,408,408
BEGIN DESCRIPTION:
Mapping XS f1a7888c
END DESCRIPTION:
XS GIS Cut Line= 3
      3840961.41     10112490.51      3840068.45     10112078.81
      3839183.53     10111839.14
#Sta/Elev= 30
  4016.7  187.48  4047.2  185.77  4175.5  181.49  4207.8  178.47  4433.4  174.05
  4450.1  174.91  4516.1  172.51  4571.2  173.28  4582.2  175.46  4599.6  173.87
  4714.4  175.64  4748.4  171.58  4779.8  173.48  4817.2  173.11  4879.5   169.4
    4909  171.32  4960.4  169.44  4967.6  167.85  4983.4   168.8  4984.9  163.09
  4985.4  162.59  5009.7  162.59  5031.7   171.7  5053.2  173.19  5252.2  171.65
    5384  175.27  5404.7  174.08  5462.8  175.38    5625  178.16  5916.8  180.25
#Mann= 7 ,-1 , 0
  4016.7     .05       0  4047.2     .12       0  4779.8      .1       0
    4909     .07       0  5031.7      .1       0  5252.2     .12       0
  5462.8     .05       0
Bank Sta=4909,5031.7
XS Rating Curve= 0 ,0
Exp/Cntr=0.3,0.1

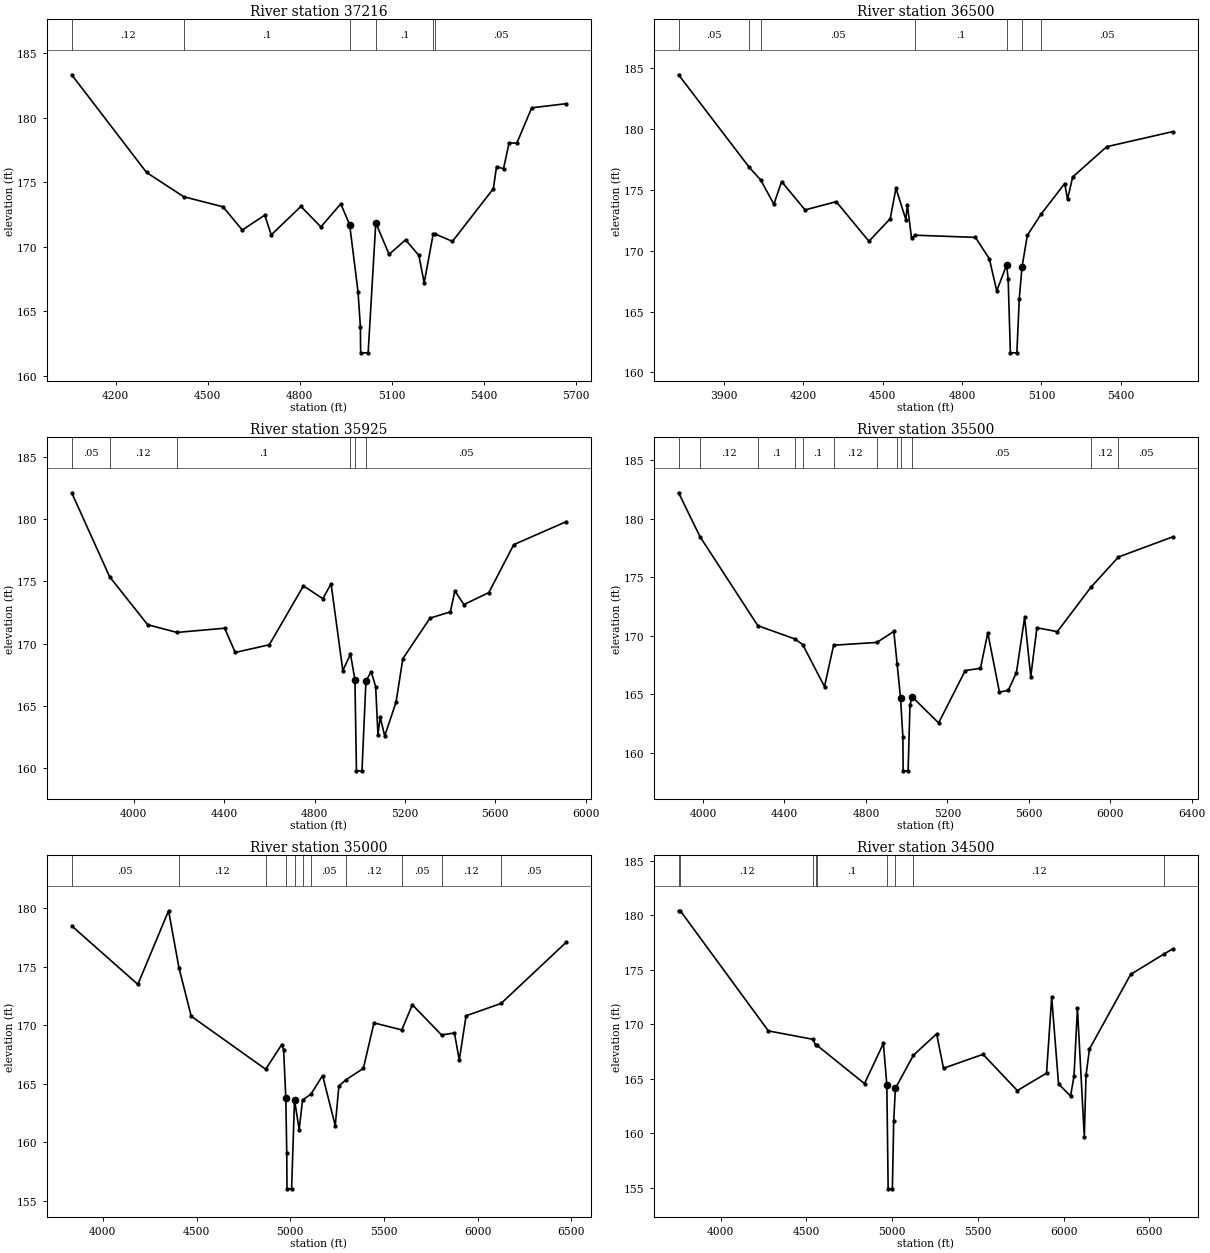
Type RM Length L Ch R = 1 ,37216   ,716,716,716
BEGIN DESCRIPTION:
STEWARTS CREEK 72.0
END DESCRIPTION:
XS GIS Cut Line= 3
      3840988.28     10111967.93      3840088.27     10111686.78
       3839436.2     10111540.85
#Sta/Elev= 30
  4057.1  183.32  4300.9  175.75    4422  173.87  4549.9  173.09  4612.8  171.29
  4686.1  172.44  4707.1  170.91  4803.9  173.12  4868.9  171.53  4933.8  173.32
 4962.67 171.695    4990  166.49  4997.6  163.79  4998.5  161.77  5022.9  161.77
  5047.8  171.85  5091.2   169.4  5144.8  170.53  5188.2  169.32  5205.4  167.19
    5235     171  5240.3  170.99  5297.6  170.41  5430.8  174.49  5441.1  176.19
  5463.9  176.04  5482.1  178.04  5507.3  178.02  5555.8  180.76  5668.2  181.08
#Mann= 6 ,-1 , 0
  4057.1     .12       0    4422      .1       0 4962.67     .07       0
  5047.8      .1       0    5235     .12       0  5240.3     .05       0
Bank Sta=4962.67,5047.8
XS Rating Curve= 0 ,0
Exp/Cntr=0.3,0.1

Type RM Length L Ch R = 1 ,36500   ,575,575,575
BEGIN DESCRIPTION:
STEWARTS CREEK 71.0
END DESCRIPTION:
XS GIS Cut Line= 3
      3841075.15     10111825.59      3839974.26     10111191.18
      3839381.78     10111113.91
#Sta/Elev= 30
  3729.4  184.48  3996.6  176.86  4039.8  175.82  4089.4  173.83  4118.7  175.69
  4207.2  173.36    4325  174.04  4448.5  170.78    4529  172.64  4550.6  175.14
  4587.9  172.57  4593.7  173.78  4609.4  171.05  4622.4  171.28  4850.8   171.1
  4903.5  169.33  4931.3   166.7  4968.6  168.83  4974.4  167.68  4982.9   161.6
  5007.3   161.6  5016.5  166.06  5026.6  168.63  5046.8  171.26  5098.5     173
    5188  175.53  5198.7  174.24  5218.2  176.07  5346.6  178.56  5597.5  179.81
#Mann= 7 ,-1 , 0
  3729.4     .05       0  3996.6     .12       0  4039.8     .05       0
  4622.4      .1       0  4968.6     .07       0  5026.6      .1       0
  5098.5     .05       0
Bank Sta=4968.6,5026.6
XS Rating Curve= 0 ,0
Exp/Cntr=0.3,0.1

Type RM Length L Ch R = 1 ,35925   ,425,425,425
BEGIN DESCRIPTION:
STEWARTS CREEK 70.0
END DESCRIPTION:
XS GIS Cut Line= 3
      3841505.68     10111367.25      3840338.41      10110854.3
      3839425.85     10110908.91
#Sta/Elev= 30
    3725  182.12    3893  175.37  4061.2  171.52  4190.7   170.9  4402.2  171.24
  4448.9  169.29  4599.9  169.91  4750.9  174.64  4836.8  173.61  4873.2  174.81
  4925.3  167.83  4959.1  169.16  4978.8  167.11  4985.6  159.78    5010  159.78
  5027.7     167  5050.7  167.74  5070.7  166.55  5080.7  162.67  5090.7  164.09
  5110.8  162.58  5160.9   165.3  5190.9  168.79  5311.1  172.05  5401.3  172.55
  5421.3  174.24  5461.4  173.14  5571.6   174.1  5681.8  177.95  5914.2   179.8
#Mann= 6 ,-1 , 0
    3725     .05       0    3893     .12       0  4190.7      .1       0
  4959.1     .05       0  4978.8     .07       0  5027.7     .05       0
Bank Sta=4978.8,5027.7
XS Rating Curve= 0 ,0
Exp/Cntr=0.3,0.1

Type RM Length L Ch R = 1 ,35500   ,500,500,500
BEGIN DESCRIPTION:
STEWARTS CREEK 69.0
END DESCRIPTION:
XS GIS Cut Line= 3
      3841519.58     10111092.95      3840564.08     10110508.25
      3839262.75     10110645.01
#Sta/Elev= 30
  3879.8  182.21  3985.3  178.46    4269  170.87  4451.7  169.73  4489.2  169.26
  4596.5  165.67  4641.2   169.2  4853.8  169.44    4937  170.38  4953.4  167.56
 4969.88 164.688  4981.5  161.38  4982.7  158.48  5007.1  158.48  5016.3  164.09
  5026.4   164.8  5157.1  162.57  5287.8  167.04  5362.5  167.23  5398.4  170.26
  5455.6   165.2    5499  165.35  5539.2  166.87  5579.4  171.57  5609.6  166.51
  5639.7  170.69  5739.9  170.36  5904.6  174.14  6040.2  176.73  6308.5  178.46
#Mann= 12 ,-1 , 0
  3879.8     .05       0  3985.3     .12       0    4269      .1       0
  4451.7     .12       0  4489.2      .1       0  4641.2     .12       0
  4853.8      .1       0  4953.4     .05       0 4969.88     .07       0
  5026.4     .05       0  5904.6     .12       0  6040.2     .05       0
Bank Sta=4969.88,5026.4
XS Rating Curve= 0 ,0
Exp/Cntr=0.3,0.1

Type RM Length L Ch R = 1 ,35000   ,500,500,500
BEGIN DESCRIPTION:
STEWARTS CREEK 68.0
END DESCRIPTION:
XS GIS Cut Line= 3
       3841731.4     10109915.85      3840572.71     10110048.01
      3839182.79      10110533.9
#Sta/Elev= 30
  3833.8  178.48  4186.7  173.48  4350.7  179.77    4406  174.91  4471.5  170.76
  4868.8  166.23  4954.6  168.34  4964.6   167.9 4976.23 163.731  4981.3  159.03
  4982.5  156.01  5007.1  156.01  5022.7  163.61  5047.5  161.07  5065.6   163.6
  5110.7  164.11  5172.6  165.69    5240  161.41  5259.4  164.79  5296.2  165.32
  5389.9   166.3  5446.7  170.19  5595.2  169.59  5651.3  171.74  5807.1  169.16
    5876  169.33  5901.8  167.01  5938.1   170.8  6124.8  171.85  6472.4  177.08
#Mann= 11 ,-1 , 0
  3833.8     .05       0    4406     .12       0  4868.8      .1       0
 4976.23     .07       0  5022.7      .1       0  5065.6     .12       0
  5110.7     .05       0  5296.2     .12       0  5595.2     .05       0
  5807.1     .12       0  6124.8     .05       0
Bank Sta=4976.23,5022.7
XS Rating Curve= 0 ,0
Exp/Cntr=0.3,0.1

Type RM Length L Ch R = 1 ,34500   ,500,500,500
BEGIN DESCRIPTION:
STEWARTS CREEK 67.0
END DESCRIPTION:
XS GIS Cut Line= 3
      3841720.92     10109648.49      3840476.55     10109579.13
      3838840.94     10109478.47
#Sta/Elev= 30
  3753.7  180.39  3763.9  180.41  4277.6  169.38  4537.3  168.61  4552.7  168.09
    4561  168.06  4838.4  164.54  4948.6  168.23  4968.6  164.44  4976.4  154.88
    5001  154.88  5008.7  161.09  5018.7  164.11  5123.9  167.15  5259.2  169.11
  5299.3  165.95  5529.7  167.23  5730.1   163.9  5900.4   165.5  5930.5  172.47
  5970.5  164.51  6040.7   163.4  6060.7  165.24  6080.7  171.45  6120.8  159.66
  6130.8  165.31  6150.9  167.72  6391.3  174.57  6587.7  176.46  6638.7  176.93
#Mann= 9 ,-1 , 0
  3753.7     .05       0  3763.9     .12       0  4537.3      .1       0
  4552.7     .12       0    4561      .1       0  4968.6     .07       0
  5018.7      .1       0  5123.9     .12       0  6587.7     .05       0
Bank Sta=4968.6,5018.7
XS Rating Curve= 0 ,0
Exp/Cntr=0.3,0.1

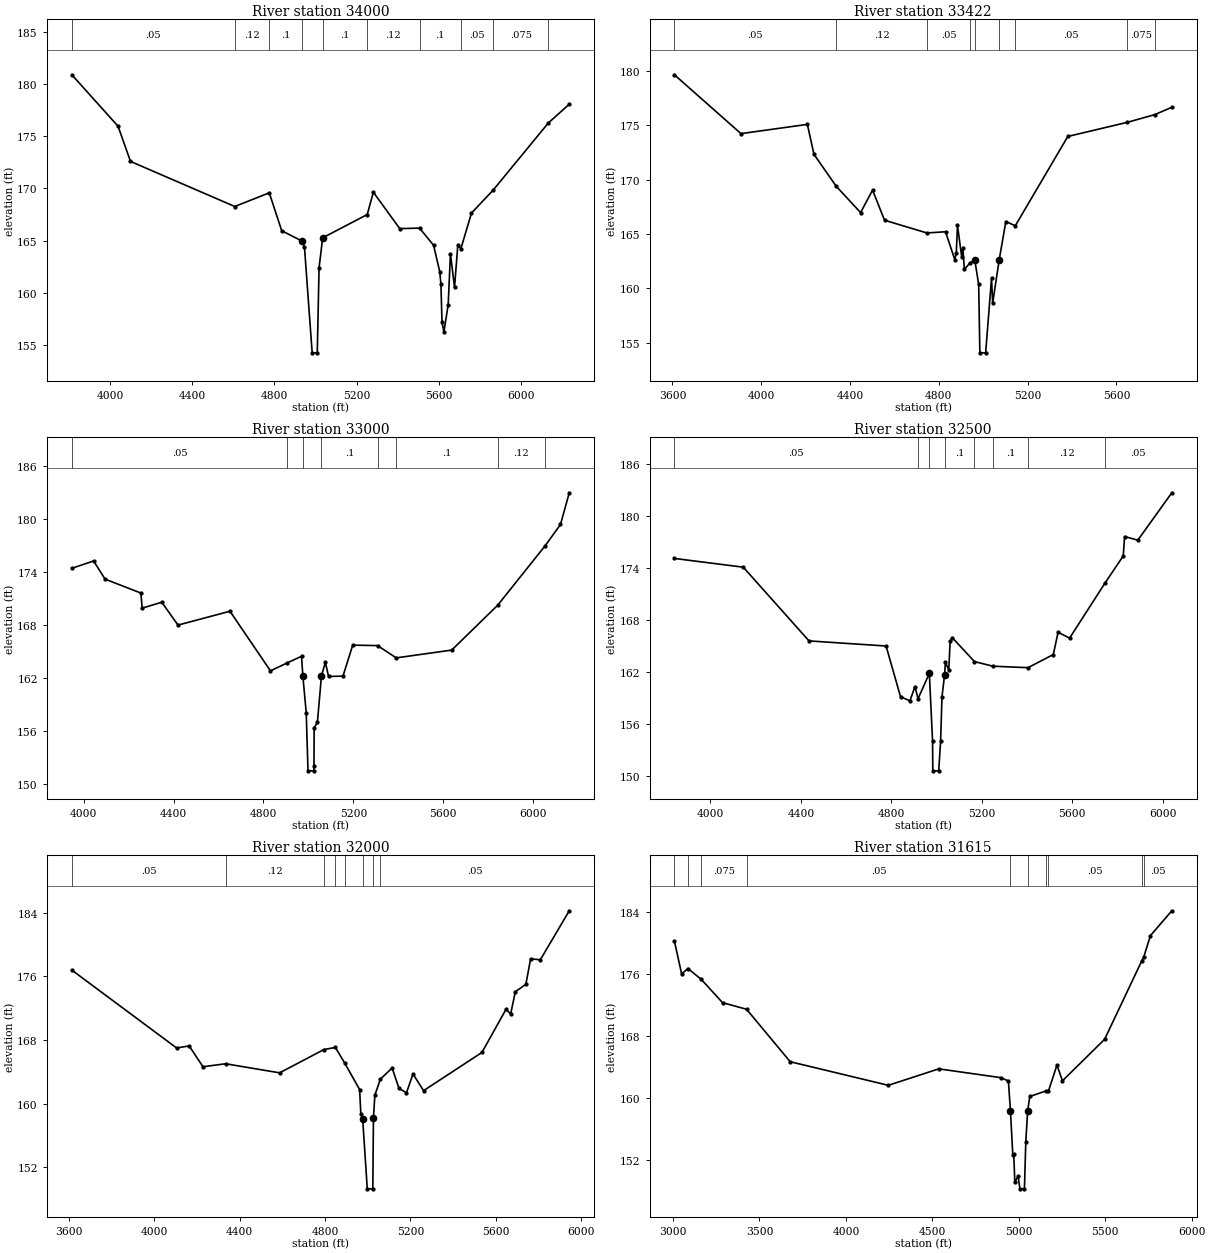
Type RM Length L Ch R = 1 ,34000   ,578,578,578
BEGIN DESCRIPTION:
STEWARTS CREEK 66.0
END DESCRIPTION:
XS GIS Cut Line= 3
      3841720.94     10109412.38      3840544.61     10109255.04
      3839345.92     10108954.04
#Sta/Elev= 30
  3813.2  180.89  4038.3  175.96  4098.8  172.59  4606.7  168.27  4774.8  169.58
  4835.3  165.95  4936.2  164.94  4946.3  164.36  4983.7  154.25  5008.5  154.25
  5017.3  162.39  5034.8  165.27  5251.9   167.5  5281.7  169.64  5410.3  166.15
  5506.6   166.2  5574.9  164.56    5605  162.04  5610.9  160.81  5616.1  157.17
  5625.6  156.27  5646.2  158.87  5657.2  163.75  5677.1  160.52  5693.2   164.6
  5708.2  164.24  5759.6  167.64  5865.6  169.85  6133.8  176.27  6235.9  178.07
#Mann= 10 ,-1 , 0
  3813.2     .05       0  4606.7     .12       0  4774.8      .1       0
  4936.2     .07       0  5034.8      .1       0  5251.9     .12       0
  5506.6      .1       0  5708.2     .05       0  5865.6    .075       0
  6133.8     .05       0
Bank Sta=4936.2,5034.8
XS Rating Curve= 0 ,0
Exp/Cntr=0.3,0.1

Type RM Length L Ch R = 1 ,33422   ,422,422,422
BEGIN DESCRIPTION:
STEWARTS CREEK 65.0
END DESCRIPTION:
XS GIS Cut Line= 3
      3841720.98     10109287.39      3840428.69     10108771.66
      3839588.13     10108648.09
#Sta/Elev= 30
  3608.6  179.64  3908.5  174.23  4207.6  175.08  4237.3  172.33  4337.3   169.4
  4447.5  166.97  4501.4  169.04  4555.3  166.27  4746.2   165.1  4830.1  165.21
  4871.7  162.65  4878.6  163.26    4884  165.79  4902.9  162.91  4908.3  163.76
  4914.8  161.75  4941.7  162.37  4962.2  162.58  4979.4  160.37  4984.8  154.08
  5010.8  154.08  5037.3  160.93  5042.4  158.64  5071.6   162.6  5101.9  166.15
  5144.4  165.76    5381  173.97  5649.3  175.27  5773.2  175.98  5849.6  176.65
#Mann= 9 ,-1 , 0
  3608.6     .05       0  4337.3     .12       0  4746.2     .05       0
  4941.7      .1       0  4962.2     .07       0  5071.6      .1       0
  5144.4     .05       0  5649.3    .075       0  5773.2     .05       0
Bank Sta=4962.2,5071.6
XS Rating Curve= 0 ,0
Exp/Cntr=0.3,0.1

Type RM Length L Ch R = 1 ,33000   ,500,500,500
BEGIN DESCRIPTION:
STEWARTS CREEK 64.0
END DESCRIPTION:
XS GIS Cut Line= 3
      3841498.04     10109036.75      3840623.31     10108451.78
      3839714.19     10107730.33
#Sta/Elev= 30
  3947.7  174.43  4044.5  175.26  4095.6   173.2  4254.7  171.63  4260.7  169.92
  4347.8  170.59  4419.9     168  4651.1  169.57  4831.3  162.82  4905.8  163.72
  4969.4  164.47  4975.4  162.24  4990.4  158.08  4998.3   151.5  5024.3   151.5
  5024.8     152  5025.7  156.39  5040.1  156.98 5058.11 162.247  5075.4  163.79
  5089.8  162.19  5153.9  162.22  5197.2  165.73  5307.6  165.68  5390.9  164.29
  5637.7  165.17  5841.8  170.24  6052.4  176.95  6121.6  179.39  6160.6  182.98
#Mann= 8 ,-1 , 0
  3947.7     .05       0  4905.8      .1       0  4975.4     .07       0
 5058.11      .1       0  5307.6     .12       0  5390.9      .1       0
  5841.8     .12       0  6052.4     .05       0
Bank Sta=4975.4,5058.11
XS Rating Curve= 0 ,0
Exp/Cntr=0.3,0.1

Type RM Length L Ch R = 1 ,32500   ,500,500,500
BEGIN DESCRIPTION:
STEWARTS CREEK 63.0
END DESCRIPTION:
XS GIS Cut Line= 3
      3841701.97     10108845.73      3840817.55     10108096.21
      3839952.87     10107517.63
#Sta/Elev= 30
  3840.7  175.07  4145.3  174.06    4436  165.55  4776.8  164.96  4840.6  159.11
  4882.3  158.63  4904.4  160.27  4918.2  158.88  4968.1   161.8  4982.3  154.01
  4983.5  150.55  5009.5  150.55    5018  153.99    5024   159.1 5035.61 161.652
    5039  163.11    5054  162.17    5060  165.51    5069  165.94  5167.7  163.16
  5249.4  162.63  5404.4  162.46  5516.4  163.98  5537.4  166.55  5588.4  165.87
  5744.4  172.21  5825.6  175.36  5831.6   177.6    5890  177.18  6040.4  182.65
#Mann= 8 ,-1 , 0
  3840.7     .05       0  4918.2      .1       0  4968.1     .07       0
 5035.61      .1       0  5167.7     .12       0  5249.4      .1       0
  5404.4     .12       0  5744.4     .05       0
Bank Sta=4968.1,5035.61
XS Rating Curve= 0 ,0
Exp/Cntr=0.3,0.1

Type RM Length L Ch R = 1 ,32000   ,385,385,385
BEGIN DESCRIPTION:
STEWARTS CREEK 62.0
END DESCRIPTION:
XS GIS Cut Line= 3
      3842096.76     10108462.04      3840897.33     10107768.72
      3840068.97      10107316.2
#Sta/Elev= 30
  3614.6  176.77  4105.2     167    4164  167.26  4228.6  164.64  4334.3  165.02
  4587.5  163.88  4794.8   166.8  4848.7  167.07  4891.8  165.13  4962.2  161.78
  4967.9  158.72  4976.3  158.14    4998  149.32    5024  149.32  5026.9 158.182
  5033.6  161.09  5059.6  163.09  5114.4  164.49  5146.7  161.92  5181.7  161.38
  5212.2  163.74  5261.5  161.64    5535  166.44  5647.7  171.85  5669.5  171.27
  5691.3  174.06  5740.7  174.99  5762.9  178.19  5808.4  178.07  5943.9  184.22
#Mann= 8 ,-1 , 0
  3614.6     .05       0  4334.3     .12       0  4794.8      .1       0
  4848.7     .12       0  4891.8      .1       0  4976.3     .07       0
  5026.9      .1       0  5059.6     .05       0
Bank Sta=4976.3,5026.9
XS Rating Curve= 0 ,0
Exp/Cntr=0.3,0.1

Type RM Length L Ch R = 1 ,31615   ,125,125,125
BEGIN DESCRIPTION:
Mapping XS 66d0620b
END DESCRIPTION:
XS GIS Cut Line= 3
      3842868.44     10107958.58      3841036.89     10107511.54
      3840101.14     10107182.29
#Sta/Elev= 30
    3008  180.26  3049.8  176.03  3086.3  176.73  3163.4  175.33  3286.5  172.33
  3425.3  171.48  3677.7  164.72  4245.3  161.68    4537   163.8  4895.5  162.67
    4940  162.24  4951.9 158.372  4965.6  152.66  4970.9  152.84  4977.1   149.2
  4996.6  149.97  5006.4  148.34  5032.7  148.34  5040.7  154.42  5051.3  158.38
  5063.8  160.24  5155.3  160.94  5171.8  160.94  5220.9  164.29  5252.7  162.26
  5496.6  167.61  5711.8  177.73  5722.2  178.16  5761.6  180.97  5885.3  184.17
#Mann= 10 ,-1 , 0
    3008    .075       0  3086.3      .1       0  3163.4    .075       0
  3425.3     .05       0  4951.9     .07       0  5051.3     .05       0
  5155.3      .1       0  5171.8     .05       0  5711.8    .075       0
  5722.2     .05       0
Bank Sta=4951.9,5051.3
XS Rating Curve= 0 ,0
Exp/Cntr=0.3,0.1