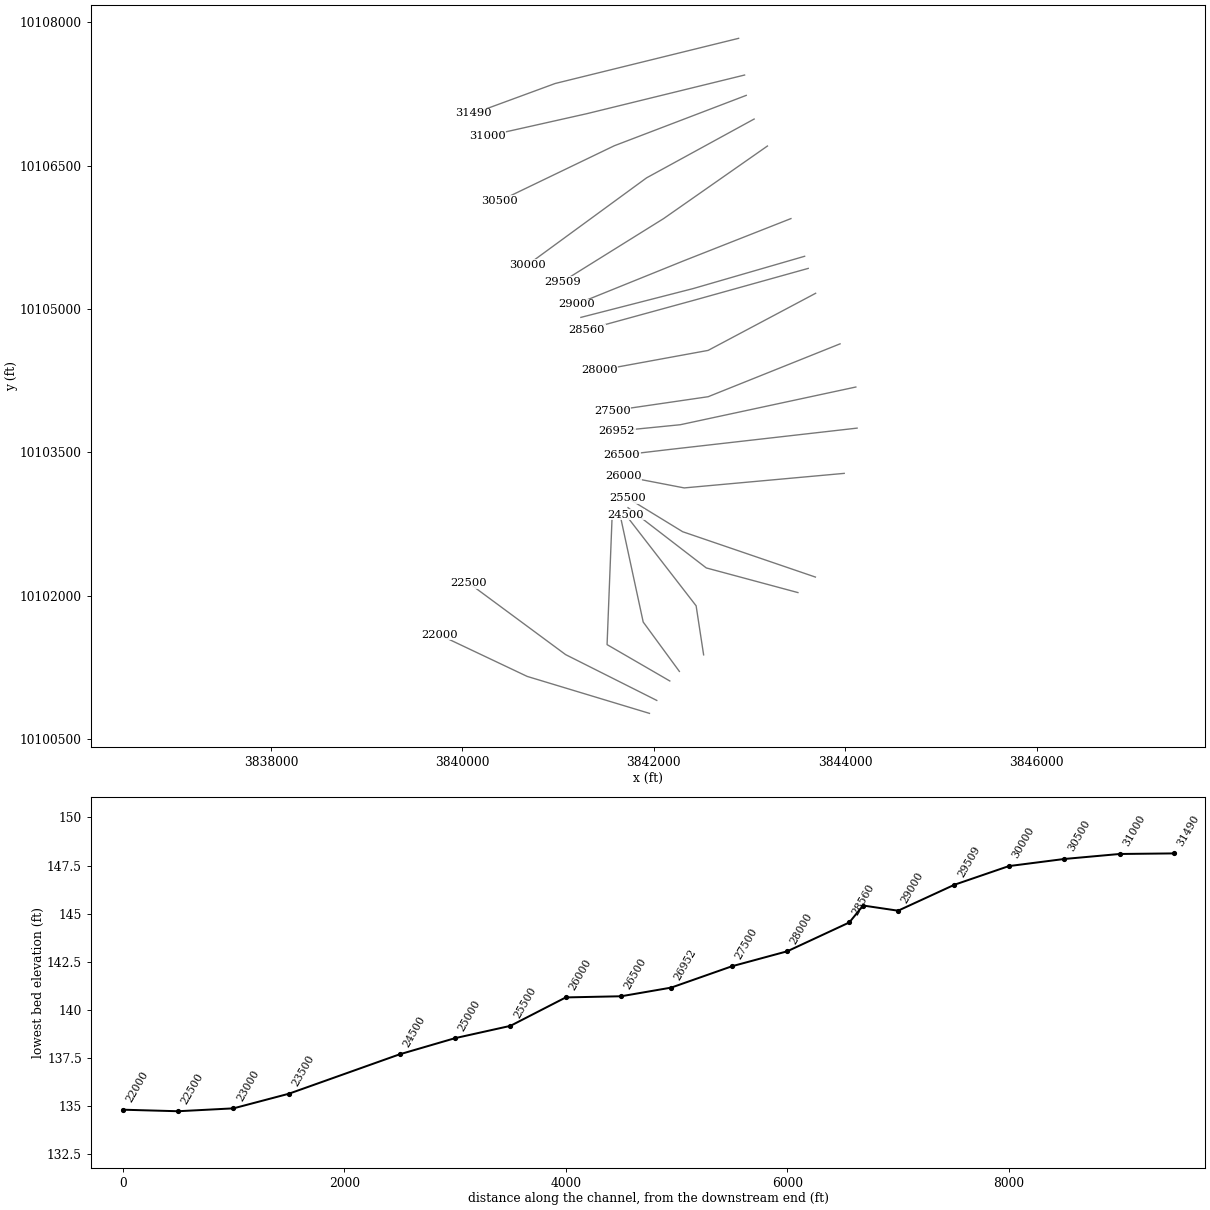
HEC-RAS study STEWARTS CREEK.prj: STEWARTS CREEK Base Level Engineering

--- STEWARTS CREEK.g10 (geometry) --- (continued)

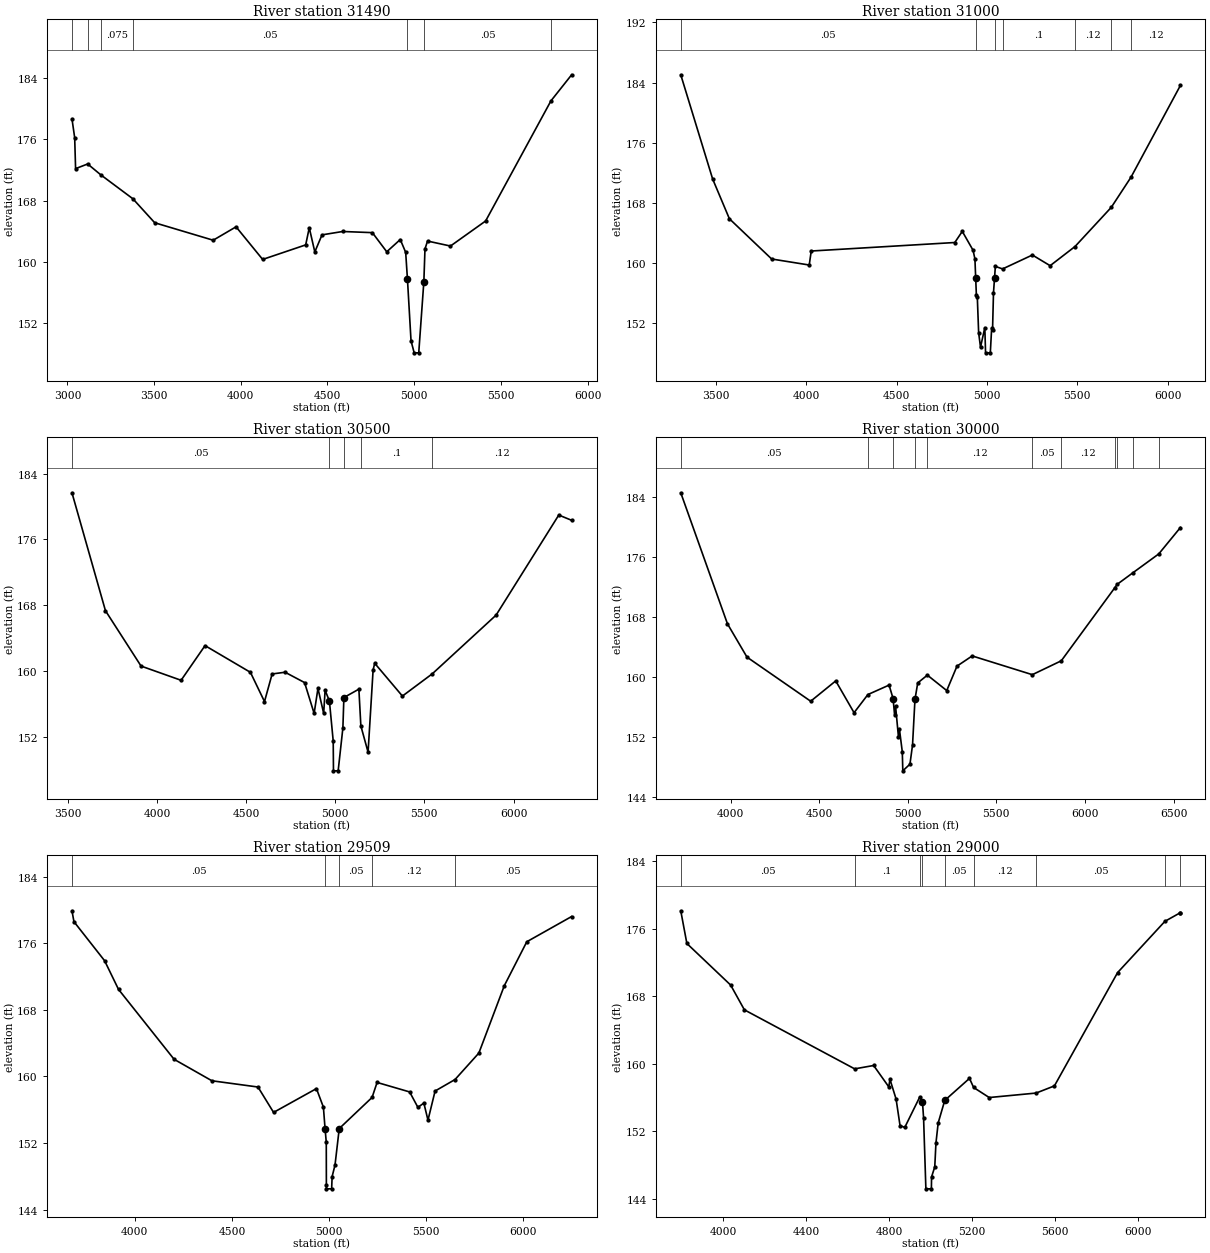
Type RM Length L Ch R = 1 ,31490   ,490,490,490
BEGIN DESCRIPTION:
STEWARTS CREEK 61.0
END DESCRIPTION:
XS GIS Cut Line= 3
      3842886.91     10107830.13      3840970.39     10107358.05
      3840117.81     10107044.54
#Sta/Elev= 30
  3026.2   178.7  3041.9  176.23  3047.1  172.19  3116.7   172.8  3192.5  171.38
  3377.8  168.25  3503.6  165.12  3840.8  162.84  3972.7  164.59  4126.2  160.33
  4374.4  162.23    4395  164.47    4427  161.31  4468.5  163.54  4587.8  163.98
    4759  163.83    4842  161.33  4919.9  162.93  4951.1  161.26  4961.4  157.74
    4982   149.7  5000.2  148.13  5026.5  148.13    5056  157.44  5062.5  161.71
  5077.3  162.73  5209.5  162.08  5412.2  165.35    5789  181.04  5908.4  184.45
#Mann= 7 ,-1 , 0
  3026.2    .075       0  3116.7     .05       0  3192.5    .075       0
  3377.8     .05       0  4961.4     .07       0    5056     .05       0
    5789    .075       0
Bank Sta=4961.4,5056
XS Rating Curve= 0 ,0
Exp/Cntr=0.3,0.1

Type RM Length L Ch R = 1 ,31000   ,500,500,500
BEGIN DESCRIPTION:
STEWARTS CREEK 60.0
END DESCRIPTION:
XS GIS Cut Line= 3
      3842949.23     10107446.44      3841303.58     10107042.93
      3840258.26     10106808.42
#Sta/Elev= 30
  3305.6  185.05  3482.1   171.2  3574.7  165.92  3808.7  160.57  4016.7  159.77
  4027.8  161.63  4822.3  162.76  4863.9  164.24  4923.5  161.73  4933.8  160.58
 4938.13 157.982  4941.9  155.72    4947  155.52  4954.4  150.77  4964.7  148.85
  4988.6  151.45  4992.7   148.1    5019   148.1  5026.3  151.34  5031.4   151.2
  5036.6  156.09 5042.35 158.044  5046.9  159.59  5086.9  159.25  5251.8   161.1
  5350.1  159.68  5487.9  162.23  5688.4  167.43  5797.7  171.44  6071.3  183.64
#Mann= 7 ,-1 , 0
  3305.6     .05       0 4938.13     .07       0 5042.35     .05       0
  5086.9      .1       0  5487.9     .12       0  5688.4     .05       0
  5797.7     .12       0
Bank Sta=4938.13,5042.35
XS Rating Curve= 0 ,0
Exp/Cntr=0.3,0.1

Type RM Length L Ch R = 1 ,30500   ,500,500,500
BEGIN DESCRIPTION:
STEWARTS CREEK 59.0
END DESCRIPTION:
XS GIS Cut Line= 3
      3842966.54     10107233.75      3841587.39     10106706.78
      3840392.86     10106131.36
#Sta/Elev= 30
  3523.6  181.68  3711.4  167.33  3911.1  160.59  4135.6  158.86  4269.9  163.08
  4524.4  159.83  4603.4  156.27  4646.2  159.63  4718.8  159.84  4828.2  158.58
  4881.7  154.83  4903.2  157.87  4935.3  154.83  4943.3  157.65  4967.4  156.34
  4988.8  151.46  4990.2  147.84  5016.5  147.84    5043  153.06  5048.6  156.76
  5132.7  157.78  5143.8  153.31  5184.3  150.11  5212.5  160.12  5221.5  160.93
  5376.9  156.94  5544.5  159.65  5902.2  166.79  6253.8  178.97  6325.9  178.33
#Mann= 5 ,-1 , 0
  3523.6     .05       0  4967.4     .07       0  5048.6     .05       0
  5143.8      .1       0  5544.5     .12       0
Bank Sta=4967.4,5048.6
XS Rating Curve= 0 ,0
Exp/Cntr=0.3,0.1

Type RM Length L Ch R = 1 ,30000   ,491,491,491
BEGIN DESCRIPTION:
STEWARTS CREEK 58.0
END DESCRIPTION:
XS GIS Cut Line= 3
      3843049.04     10106986.36      3841925.53     10106371.63
      3840683.57     10105462.91
#Sta/Elev= 30
  3719.3  184.54  3982.8  167.07    4093  162.63  4452.5  156.75  4593.8  159.46
  4697.2  155.22  4775.3  157.64  4894.8   158.9  4917.6  157.09  4925.7  154.97
  4931.4  156.11  4947.6  152.02  4953.3  153.01  4969.4  150.01  4972.3  147.47
  5012.6  148.36  5027.2  150.92 5040.92 156.995  5056.5  159.19  5110.9  160.23
  5220.2  158.17  5278.1  161.43  5363.8  162.79  5703.1  160.29  5866.6  162.14
  6169.5  171.91  6181.2  172.32  6271.5  173.89  6416.7  176.39  6538.9  179.91
#Mann= 11 ,-1 , 0
  3719.3     .05       0  4775.3      .1       0  4917.6     .07       0
 5040.92      .1       0  5110.9     .12       0  5703.1     .05       0
  5866.6     .12       0  6169.5    .075       0  6181.2     .12       0
  6271.5    .075       0  6416.7     .05       0
Bank Sta=4917.6,5040.92
XS Rating Curve= 0 ,0
Exp/Cntr=0.3,0.1

Type RM Length L Ch R = 1 ,29509   ,509,509,509
BEGIN DESCRIPTION:
STEWARTS CREEK 57.0
END DESCRIPTION:
XS GIS Cut Line= 3
      3843187.91     10106704.23      3842103.67     10105945.75
      3841044.73     10105285.53
#Sta/Elev= 30
  3676.8   179.9    3687  178.59  3844.8   173.9  3916.3  170.46  4202.3  162.06
  4396.9  159.48    4634  158.73  4714.2  155.68  4934.8  158.54  4970.6  156.31
  4979.3  153.69  4985.4   152.1  4985.9     147  4986.4   146.5    5013   146.5
  5015.5  147.97  5030.4  149.37  5052.1  153.74  5221.1  157.48  5246.8  159.28
  5414.3  158.14  5456.8  156.29  5487.5   156.8  5508.7  154.75  5545.3  158.25
  5647.9  159.63  5770.6  162.81  5901.6  170.91  6017.2  176.18  6247.9  179.21
#Mann= 5 ,-1 , 0
  3676.8     .05       0  4979.3     .07       0  5052.1     .05       0
  5221.1     .12       0  5647.9     .05       0
Bank Sta=4979.3,5052.1
XS Rating Curve= 0 ,0
Exp/Cntr=0.3,0.1

Type RM Length L Ch R = 1 ,29000   ,316,316,316
BEGIN DESCRIPTION:
STEWARTS CREEK 56.0
END DESCRIPTION:
XS GIS Cut Line= 3
       3843433.6     10105945.57      3842312.24     10105503.65
        3841194.     10105051.47
#Sta/Elev= 30
  3794.7  178.13  3824.2  174.25  4035.4  169.32  4101.8  166.38    4634  159.38
  4725.6  159.78  4798.8  157.24  4804.2  158.15  4833.9   155.8  4852.9  152.66
  4875.7  152.43  4947.4  156.01  4961.2  155.49  4966.6  153.55  4977.7  145.15
  5004.3  145.15  5005.1  146.56  5020.6  147.76  5026.3  150.59  5037.1  152.97
  5068.8  155.64  5188.1  158.25  5208.1  157.17  5283.4  155.98  5509.7  156.51
    5598  157.36    5903   170.8  6131.4  176.88  6204.9  177.89  6206.2  177.89
#Mann= 9 ,-1 , 0
  3794.7     .05       0    4634      .1       0  4947.4     .05       0
  4961.2     .07       0  5068.8     .05       0  5208.1     .12       0
  5509.7     .05       0  6131.4      .1       0  6204.9    .075       0
Bank Sta=4961.2,5068.8
XS Rating Curve= 0 ,0
Exp/Cntr=0.3,0.1

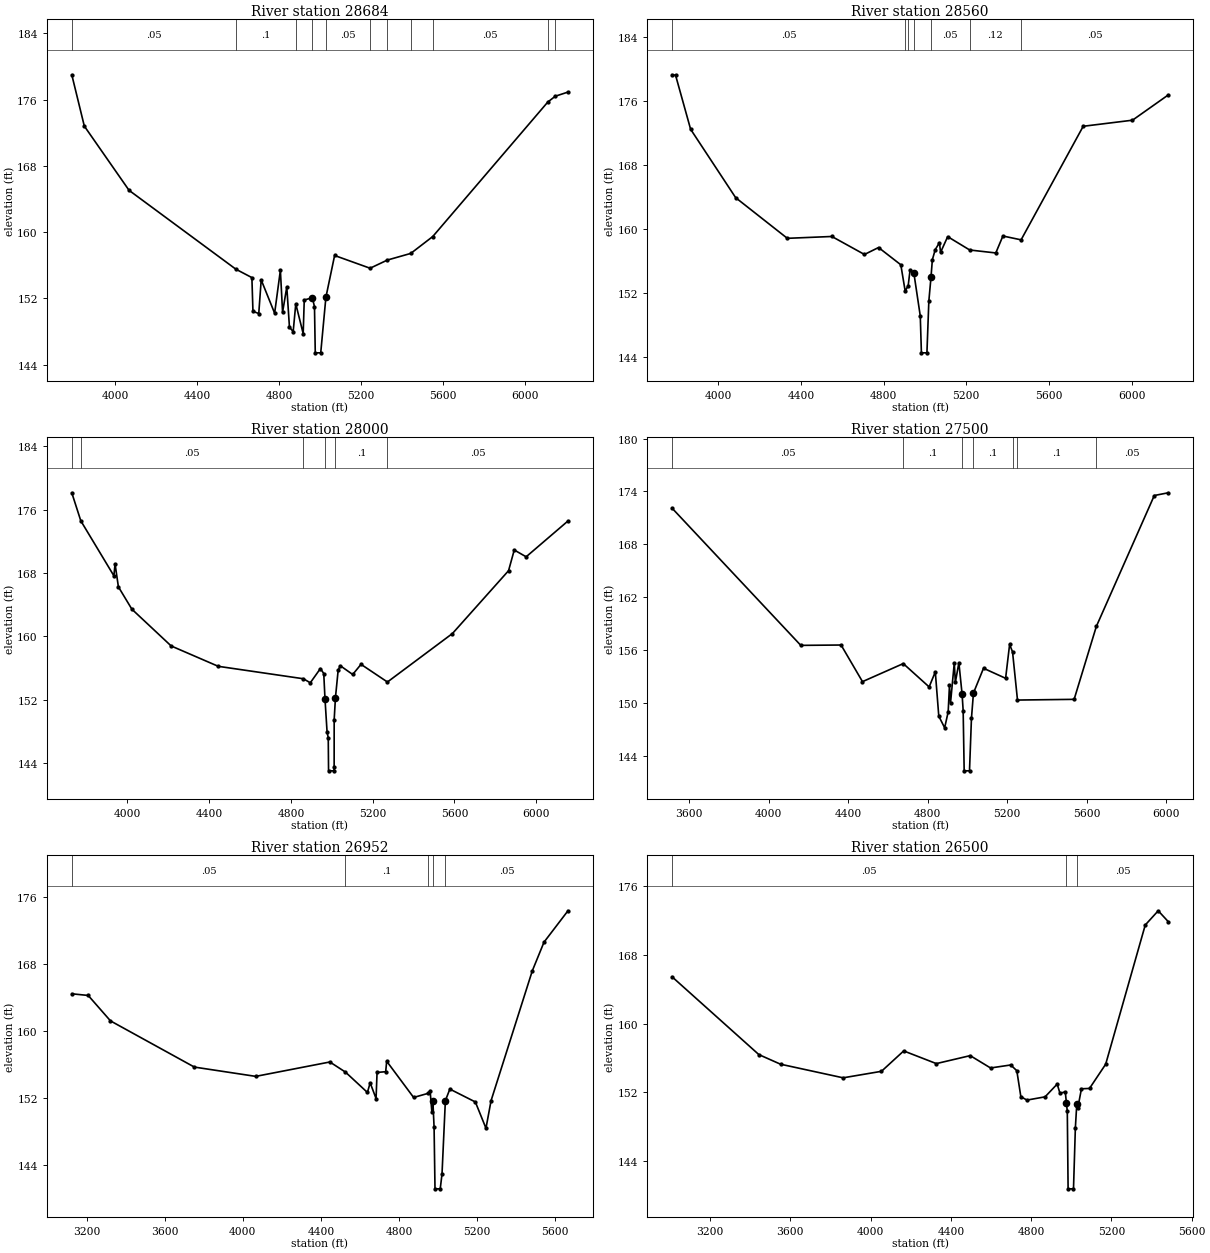
Type RM Length L Ch R = 1 ,28684   ,124,124,124
BEGIN DESCRIPTION:
Mapping XS 3c21ce2f
END DESCRIPTION:
XS GIS Cut Line= 3
      3843576.58      10105551.4      3842412.32     10105213.88
      3841238.69     10104912.54
#Sta/Elev= 30
  3787.8  179.01    3849  172.81  4067.6  165.05  4589.6  155.52  4667.6  154.51
  4672.8  150.43  4701.2  150.17  4713.1  154.23  4778.7  150.21  4806.8   155.4
  4817.5  150.32  4838.1  153.38  4851.1  148.52  4869.3  147.98    4882  151.34
  4918.2  147.74  4923.4   151.8    4963  152.08  4973.4  150.99  4977.2  145.42
  5003.9  145.42 5029.16 152.133  5071.7  157.18    5245  155.64  5329.6  156.63
  5443.7  157.43  5551.2  159.47  6113.3  175.72  6149.8  176.42  6211.7  176.92
#Mann= 11 ,-1 , 0
  3787.8     .05       0  4589.6      .1       0    4882     .05       0
    4963     .07       0 5029.16     .05       0    5245     .12       0
  5329.6     .05       0  5443.7     .12       0  5551.2     .05       0
  6113.3      .1       0  6149.8    .075       0
Bank Sta=4963,5029.16
XS Rating Curve= 0 ,0
Exp/Cntr=0.3,0.1

Type RM Length L Ch R = 1 ,28560   ,560,560,560
BEGIN DESCRIPTION:
STEWARTS CREEK 55.0
END DESCRIPTION:
XS GIS Cut Line= 3
      3843614.14     10105424.67      3842436.04     10105095.95
      3841300.96     10104784.63
#Sta/Elev= 30
  3776.9  179.31  3793.8  179.25  3866.5   172.5  4084.5  163.94  4334.3  158.86
  4549.8  159.09  4707.4  156.84  4775.6  157.71  4883.3  155.55  4904.4  152.26
    4919  152.95  4927.9  154.87  4946.2  154.56  4977.4  149.15  4982.9  144.54
  5009.6  144.54  5018.9  151.02  5029.2  153.98  5035.9  156.19    5050  157.46
  5070.3  158.32  5075.5   157.1    5110  159.07  5216.5   157.4  5342.7  157.03
  5377.1  159.15  5465.1  158.67  5765.5  172.87  6003.9  173.63    6177  176.79
#Mann= 7 ,-1 , 0
  3776.9     .05       0  4904.4      .1       0    4919     .05       0
  4946.2     .07       0  5029.2     .05       0  5216.5     .12       0
  5465.1     .05       0
Bank Sta=4946.2,5029.2
XS Rating Curve= 0 ,0
Exp/Cntr=0.3,0.1

Type RM Length L Ch R = 1 ,28000   ,500,500,500
BEGIN DESCRIPTION:
STEWARTS CREEK 54.0
END DESCRIPTION:
XS GIS Cut Line= 3
      3843691.54     10105164.51      3842568.38     10104567.42
      3841432.02     10104359.12
#Sta/Elev= 30
    3728  178.13  3772.1  174.59    3934  167.65  3939.7  169.16    3956  166.26
  4021.9  163.44  4214.1   158.8  4444.5  156.23  4861.1  154.66  4894.7  154.15
  4944.3  155.95  4960.6  155.32  4966.6  152.15  4976.9  147.91  4982.6  147.23
  4984.1  143.04  5010.9  143.04  5011.4  143.54  5011.6   149.5 5017.85 152.289
    5031  155.72  5041.2  156.31  5102.2   155.2  5142.9  156.48  5272.1  154.25
  5590.2  160.37  5864.7   168.3  5892.5  170.91  5950.7  170.05  6155.3  174.57
#Mann= 6 ,-1 , 0
    3728    .075       0  3772.1     .05       0  4861.1      .1       0
  4966.6     .07       0 5017.85      .1       0  5272.1     .05       0
Bank Sta=4966.6,5017.85
XS Rating Curve= 0 ,0
Exp/Cntr=0.3,0.1

Type RM Length L Ch R = 1 ,27500   ,548,548,548
BEGIN DESCRIPTION:
STEWARTS CREEK 53.0
END DESCRIPTION:
XS GIS Cut Line= 3
      3843946.75     10104635.86      3842568.46      10104083.1
      3841568.26     10103937.08
#Sta/Elev= 30
    3515  172.09  4162.4  156.51    4365  156.55  4472.7  152.39  4677.8  154.44
    4808  151.79    4839   153.5  4856.5  148.47    4886  147.15  4903.7  148.95
  4910.3  151.99  4915.6  149.99  4934.5  154.52  4939.8  152.31  4957.6  154.54
 4973.73 150.966  4979.1   149.1  4984.2  142.26    5011  142.26  5020.8  148.22
  5030.9   151.1  5081.5  153.91  5192.6  152.77  5212.8  156.62  5227.5  155.77
  5252.4   150.3  5537.3  150.38    5649  158.66  5940.5  173.53  6010.8  173.84
#Mann= 7 ,-1 , 0
    3515     .05       0  4677.8      .1       0 4973.73     .07       0
  5030.9      .1       0  5227.5     .05       0  5252.4      .1       0
    5649     .05       0
Bank Sta=4973.73,5030.9
XS Rating Curve= 0 ,0
Exp/Cntr=0.3,0.1

Type RM Length L Ch R = 1 ,26952   ,452,452,452
BEGIN DESCRIPTION:
STEWARTS CREEK 52.0
END DESCRIPTION:
XS GIS Cut Line= 3
      3844111.66     10104184.47      3842277.56     10103790.22
      3841616.03     10103724.41
#Sta/Elev= 30
    3124  164.46  3208.1  164.26  3322.2  161.22  3751.8   155.7  4065.9  154.59
  4445.5  156.31  4525.4   155.1  4637.8  152.67  4651.9  153.82  4682.1  151.94
  4687.2  155.06  4731.4  155.15  4736.5   156.4  4874.4  152.07  4948.3  152.56
  4958.8  152.89    4968  150.29  4973.1   151.6  4979.2  148.52  4983.9  141.15
  5010.7  141.15  5019.8  142.92    5037 151.691    5060  153.07  5190.6  151.53
  5244.9  148.39    5271  151.69  5482.1   167.2  5542.1  170.63  5664.8  174.38
#Mann= 5 ,-1 , 0
    3124     .05       0  4525.4      .1       0  4948.3     .05       0
  4973.1     .07       0    5037     .05       0
Bank Sta=4973.1,5037
XS Rating Curve= 0 ,0
Exp/Cntr=0.3,0.1

Type RM Length L Ch R = 1 ,26500   ,500,500,500
BEGIN DESCRIPTION:
STEWARTS CREEK 51.0
END DESCRIPTION:
XS GIS Cut Line= 3
      3844124.76     10103754.79      3842148.15     10103529.53
      3841668.11     10103472.67
#Sta/Elev= 30
  3010.6  165.45  3443.1  156.37    3551  155.25    3863  153.66  4054.1  154.42
  4164.9   156.8  4327.5  155.32  4496.4  156.25  4597.7  154.81  4698.4  155.16
  4728.6  154.49  4748.7  151.46  4778.9  151.06  4869.5  151.44  4929.8  152.93
  4943.6  151.86  4970.1  152.02  4975.9 150.705  4980.2  149.73  4984.2   140.7
  5011.1   140.7  5020.4  147.81  5027.5  150.62  5032.5  150.14  5050.7  152.38
  5090.9  152.42  5171.5  155.25  5368.7   171.5  5433.3  173.16  5483.4  171.89
#Mann= 3 , 0 , 0
  3010.6     .05       0  4975.9     .07       0  5027.5     .05       0
Bank Sta=4975.9,5027.5
XS Rating Curve= 0 ,0
Exp/Cntr=0.3,0.1

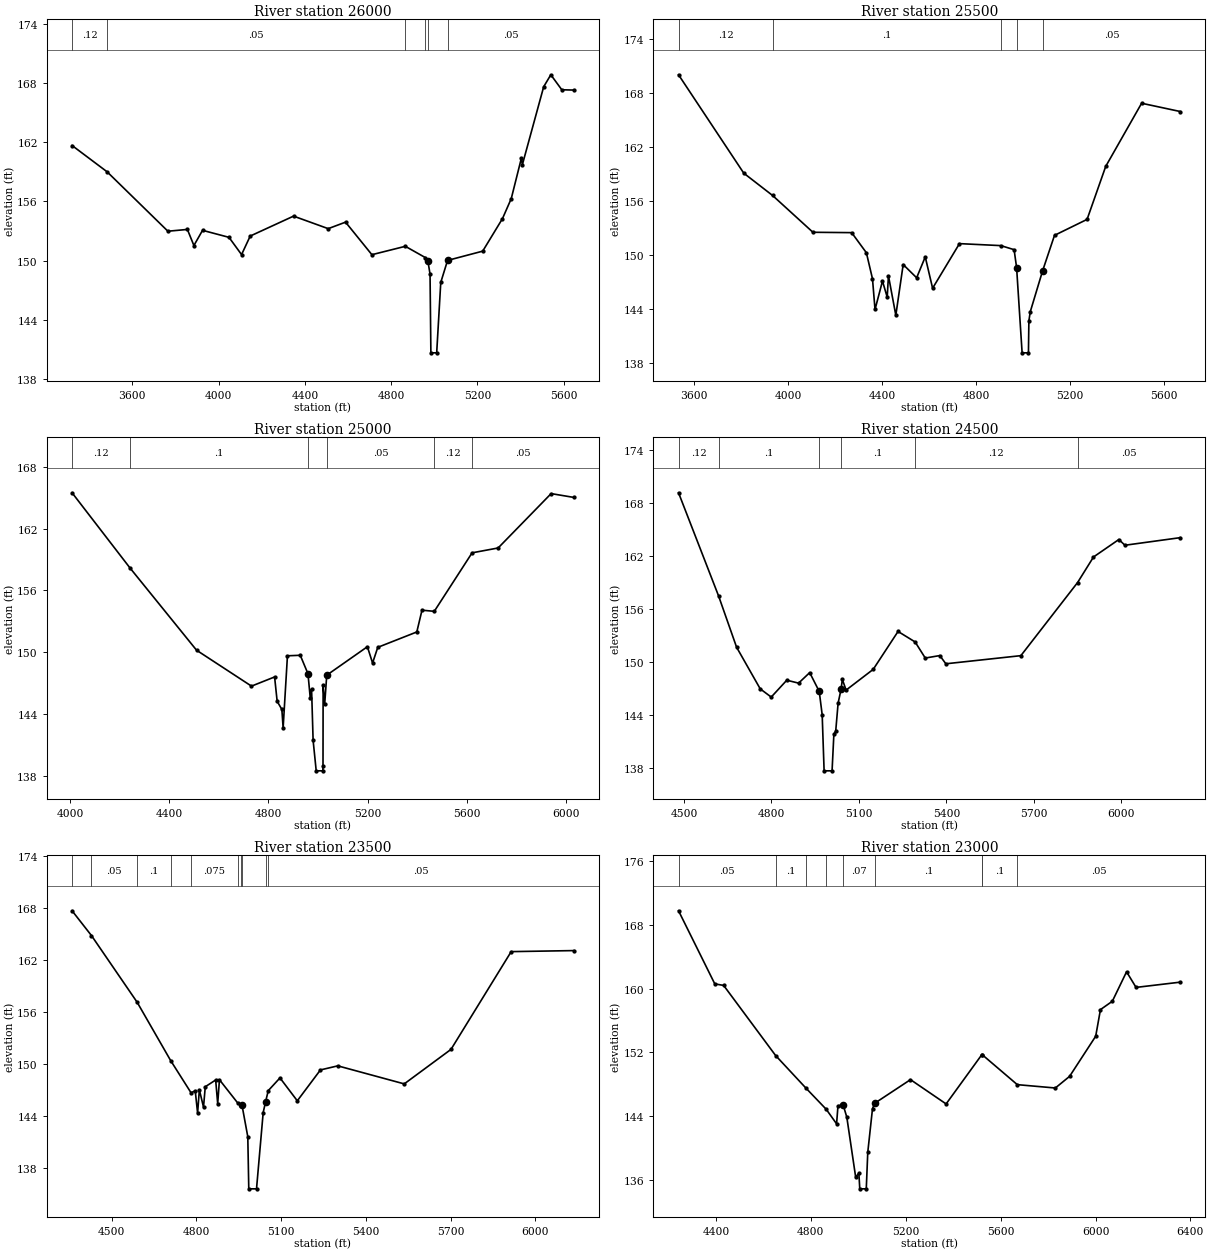
Type RM Length L Ch R = 1 ,26000   ,500,500,500
BEGIN DESCRIPTION:
STEWARTS CREEK 50.0
END DESCRIPTION:
XS GIS Cut Line= 3
       3843990.2      10103281.7       3842318.3     10103129.56
        3841683.     10103252.04
#Sta/Elev= 30
  3321.2  161.66  3483.8  158.99  3765.4  152.97  3855.7  153.15  3885.9  151.52
    3926  153.06  4048.5  152.35  4106.8   150.6  4146.9  152.48  4347.8   154.5
  4508.4  153.23  4588.8  153.89  4710.9  150.59  4865.9  151.44  4958.4   150.3
  4970.3  149.96  4980.4  148.63  4984.3  140.64  5011.2  140.64  5030.1  147.78
  5061.6  150.01  5224.5  150.95  5316.2  154.25  5356.9  156.28  5403.5  160.35
  5408.5  159.73  5507.2  167.62  5540.2  168.83  5591.1  167.31    5647  167.28
#Mann= 6 ,-1 , 0
  3321.2     .12       0  3483.8     .05       0  4865.9     .12       0
  4958.4     .05       0  4970.3     .07       0  5061.6     .05       0
Bank Sta=4970.3,5061.6
XS Rating Curve= 0 ,0
Exp/Cntr=0.3,0.1

Type RM Length L Ch R = 1 ,25500   ,500,500,500
BEGIN DESCRIPTION:
STEWARTS CREEK 49.0
END DESCRIPTION:
XS GIS Cut Line= 3
      3843689.03     10102197.47       3842302.4     10102671.46
      3841731.34     10103021.48
#Sta/Elev= 30
  3534.6  170.02  3812.2   159.1  3934.5  156.63  4106.5  152.54  4271.3   152.5
  4333.9  150.27  4359.9  147.38  4370.7  143.97  4402.4  147.13  4422.6  145.33
  4427.8  147.72  4459.2  143.33  4490.5  148.96  4547.8  147.49  4584.4  149.81
  4615.7  146.33    4730  151.28    4906  151.06  4962.5  150.61  4973.1  148.63
  4996.6  139.16  5023.5  139.16  5025.4  142.71  5031.3  143.72  5083.5  148.24
  5134.4   152.2    5273  153.97  5352.3  159.85  5505.1  166.86  5669.8  165.94
#Mann= 5 ,-1 , 0
  3534.6     .12       0  3934.5      .1       0    4906     .05       0
  4973.1     .07       0  5083.5     .05       0
Bank Sta=4973.1,5083.5
XS Rating Curve= 0 ,0
Exp/Cntr=0.3,0.1

Type RM Length L Ch R = 1 ,25000   ,500,500,500
BEGIN DESCRIPTION:
STEWARTS CREEK 48.0
END DESCRIPTION:
XS GIS Cut Line= 3
      3843506.56     10102035.29      3842548.85     10102293.07
      3841731.38      10102922.8
#Sta/Elev= 30
  4008.2  165.47  4241.9  158.18  4510.3  150.21  4731.8  146.73    4825  147.62
  4835.3  145.26  4854.3  144.47  4859.4  142.68  4876.8  149.67  4928.5  149.72
  4959.6  147.93  4968.9  145.55  4974.1  146.46  4980.3  141.48  4992.8  138.52
  5019.7  138.52  5020.2  139.02  5020.7  146.81  5027.1  145.02  5035.3  147.79
  5199.2  150.55  5220.1  148.97  5241.1  150.49  5398.5  151.98  5419.4  154.09
    5469  153.98  5621.5  159.65  5726.5  160.12  5940.3  165.39  6031.9  165.02
#Mann= 6 ,-1 , 0
  4008.2     .12       0  4241.9      .1       0  4959.6     .07       0
  5035.3     .05       0    5469     .12       0  5621.5     .05       0
Bank Sta=4959.6,5035.3
XS Rating Curve= 0 ,0
Exp/Cntr=0.3,0.1

Type RM Length L Ch R = 1 ,24500   ,1000,1000,1000
BEGIN DESCRIPTION:
STEWARTS CREEK 47.0
END DESCRIPTION:
XS GIS Cut Line= 3
      3842521.28     10101384.24      3842442.82     10101896.97
      3841707.58      10102847.5
#Sta/Elev= 30
  4481.3  169.16  4618.6  157.48  4680.4  151.67  4761.4  146.96  4799.1  146.03
  4852.4  147.94  4892.9  147.61    4931   148.8  4963.7  146.67  4973.8  144.03
  4980.4  137.68  5007.7  137.68  5013.9  141.83  5020.2  142.18  5028.4  145.34
 5038.61 146.931  5042.9  148.03  5055.8  146.82  5148.8  149.17  5233.9  153.46
  5292.5  152.27  5327.2  150.45    5377  150.73  5397.8   149.8    5655  150.72
  5849.5     159    5904  161.89    5991  163.87  6011.8  163.22  6201.7  164.08
#Mann= 6 ,-1 , 0
  4481.3     .12       0  4618.6      .1       0  4963.7     .07       0
 5038.61      .1       0  5292.5     .12       0  5849.5     .05       0
Bank Sta=4963.7,5038.61
XS Rating Curve= 0 ,0
Exp/Cntr=0.3,0.1

Type RM Length L Ch R = 1 ,23500   ,500,500,500
BEGIN DESCRIPTION:
STEWARTS CREEK 46.0
END DESCRIPTION:
XS GIS Cut Line= 3
      3842267.87     10101211.04      3841889.91     10101727.26
      3841650.58     10102837.87
#Sta/Elev= 30
  4360.2  167.69  4428.9  164.83  4590.6  157.14  4709.1  150.42  4781.2  146.71
  4796.1  146.93  4804.5  144.36  4810.7  147.05  4825.4  145.05  4831.6   147.4
  4868.4  148.18  4875.6  145.45  4881.8  148.21  4946.2  145.54  4957.3  145.33
  4961.3  145.33  4982.1  141.64  4985.6  135.63    5013  135.63  5036.6  144.43
  5044.8  145.63  5054.5  146.95    5096  148.42  5157.3  145.78  5239.2  149.34
  5300.6  149.81  5535.8  147.73  5701.3  151.71  5914.3  162.98  6136.1   163.1
#Mann= 10 ,-1 , 0
  4360.2     .12       0  4428.9     .05       0  4590.6      .1       0
  4709.1     .05       0  4781.2    .075       0  4946.2     .05       0
  4957.3    .075       0  4961.3     .07       0  5044.8    .075       0
  5054.5     .05       0
Bank Sta=4961.3,5044.8
XS Rating Curve= 0 ,0
Exp/Cntr=0.3,0.1

Type RM Length L Ch R = 1 ,23000   ,500,500,500
BEGIN DESCRIPTION:
STEWARTS CREEK 45.0
END DESCRIPTION:
XS GIS Cut Line= 3
      3842167.85     10101111.07      3841512.49     10101491.13
      3841565.79     10102847.49
#Sta/Elev= 30
  4242.4  169.78  4395.2   160.6  4432.5  160.41  4651.5  151.61  4779.6  147.51
  4864.8  144.86  4908.6  143.03  4914.4  145.29    4936  145.43  4951.7  143.86
    4989  136.34  5002.5  136.84  5006.3  134.87  5033.7  134.87    5040  139.46
    5060  144.95    5070  145.63  5220.1  148.58  5370.2  145.53  5520.9  151.72
  5521.6  151.73  5670.3  147.95  5830.6  147.53  5890.6  148.99  6000.7  154.03
  6020.7  157.37  6070.8  158.42  6130.8  162.12  6170.8  160.16  6357.4  160.82
#Mann= 9 ,-1 , 0
  4242.4     .05       0  4651.5      .1       0  4779.6     .05       0
  4864.8      .1       0    4936     .07       0    5070      .1       0
  5520.9     .05       0  5521.6      .1       0  5670.3     .05       0
Bank Sta=4936,5070
XS Rating Curve= 0 ,0
Exp/Cntr=0.3,0.1

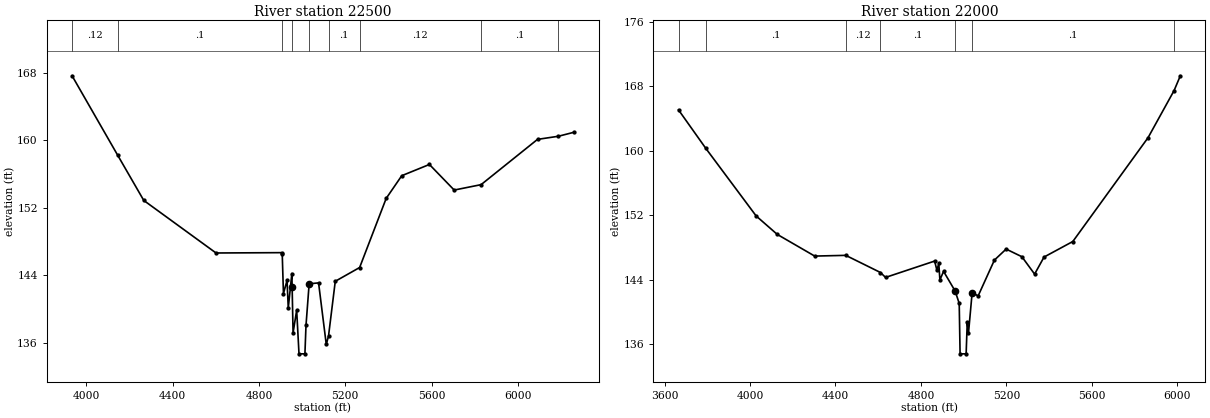
Type RM Length L Ch R = 1 ,22500   ,500,500,500
BEGIN DESCRIPTION:
STEWARTS CREEK 44.0
END DESCRIPTION:
XS GIS Cut Line= 3
      3842031.69      10100907.7      3841079.01     10101386.87
      3840066.44     10102135.56
#Sta/Elev= 30
  3933.6  167.64  4145.1  158.23    4266  152.88  4600.8  146.66  4904.3   146.7
  4907.7  146.51  4913.3  141.86    4930  143.41  4935.6  140.14  4952.3  144.23
 4953.56  142.65  4957.9  137.21  4974.6  139.88  4985.4  134.72  5012.8  134.72
  5017.8  138.08  5032.4  143.01  5076.1  143.12  5111.8  135.83  5122.3  136.85
  5153.5  143.31  5266.4  144.94  5389.4  153.12  5461.6  155.81  5589.8  157.14
  5704.6  154.11  5829.3  154.75  6090.8  160.11  6187.6  160.48  6259.3  160.95
#Mann= 9 ,-1 , 0
  3933.6     .12       0  4145.1      .1       0  4904.3     .05       0
 4953.56     .07       0  5032.4     .05       0  5122.3      .1       0
  5266.4     .12       0  5829.3      .1       0  6187.6     .05       0
Bank Sta=4953.56,5032.4
XS Rating Curve= 0 ,0
Exp/Cntr=0.3,0.1

Type RM Length L Ch R = 1 ,22000   ,563,563,563
BEGIN DESCRIPTION:
STEWARTS CREEK 43.0
END DESCRIPTION:
XS GIS Cut Line= 3
      3841955.34     10100772.27      3840677.91     10101158.71
      3839761.49     10101593.18
#Sta/Elev= 30
  3665.4  165.09  3793.2  160.31  4028.8  151.92  4127.6  149.63  4302.7  146.94
  4448.1  147.03  4610.6   144.9  4634.4  144.29  4864.2  146.32  4874.7  145.19
  4883.6  146.02  4888.8  143.98    4906  145.04  4959.9  142.61  4979.2  141.07
  4983.3   134.8  5011.6   134.8  5016.9  138.75  5022.5  137.34  5039.7  142.39
  5067.9     142  5143.9  146.44  5198.8  147.81  5272.6  146.86  5332.1   144.7
  5376.3  146.82    5511  148.75  5863.3  161.65  5985.1   167.5  6014.2  169.33
#Mann= 7 ,-1 , 0
  3665.4     .12       0  3793.2      .1       0  4448.1     .12       0
  4610.6      .1       0  4959.9     .07       0  5039.7      .1       0
  5985.1     .12       0
Bank Sta=4959.9,5039.7
XS Rating Curve= 0 ,0
Exp/Cntr=0.3,0.1