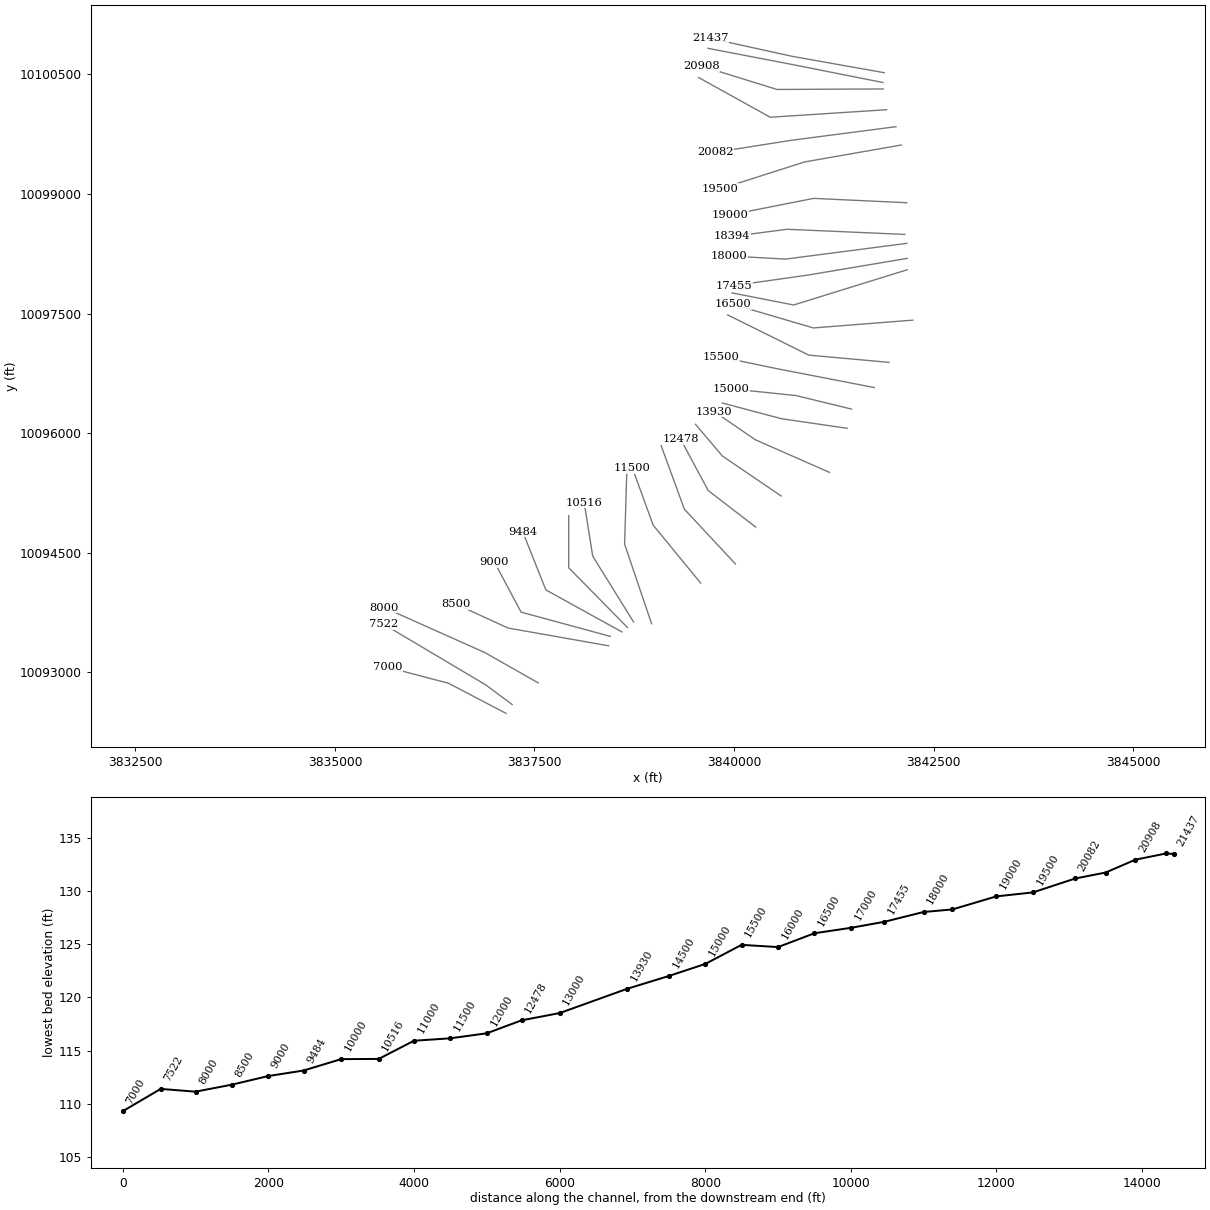
HEC-RAS study STEWARTS CREEK.prj: STEWARTS CREEK Base Level Engineering

--- STEWARTS CREEK.g10 (geometry) --- (continued)

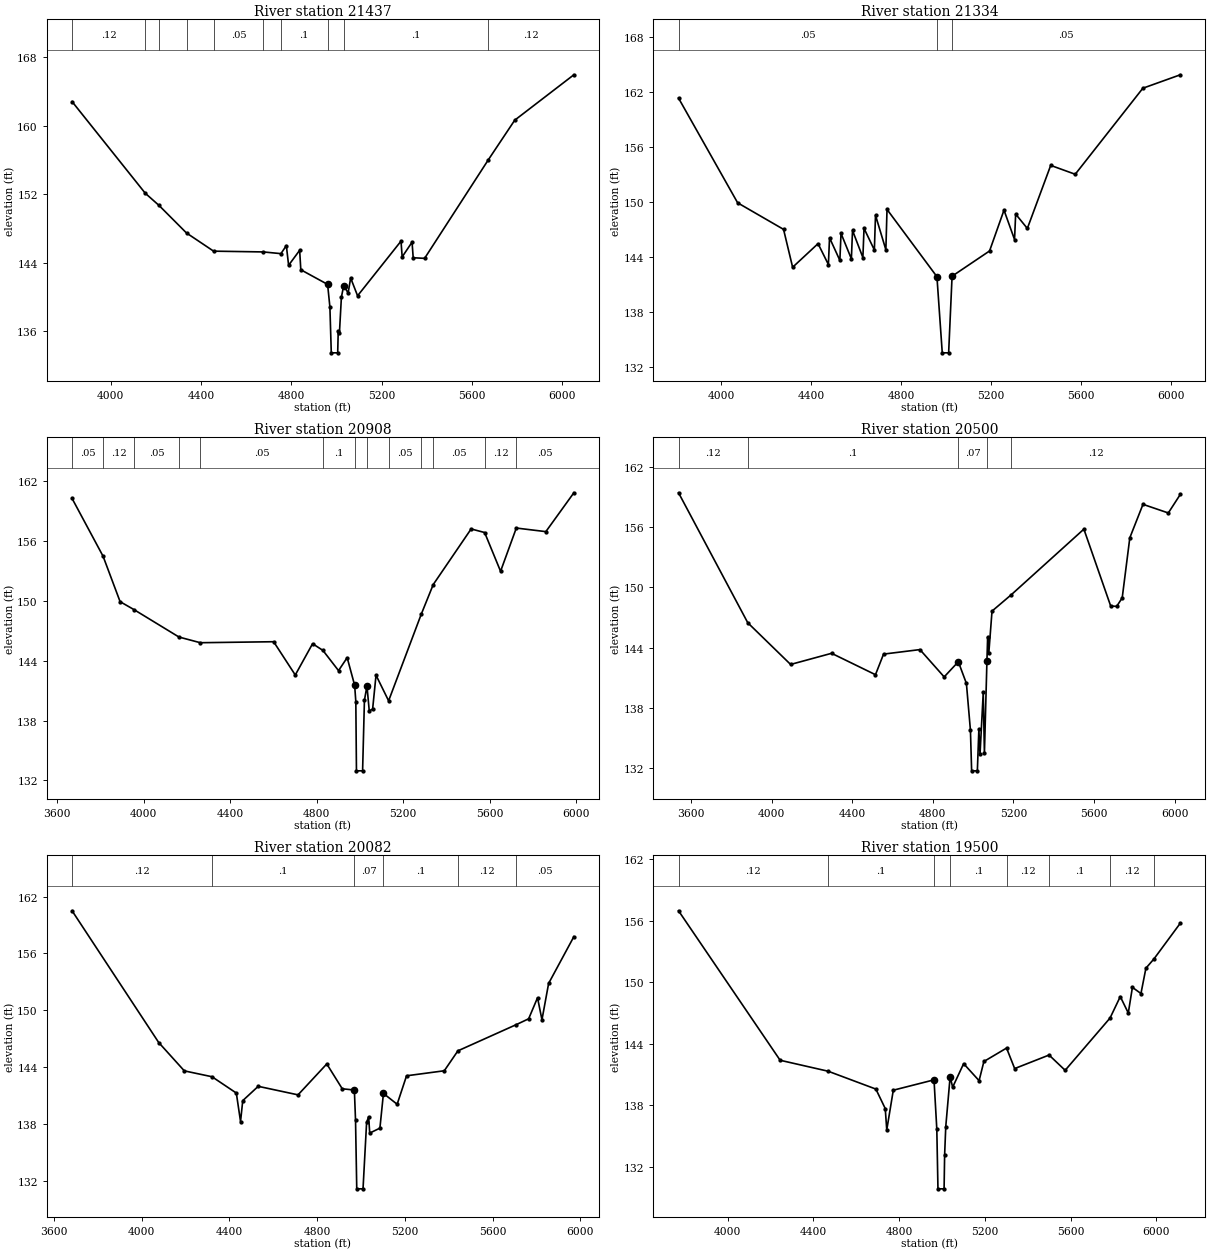
Type RM Length L Ch R = 1 ,21437   ,103,103,103
BEGIN DESCRIPTION:
STEWARTS CREEK 42.0
END DESCRIPTION:
XS GIS Cut Line= 3
      3841882.34     10100518.82      3840728.58     10100724.22
      3839702.06     10100949.75
#Sta/Elev= 30
  3828.1  162.81  4152.4  152.11  4213.2  150.69  4335.1  147.47  4455.1  145.35
  4675.2  145.26  4753.4  145.06  4777.3     146  4787.4   143.7  4836.3  145.45
  4841.4  143.18  4960.1  141.47  4970.3  138.82  4976.4  133.48  5004.8  133.48
  5007.2  136.04  5012.4  135.76  5021.2  139.97  5031.5  141.34    5051  140.46
  5062.2  142.22  5092.9  140.14  5285.3  146.52  5290.4  144.68  5334.2   146.4
  5339.3  144.58  5389.8  144.51  5672.2  156.02  5789.1  160.64    6051  165.94
#Mann= 10 ,-1 , 0
  3828.1     .12       0  4152.4     .05       0  4213.2     .12       0
  4335.1      .1       0  4455.1     .05       0  4675.2     .12       0
  4753.4      .1       0  4960.1     .07       0  5031.5      .1       0
  5672.2     .12       0
Bank Sta=4960.1,5031.5
XS Rating Curve= 0 ,0
Exp/Cntr=0.3,0.1

Type RM Length L Ch R = 1 ,21334   ,426,426,426
BEGIN DESCRIPTION:
Mapping XS 6e584a58
END DESCRIPTION:
XS GIS Cut Line= 3
      3841865.92     10100395.96      3840698.41     10100627.76
      3839674.01     10100824.37
#Sta/Elev= 30
  3809.7  161.37  4072.8  149.93  4277.1  147.03  4317.5  142.89  4430.6  145.47
  4476.7  143.19  4481.8  146.11  4527.8  143.64  4532.9  146.59    4579  143.81
  4584.1  146.91  4630.2  143.95  4635.3  147.14  4681.3  144.78  4686.4  148.57
  4732.5   144.8  4737.6  149.21  4959.8  141.86  4983.5  133.54  5011.9  133.54
  5027.2 141.913    5194  144.67  5258.3  149.13  5305.2  145.92  5310.2   148.7
  5362.2  147.13  5466.2  154.02  5575.3  153.05  5876.3  162.45  6043.1  163.92
#Mann= 3 , 0 , 0
  3809.7     .05       0  4959.8     .07       0  5027.2     .05       0
Bank Sta=4959.8,5027.2
XS Rating Curve= 0 ,0
Exp/Cntr=0.3,0.1

Type RM Length L Ch R = 1 ,20908   ,408,408,408
BEGIN DESCRIPTION:
STEWARTS CREEK 41.0
END DESCRIPTION:
XS GIS Cut Line= 3
      3841869.98     10100315.38       3840538.7     10100308.77
      3839594.21     10100602.14
#Sta/Elev= 30
  3668.7  160.29  3812.1  154.49  3890.8  149.93  3954.5  149.14    4163  146.38
  4261.6  145.81  4600.8  145.91  4700.8  142.57  4780.8  145.71  4828.6  145.04
  4900.8  143.01  4940.8  144.31 4975.34 141.539  4980.8  139.89  4983.7  132.95
  5012.1  132.95  5020.6  140.03  5032.3  141.47  5042.8  138.99  5058.4  139.13
  5074.2  142.55  5132.4  139.98  5283.7  148.69  5338.8  151.65    5514  157.23
  5576.4  156.87  5650.1  152.98  5722.9  157.32  5859.5  156.96    5989  160.86
#Mann= 13 ,-1 , 0
  3668.7     .05       0  3812.1     .12       0  3954.5     .05       0
    4163     .12       0  4261.6     .05       0  4828.6      .1       0
 4975.34     .07       0  5032.3      .1       0  5132.4     .05       0
  5283.7     .12       0  5338.8     .05       0  5576.4     .12       0
  5722.9     .05       0
Bank Sta=4975.34,5032.3
XS Rating Curve= 0 ,0
Exp/Cntr=0.3,0.1

Type RM Length L Ch R = 1 ,20500   ,418,418,418
BEGIN DESCRIPTION:
STEWARTS CREEK 40.0
END DESCRIPTION:
XS GIS Cut Line= 3
      3841912.53     10100054.96      3840454.38     10099960.56
      3839555.76      10100458.6
#Sta/Elev= 30
  3538.8  159.42  3882.2  146.48  4094.6  142.33  4297.8  143.44  4515.5  141.31
  4555.6  143.36    4736  143.81  4856.2  141.09  4926.4   142.6  4966.5  140.44
  4986.5  135.76  4992.4  131.74  5020.8  131.74  5028.3  135.88    5034  133.39
    5050  139.55  5055.8   133.5 5068.28 142.679  5071.8  145.05  5077.5  143.44
  5093.5  147.64  5189.6  149.28  5549.1   155.8    5682  148.15  5711.7  148.11
  5739.2  148.96  5776.9  154.94  5842.2  158.27  5967.8  157.41  6027.4  159.26
#Mann= 5 ,-1 , 0
  3538.8     .12       0  3882.2      .1       0  4926.4     .07       0
 5068.28      .1       0  5189.6     .12       0
Bank Sta=4926.4,5068.28
XS Rating Curve= 0 ,0
Exp/Cntr=0.3,0.1

Type RM Length L Ch R = 1 ,20082   ,582,582,582
BEGIN DESCRIPTION:
STEWARTS CREEK 39.0
END DESCRIPTION:
XS GIS Cut Line= 3
      3842029.69     10099842.28      3840723.32     10099672.17
      3839764.14     10099521.11
#Sta/Elev= 30
  3682.6   160.5  4077.7  146.61  4194.5  143.62  4320.8     143  4431.7  141.28
  4450.9  138.28    4461  140.48  4531.5  141.99  4713.1  141.09  4844.2  144.35
  4914.8  141.73    4970   141.6  4975.3  138.43  4980.9  131.18  5009.5  131.18
  5025.8  138.18    5035  138.78  5040.1  137.06  5086.5  137.58  5102.6  141.24
  5165.1   140.1    5208   143.1  5380.1  143.63  5442.1  145.73  5708.8   148.5
  5764.8  149.11  5805.3  151.33  5825.5  149.01  5855.9  152.84    5971  157.77
#Mann= 6 ,-1 , 0
  3682.6     .12       0  4320.8      .1       0    4970     .07       0
  5102.6      .1       0  5442.1     .12       0  5708.8     .05       0
Bank Sta=4970,5102.6
XS Rating Curve= 0 ,0
Exp/Cntr=0.3,0.1

Type RM Length L Ch R = 1 ,19500   ,500,500,500
BEGIN DESCRIPTION:
STEWARTS CREEK 38.0
END DESCRIPTION:
XS GIS Cut Line= 3
      3842094.87     10099612.26      3840884.03     10099400.02
      3839824.85     10099061.03
#Sta/Elev= 30
  3770.7  156.99  4244.8  142.41    4469  141.34  4691.5   139.6  4735.2   137.7
  4742.3  135.62  4772.8  139.49  4962.8   140.5  4975.8   135.7  4981.2  129.87
  5009.8  129.87  5012.3  133.17  5017.6  135.94    5038  140.81  5049.7  139.78
    5101  142.08  5173.1  140.42  5195.5  142.29  5301.3   143.6  5339.1   141.6
  5499.6  142.92  5574.7  141.43  5784.2  146.53  5831.9  148.62  5869.3  147.02
  5888.5  149.52  5928.4  148.92  5951.5  151.39  5988.9  152.29  6112.1  155.78
#Mann= 8 ,-1 , 0
  3770.7     .12       0    4469      .1       0  4962.8     .07       0
    5038      .1       0  5301.3     .12       0  5499.6      .1       0
  5784.2     .12       0  5988.9     .05       0
Bank Sta=4962.8,5038
XS Rating Curve= 0 ,0
Exp/Cntr=0.3,0.1

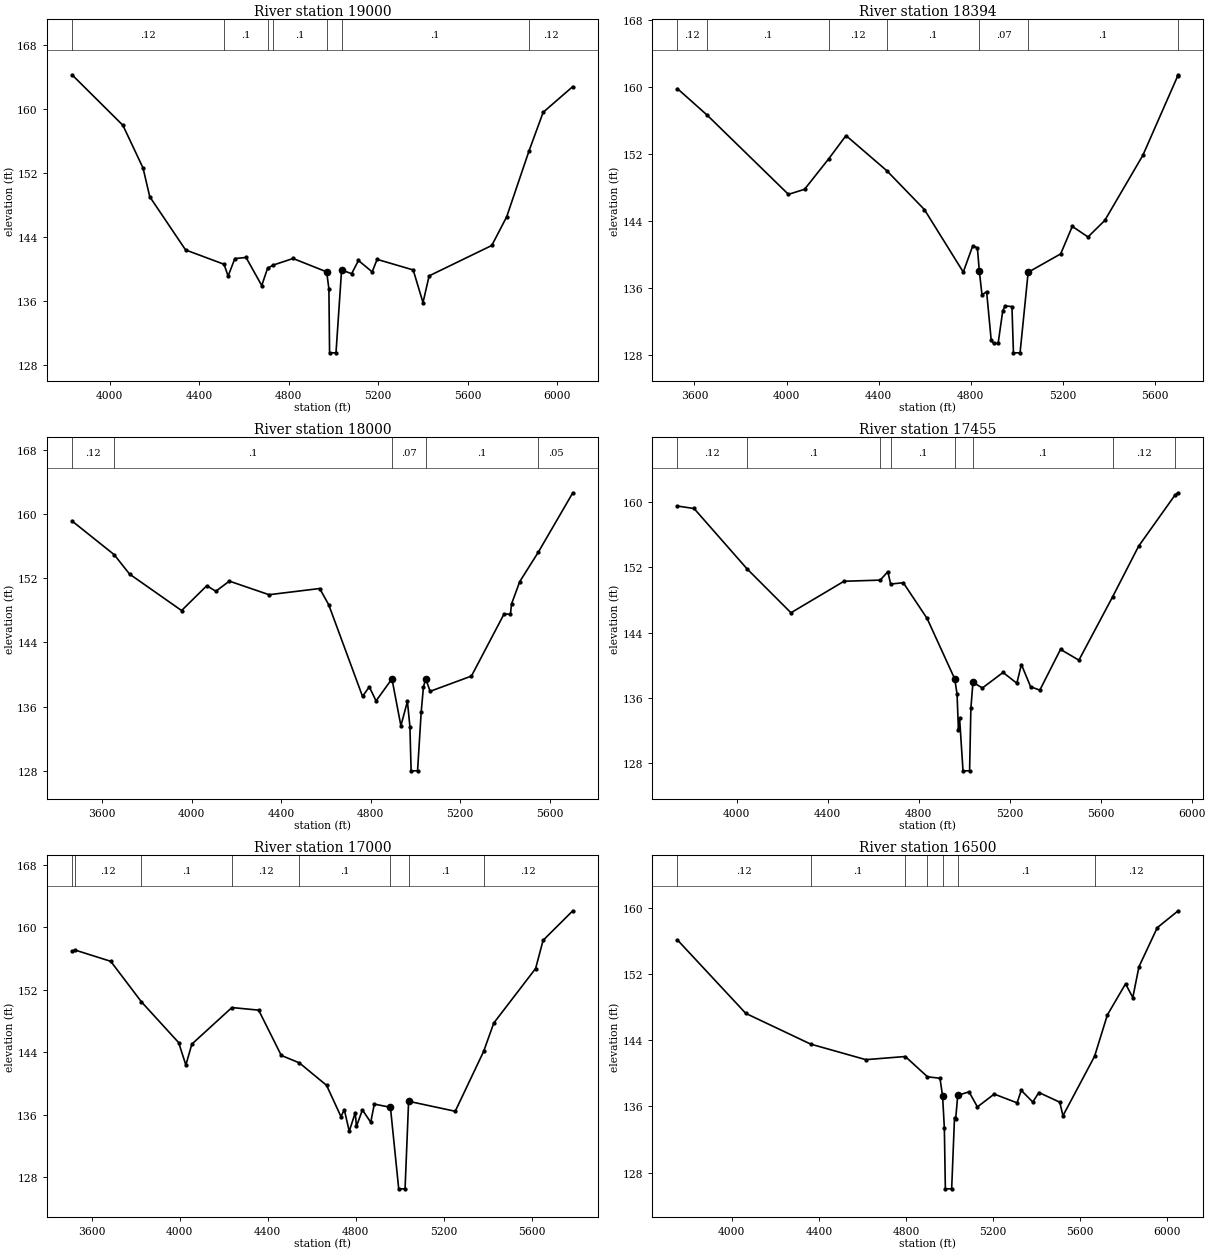
Type RM Length L Ch R = 1 ,19000   ,606,606,606
BEGIN DESCRIPTION:
STEWARTS CREEK 37.0
END DESCRIPTION:
XS GIS Cut Line= 3
      3842164.98      10098888.7      3840998.26     10098943.45
      3839947.79     10098735.79
#Sta/Elev= 30
    3832  164.25  4059.4  157.94  4149.5   152.6  4179.5  149.01  4339.7  142.36
  4511.5  140.57  4529.9  139.09  4559.9  141.28    4610  141.42  4680.1  137.91
  4706.4  140.08  4732.7  140.48  4820.2  141.29  4970.4  139.62  4980.4  137.49
  4983.4   129.5  5012.1   129.5  5037.1  139.86    5082  139.39  5112.5  141.04
  5173.7  139.62    5196  141.18  5357.2  139.86    5401  135.78  5428.5  139.12
  5708.6  142.92  5775.1   146.5  5874.3  154.68  5938.2  159.56  6070.8  162.78
#Mann= 7 ,-1 , 0
    3832     .12       0  4511.5      .1       0  4706.4     .12       0
  4732.7      .1       0  4970.4     .07       0  5037.1      .1       0
  5874.3     .12       0
Bank Sta=4970.4,5037.1
XS Rating Curve= 0 ,0
Exp/Cntr=0.3,0.1

Type RM Length L Ch R = 1 ,18394   ,394,394,394
BEGIN DESCRIPTION:
STEWARTS CREEK 36.0
END DESCRIPTION:
XS GIS Cut Line= 3
      3842139.55     10098491.53      3840667.07     10098556.07
      3839971.64     10098466.24
#Sta/Elev= 30
  3526.1  159.78  3655.3  156.62  4008.3  147.17  4078.3  147.77  4182.8  151.39
  4258.5  154.18  4435.6  149.99  4598.8  145.36  4767.8   137.9    4809  141.04
    4829  140.79  4837.5 138.021  4849.1  135.17  4869.1  135.57  4889.1  129.77
  4899.1   129.4  4919.1  129.39  4939.2  133.28  4949.2  133.86  4979.2  133.79
  4985.6  128.27  5014.4  128.27  5049.6  137.88  5190.8  140.07  5241.2  143.35
  5309.5  142.09  5382.4  144.06  5547.6  151.82  5699.9  161.34  5701.2  161.43
#Mann= 7 ,-1 , 0
  3526.1     .12       0  3655.3      .1       0  4182.8     .12       0
  4435.6      .1       0  4837.5     .07       0  5049.6      .1       0
  5699.9     .12       0
Bank Sta=4837.5,5049.6
XS Rating Curve= 0 ,0
Exp/Cntr=0.3,0.1

Type RM Length L Ch R = 1 ,18000   ,545,545,545
BEGIN DESCRIPTION:
STEWARTS CREEK 35.0
END DESCRIPTION:
XS GIS Cut Line= 3
      3842165.01     10098379.51      3840643.67     10098182.02
      3839941.28     10098221.57
#Sta/Elev= 30
  3465.9  159.11  3654.4  154.92  3722.9  152.51  3955.4  147.97  4068.1  151.06
  4108.4  150.37  4168.9  151.63  4346.2  149.94  4572.3  150.71  4612.6  148.71
  4763.9  137.29  4794.1  138.48  4824.4  136.73  4895.4  139.47  4935.3  133.64
  4964.5  136.66  4975.6  133.54    4981  128.03  5009.8  128.03  5025.9  135.29
  5035.9  138.42  5045.9  139.51  5065.9  137.92  5250.6  139.82  5396.4  147.55
  5424.7   147.5  5429.7  148.79  5466.6  151.58  5549.9  155.26  5703.5  162.62
#Mann= 5 ,-1 , 0
  3465.9     .12       0  3654.4      .1       0  4895.4     .07       0
  5045.9      .1       0  5549.9     .05       0
Bank Sta=4895.4,5045.9
XS Rating Curve= 0 ,0
Exp/Cntr=0.3,0.1

Type RM Length L Ch R = 1 ,17455   ,455,455,455
BEGIN DESCRIPTION:
STEWARTS CREEK 34.0
END DESCRIPTION:
XS GIS Cut Line= 3
      3842170.03     10098191.09      3840927.39      10097982.1
      3839995.81     10097849.94
#Sta/Elev= 30
  3739.9  159.45  3813.1  159.15  4045.9  151.78    4239  146.41  4472.2  150.26
  4631.3   150.4  4664.9  151.43  4677.1  149.92  4732.8  150.08  4837.3  145.72
    4959  138.32  4969.1  136.44  4975.1  132.03  4980.2  133.51  4995.2   127.1
  5024.1   127.1  5029.8  134.77  5038.9  137.92  5080.3  137.22  5171.2  139.12
  5231.8   137.8  5251.7  140.09  5292.4  137.37  5332.8  136.96  5423.7  141.94
  5504.5  140.62  5652.5  148.35  5767.1  154.55  5927.9  160.83  5940.9  161.07
#Mann= 8 ,-1 , 0
  3739.9     .12       0  4045.9      .1       0  4631.3     .12       0
  4677.1      .1       0    4959     .07       0  5038.9      .1       0
  5652.5     .12       0  5927.9     .05       0
Bank Sta=4959,5038.9
XS Rating Curve= 0 ,0
Exp/Cntr=0.3,0.1

Type RM Length L Ch R = 1 ,17000   ,500,500,500
BEGIN DESCRIPTION:
STEWARTS CREEK 33.0
END DESCRIPTION:
XS GIS Cut Line= 3
      3842170.04     10098048.51       3840747.7     10097606.94
      3839975.39     10097758.28
#Sta/Elev= 30
  3510.7  156.93  3523.6  157.12  3686.7  155.67  3826.5  150.47  3995.5  145.26
  4028.1  142.39  4055.4  145.07  4237.3  149.75    4359  149.42  4461.9  143.62
  4543.8  142.67  4667.8  139.79    4733   135.8  4748.5  136.65  4770.8  133.91
  4798.1  136.29  4803.4  134.53  4830.7  136.64  4868.5  135.06  4884.7  137.39
    4958  136.98  4995.6  126.54  5024.5  126.54  5040.6  137.75  5252.5  136.47
  5381.6  144.13  5427.8  147.77  5617.9  154.75    5652  158.36    5787  162.14
#Mann= 8 ,-1 , 0
  3510.7      .1       0  3523.6     .12       0  3826.5      .1       0
  4237.3     .12       0  4543.8      .1       0    4958     .07       0
  5040.6      .1       0  5381.6     .12       0
Bank Sta=4958,5040.6
XS Rating Curve= 0 ,0
Exp/Cntr=0.3,0.1

Type RM Length L Ch R = 1 ,16500   ,500,500,500
BEGIN DESCRIPTION:
STEWARTS CREEK 32.0
END DESCRIPTION:
XS GIS Cut Line= 3
      3842241.37     10097417.12      3840994.81     10097319.23
      3839985.55     10097615.72
#Sta/Elev= 30
  3749.6  156.11  4064.1  147.23  4362.2  143.52  4615.8  141.64  4797.3  142.02
  4899.3  139.57  4956.8  139.39  4968.8 137.234  4976.9  133.37  4981.5  126.03
  5010.5  126.03  5023.6  134.65  5028.8  134.46  5038.5  137.33  5090.3  137.75
  5128.9  135.93  5206.1  137.48  5311.4  136.42  5330.3  137.93  5383.4  136.52
  5411.5  137.67  5507.5   136.5  5522.1  134.86  5667.4  142.04  5726.4  147.05
  5809.9   150.8  5843.3  149.15  5871.4  152.86  5955.7  157.59  6051.9  159.63
#Mann= 7 ,-1 , 0
  3749.6     .12       0  4362.2      .1       0  4797.3     .12       0
  4899.3      .1       0  4968.8     .07       0  5038.5      .1       0
  5667.4     .12       0
Bank Sta=4968.8,5038.5
XS Rating Curve= 0 ,0
Exp/Cntr=0.3,0.1

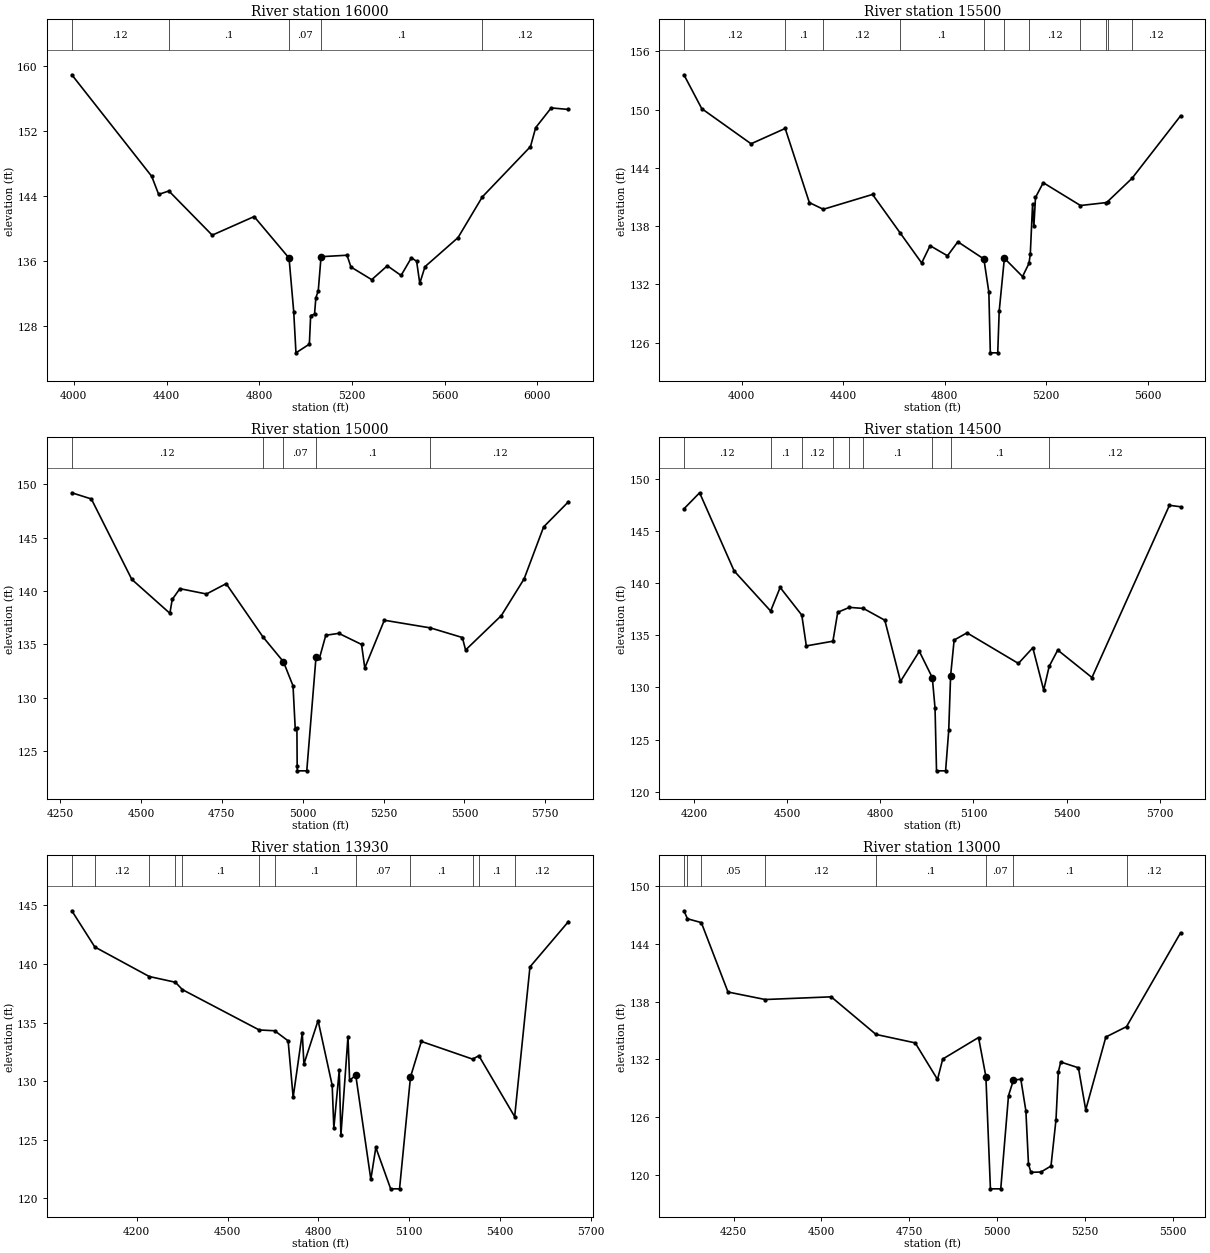
Type RM Length L Ch R = 1 ,16000   ,500,500,500
BEGIN DESCRIPTION:
STEWARTS CREEK 31.0
END DESCRIPTION:
XS GIS Cut Line= 3
      3841940.91     10096887.55      3840936.63     10096978.59
      3839921.16     10097482.44
#Sta/Elev= 30
  3991.6  158.97  4336.1  146.47  4366.2  144.24  4410.2  144.66  4597.1  139.22
  4777.9  141.51  4928.5   136.4  4948.6  129.82  4958.3  124.73  5016.1   125.8
  5021.7  129.32  5038.5  129.49  5044.1   131.5  5054.5  132.38  5066.5  136.57
  5178.6  136.75  5195.4   135.3  5285.1  133.74  5352.3  135.45  5411.7  134.26
  5456.3  136.44  5478.7     136  5492.3  133.29  5514.8  135.34  5657.3  138.92
    5762  143.93  5969.8  150.13  5992.2  152.46  6059.1  154.89  6133.6   154.7
#Mann= 5 ,-1 , 0
  3991.6     .12       0  4410.2      .1       0  4928.5     .07       0
  5066.5      .1       0    5762     .12       0
Bank Sta=4928.5,5066.5
XS Rating Curve= 0 ,0
Exp/Cntr=0.3,0.1

Type RM Length L Ch R = 1 ,15500   ,500,500,500
BEGIN DESCRIPTION:
STEWARTS CREEK 30.0
END DESCRIPTION:
XS GIS Cut Line= 3
      3841757.58     10096571.85      3840552.63     10096805.54
      3839837.93     10096953.74
#Sta/Elev= 30
  3772.6  153.59  3842.9   150.1  4037.2  146.48  4171.7  148.06  4266.9  140.42
  4321.9  139.73  4515.9  141.26  4625.7  137.26  4709.5   134.2  4742.7  135.98
  4811.3  134.94  4852.1  136.38  4954.7  134.61  4974.3  131.19  4980.1  124.94
  5009.3  124.94  5015.1  129.25  5035.5  134.69    5107   132.8  5132.3  134.15
  5137.6  135.09  5146.6  140.27  5151.7  137.96  5158.1  140.95  5188.7  142.47
  5335.4  140.12  5436.9  140.42  5442.2  140.52  5538.5  142.92  5729.9  149.36
#Mann= 11 ,-1 , 0
  3772.6     .12       0  4171.7      .1       0  4321.9     .12       0
  4625.7      .1       0  4954.7     .07       0  5035.5      .1       0
  5132.3     .12       0  5335.4      .1       0  5436.9     .12       0
  5442.2     .05       0  5538.5     .12       0
Bank Sta=4954.7,5035.5
XS Rating Curve= 0 ,0
Exp/Cntr=0.3,0.1

Type RM Length L Ch R = 1 ,15000   ,500,500,500
BEGIN DESCRIPTION:
STEWARTS CREEK 29.0
END DESCRIPTION:
XS GIS Cut Line= 3
      3841472.42     10096301.98      3840778.75     10096471.15
      3839961.49     10096556.43
#Sta/Elev= 30
    4286  149.21  4346.4  148.63  4471.5  141.09  4589.2  137.91  4596.5  139.21
  4620.1  140.22  4702.4  139.72  4763.3  140.69  4876.7  135.71  4940.3  133.37
    4970  131.11  4976.9  127.05    4982  127.17  4982.8  123.64  4983.3  123.14
  5012.5  123.14  5041.1  133.81  5051.8  133.71  5071.3  135.85  5111.5  136.03
  5181.9  134.99  5191.9  132.78  5252.3  137.26    5395  136.54  5493.6  135.64
  5503.6  134.47  5614.2   137.7  5684.6  141.14  5744.9  146.01  5821.7  148.37
#Mann= 5 ,-1 , 0
    4286     .12       0  4876.7      .1       0  4940.3     .07       0
  5041.1      .1       0    5395     .12       0
Bank Sta=4940.3,5041.1
XS Rating Curve= 0 ,0
Exp/Cntr=0.3,0.1

Type RM Length L Ch R = 1 ,14500   ,570,570,570
BEGIN DESCRIPTION:
STEWARTS CREEK 28.0
END DESCRIPTION:
XS GIS Cut Line= 3
      3841417.82     10096061.08      3840594.45     10096181.28
       3839853.2     10096378.35
#Sta/Elev= 30
  4167.9  147.11  4218.4  148.65  4329.6  141.16  4447.1  137.32  4477.7  139.58
  4547.4  136.93    4562  133.98  4647.6  134.43  4663.1   137.2  4700.8  137.67
  4745.8  137.57  4814.7  136.44  4865.2  130.58  4925.8  133.46  4967.6  130.94
  4976.4  128.03  4981.2  122.01  5010.4  122.01  5020.5  125.89  5026.5 131.101
  5037.9  134.54  5079.3  135.23  5244.8   132.3  5291.2   133.8  5326.2  129.75
  5343.9  132.02  5371.5  133.58  5481.7  130.95  5731.1  147.45    5767  147.31
#Mann= 9 ,-1 , 0
  4167.9     .12       0  4447.1      .1       0  4547.4     .12       0
  4647.6      .1       0  4700.8     .12       0  4745.8      .1       0
  4967.6     .07       0  5026.5      .1       0  5343.9     .12       0
Bank Sta=4967.6,5026.5
XS Rating Curve= 0 ,0
Exp/Cntr=0.3,0.1

Type RM Length L Ch R = 1 ,13930   ,930,930,930
BEGIN DESCRIPTION:
STEWARTS CREEK 27.0
END DESCRIPTION:
XS GIS Cut Line= 3
      3841197.03     10095508.34      3840268.55     10095916.92
      3839752.12      10096270.9
#Sta/Elev= 30
  3985.6  144.54  4061.6  141.45  4241.4  138.93  4327.7  138.44    4351  137.81
  4604.4  134.37  4655.7   134.3  4700.1  133.44  4716.7  128.62  4746.8   134.1
  4752.3  131.46    4799  135.17  4845.6  129.65  4851.1     126    4869  130.94
  4874.4  125.37  4897.8  133.81  4903.2  130.06  4923.4 130.521  4973.3  121.62
  4989.8  124.34  5038.8  120.81  5068.1  120.81  5104.3  130.36  5140.1  133.39
  5309.5  131.88  5330.1  132.17  5448.4  126.97  5498.9  139.75  5626.1  143.62
#Mann= 12 ,-1 , 0
  3985.6     .05       0  4061.6     .12       0  4241.4     .05       0
  4327.7     .12       0    4351      .1       0  4604.4     .12       0
  4655.7      .1       0  4923.4     .07       0  5104.3      .1       0
  5309.5     .12       0  5330.1      .1       0  5448.4     .12       0
Bank Sta=4923.4,5104.3
XS Rating Curve= 0 ,0
Exp/Cntr=0.3,0.1

Type RM Length L Ch R = 1 ,13000   ,522,522,522
BEGIN DESCRIPTION:
STEWARTS CREEK 26.0
END DESCRIPTION:
XS GIS Cut Line= 3
      3840591.55     10095212.27      3839854.75     10095713.46
      3839517.88     10096111.03
#Sta/Elev= 30
  4108.9  147.44  4118.9  146.61  4158.4  146.21  4234.2  138.99  4340.1  138.21
  4527.6  138.49    4655  134.58  4766.5   133.7  4829.9   129.9  4844.8  132.02
  4946.6  134.26  4967.5   130.2  4980.4  118.52  5009.8  118.52  5031.8  128.21
    5046  129.85  5066.9  129.91  5081.2  126.64  5088.6   121.1  5095.5  120.24
    5124  120.27  5152.6  120.89  5166.9  125.73  5173.5  130.69  5180.4  131.71
  5230.6  131.11  5251.4  126.74  5308.6  134.31  5367.4  135.39  5521.1  145.15
#Mann= 8 ,-1 , 0
  4108.9     .05       0  4118.9     .12       0  4158.4     .05       0
  4340.1     .12       0    4655      .1       0  4967.5     .07       0
    5046      .1       0  5367.4     .12       0
Bank Sta=4967.5,5046
XS Rating Curve= 0 ,0
Exp/Cntr=0.3,0.1

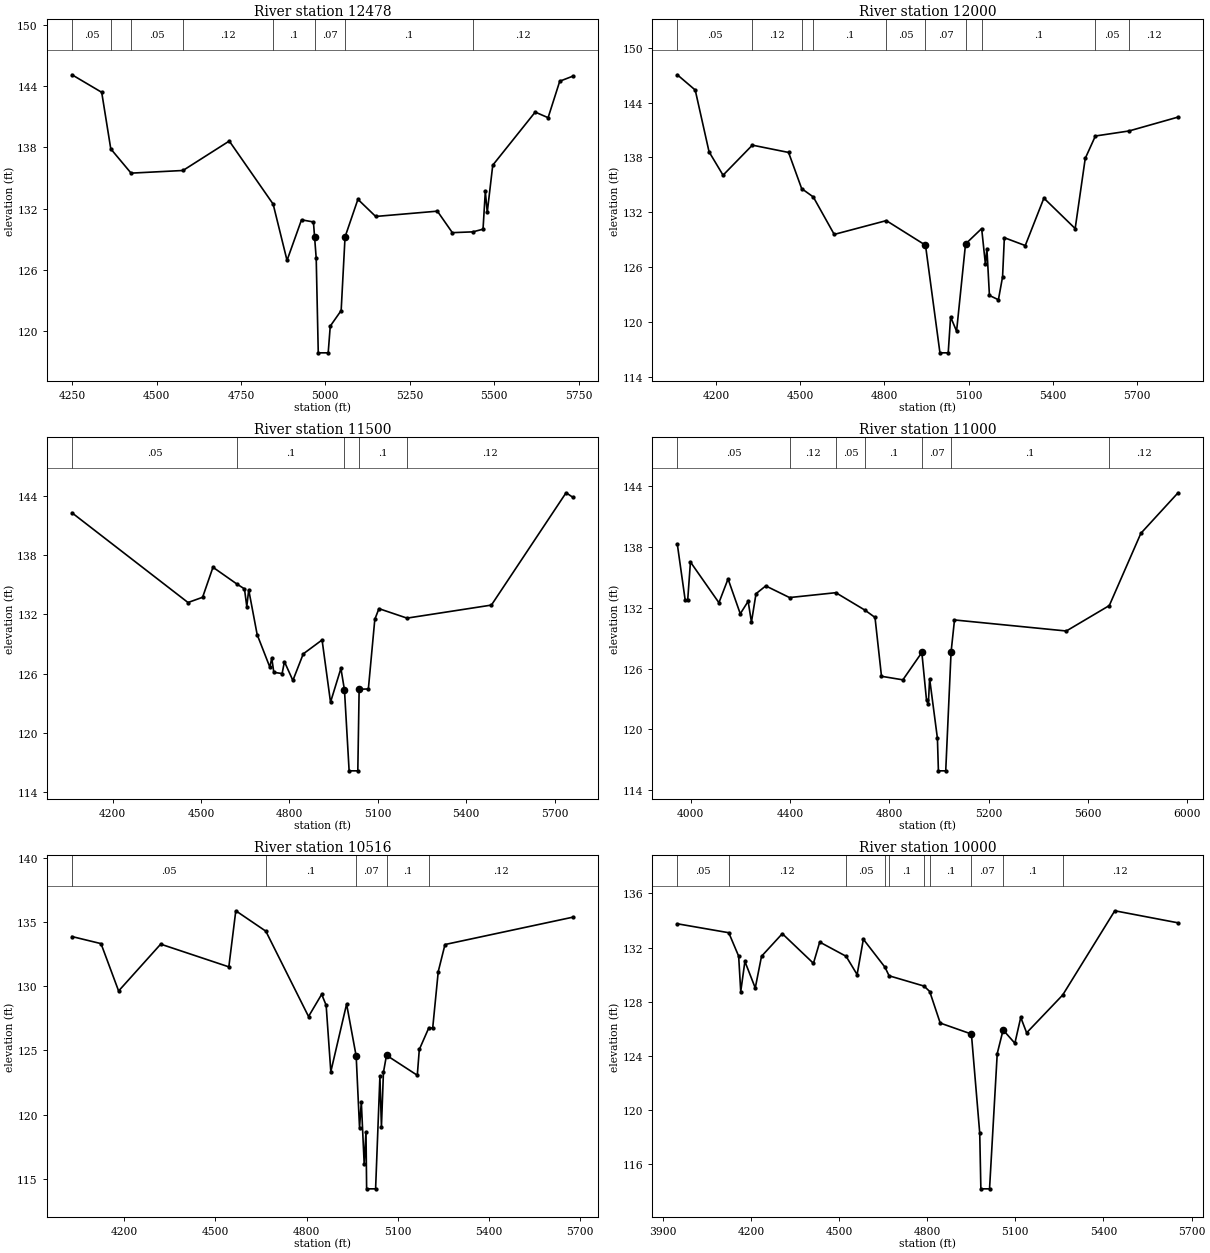
Type RM Length L Ch R = 1 ,12478   ,478,478,478
BEGIN DESCRIPTION:
STEWARTS CREEK 25.0
END DESCRIPTION:
XS GIS Cut Line= 3
      3840272.57     10094822.58      3839677.87     10095279.88
      3839330.74     10095925.02
#Sta/Elev= 30
  4249.8  145.12  4337.7   143.4  4364.6  137.85  4424.7  135.47  4578.4  135.73
  4715.5  138.62  4845.4  132.43  4886.5  126.91  4929.4  130.89  4964.7  130.68
 4968.04  129.23  4972.9  127.12    4979  117.84  5008.4  117.84  5014.5  120.46
  5046.8  121.99  5058.3  129.21  5096.4   132.9    5149  131.22  5331.7  131.74
  5376.1  129.63  5436.8  129.71  5466.9  129.97  5473.7  133.67  5479.4  131.62
  5495.7  136.25  5621.4  141.46  5659.6  140.91  5694.1  144.49  5732.6  144.98
#Mann= 8 ,-1 , 0
  4249.8     .05       0  4364.6     .12       0  4424.7     .05       0
  4578.4     .12       0  4845.4      .1       0 4968.04     .07       0
  5058.3      .1       0  5436.8     .12       0
Bank Sta=4968.04,5058.3
XS Rating Curve= 0 ,0
Exp/Cntr=0.3,0.1

Type RM Length L Ch R = 1 ,12000   ,500,500,500
BEGIN DESCRIPTION:
STEWARTS CREEK 24.0
END DESCRIPTION:
XS GIS Cut Line= 3
      3840017.86     10094361.06      3839378.44     10095047.07
      3839087.71      10095842.5
#Sta/Elev= 30
  4062.2  147.05    4126  145.38  4175.3  138.62  4225.2  136.06  4329.6  139.35
  4458.7  138.55  4505.4  134.59  4546.8  133.68  4621.4  129.58  4807.1  131.09
  4946.7   128.4  4998.2  116.62  5027.7  116.62  5036.2  120.55  5057.5  118.99
  5089.4  128.53  5146.9  130.22  5160.3  126.31  5165.6  128.02  5174.6   122.9
  5206.6  122.43  5221.4  124.93  5227.8  129.22  5302.3  128.36  5368.7  133.55
  5480.2  130.22  5516.1   137.9  5552.2  140.35    5672   140.9  5846.9  142.42
#Mann= 10 ,-1 , 0
  4062.2     .05       0  4329.6     .12       0  4505.4     .05       0
  4546.8      .1       0  4807.1     .05       0  4946.7     .07       0
  5089.4     .05       0  5146.9      .1       0  5552.2     .05       0
    5672     .12       0
Bank Sta=4946.7,5089.4
XS Rating Curve= 0 ,0
Exp/Cntr=0.3,0.1

Type RM Length L Ch R = 1 ,11500   ,500,500,500
BEGIN DESCRIPTION:
STEWARTS CREEK 23.0
END DESCRIPTION:
XS GIS Cut Line= 3
      3839582.35     10094121.46      3838987.75     10094846.53
      3838727.31     10095562.43
#Sta/Elev= 30
  4062.3  142.27    4456  133.19  4505.5  133.72  4540.7  136.76    4622  135.06
  4647.6  134.57  4655.5  132.78    4662  134.48  4690.7  129.94  4733.7  126.65
  4740.2  127.57  4747.2  126.12  4775.4     126  4783.2   127.2  4811.9   125.3
  4847.1  127.99    4911   129.4  4939.7   123.1  4974.9  126.52    4987 124.336
  5002.8  116.15  5032.3  116.15  5036.8  124.41  5068.1  124.44    5090  131.49
    5104  132.57  5199.3  131.61  5485.7  132.93  5739.1   144.3  5761.8  143.85
#Mann= 5 ,-1 , 0
  4062.3     .05       0    4622      .1       0    4987     .07       0
  5036.8      .1       0  5199.3     .12       0
Bank Sta=4987,5036.8
XS Rating Curve= 0 ,0
Exp/Cntr=0.3,0.1

Type RM Length L Ch R = 1 ,11000   ,484,484,484
BEGIN DESCRIPTION:
STEWARTS CREEK 22.0
END DESCRIPTION:
XS GIS Cut Line= 3
      3838967.85     10093611.07      3838629.73     10094608.73
      3838658.68      10095570.7
#Sta/Elev= 30
  3946.6  138.28  3978.3  132.76  3988.4  132.78  3999.4  136.53  4114.1  132.51
  4150.8  134.86    4200  131.42  4231.7  132.65    4245   130.6  4263.4   133.4
  4302.6  134.17  4398.3  133.02  4584.7   133.5  4701.8  131.78  4742.4  131.06
  4768.5  125.25  4854.6   124.9  4930.9   127.6  4949.7  122.91    4957  122.48
  4962.3  125.01  4993.7  119.12  4997.6  115.92  5027.1  115.92  5048.6 127.634
  5062.4  130.81  5512.6  129.72  5685.6  132.23  5812.7  139.36  5962.4  143.36
#Mann= 7 ,-1 , 0
  3946.6     .05       0  4398.3     .12       0  4584.7     .05       0
  4701.8      .1       0  4930.9     .07       0  5048.6      .1       0
  5685.6     .12       0
Bank Sta=4930.9,5048.6
XS Rating Curve= 0 ,0
Exp/Cntr=0.3,0.1

Type RM Length L Ch R = 1 ,10516   ,516,516,516
BEGIN DESCRIPTION:
STEWARTS CREEK 21.0
END DESCRIPTION:
XS GIS Cut Line= 3
      3838742.01     10093633.18      3838229.92     10094458.64
      3838123.96     10095126.18
#Sta/Elev= 30
  4028.6  133.87    4124  133.32  4181.9  129.63  4320.3  133.28  4544.5  131.51
  4567.4  135.88  4666.2  134.29  4806.7  127.64  4849.9  129.37  4864.6  128.52
    4880  123.34  4931.9  128.61 4963.43 124.553  4974.5  118.96  4980.3     121
  4989.8  116.14  4995.7  118.66  4997.8  114.21  5027.3  114.21  5041.5  122.98
  5046.5  119.03  5053.1  123.29  5063.2  124.62  5164.5  123.06  5171.1  125.07
  5202.6  126.77  5215.1  126.73  5233.4  131.14  5255.6  133.25  5675.9  135.38
#Mann= 5 ,-1 , 0
  4028.6     .05       0  4666.2      .1       0 4963.43     .07       0
  5063.2      .1       0  5202.6     .12       0
Bank Sta=4963.43,5063.2
XS Rating Curve= 0 ,0
Exp/Cntr=0.3,0.1

Type RM Length L Ch R = 1 ,10000   ,516,516,516
BEGIN DESCRIPTION:
STEWARTS CREEK 20.0
END DESCRIPTION:
XS GIS Cut Line= 3
      3838665.63     10093563.72      3837929.44     10094312.54
      3837929.51     10094966.34
#Sta/Elev= 30
  3949.9  133.76  4124.9   133.1  4158.6  131.37  4165.7  128.75  4179.8  130.98
  4215.1  129.02  4236.4  131.36  4307.1  133.03  4413.1  130.84  4434.4  132.41
  4524.2  131.36  4561.7  130.01  4582.9  132.62  4656.6  130.55  4670.5  129.92
  4789.5  129.16  4808.7  128.76  4844.5  126.43  4950.6  125.62  4978.9  118.31
  4982.8  114.19  5012.3  114.19  5038.5  124.18  5058.5  125.92  5098.5  124.94
  5118.5  126.85  5138.5  125.71  5261.2   128.5  5438.5  134.72  5653.8  133.83
#Mann= 10 ,-1 , 0
  3949.9     .05       0  4124.9     .12       0  4524.2     .05       0
  4656.6     .12       0  4670.5      .1       0  4789.5     .12       0
  4808.7      .1       0  4950.6     .07       0  5058.5      .1       0
  5261.2     .12       0
Bank Sta=4950.6,5058.5
XS Rating Curve= 0 ,0
Exp/Cntr=0.3,0.1

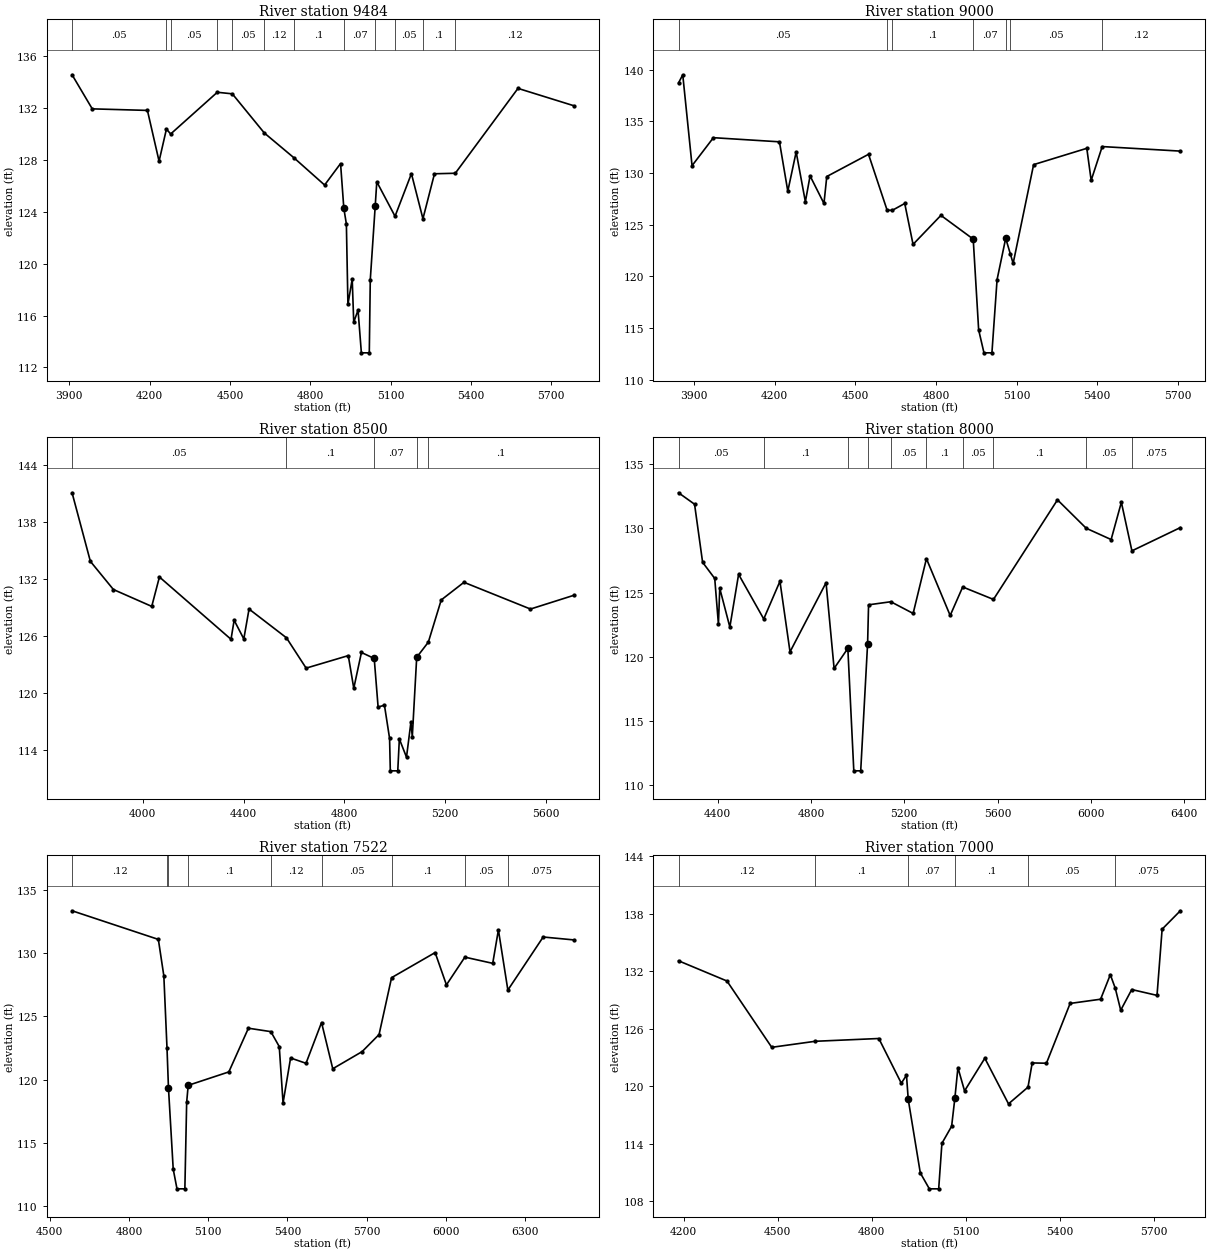
Type RM Length L Ch R = 1 ,9484    ,484,484,484
BEGIN DESCRIPTION:
STEWARTS CREEK 19.0
END DESCRIPTION:
XS GIS Cut Line= 3
       3838596.2     10093508.16      3837642.62     10094035.74
      3837353.13     10094765.09
#Sta/Elev= 30
  3910.2  134.58  3985.6  131.95  4191.7  131.83  4235.2  127.91  4262.7  130.39
  4278.5  130.01  4452.7  133.23  4508.8  133.11  4628.3  130.09  4739.2  128.17
  4853.6  126.07  4913.2  127.73  4925.4  124.27  4934.9  123.07  4940.7  116.86
  4956.7  118.81  4962.4  115.48  4978.5  116.42  4990.9  113.12  5020.5  113.12
  5024.2  118.76 5042.75  124.48  5048.5  126.32  5116.7  123.66  5177.9  126.95
  5220.9  123.47    5264  126.94  5341.8  126.98    5576  133.53  5784.7  132.19
#Mann= 12 ,-1 , 0
  3910.2     .05       0  4262.7     .12       0  4278.5     .05       0
  4452.7     .12       0  4508.8     .05       0  4628.3     .12       0
  4739.2      .1       0  4925.4     .07       0 5042.75      .1       0
  5116.7     .05       0  5220.9      .1       0  5341.8     .12       0
Bank Sta=4925.4,5042.75
XS Rating Curve= 0 ,0
Exp/Cntr=0.3,0.1

Type RM Length L Ch R = 1 ,9000    ,500,500,500
BEGIN DESCRIPTION:
STEWARTS CREEK 18.0
END DESCRIPTION:
XS GIS Cut Line= 3
      3838450.38     10093452.61      3837332.79     10093756.64
      3836998.97     10094383.15
#Sta/Elev= 30
  3841.8  138.73  3857.5  139.52  3892.1  130.72  3971.6  133.43  4217.5  133.03
  4248.6  128.25  4279.7  132.05    4314  127.23  4331.5  129.73  4383.2  127.06
  4393.7  129.67  4549.1  131.82  4618.2  126.42  4637.1  126.39  4683.9  127.06
  4714.9   123.1  4818.6  125.91 4938.84 123.611  4959.1  114.82  4978.9   112.6
  5008.5   112.6  5027.7  119.69  5059.8  123.69  5077.6  122.13  5087.5  121.26
  5163.7  130.82  5361.7   132.4    5378   129.3  5419.1  132.57  5709.9  132.13
#Mann= 7 ,-1 , 0
  3841.8     .05       0  4618.2     .12       0  4637.1      .1       0
 4938.84     .07       0  5059.8      .1       0  5077.6     .05       0
  5419.1     .12       0
Bank Sta=4938.84,5059.8
XS Rating Curve= 0 ,0
Exp/Cntr=0.3,0.1

Type RM Length L Ch R = 1 ,8500    ,500,500,500
BEGIN DESCRIPTION:
STEWARTS CREEK 17.0
END DESCRIPTION:
XS GIS Cut Line= 3
      3838429.47     10093334.57      3837167.91      10093557.5
      3836521.34     10093854.68
#Sta/Elev= 30
  3718.9  141.11  3791.6  133.88    3883  130.91  4035.3  129.13  4065.8  132.23
  4350.1  125.66  4362.5  127.67  4400.9   125.7  4421.7  128.85  4570.2  125.82
  4648.4  122.62  4815.8  123.94  4837.6   120.5    4868  124.27  4918.8  123.64
  4934.2  118.52  4959.4  118.71  4979.8  115.21  4982.7  111.79  5012.3  111.79
  5018.6  115.15    5047  113.23  5064.5  116.92    5070  115.39  5087.5  123.76
  5133.7  125.36  5184.9  129.81  5275.2  131.67  5539.3  128.85  5711.6   130.3
#Mann= 5 ,-1 , 0
  3718.9     .05       0  4570.2      .1       0  4918.8     .07       0
  5087.5     .05       0  5133.7      .1       0
Bank Sta=4918.8,5087.5
XS Rating Curve= 0 ,0
Exp/Cntr=0.3,0.1

Type RM Length L Ch R = 1 ,8000    ,478,478,478
BEGIN DESCRIPTION:
STEWARTS CREEK 16.0
END DESCRIPTION:
XS GIS Cut Line= 3
      3837547.59     10092869.27      3836880.12     10093248.95
      3835617.04     10093813.72
#Sta/Elev= 30
  4232.1  132.77  4300.8  131.88  4335.3  127.36  4387.3   126.1  4403.1  122.55
  4408.9  125.33  4452.1  122.32  4489.6  126.42  4597.4  122.95  4666.9  125.88
  4710.1  120.39  4864.6  125.77  4899.1   119.1    4958  120.66  4983.6  111.13
  5013.2  111.13 5042.74 121.032  5046.9  124.05  5142.3  124.29    5238  123.38
    5295  127.64  5396.8  123.22  5450.5  125.44  5582.4  124.47  5856.9  132.22
    5980  130.01  6086.9  129.13  6130.8  132.03    6176  128.25  6383.6  130.06
#Mann= 10 ,-1 , 0
  4232.1     .05       0  4597.4      .1       0    4958     .07       0
 5042.74     .12       0  5142.3     .05       0    5295      .1       0
  5450.5     .05       0  5582.4      .1       0    5980     .05       0
    6176    .075       0
Bank Sta=4958,5042.74
XS Rating Curve= 0 ,0
Exp/Cntr=0.3,0.1

Type RM Length L Ch R = 1 ,7522    ,522,522,522
BEGIN DESCRIPTION:
STEWARTS CREEK 15.0
END DESCRIPTION:
XS GIS Cut Line= 3
      3837221.19     10092598.45      3836887.34     10092845.98
      3835611.43     10093604.59
#Sta/Elev= 30
  4584.4  133.34  4911.1  131.08  4931.9   128.2  4943.8  122.53 4949.42 119.355
  4967.4  112.94  4981.7  111.39  5011.5  111.39  5018.3  118.22  5024.1  119.56
    5178  120.62  5252.1  124.07    5337   123.8  5368.9  122.62  5383.3  118.17
  5411.8  121.72  5470.2   121.3    5529  124.52  5571.5  120.87  5682.5  122.22
  5746.8  123.57  5794.2  128.06  5959.1  130.04  6001.9  127.49  6071.7  129.68
  6177.2  129.19  6198.7  131.83  6234.5  127.08  6368.2  131.27  6484.4  131.04
#Mann= 9 ,-1 , 0
  4584.4     .12       0  4943.8      .1       0 4949.42     .07       0
  5024.1      .1       0    5337     .12       0    5529     .05       0
  5794.2      .1       0  6071.7     .05       0  6234.5    .075       0
Bank Sta=4949.42,5024.1
XS Rating Curve= 0 ,0
Exp/Cntr=0.3,0.1

Type RM Length L Ch R = 1 ,7000    ,500,500,500
BEGIN DESCRIPTION:
STEWARTS CREEK 14.0
END DESCRIPTION:
XS GIS Cut Line= 3
      3837144.82     10092487.32      3836421.43     10092865.76
      3835661.66     10093065.14
#Sta/Elev= 30
  4183.6  133.09  4338.2  130.98  4481.1  124.06    4620  124.69    4823  124.98
  4894.8  120.31  4911.3  121.15  4916.9  118.62  4955.4  110.95  4984.3  109.29
  5014.1  109.29  5024.4  114.04  5055.4  115.82  5065.7  118.74  5075.5  121.94
  5096.7  119.51  5161.4  122.92    5237  118.16  5299.2   119.9  5312.6  122.43
  5358.1   122.4  5433.7  128.64    5531  129.08    5562  131.64  5577.9  130.22
  5595.2  127.93  5630.4  130.09  5711.1  129.48  5727.4  136.39  5785.5  138.31
#Mann= 6 ,-1 , 0
  4183.6     .12       0    4620      .1       0  4916.9     .07       0
  5065.7      .1       0  5299.2     .05       0  5577.9    .075       0
Bank Sta=4916.9,5065.7
XS Rating Curve= 0 ,0
Exp/Cntr=0.3,0.1