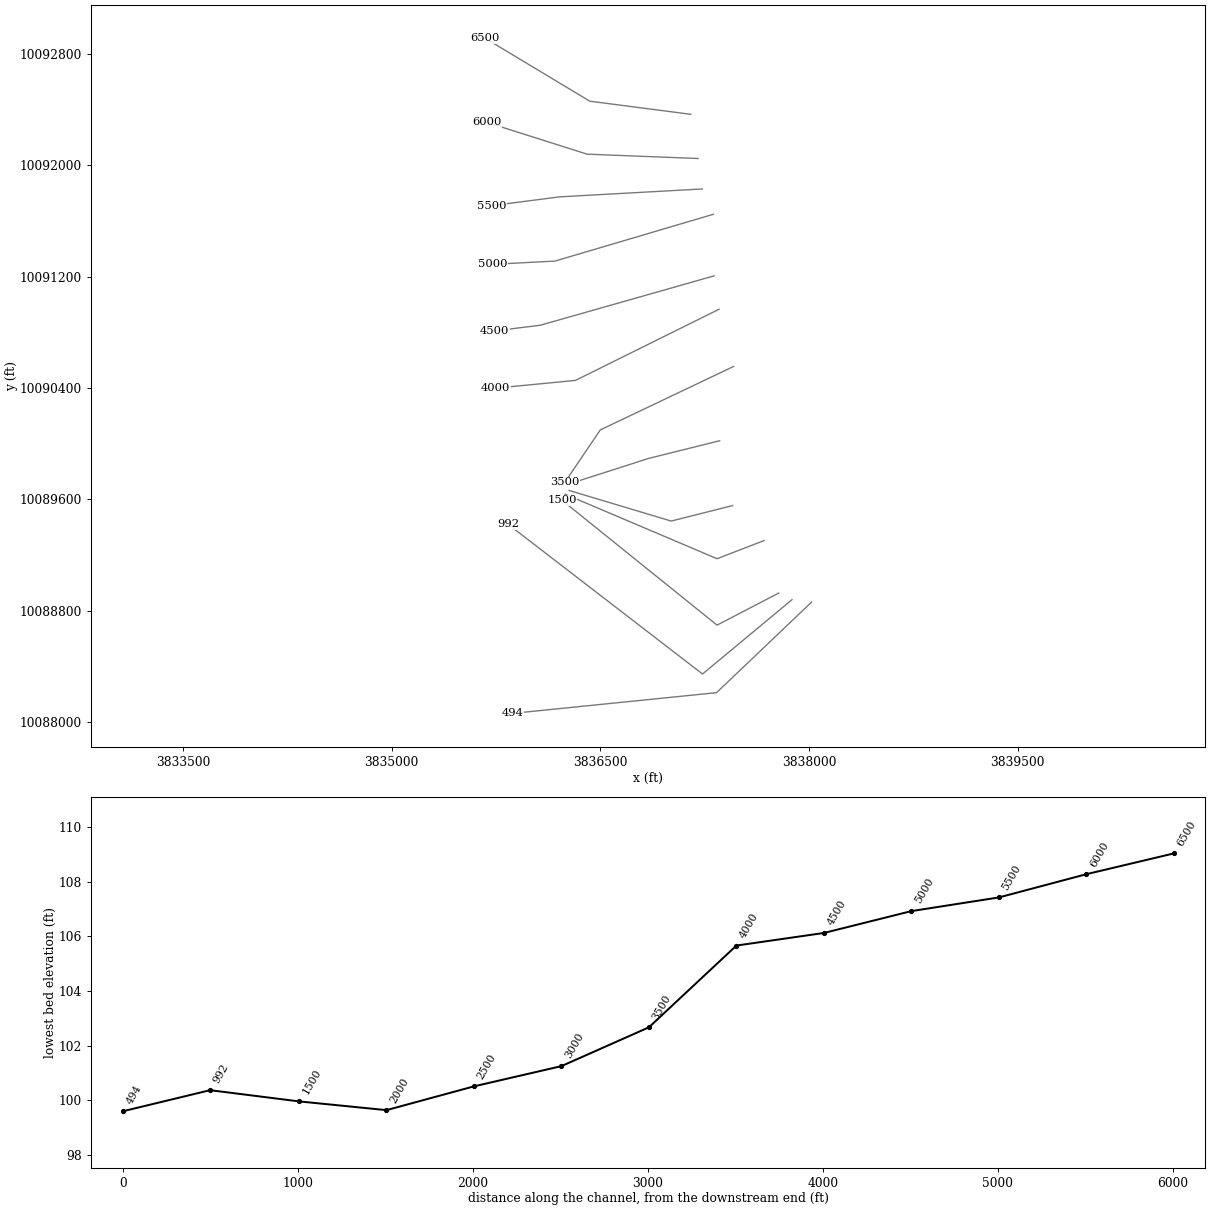
HEC-RAS study STEWARTS CREEK.prj: STEWARTS CREEK Base Level Engineering

--- STEWARTS CREEK.g10 (geometry) --- (continued)

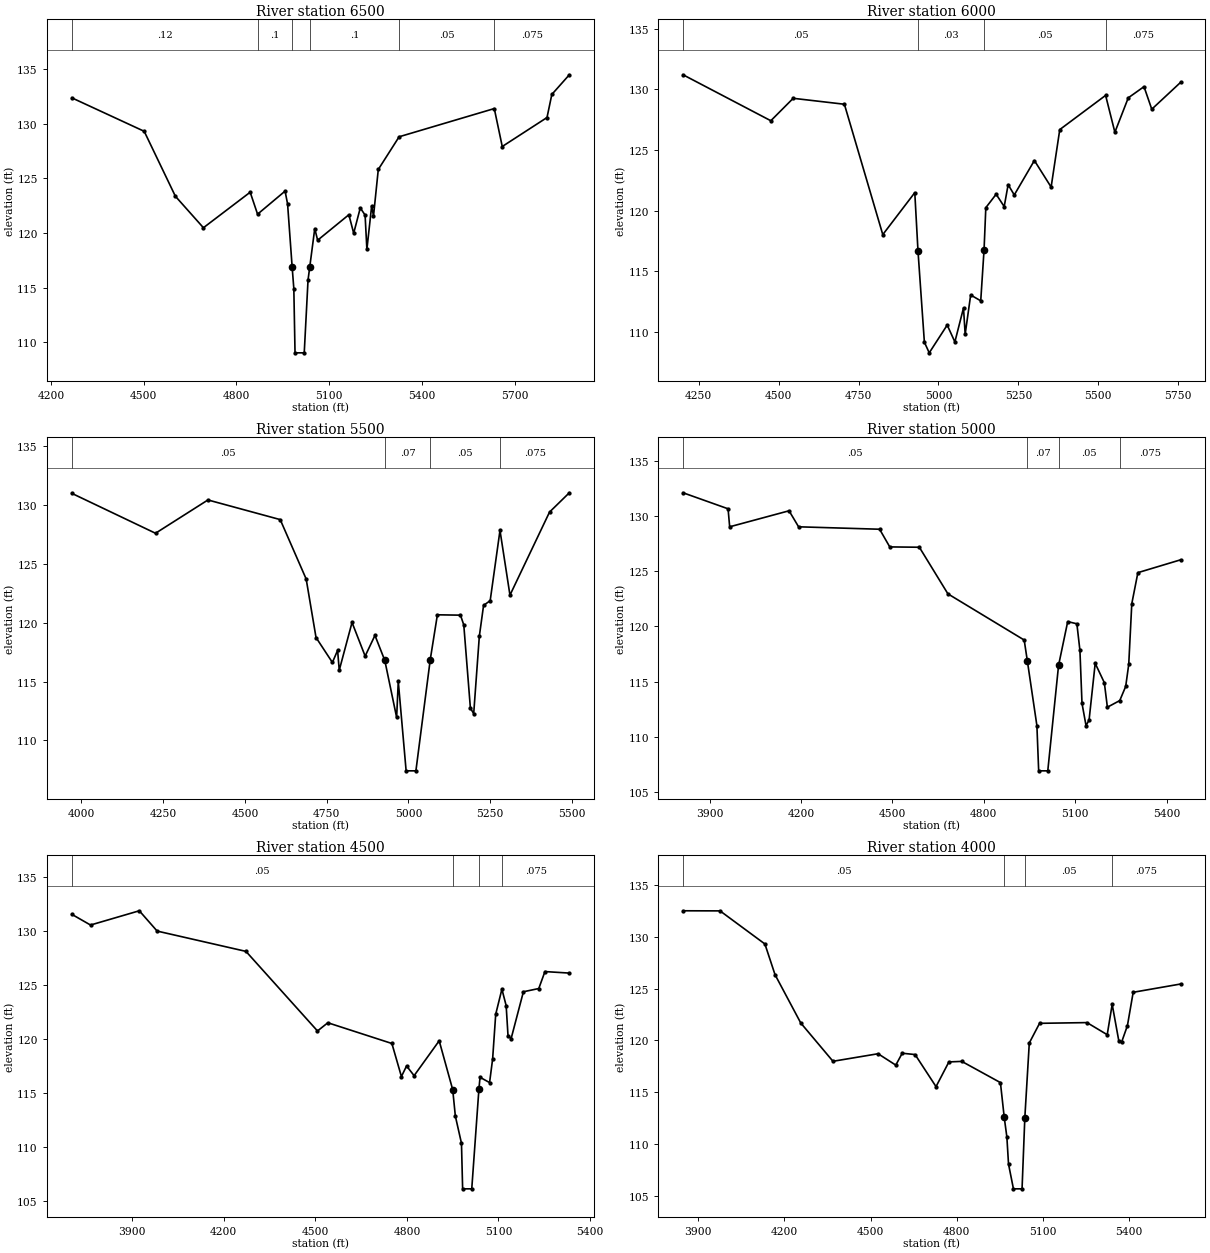
Type RM Length L Ch R = 1 ,6500    ,500,500,500
BEGIN DESCRIPTION:
STEWARTS CREEK 13.0
END DESCRIPTION:
XS GIS Cut Line= 3
      3837150.02     10092367.55      3836423.43     10092461.98
      3835671.88     10092913.79
#Sta/Elev= 30
  4267.3  132.35  4501.4  129.29  4602.3  123.35    4693  120.47  4844.3  123.72
  4868.2  121.71  4957.2  123.82  4965.3  122.65  4980.2 116.836  4985.5  114.91
  4989.4  109.03  5019.2  109.03  5031.5   115.7  5037.1 116.895  5053.2  120.39
  5062.6  119.33  5163.6  121.66  5179.2  119.97  5200.5  122.28  5216.1  121.63
  5221.9  118.49  5237.4  122.48  5243.3  121.54  5258.8   125.8  5326.2  128.79
  5634.1  131.37  5659.9   127.9  5804.7  130.55  5820.3  132.66  5876.9  134.46
#Mann= 6 ,-1 , 0
  4267.3     .12       0  4868.2      .1       0  4980.2     .07       0
  5037.1      .1       0  5326.2     .05       0  5634.1    .075       0
Bank Sta=4980.2,5037.1
XS Rating Curve= 0 ,0
Exp/Cntr=0.3,0.1

Type RM Length L Ch R = 1 ,6000    ,500,500,500
BEGIN DESCRIPTION:
STEWARTS CREEK 12.0
END DESCRIPTION:
XS GIS Cut Line= 3
      3837202.11     10092049.84      3836403.92     10092081.22
      3835682.01     10092310.02
#Sta/Elev= 30
  4201.2   131.2  4475.7  127.41  4545.7  129.26  4705.8  128.77  4825.9  118.02
    4926  121.48    4936  116.68    4956  109.15  4971.2  108.27  5027.4  110.56
  5051.4  109.17  5078.4  111.97  5083.6   109.8  5100.8  113.04  5132.3  112.56
  5142.7  116.78  5148.2  120.24  5180.5  121.35  5205.7  120.33    5218  122.14
  5237.2  121.29  5300.1  124.13  5352.5  121.94  5379.5  126.68  5522.9   129.5
  5551.9  126.46  5593.8   129.3    5643  130.22  5667.3  128.36  5757.3  130.57
#Mann= 4 ,-1 , 0
  4201.2     .05       0    4936     .03       0  5142.7     .05       0
  5522.9    .075       0
Bank Sta=4936,5142.7
XS Rating Curve= 0 ,0
Exp/Cntr=0.3,0.1

Type RM Length L Ch R = 1 ,5500    ,500,500,500
BEGIN DESCRIPTION:
STEWARTS CREEK 11.0
END DESCRIPTION:
XS GIS Cut Line= 3
      3837233.28     10091831.09      3836205.76     10091774.14
      3835717.82     10091711.07
#Sta/Elev= 30
  3970.9     131  4226.7  127.61    4387  130.44    4608  128.77  4687.4  123.72
  4717.5  118.75  4767.6  116.63  4783.5  117.66  4788.5  115.97  4827.6  120.03
  4867.7  117.17  4897.7  118.93  4927.8   116.8    4964  111.96    4969  115.02
    4993  107.42  5022.9  107.42  5066.8  116.88  5088.6  120.68  5159.2  120.65
  5169.3  119.82  5189.5  112.75  5199.6  112.28  5216.8  118.85  5229.8  121.48
    5250  121.88    5280  127.85  5310.5  122.35  5431.5  129.41    5492  131.05
#Mann= 4 ,-1 , 0
  3970.9     .05       0  4927.8     .07       0  5066.8     .05       0
    5280    .075       0
Bank Sta=4927.8,5066.8
XS Rating Curve= 0 ,0
Exp/Cntr=0.3,0.1

Type RM Length L Ch R = 1 ,5000    ,500,500,500
BEGIN DESCRIPTION:
STEWARTS CREEK 10.0
END DESCRIPTION:
XS GIS Cut Line= 3
      3837311.45      10091648.8      3836172.99     10091312.48
      3835728.08     10091289.42
#Sta/Elev= 30
  3812.9  132.09  3960.6  130.64  3965.8  129.01  4160.7  130.46    4192  129.01
  4457.9  128.79  4491.2  127.19  4588.3  127.16  4682.1  122.94  4932.4  118.76
  4942.8  116.86  4974.1  111.01  4979.9  106.92  5009.8  106.92  5045.2  116.47
  5075.2  120.43  5105.3  120.23  5115.3  117.82  5122.1  113.03  5135.3  111.02
  5145.3  111.51  5165.4  116.65  5195.4   114.9  5205.4  112.68    5246  113.28
  5265.5  114.56  5275.5  116.56  5285.5  122.05  5305.5  124.86  5445.5  126.02
#Mann= 4 ,-1 , 0
  3812.9     .05       0  4942.8     .07       0  5045.2     .05       0
    5246    .075       0
Bank Sta=4942.8,5045.2
XS Rating Curve= 0 ,0
Exp/Cntr=0.3,0.1

Type RM Length L Ch R = 1 ,4500    ,500,500,500
BEGIN DESCRIPTION:
STEWARTS CREEK 9.0
END DESCRIPTION:
XS GIS Cut Line= 3
      3837316.68      10091206.1      3836068.16     10090851.48
      3835738.53     10090810.26
#Sta/Elev= 30
  3702.1  131.54  3763.3  130.55  3923.1  131.87  3981.6  129.99  4272.6  128.11
    4507  120.74  4540.9   121.5  4750.8  119.58    4782  116.52  4798.9   117.5
  4823.6   116.6  4905.8  119.83  4950.1   115.3  4958.7  112.86  4978.8  110.34
  4982.6  106.12  5012.5  106.12 5035.97 115.361  5039.6  116.45  5070.9  115.96
  5080.9  118.15    5091  122.29  5111.3  124.61  5125.2  123.09  5131.3  120.31
  5141.4  120.02  5181.7  124.37  5232.1  124.67  5252.3  126.24  5332.2   126.1
#Mann= 4 ,-1 , 0
  3702.1     .05       0  4950.1     .05       0 5035.97     .05       0
  5111.3    .075       0
Bank Sta=4950.1,5035.97
XS Rating Curve= 0 ,0
Exp/Cntr=0.3,0.1

Type RM Length L Ch R = 1 ,4000    ,500,500,500
BEGIN DESCRIPTION:
STEWARTS CREEK 8.0
END DESCRIPTION:
XS GIS Cut Line= 3
      3837353.15     10090966.52      3836320.21     10090454.67
      3835743.71      10090398.8
#Sta/Elev= 30
  3847.2  132.54  3975.9  132.53  4132.1  129.33  4167.4  126.36    4257  121.69
  4369.1  117.99  4526.1  118.72  4587.8  117.62  4610.2  118.77    4655  118.64
  4727.9  115.54  4772.7  117.93  4817.6  117.98  4952.1  115.93  4965.3 112.583
  4974.5  110.68  4980.3  108.05  4997.4  105.66  5027.4  105.66  5037.1 112.553
  5052.6  119.76  5088.4  121.66  5253.5  121.73  5323.9  120.56  5341.2  123.49
  5364.1  119.99  5374.1  119.85  5394.2  121.43  5414.3  124.66  5579.2  125.46
#Mann= 4 ,-1 , 0
  3847.2     .05       0  4965.3     .07       0  5037.1     .05       0
  5341.2    .075       0
Bank Sta=4965.3,5037.1
XS Rating Curve= 0 ,0
Exp/Cntr=0.3,0.1

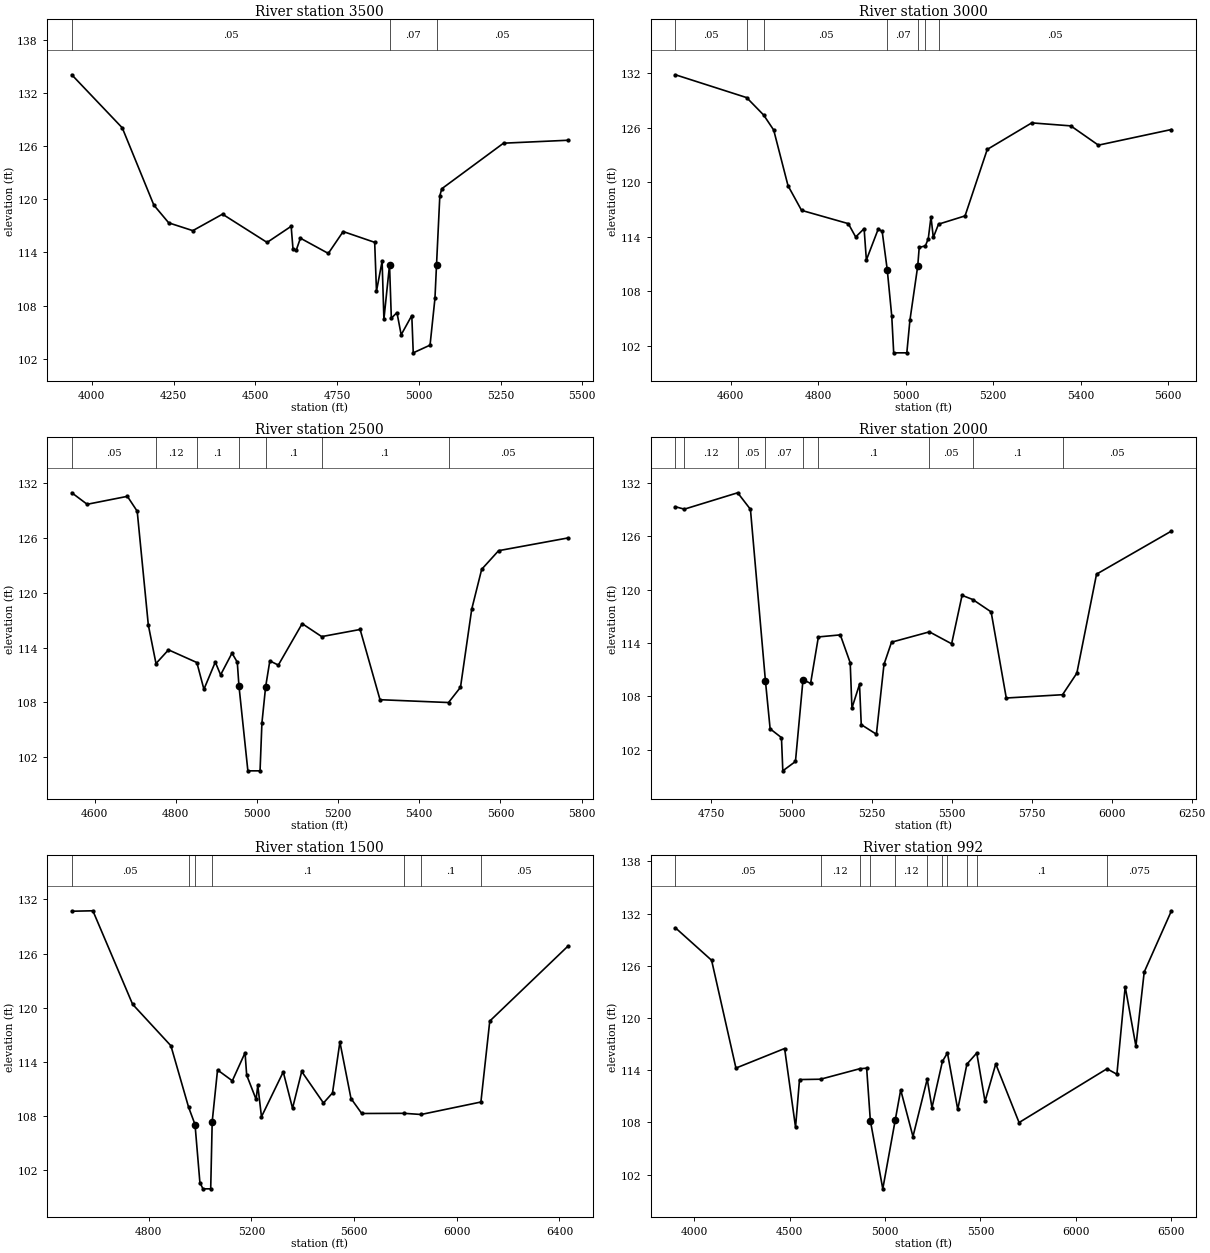
Type RM Length L Ch R = 1 ,3500    ,500,500,500
BEGIN DESCRIPTION:
STEWARTS CREEK 7.0
END DESCRIPTION:
XS GIS Cut Line= 3
      3837457.25     10090555.03      3836499.08      10090098.9
      3836243.74      10089721.7
#Sta/Elev= 30
  3938.8  134.05  4093.2  128.06  4189.8  119.34  4235.2  117.34  4308.9  116.46
  4399.7  118.32    4536  115.13  4609.6  116.95  4615.2   114.4  4624.8  114.22
  4637.9  115.61  4723.2  113.89  4768.6  116.36    4865  115.14  4870.5  109.63
  4887.7  113.01  4893.2  106.46  4910.4  112.59  4915.9  106.58  4933.1  107.21
    4946  104.71  4978.5  106.88  4982.9  102.67  5034.3  103.54  5049.3  108.82
 5054.13 112.627  5064.2   120.4  5070.2  121.19  5258.9  126.33  5455.5  126.66
#Mann= 3 , 0 , 0
  3938.8     .05       0  4910.4     .07       0 5054.13     .05       0
Bank Sta=4910.4,5054.13
XS Rating Curve= 0 ,0
Exp/Cntr=0.3,0.1

Type RM Length L Ch R = 1 ,3000    ,500,500,500
BEGIN DESCRIPTION:
STEWARTS CREEK 6.0
END DESCRIPTION:
XS GIS Cut Line= 3
      3837357.42     10090021.19      3836847.12     10089894.04
       3836268.9     10089708.69
#Sta/Elev= 30
  4474.1  131.83  4636.8  129.32  4675.7   127.4  4698.6  125.75  4731.3  119.63
  4762.2  116.92    4869  115.46  4885.9  113.99  4905.1  114.91  4910.3  111.46
  4937.4  114.87  4946.4   114.6    4958  110.38  4968.3  105.27  4972.7  101.25
  5002.7  101.25  5009.7  104.81 5027.64 110.808    5031  112.85  5045.1  113.01
  5051.7  113.81  5057.9   116.2  5063.2  113.94  5075.1   115.4  5135.7  116.31
  5186.4  123.62  5288.1  126.54  5377.3  126.21  5440.3  124.09  5607.2  125.81
#Mann= 7 ,-1 , 0
  4474.1     .05       0  4636.8      .1       0  4675.7     .05       0
    4958     .07       0 5027.64     .05       0  5045.1      .1       0
  5075.1     .05       0
Bank Sta=4958,5027.64
XS Rating Curve= 0 ,0
Exp/Cntr=0.3,0.1

Type RM Length L Ch R = 1 ,2500    ,500,500,500
BEGIN DESCRIPTION:
STEWARTS CREEK 5.0
END DESCRIPTION:
XS GIS Cut Line= 3
      3837450.74     10089555.04      3837008.35     10089443.65
      3836274.59     10089663.55
#Sta/Elev= 30
  4543.8  130.96  4581.7   129.7  4680.8  130.57    4705  128.94  4732.4  116.48
  4751.3  112.26  4782.1  113.76    4852  112.37  4869.4  109.44  4897.4  112.42
  4910.5  111.02  4938.6   113.4  4951.6  112.41 4955.64 109.844  4977.7  100.51
  5007.7  100.51  5012.3  105.75  5021.4   109.7  5031.8  112.55  5052.7  112.09
  5111.5  116.63  5159.6  115.21  5254.3  115.99  5303.3   108.3  5472.1  107.99
  5501.6  109.66  5529.3  118.22  5553.8  122.58  5595.5  124.62    5766  126.01
#Mann= 7 ,-1 , 0
  4543.8     .05       0  4751.3     .12       0    4852      .1       0
 4955.64     .07       0  5021.4      .1       0  5159.6      .1       0
  5472.1     .05       0
Bank Sta=4955.64,5021.4
XS Rating Curve= 0 ,0
Exp/Cntr=0.3,0.1

Type RM Length L Ch R = 1 ,2000    ,500,500,500
BEGIN DESCRIPTION:
STEWARTS CREEK 4.0
END DESCRIPTION:
XS GIS Cut Line= 3
      3837676.52     10089303.33      3837338.16     10089172.98
      3836245.85     10089636.81
#Sta/Elev= 30
  4637.4   129.3  4665.2  129.03  4831.8  130.87  4871.7  129.01 4918.56 109.721
  4933.2  104.36  4968.6  103.37  4972.8   99.64  5012.3  100.69  5035.9  109.88
  5059.6  109.46  5083.9  114.68  5152.4  114.91  5183.3  111.78  5188.7  106.69
  5212.4  109.36  5217.8  104.83  5265.1  103.75  5288.8  111.59  5312.4  114.09
  5430.7  115.25  5500.1  113.91  5532.7  119.35  5566.2  118.88  5623.5  117.49
  5670.8  107.82  5846.5  108.19  5891.2  110.61  5952.7  121.73  6186.7  126.57
#Mann= 9 ,-1 , 0
  4637.4     .05       0  4665.2     .12       0  4831.8     .05       0
 4918.56     .07       0  5035.9     .05       0  5083.9      .1       0
  5430.7     .05       0  5566.2      .1       0  5846.5     .05       0
Bank Sta=4918.56,5035.9
XS Rating Curve= 0 ,0
Exp/Cntr=0.3,0.1

Type RM Length L Ch R = 1 ,1500    ,508,508,508
BEGIN DESCRIPTION:
STEWARTS CREEK 3.0
END DESCRIPTION:
XS GIS Cut Line= 3
      3837781.74     10088926.15      3837338.37     10088695.46
      3836222.68     10089593.96
#Sta/Elev= 30
  4500.2  130.69  4582.4  130.74  4737.2  120.39  4886.3   115.8  4955.1  109.01
  4980.3  107.08  4999.3  100.65  5011.3   99.96  5041.4   99.96  5047.2  107.39
    5068  113.12  5125.6  111.92  5175.2  115.02  5181.6  112.54  5218.3  109.86
  5224.8  111.41  5239.2  107.94    5324   112.9  5360.2  108.88  5395.9  112.95
  5480.7  109.46  5515.9  110.58  5544.7  116.21  5587.9  109.96  5629.8   108.3
  5794.6  108.32  5860.9  108.19    6094  109.57  6128.5  118.53  6432.5  126.81
#Mann= 7 ,-1 , 0
  4500.2     .05       0  4955.1      .1       0  4980.3     .07       0
  5047.2      .1       0  5794.6     .05       0  5860.9      .1       0
    6094     .05       0
Bank Sta=4980.3,5047.2
XS Rating Curve= 0 ,0
Exp/Cntr=0.3,0.1

Type RM Length L Ch R = 1 ,992     ,498,498,498
BEGIN DESCRIPTION:
STEWARTS CREEK 2.0
END DESCRIPTION:
XS GIS Cut Line= 3
       3837877.2      10088878.4      3837233.76     10088344.11
      3835836.18     10089420.51
#Sta/Elev= 30
    3901  130.37  4090.6  126.64  4218.2  114.25  4473.4   116.5  4530.7  107.45
  4551.5  112.93  4661.8  112.97  4866.5  114.17  4903.5  114.24 4922.81 108.224
  4988.1  100.37    5053  108.23    5082  111.74  5146.3  106.38    5221  112.98
    5246   109.7  5300.7  115.02  5327.1  115.99    5381   109.5    5429   114.7
  5480.7  115.98  5524.1  110.43  5580.3  114.72  5702.6  107.99  6163.4  114.17
  6215.4  113.54  6258.9   123.6  6315.1  116.77  6358.6  125.29  6501.4  132.33
#Mann= 11 ,-1 , 0
    3901     .05       0  4661.8     .12       0  4866.5      .1       0
 4922.81     .07       0    5053     .12       0    5221      .1       0
  5300.7     .12       0  5327.1      .1       0    5429     .12       0
  5480.7      .1       0  6163.4    .075       0
Bank Sta=4922.81,5053
XS Rating Curve= 0 ,0
Exp/Cntr=0.3,0.1

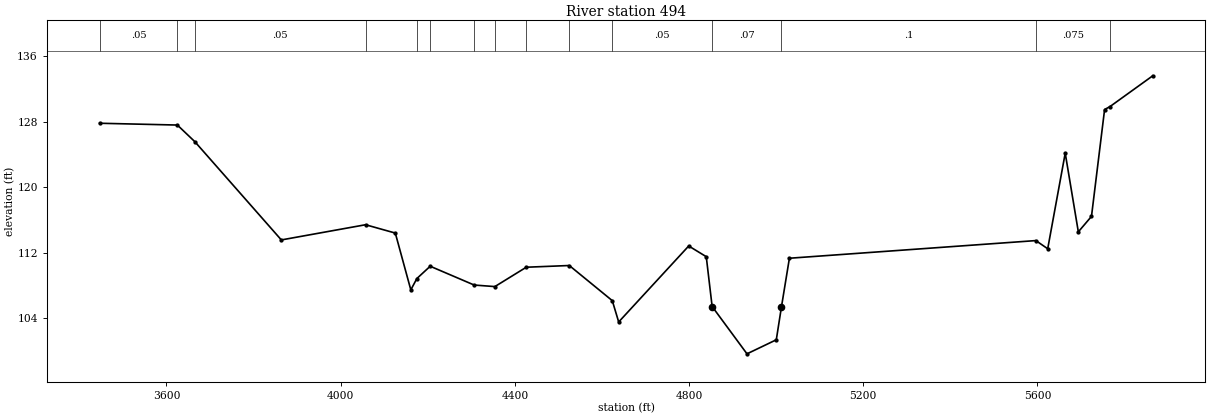
Type RM Length L Ch R = 1 ,494     ,0,0,0
BEGIN DESCRIPTION:
STEWARTS CREEK 1.0
END DESCRIPTION:
XS GIS Cut Line= 3
      3838017.85     10088861.07      3837334.68       10088210.
      3835867.85     10088061.07
#Sta/Elev= 30
  3446.6  127.82  3625.1   127.6  3665.3  125.56  3863.8  113.54  4057.2   115.4
  4125.5  114.38  4161.1  107.43  4175.1  108.82  4205.6  110.32  4306.6  108.02
  4354.1  107.83  4426.2   110.2    4525  110.41  4623.7  106.11  4638.4   103.5
  4799.2   112.8  4839.5  111.49 4852.98 105.391    4933    99.6  5000.3  101.32
 5012.18 105.362  5030.4   111.3  5596.3  113.46  5623.5  112.46  5663.7  124.16
  5693.8  114.53    5724  116.42  5754.1   129.5  5766.2  129.85  5864.7  133.63
#Mann= 15 ,-1 , 0
  3446.6     .05       0  3625.1     .12       0  3665.3     .05       0
  4057.2     .12       0  4175.1     .05       0  4205.6      .1       0
  4306.6     .05       0  4354.1     .12       0  4426.2     .05       0
    4525     .12       0  4623.7     .05       0 4852.98     .07       0
 5012.18      .1       0  5596.3    .075       0  5766.2      .1       0
Bank Sta=4852.98,5012.18
XS Rating Curve= 0 ,0
Exp/Cntr=0.3,0.1