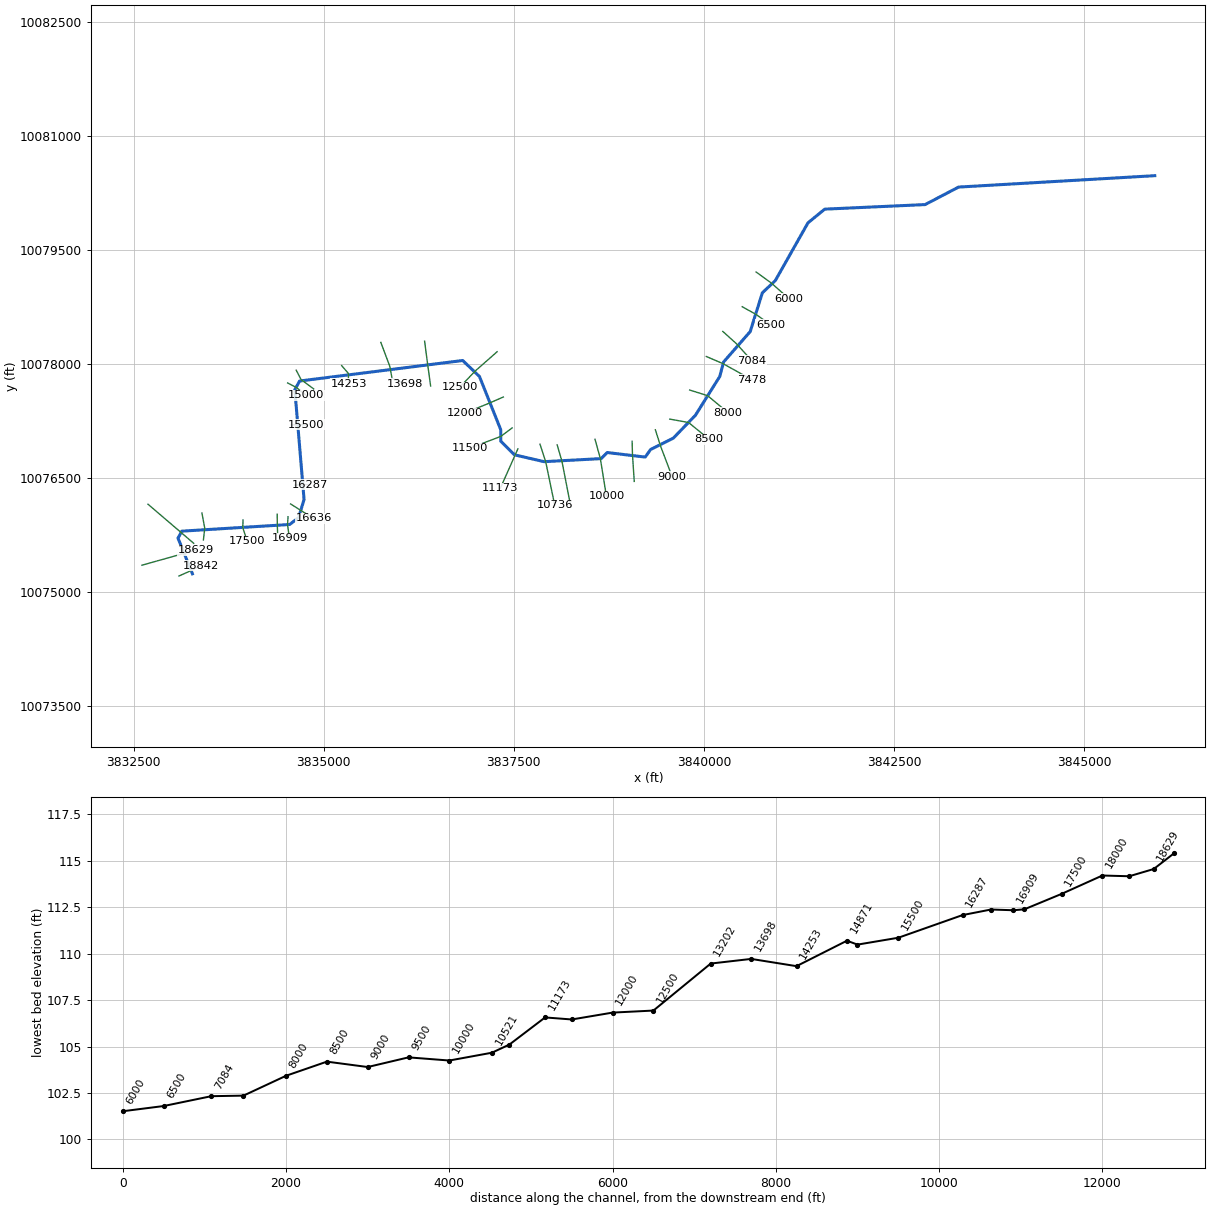
--- TRADE CTR DITCH_COLLEGE PK DITCH.prj (project) ---

Proj Title=TRADE CTR DITCH_COLLEGE PK DITCH Base Level Engineering
Current Plan=p01
Default Exp/Contr=0.3,0.1
English Units
Geom File=g01
Flow File=f01
Plan File=p01
Y Axis Title=Elevation
X Axis Title(PF)=Main Channel Distance
X Axis Title(XS)=Station
BEGIN DESCRIPTION:
TRADE CTR DITCH_COLLEGE PK DITCH
END DESCRIPTION:
DSS File=dss
DSS Export Rating Curves= 0
DSS Export Rating Curve Sorted= 0
DSS Export Volume Flow Curves= 0
DXF OffsetX= 0
DXF OffsetY= 0
DXF ScaleX= 1
DXF ScaleY= 10

--- TRADE CTR DITCH_COLLEGE PK DITCH.p01 (plan) ---

Plan Title=Multiple Run
Program Version=4.10
Short Identifier=Multiple Run
Geom File=g01
Flow File=f01
Subcritical Flow
K Sum by GR= 0
Std Step Tol= 0.01
Critical Tol= 0.01
Num of Std Step Trials= 20
Max Error Tol= 0.3
Flow Tol Ratio= 0.001
Split Flow NTrial= 30
Split Flow Tol= 0.02
Split Flow Ratio= 0.02
Log Output Level= 0
Friction Slope Method= 1
Unsteady Friction Slope Method= 2
Unsteady Bridges Friction Slope Method= 1
Parabolic Critical Depth
Global Vel Dist= 1 , 1 , 1
Global Log Level= 0
CheckData=True
Encroach Param=-1 ,0,0, 0
BEGIN DESCRIPTION:
Multiple Run
END DESCRIPTION:
Computation Interval=1HOUR
Output Interval=1HOUR
Run HTab= 0
Run UNet= 0
Run PostProcess= 0
Run WQNet= 0
UNET Theta= 1
UNET Theta Warmup= 1
UNET ZTol= 0.02
UNET ZSATol= 0.05
UNET MxIter= 20
UNET MaxInSteps= 0
UNET DtIC= 0
UNET DtMin= 0
UNET MaxCRTS= 20
UNET WFStab= 2
UNET SFStab= 1
UNET WFX= 1
UNET SFX= 1
UNET DSS MLevel= 4
UNET DZMax Abort= 100
UNET Convert EG Bridges= 0
UNET Use Existing IB Tables=-1
UNET Froude Reduction=False
UNET Froude Limit= 1
UNET Froude Power= 10
UNET Time Slicing=0,0, 5
UNET Junction Losses=0
Instantaneous Interval=1HOUR
DSS File=dss
Write IC File= 0
Write IC File at Sim End=0
Echo Input=False
Echo Parameters=False
Echo Output=False
Write Detailed= 0
WQ AD Non Conservative
WQ ULTIMATE=-1
WQ Max Comp Step=1HOUR
WQ Output Interval=15MIN
WQ Output Selected Increments= 0
WQ Output face flow=0
WQ Output face velocity=0
WQ Output face area=0
WQ Output face dispersion=0
WQ Output cell volume=0
WQ Output cell surface area=0
WQ Output cell continuity=0
WQ Output cumulative cell continuity=0
WQ Output face conc=0
WQ Output face dconc_dx=0
WQ Output face courant=0
WQ Output face peclet=0
WQ Output face adv mass=0
WQ Output face disp mass=0
WQ Output cell mass=0
WQ Output cell source sink temp=0
WQ Output cell source sink nsm=0
WQ Output MaxMinRange=-1
WQ Daily Max Min Mean=-1
WQ Daily Range=0
WQ Daily Time=0
WQ Create Restart=0
WQ Fixed Restart=0
WQ System Summary=0
WQ Use Fixed Temperature=0
Sorting and Armoring Iterations= 10
XS Update Threshold= 0.02
Hydraulics Update Threshold= 0.02
Energy Slope Method= 1
Volume Change Method= 0
XS Weighting Method= 0
Number of US Weighted Cross Sections= 1
Number of DS Weighted Cross Sections= 1
Upstream XS Weight=0.25
Main XS Weight=0.5
Downstream XS Weight=0.25
Number of DS XS's Weighted with US Boundary= 1
Upstream Boundary Weight= 1
Weight of XSs Associated with US Boundary= 0
Number of US XS's Weighted with DS Boundary= 1
Downstream Boundary Weight= 0.5
Weight of XSs Associated with DS Boundary= 0.5
Sediment Output Level= 4
Mass or Volume Output= 0
Output Increment Type= 1
Profile and TS Output Increment= 10
XS Output Flag= 0
XS Output Increment= 10
Disregard all LS=0
Disregard all Conn=0
Disregard all Breaches=0
Disregard all Pumps=0

--- TRADE CTR DITCH_COLLEGE PK DITCH.f01 (steady flow) ---

Flow Title=Multiple
Program Version=4.10
Number of Profiles= 7
Profile Names=10-year,25-year,50-year,1pct_min,100-year,1pct_plu,500-year
River Rch & RM=TRADE CTR DITCH_,Reach-1         ,18842
     471     615     813     353    1066    3219    1895
River Rch & RM=TRADE CTR DITCH_,Reach-1         ,18329
     790    1060    1421     627    1892    5714    3461
River Rch & RM=TRADE CTR DITCH_,Reach-1         ,14871
    1176    1627    2230    1003    3030    9150    5784
River Rch & RM=TRADE CTR DITCH_,Reach-1         ,13698
    1309    1802    2461    1102    3328   10050    6290
River Rch & RM=TRADE CTR DITCH_,Reach-1         ,12000
    1199    1615    2172     956    2887    8719    5280
River Rch & RM=TRADE CTR DITCH_,Reach-1         ,2500
    1242    1669    2239     983    2969    8966    5403
Boundary for River Rch & Prof#=TRADE CTR DITCH_,Reach-1         , 1
Up Type= 0
Dn Type= 3
Dn Slope=0.005
Boundary for River Rch & Prof#=TRADE CTR DITCH_,Reach-1         , 2
Up Type= 0
Dn Type= 3
Dn Slope=0.005
Boundary for River Rch & Prof#=TRADE CTR DITCH_,Reach-1         , 3
Up Type= 0
Dn Type= 3
Dn Slope=0.005
Boundary for River Rch & Prof#=TRADE CTR DITCH_,Reach-1         , 4
Up Type= 0
Dn Type= 3
Dn Slope=0.005
Boundary for River Rch & Prof#=TRADE CTR DITCH_,Reach-1         , 5
Up Type= 0
Dn Type= 3
Dn Slope=0.005
Boundary for River Rch & Prof#=TRADE CTR DITCH_,Reach-1         , 6
Up Type= 0
Dn Type= 3
Dn Slope=0.005
Boundary for River Rch & Prof#=TRADE CTR DITCH_,Reach-1         , 7
Up Type= 0
Dn Type= 3
Dn Slope=0.005
DSS Import GetInterval= 0
DSS Import GetPeak= 0
DSS Import FillOption= 0

--- TRADE CTR DITCH_COLLEGE PK DITCH.g01 (geometry) ---

Geom Title=Existing Conditions
Program Version=4.10

River Reach=TRADE CTR DITCH_,Reach-1
Reach XY= 30
      3833274.26      10075242.5      3833084.33     10075711.66
      3833134.72     10075802.94      3834553.07     10075890.89
      3834670.44     10075982.05      3834742.02     10076219.96
      3834620.56     10077663.23      3834683.39     10077777.03
      3836828.24     10078046.86      3837048.24     10077836.86
      3837328.24     10077136.86      3837328.24     10076986.86
      3837508.24     10076806.86      3837898.24     10076716.86
      3838648.24     10076756.86      3838728.24     10076836.86
      3839228.24     10076776.86      3839298.24     10076876.86
      3839598.24     10077026.86      3839888.24     10077326.86
      3840208.24     10077836.86      3840258.24     10078026.86
      3840608.24     10078426.86      3840768.24     10078936.86
      3840938.24     10079096.86      3841368.24     10079856.86
      3841588.24     10080036.86      3842908.24     10080096.86
      3843348.24     10080326.86      3845928.24     10080476.86

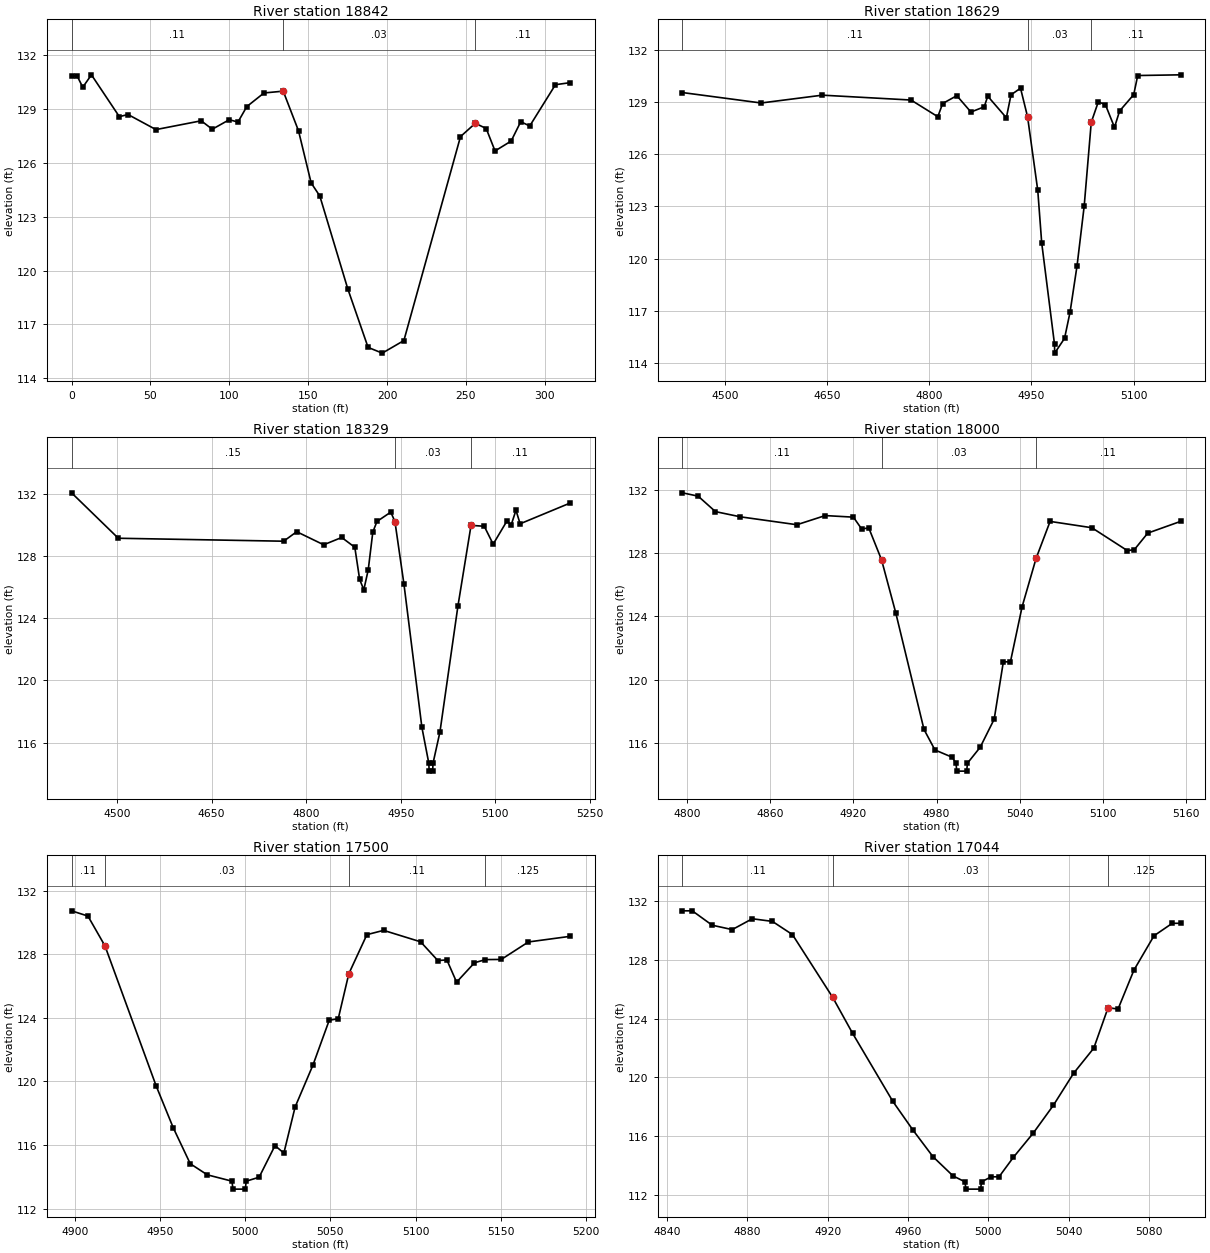
Type RM Length L Ch R = 1 ,18842   ,247,247,247
XS GIS Cut Line= 3
       3833096.4     10075213.17      3833260.57     10075286.38
      3833380.62     10075350.41
#Sta/Elev= 30
       0  130.84     3.5  130.84     7.1  130.21    12.6   130.9    30.3  128.57
    35.8  128.69    53.5  127.85    82.2  128.34    89.2  127.87     100   128.4
   105.5  128.27   111.1  129.13     122  129.89   134.2  129.99   143.9  127.78
   151.9  124.88   157.4  124.15   175.1  118.99     188  115.72     197   115.4
   210.7   116.1   246.6  127.46     256   128.2   262.9  127.91   268.5  126.66
   278.7  127.21   284.8  128.29   290.5  128.05   306.8  130.35   315.8  130.46
#Mann= 3 , 0 , 0
       0     .11       0   134.2     .03       0     256     .11       0
Bank Sta=134.2,256
XS Rating Curve= 0 ,0
Exp/Cntr=0.3,0.1

Type RM Length L Ch R = 1 ,18629   ,300,300,300
BEGIN DESCRIPTION:
Mapping XS 729a8b13
END DESCRIPTION:
XS GIS Cut Line= 2
      3832610.17     10075355.27      3833313.95     10075552.88
#Sta/Elev= 30
  4437.9  129.55  4553.4  128.95  4643.2   129.4  4773.4  129.12  4812.7  128.16
  4819.8  128.92  4840.6  129.37  4861.3  128.43  4880.8  128.73    4886  129.34
  4913.3   128.1  4920.1  129.42  4934.1   129.8  4944.4  128.16  4959.4  123.92
  4965.2  120.89    4984  115.06  4984.2  114.56  4998.7  115.41  5006.8  116.92
  5017.1   119.6  5027.5  123.01  5037.9  127.84  5048.3  129.02  5058.7  128.85
    5072  127.55  5079.5  128.49  5100.2  129.43  5106.1  130.53  5168.9  130.57
#Mann= 3 , 0 , 0
  4437.9     .11       0  4944.4     .03       0  5037.9     .11       0
Bank Sta=4944.4,5037.9
XS Rating Curve= 0 ,0
Exp/Cntr=0.3,0.1

Type RM Length L Ch R = 1 ,18329   ,329,329,329
BEGIN DESCRIPTION:
Mapping XS f0aa4bc0
END DESCRIPTION:
XS GIS Cut Line= 2
      3832690.02     10076157.38      3833290.78     10075643.43
#Sta/Elev= 30
  4427.6  132.06  4501.8  129.14  4764.2  128.95    4785  129.56  4827.8  128.72
  4856.4  129.19  4877.2  128.56  4884.9  126.49  4891.5  125.83  4898.5  127.11
  4905.8  129.54  4912.4  130.22  4934.3  130.82  4940.9  130.21  4955.2  126.19
  4983.7  116.98  4994.7  114.67  4995.2  114.17  5000.8  114.17  5001.3  114.67
  5012.3  116.68  5040.8  124.76  5061.7  129.97  5082.7  129.91  5096.8  128.76
  5118.7  130.25  5125.3  129.98    5133  130.94  5139.6  130.07  5218.2  131.39
#Mann= 3 , 0 , 0
  4427.6     .15       0  4940.9     .03       0  5061.7     .11       0
Bank Sta=4940.9,5061.7
XS Rating Curve= 0 ,0
Exp/Cntr=0.3,0.1

Type RM Length L Ch R = 1 ,18000   ,500,500,500
BEGIN DESCRIPTION:
TRADE CTR DITCH_COLLEGE PK DITCH 36.0
END DESCRIPTION:
XS GIS Cut Line= 3
      3833399.02     10076042.19      3833436.22     10075842.43
      3833418.55     10075687.63
#Sta/Elev= 30
  4796.8  131.83  4808.1  131.62  4820.6  130.64  4838.6  130.31  4879.3  129.81
  4899.7  130.39    4920  130.29    4926  129.54  4931.1  129.61  4940.3  127.59
  4950.5  124.25  4970.9  116.85  4978.8  115.55  4991.2  115.09    4994  114.71
  4994.5  114.21  5001.7  114.21  5002.2  114.71  5011.4  115.72  5021.5   117.5
  5028.1  121.13  5033.2  121.13  5041.6  124.61  5051.7  127.68  5061.8  130.02
  5091.9  129.62  5117.5  128.17  5122.5  128.23  5132.2  129.28  5155.8  130.02
#Mann= 3 , 0 , 0
  4796.8     .11       0  4940.3     .03       0  5051.7     .11       0
Bank Sta=4940.3,5051.7
XS Rating Curve= 0 ,0
Exp/Cntr=0.3,0.1

Type RM Length L Ch R = 1 ,17500   ,456,456,456
BEGIN DESCRIPTION:
TRADE CTR DITCH_COLLEGE PK DITCH 35.0
END DESCRIPTION:
XS GIS Cut Line= 3
      3833939.38     10075950.65      3833936.18      10075848.9
      3833995.38     10075668.04
#Sta/Elev= 30
  4898.2  130.74  4907.8  130.41  4917.8  128.53  4947.8  119.72  4957.8  117.09
  4967.8  114.82  4977.8  114.12  4992.3  113.72  4992.8  113.22  5000.1  113.22
  5000.6  113.72  5008.2  113.97  5017.5  115.96  5022.7  115.49  5029.3  118.39
  5039.8  121.04  5049.3  123.85  5054.6  123.95  5060.8  126.78  5071.4  129.24
  5081.2  129.51  5102.9  128.79    5113  127.61  5118.3  127.65    5124  126.25
  5134.5  127.47  5140.9  127.67  5150.2  127.68  5166.1  128.78  5190.3  129.13
#Mann= 4 ,-1 , 0
  4898.2     .11       0  4917.8     .03       0  5060.8     .11       0
  5140.9    .125       0
Bank Sta=4917.8,5060.8
XS Rating Curve= 0 ,0
Exp/Cntr=0.3,0.1

Type RM Length L Ch R = 1 ,17044   ,135,135,135
BEGIN DESCRIPTION:
TRADE CTR DITCH_COLLEGE PK DITCH 34.0
END DESCRIPTION:
XS GIS Cut Line= 3
      3834388.95     10076025.88      3834390.68     10075868.15
      3834394.15     10075777.86
#Sta/Elev= 30
  4847.6  131.36  4852.5  131.36  4862.4  130.38  4872.4  130.08  4882.4  130.82
  4892.4  130.64  4902.4  129.74  4922.4  125.47  4932.4     123  4952.4  118.37
  4962.4  116.42  4972.4   114.6  4982.4  113.29  4988.3  112.89  4988.8  112.39
  4996.1  112.39  4996.6  112.89  5001.4  113.23  5005.3  113.23  5012.4  114.55
  5022.4  116.22  5032.4  118.11  5042.4  120.28  5052.5     122  5059.6  124.75
  5064.6  124.67  5072.5  127.32  5082.5  129.66  5091.6  130.51  5095.7  130.51
#Mann= 3 , 0 , 0
  4847.6     .11       0  4922.4     .03       0  5059.6    .125       0
Bank Sta=4922.4,5059.6
XS Rating Curve= 0 ,0
Exp/Cntr=0.3,0.1

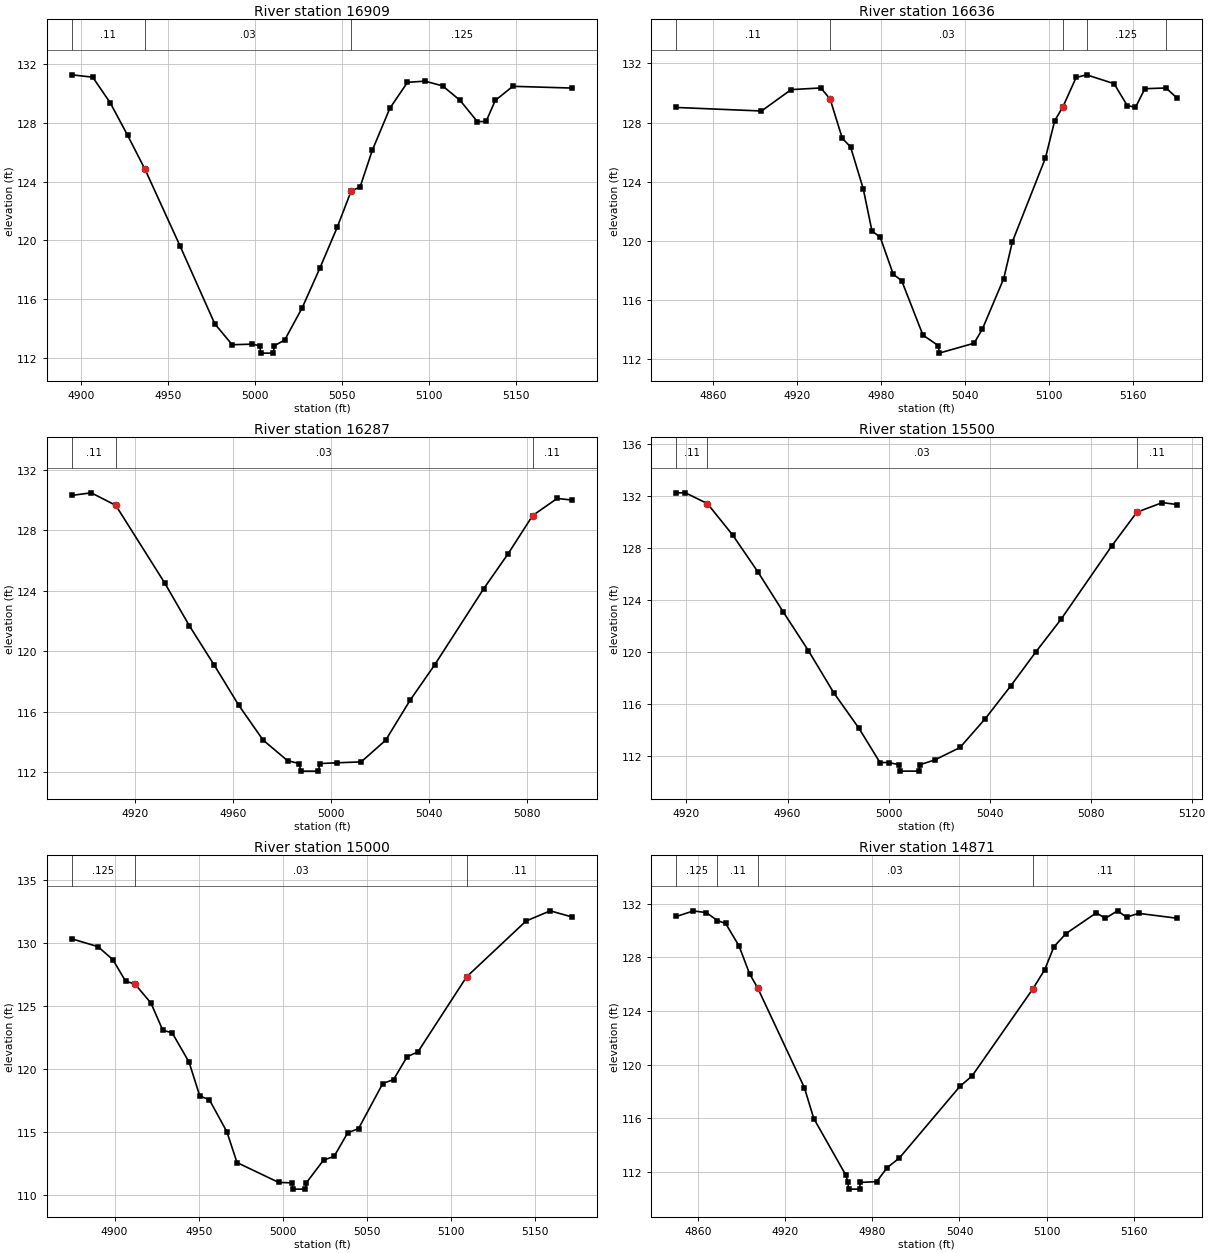
Type RM Length L Ch R = 1 ,16909   ,273,273,273
BEGIN DESCRIPTION:
TRADE CTR DITCH_COLLEGE PK DITCH 33.0
END DESCRIPTION:
XS GIS Cut Line= 3
      3834531.36     10075993.17       3834524.8     10075889.56
      3834549.54     10075707.25
#Sta/Elev= 30
  4894.5  131.25  4906.6  131.09  4916.6  129.36  4926.7  127.13  4936.7  124.82
  4956.7  119.65  4976.8  114.33  4986.8  112.91  4998.3  112.95  5002.7  112.84
  5003.2  112.34  5010.5  112.34    5011  112.84    5017  113.23  5027.1  115.43
  5037.2  118.11  5047.2  120.89  5055.3  123.38  5060.3  123.61  5067.4  126.13
  5077.5  128.98  5087.6  130.74  5097.7  130.82  5107.8   130.5  5117.9  129.51
  5127.8  128.07  5132.8  128.08  5138.1  129.51  5148.2  130.47  5182.3  130.35
#Mann= 3 , 0 , 0
  4894.5     .11       0  4936.7     .03       0  5055.3    .125       0
Bank Sta=4936.7,5055.3
XS Rating Curve= 0 ,0
Exp/Cntr=0.3,0.1

Type RM Length L Ch R = 1 ,16636   ,349,349,349
BEGIN DESCRIPTION:
Mapping XS 58514661
END DESCRIPTION:
XS GIS Cut Line= 2
      3834565.02     10076160.84      3834867.12     10075969.86
#Sta/Elev= 30
  4833.8  129.02  4894.6  128.78  4915.8  130.23    4937  130.34  4943.6  129.59
  4952.3  126.93  4958.2  126.35  4967.3   123.5  4973.5  120.65  4979.4  120.23
  4988.7  117.72  4994.7  117.29  5009.9   113.6    5021  112.88  5021.5  112.38
  5046.4  113.05  5052.3     114  5067.6  117.43  5073.8  119.93  5097.4   125.6
    5104  128.12  5109.9  129.07  5119.3  131.05  5126.8  131.23  5146.4  130.63
  5155.8  129.15  5161.7  129.03  5168.4  130.29  5183.5  130.34  5191.2  129.67
#Mann= 5 ,-1 , 0
  4833.8     .11       0  4943.6     .03       0  5109.9     .11       0
  5126.8    .125       0  5183.5     .11       0
Bank Sta=4943.6,5109.9
XS Rating Curve= 0 ,0
Exp/Cntr=0.3,0.1

Type RM Length L Ch R = 1 ,16287   ,787,787,787
BEGIN DESCRIPTION:
TRADE CTR DITCH_COLLEGE PK DITCH 32.0
END DESCRIPTION:
XS GIS Cut Line= 3
       3834619.9      10076408.7      3834720.61     10076414.85
      3834823.91     10076415.64
#Sta/Elev= 23
  4894.1   130.3  4902.1  130.47  4912.1  129.64  4932.1   124.5  4942.1  121.69
  4952.2   119.1  4962.2  116.45  4972.2  114.13  4982.2  112.77    4987  112.58
  4987.5  112.08  4994.8  112.08  4995.3  112.58  5002.2  112.63  5012.2  112.69
  5022.2  114.12  5032.2  116.77  5042.2   119.1  5062.2  124.13  5072.2  126.45
  5082.2  128.97  5092.2   130.1  5098.3  129.99
#Mann= 3 , 0 , 0
  4894.1     .11       0  4912.1     .03       0  5082.2     .11       0
Bank Sta=4912.1,5082.2
XS Rating Curve= 0 ,0
Exp/Cntr=0.3,0.1

Type RM Length L Ch R = 1 ,15500   ,500,500,500
BEGIN DESCRIPTION:
TRADE CTR DITCH_COLLEGE PK DITCH 31.0
END DESCRIPTION:
XS GIS Cut Line= 3
      3834575.59     10077200.71      3834659.58     10077199.54
      3834773.59     10077204.15
#Sta/Elev= 25
    4916  132.27  4919.6  132.27  4928.3  131.44  4938.3  129.02  4948.3  126.18
  4958.3  123.11  4968.3  120.12  4978.3  116.89  4988.3  114.15  4996.6  111.52
    5000  111.52  5004.1  111.36  5004.6  110.86    5012  110.86  5012.5  111.36
  5018.3  111.72  5028.3  112.68  5038.3   114.9  5048.3   117.4  5058.3  120.03
  5068.3  122.55  5088.3  128.17  5098.3  130.78  5108.4  131.52  5114.1  131.37
#Mann= 3 , 0 , 0
    4916     .11       0  4928.3     .03       0  5098.3     .11       0
Bank Sta=4928.3,5098.3
XS Rating Curve= 0 ,0
Exp/Cntr=0.3,0.1

Type RM Length L Ch R = 1 ,15000   ,129,129,129
BEGIN DESCRIPTION:
TRADE CTR DITCH_COLLEGE PK DITCH 30.0
END DESCRIPTION:
XS GIS Cut Line= 3
      3834526.12     10077751.75      3834637.32     10077693.59
      3834772.62     10077587.71
#Sta/Elev= 30
  4874.5  130.35  4890.1  129.73    4899  128.69  4906.5  126.99  4912.1  126.76
  4921.6  125.25  4928.6   123.1  4934.2  122.89  4944.2  120.57  4950.6  117.88
  4956.3  117.58  4966.7  115.04  4972.7   112.6  4997.5  111.02  5005.4  110.99
  5005.9  110.49  5013.4  110.49  5013.9  110.99  5024.1  112.79  5030.4  113.09
  5038.5  114.96  5044.9  115.29  5059.3  118.87  5065.7  119.18  5073.8     121
  5080.2  121.38  5109.1  127.33  5144.4  131.76  5158.8  132.57  5171.8  132.08
#Mann= 3 , 0 , 0
  4874.5    .125       0  4912.1     .03       0  5109.1     .11       0
Bank Sta=4912.1,5109.1
XS Rating Curve= 0 ,0
Exp/Cntr=0.3,0.1

Type RM Length L Ch R = 1 ,14871   ,618,618,618
BEGIN DESCRIPTION:
TRADE CTR DITCH_COLLEGE PK DITCH 29.0
END DESCRIPTION:
XS GIS Cut Line= 3
      3834638.94     10077919.33      3834702.33     10077796.89
      3834868.15     10077673.61
#Sta/Elev= 30
  4845.1  131.05  4856.8  131.46  4865.7  131.34  4873.4  130.74    4879  130.53
  4888.2  128.86  4895.5  126.77  4901.1  125.71  4933.2  118.28  4939.7  115.97
  4961.9  111.72  4963.2   111.2  4963.7   110.7  4971.2   110.7  4971.7   111.2
    4983  111.26  4990.2   112.3  4998.6  113.02  5040.3  118.37  5048.7  119.15
  5090.3  125.61  5098.7  127.08    5105  128.79  5113.3  129.77  5134.2  131.32
  5140.4  130.91  5148.8  131.47    5155     131  5163.4  131.28  5189.6  130.92
#Mann= 4 ,-1 , 0
  4845.1    .125       0  4873.4     .11       0  4901.1     .03       0
  5090.3     .11       0
Bank Sta=4901.1,5090.3
XS Rating Curve= 0 ,0
Exp/Cntr=0.3,0.1

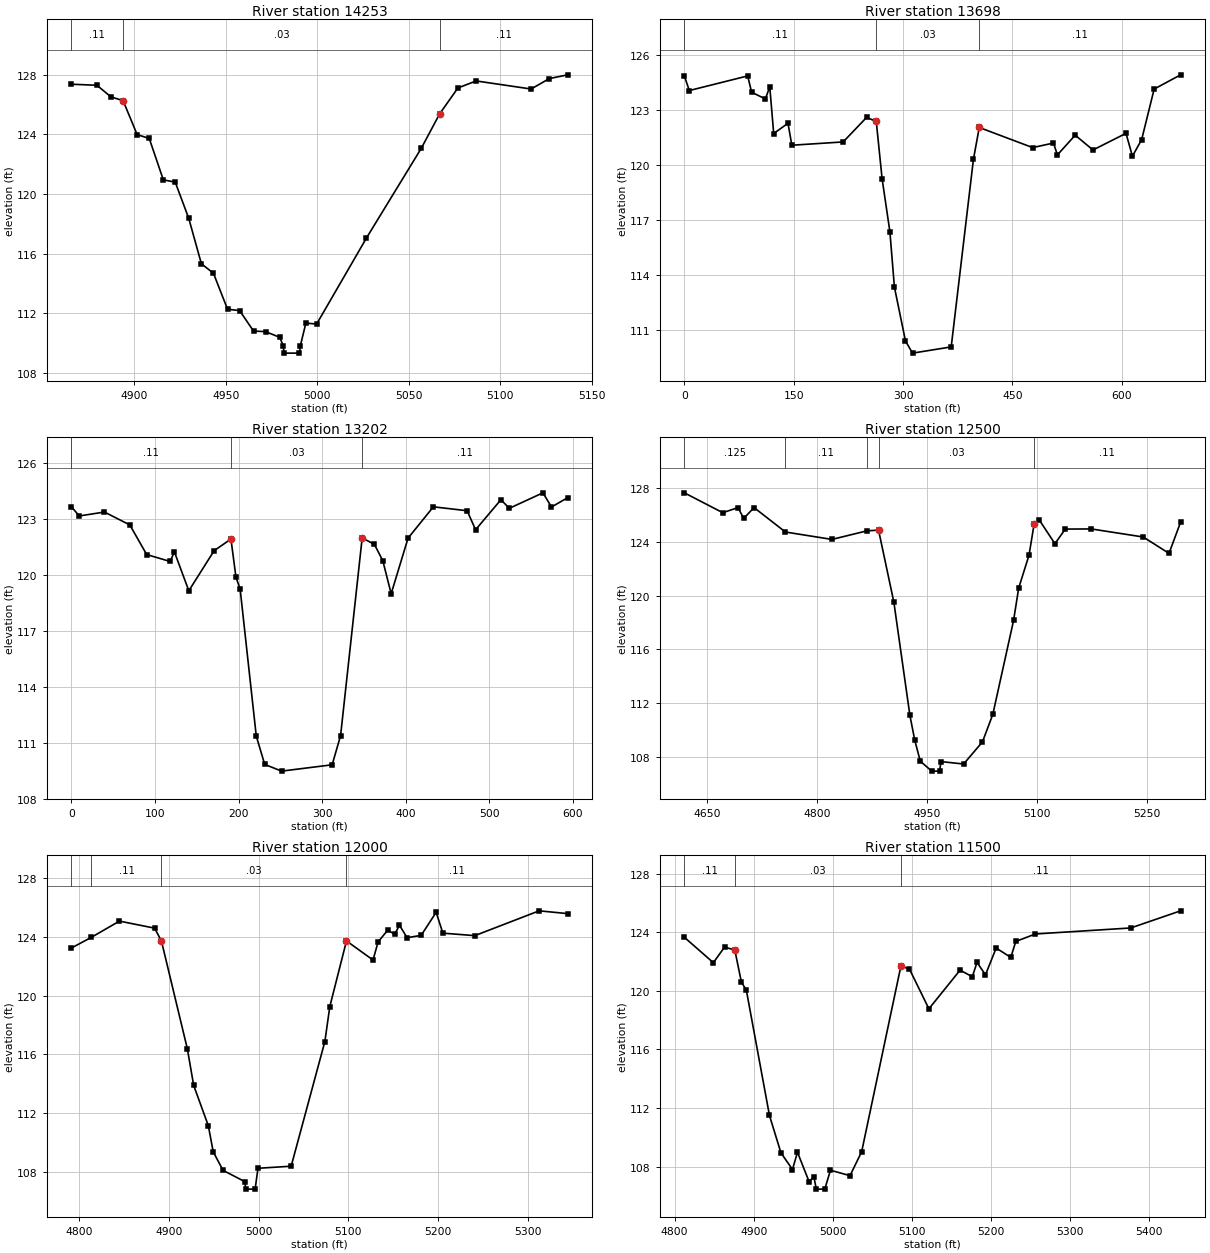
Type RM Length L Ch R = 1 ,14253   ,555,555,555
BEGIN DESCRIPTION:
TRADE CTR DITCH_COLLEGE PK DITCH 28.0
END DESCRIPTION:
XS GIS Cut Line= 3
       3835236.5     10077979.79       3835324.4     10077877.06
      3835326.57     10077741.09
#Sta/Elev= 30
  4865.7  127.35  4879.6  127.28  4887.3   126.5  4893.9  126.25  4901.6  123.97
  4908.2  123.72  4915.9  120.94  4922.4  120.79  4929.8  118.36  4936.7  115.32
  4943.3  114.68    4951  112.27  4957.6  112.18  4965.2  110.81  4971.8  110.77
  4979.5  110.39  4981.4  109.83  4981.9  109.33  4990.3  109.33  4990.8  109.83
  4993.8  111.34  4999.7  111.28  5026.9  117.04  5056.9  123.06  5066.9  125.36
  5076.9   127.1  5086.9  127.57  5116.9  127.03  5126.9  127.73  5136.9  127.98
#Mann= 3 , 0 , 0
  4865.7     .11       0  4893.9     .03       0  5066.9     .11       0
Bank Sta=4893.9,5066.9
XS Rating Curve= 0 ,0
Exp/Cntr=0.3,0.1

Type RM Length L Ch R = 1 ,13698   ,496,496,496
XS GIS Cut Line= 4
      3835751.53     10078285.07      3835871.06     10077965.83
      3835899.23     10077809.45      3836067.52     10077743.15
#Sta/Elev= 30
       0  124.88     6.7  124.08    86.8  124.88    92.2  123.99   111.1  123.62
   117.1  124.29   122.5  121.73   142.1  122.29   147.4  121.09   217.8  121.27
   249.9  122.61   263.2  122.39   271.2  119.26   281.9  116.36   288.1  113.33
   303.3  110.38     313  109.72     366  110.06   396.5  120.32   404.5  122.06
   477.8  120.96   506.3  121.21   511.7  120.56   536.1  121.64   560.5  120.83
   605.8  121.74   614.6  120.49   627.3   121.4   644.4  124.16   680.7  124.94
#Mann= 3 , 0 , 0
       0     .11       0   263.2     .03       0   404.5     .11       0
Bank Sta=263.2,404.5
XS Rating Curve= 0 ,0
Exp/Cntr=0.3,0.1

Type RM Length L Ch R = 1 ,13202   ,702,702,702
XS GIS Cut Line= 3
      3836327.09     10078300.28      3836364.55     10078015.31
      3836406.21     10077711.93
#Sta/Elev= 30
       0  123.64     9.3  123.15    39.4  123.36    69.8  122.67      90  121.08
   118.1  120.71   123.1  121.23   140.4  119.14   170.7  121.29   190.8  121.91
   196.8  119.87   201.8  119.23   221.1  111.35   231.2  109.83   251.4  109.47
   311.9  109.81     322  111.38   347.8  121.97   362.4  121.63   372.5  120.75
   382.5  118.98   402.7  121.96     433  123.64   473.4  123.43   483.5  122.41
   513.8  124.02   523.9  123.56   564.1  124.39   574.3  123.63   593.7  124.13
#Mann= 3 , 0 , 0
       0     .11       0   190.8     .03       0   347.8     .11       0
Bank Sta=190.8,347.8
XS Rating Curve= 0 ,0
Exp/Cntr=0.3,0.1

Type RM Length L Ch R = 1 ,12500   ,500,500,500
BEGIN DESCRIPTION:
TRADE CTR DITCH_COLLEGE PK DITCH 25.0
END DESCRIPTION:
XS GIS Cut Line= 3
      3837280.55       10078162.      3836994.71     10077910.39
      3836789.61      10077697.1
#Sta/Elev= 30
  4619.2  127.67  4671.5  126.19  4692.4  126.57    4700  125.76  4714.2  126.57
    4757  124.75  4820.4   124.2  4868.3  124.84    4884  124.89  4904.9  119.51
  4926.7   111.1  4933.4  109.23  4940.9  107.68  4956.5  106.94  4967.1  106.94
  4969.2  107.65    5000  107.47  5025.7  109.12  5039.8  111.17  5068.1  118.16
  5075.1  120.58  5089.2  123.03  5096.2  125.37  5103.4  125.63  5124.5  123.88
  5138.6  124.97  5174.1  124.98  5244.9  124.38  5280.1  123.16  5295.9  125.49
#Mann= 5 ,-1 , 0
  4619.2    .125       0    4757     .11       0  4868.3    .125       0
    4884     .03       0  5096.2     .11       0
Bank Sta=4884,5096.2
XS Rating Curve= 0 ,0
Exp/Cntr=0.3,0.1

Type RM Length L Ch R = 1 ,12000   ,500,500,500
BEGIN DESCRIPTION:
TRADE CTR DITCH_COLLEGE PK DITCH 24.0
END DESCRIPTION:
XS GIS Cut Line= 3
      3837362.77     10077567.07      3837171.49     10077483.61
      3836851.74     10077354.85
#Sta/Elev= 30
  4791.3  123.25  4813.6  123.98  4844.8  125.08    4884   124.6  4891.6  123.73
  4920.5  116.39  4927.6  113.89  4943.9  111.15  4949.4  109.37  4960.3  108.11
  4984.9  107.33  4985.4  106.83  4996.1  106.83  4999.3  108.25  5036.3  108.39
  5073.9  116.88  5079.4  119.26    5098  123.73  5127.6  122.43  5133.3  123.67
  5144.1  124.47  5151.7  124.18  5157.1   124.8  5165.6  123.95  5181.3  124.11
    5198  125.68  5205.5  124.26  5241.1  124.09  5312.9  125.78  5344.7  125.59
#Mann= 4 ,-1 , 0
  4791.3    .125       0  4813.6     .11       0  4891.6     .03       0
    5098     .11       0
Bank Sta=4891.6,5098
XS Rating Curve= 0 ,0
Exp/Cntr=0.3,0.1

Type RM Length L Ch R = 1 ,11500   ,327,327,327
BEGIN DESCRIPTION:
TRADE CTR DITCH_COLLEGE PK DITCH 23.0
END DESCRIPTION:
XS GIS Cut Line= 3
      3837478.48      10077160.7      3837328.24     10077048.54
      3836917.28     10076892.46
#Sta/Elev= 30
  4812.5  123.65  4849.1  121.92  4863.2  122.98  4876.2  122.79  4884.5   120.6
  4890.8  120.04    4920  111.49  4934.5  108.94  4949.1   107.8  4955.4  108.98
    4970  106.98  4976.2  107.29  4979.2  106.46  4989.9  106.46  4997.1  107.75
  5021.8  107.38  5036.5  109.01    5086  121.66  5096.7  121.51  5121.5  118.77
  5160.9  121.41  5176.4  120.96  5182.3  121.94    5193  121.09  5206.5  122.92
    5225  122.28  5231.3  123.37  5256.1  123.88  5376.6  124.29  5439.6  125.46
#Mann= 3 , 0 , 0
  4812.5     .11       0  4876.2     .03       0    5086     .11       0
Bank Sta=4876.2,5086
XS Rating Curve= 0 ,0
Exp/Cntr=0.3,0.1

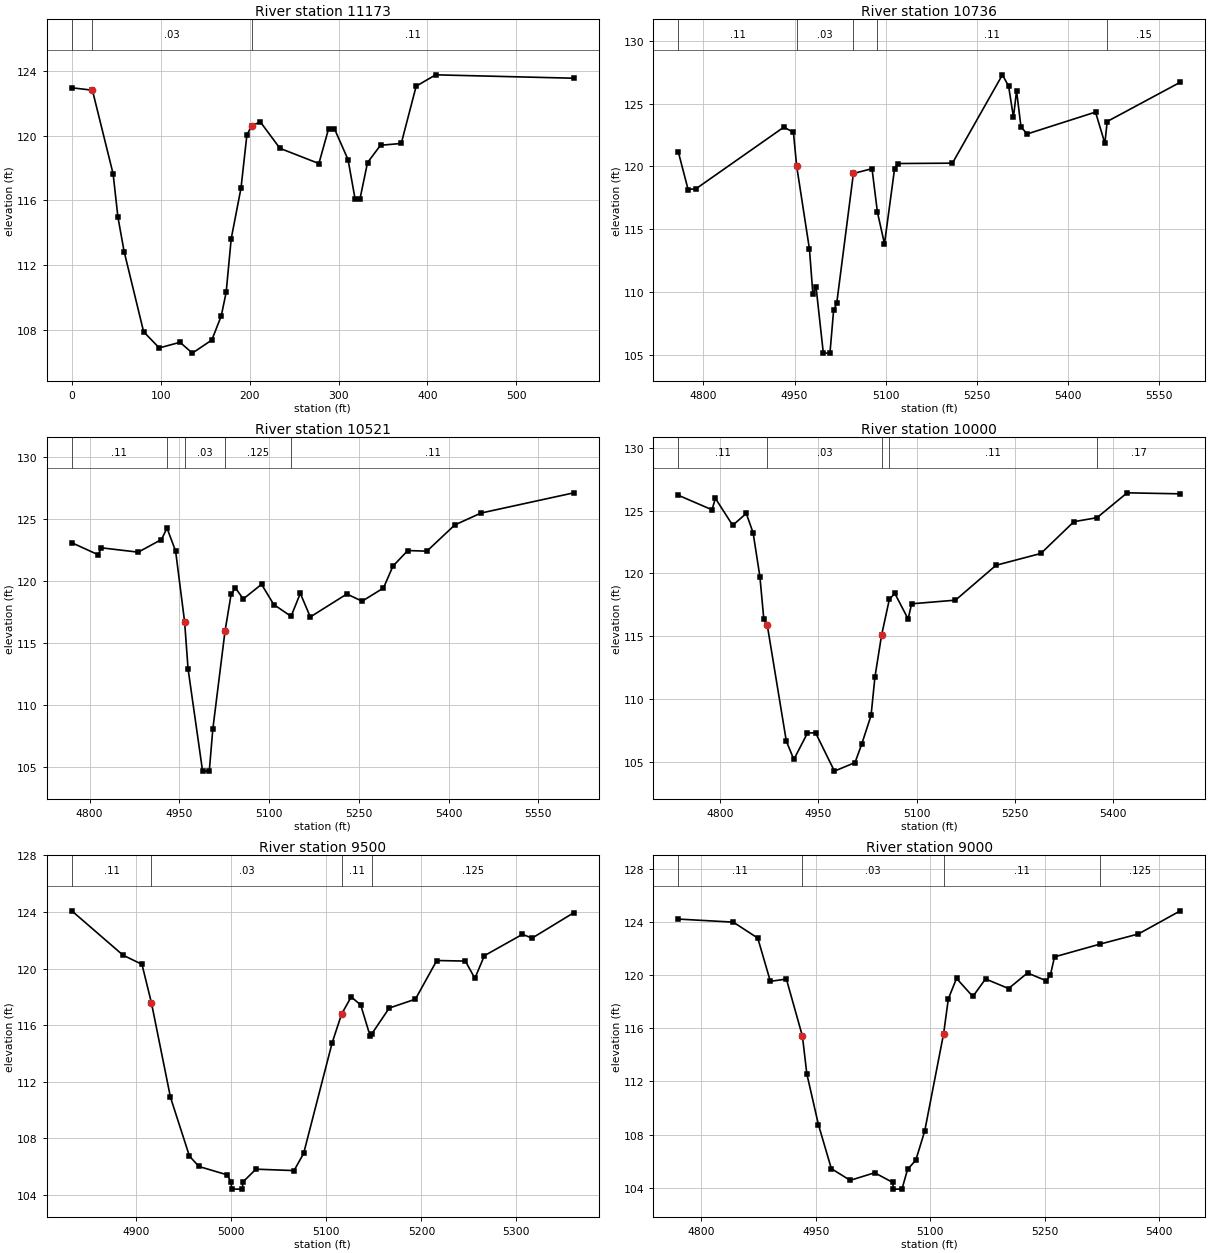
Type RM Length L Ch R = 1 ,11173   ,437,437,437
XS GIS Cut Line= 2
      3837553.37     10076884.91      3837323.73     10076369.16
#Sta/Elev= 30
       0  122.96    23.2  122.81    46.5  117.64    51.9  114.97    58.9  112.84
    80.8  107.89    98.4  106.89   121.7  107.24   135.6  106.57   157.5  107.38
   168.1  108.87   173.6  110.32   179.3  113.64   190.3  116.76   196.9  120.03
   202.3  120.63   212.2  120.84   234.1  119.22   277.9  118.28   288.8  120.43
   295.3  120.44   310.7  118.52   318.5  116.12     324  116.07   332.6  118.34
   347.2  119.41   370.5  119.52   387.3  123.06   409.2  123.76   564.6  123.55
#Mann= 3 , 0 , 0
       0     .11       0    23.2     .03       0   202.3     .11       0
Bank Sta=23.2,202.3
XS Rating Curve= 0 ,0
Exp/Cntr=0.3,0.1

Type RM Length L Ch R = 1 ,10736   ,215,215,215
BEGIN DESCRIPTION:
TRADE CTR DITCH_COLLEGE PK DITCH 22.0
END DESCRIPTION:
XS GIS Cut Line= 3
      3837844.55     10076946.45      3837920.28     10076712.32
      3838038.01     10076144.47
#Sta/Elev= 30
  4758.7  121.17  4774.9  118.15  4788.2  118.22  4932.5  123.12  4948.2  122.71
  4953.5  120.03  4974.6  113.39  4980.2  109.83  4985.5  110.35  4997.4  105.11
  5008.3  105.11  5014.3  108.51  5019.4  109.07  5046.9  119.43  5077.5  119.81
  5086.4  116.34    5098  113.82  5114.6   119.8  5119.7  120.22  5209.8  120.25
    5292  127.29  5302.2  126.39  5310.2  123.91  5315.3  126.02  5322.6  123.13
  5332.9  122.58  5445.2  124.32  5460.6  121.83  5464.4  123.57  5584.7   126.7
#Mann= 5 ,-1 , 0
  4758.7     .11       0  4953.5     .03       0  5046.9    .125       0
  5086.4     .11       0  5464.4     .15       0
Bank Sta=4953.5,5046.9
XS Rating Curve= 0 ,0
Exp/Cntr=0.3,0.1

Type RM Length L Ch R = 1 ,10521   ,521,521,521
BEGIN DESCRIPTION:
TRADE CTR DITCH_COLLEGE PK DITCH 21.0
END DESCRIPTION:
XS GIS Cut Line= 3
      3838070.26     10076937.72      3838133.02     10076722.07
      3838250.52      10076118.6
#Sta/Elev= 30
  4770.1  123.07  4814.3   122.1  4819.5  122.66  4881.2  122.31  4920.1  123.33
  4929.3  124.25  4943.7   122.4  4958.8  116.68  4964.5  112.92  4988.8  104.67
    5000  104.67  5005.9  108.05  5026.3  115.94  5036.5  118.92  5043.8  119.42
  5056.8  118.54  5087.4  119.72  5107.8  118.09  5136.7  117.14  5152.2  118.99
  5168.9  117.09    5230  118.94  5255.5  118.36  5291.2  119.42  5307.1  121.19
  5331.9  122.44  5363.8  122.39  5410.4   124.5  5454.2  125.46  5609.5  127.09
#Mann= 5 ,-1 , 0
  4770.1     .11       0  4929.3    .125       0  4958.8     .03       0
  5026.3    .125       0  5136.7     .11       0
Bank Sta=4958.8,5026.3
XS Rating Curve= 0 ,0
Exp/Cntr=0.3,0.1

Type RM Length L Ch R = 1 ,10000   ,500,500,500
BEGIN DESCRIPTION:
TRADE CTR DITCH_COLLEGE PK DITCH 20.0
END DESCRIPTION:
XS GIS Cut Line= 3
      3838567.84     10077011.12      3838638.16     10076756.86
      3838717.86     10076261.03
#Sta/Elev= 30
  4736.2  126.23  4787.7  125.07  4792.9  125.98  4819.3  123.83    4840  124.78
  4850.4  123.24  4860.8  119.74  4866.7  116.39  4871.9  115.92  4901.1  106.64
  4912.6  105.18  4933.4  107.29  4945.8   107.3  4974.5  104.25  5005.9  104.93
    5016  106.38  5030.4  108.69  5036.3  111.75  5046.4  115.07  5058.3  117.94
  5066.6  118.41  5086.9  116.37  5092.3  117.58  5159.2  117.87  5221.1  120.65
  5289.5  121.59  5339.8  124.12  5375.1  124.44  5421.1  126.42  5502.2  126.34
#Mann= 5 ,-1 , 0
  4736.2     .11       0  4871.9     .03       0  5046.4    .125       0
  5058.3     .11       0  5375.1     .17       0
Bank Sta=4871.9,5046.4
XS Rating Curve= 0 ,0
Exp/Cntr=0.3,0.1

Type RM Length L Ch R = 1 ,9500    ,500,500,500
BEGIN DESCRIPTION:
TRADE CTR DITCH_COLLEGE PK DITCH 19.0
END DESCRIPTION:
XS GIS Cut Line= 3
       3839055.7      10076984.9      3839060.17     10076816.86
      3839083.48     10076457.12
#Sta/Elev= 30
  4831.9  124.08  4885.8  120.95  4905.8   120.3  4915.8  117.57  4935.8  110.91
  4955.8  106.75  4965.8  106.02  4995.4  105.43  4999.7  104.92  5000.2  104.42
  5011.5  104.42    5012  104.92  5025.8  105.83  5065.9  105.73    5076  106.94
    5106  114.75    5116  116.79  5126.1     118  5136.1  117.43  5146.1  115.22
    5148  115.41  5166.1  117.21  5193.7  117.84  5216.2  120.57  5246.3  120.53
  5256.3  119.31  5266.3  120.91  5306.4  122.42  5316.5  122.15  5360.5  123.95
#Mann= 4 ,-1 , 0
  4831.9     .11       0  4915.8     .03       0    5116     .11       0
    5148    .125       0
Bank Sta=4915.8,5116
XS Rating Curve= 0 ,0
Exp/Cntr=0.3,0.1

Type RM Length L Ch R = 1 ,9000    ,500,500,500
BEGIN DESCRIPTION:
TRADE CTR DITCH_COLLEGE PK DITCH 18.0
END DESCRIPTION:
XS GIS Cut Line= 3
      3839361.24     10077135.99      3839431.47     10076916.86
      3839583.17     10076516.97
#Sta/Elev= 30
  4769.9   124.2    4842  123.97  4874.1  122.77  4890.6  119.52  4911.6  119.69
  4932.6   115.4  4938.4  112.56  4953.6  108.74  4970.5  105.44  4995.2  104.56
  5027.2  105.13  5051.1   104.4  5051.6   103.9    5063   103.9  5070.4  105.39
  5081.1  106.07  5092.8  108.26  5117.6  115.59  5123.8  118.21  5134.5  119.74
  5155.9  118.38  5172.5   119.7  5202.7  118.98  5227.5  120.15  5252.2  119.56
  5257.6  120.02  5262.9  121.36    5322  122.31  5372.8  123.08  5427.7  124.82
#Mann= 4 ,-1 , 0
  4769.9     .11       0  4932.6     .03       0  5117.6     .11       0
    5322    .125       0
Bank Sta=4932.6,5117.6
XS Rating Curve= 0 ,0
Exp/Cntr=0.3,0.1

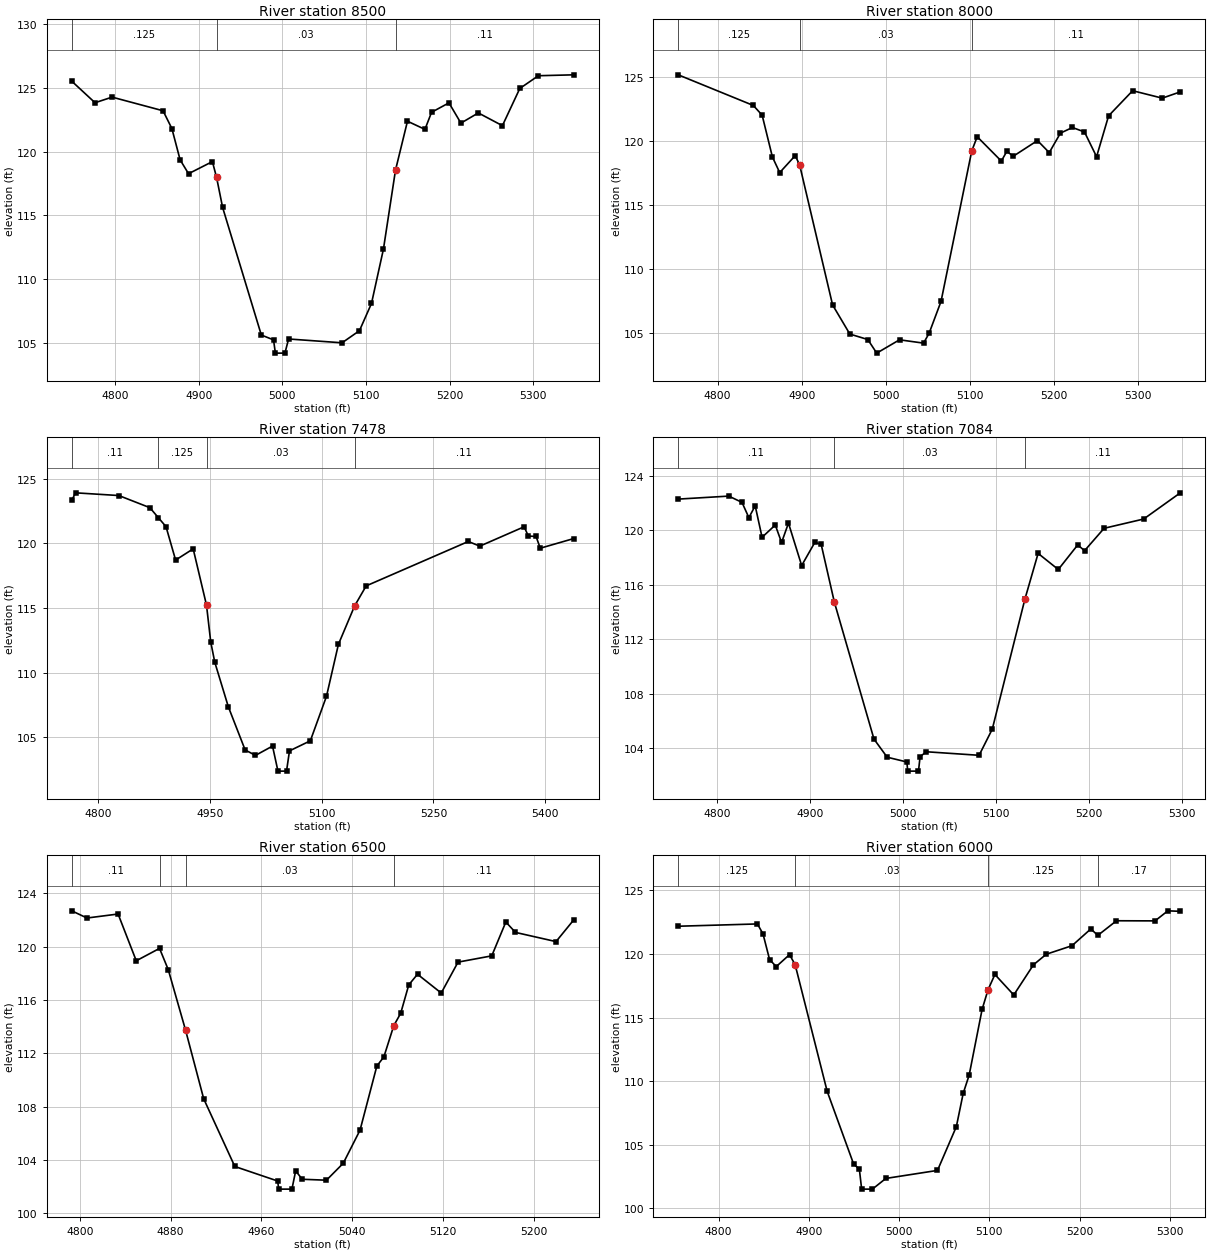
Type RM Length L Ch R = 1 ,8500    ,500,500,500
BEGIN DESCRIPTION:
TRADE CTR DITCH_COLLEGE PK DITCH 17.0
END DESCRIPTION:
XS GIS Cut Line= 3
      3839550.47     10077276.57      3839798.24     10077231.69
      3840067.87     10077011.05
#Sta/Elev= 30
  4748.2  125.53    4776  123.84  4796.4  124.28  4857.3  123.21  4867.9  121.81
  4877.7  119.36  4887.8  118.27  4916.3  119.22  4921.3  117.98  4928.5  115.63
  4974.8  105.61  4989.4  105.23  4991.6  104.19    5003  104.19  5007.4   105.3
  5071.3     105  5092.1  105.95  5106.5  108.09  5120.8  112.36  5135.2  118.55
  5149.5  122.39  5170.4  121.75  5178.3  123.09  5199.1  123.83  5213.4  122.24
  5234.2  123.04    5263  122.04  5283.8  124.96    5306  125.96  5348.4  126.03
#Mann= 3 , 0 , 0
  4748.2    .125       0  4921.3     .03       0  5135.2     .11       0
Bank Sta=4921.3,5135.2
XS Rating Curve= 0 ,0
Exp/Cntr=0.3,0.1

Type RM Length L Ch R = 1 ,8000    ,522,522,522
BEGIN DESCRIPTION:
TRADE CTR DITCH_COLLEGE PK DITCH 16.0
END DESCRIPTION:
XS GIS Cut Line= 3
      3839812.63     10077658.52      3840048.24      10077584.7
      3840317.86     10077361.07
#Sta/Elev= 30
  4753.1  125.15  4842.4  122.76  4852.9     122  4865.1  118.74  4873.8  117.52
  4892.3  118.85  4897.6  118.09  4936.7  107.19  4957.2  104.92  4978.6  104.49
  4989.2  103.43  5016.3  104.47  5044.9  104.21  5051.5  104.98  5065.7  107.47
  5102.2   119.2  5108.7  120.32  5137.4  118.42  5143.9  119.17  5151.7   118.8
  5180.4  120.02  5194.4  119.08  5207.7   120.6    5222  121.04  5236.3  120.69
  5250.7  118.76    5265  121.95  5293.6  123.91  5328.8  123.33  5350.3  123.82
#Mann= 3 , 0 , 0
  4753.1    .125       0  4897.6     .03       0  5102.2     .11       0
Bank Sta=4897.6,5102.2
XS Rating Curve= 0 ,0
Exp/Cntr=0.3,0.1

Type RM Length L Ch R = 1 ,7478    ,394,394,394
BEGIN DESCRIPTION:
TRADE CTR DITCH_COLLEGE PK DITCH 15.0
END DESCRIPTION:
XS GIS Cut Line= 3
      3840031.39     10078099.49      3840248.24     10078006.86
      3840631.79     10077793.92
#Sta/Elev= 30
  4764.2  123.34  4769.3  123.92  4827.4  123.71  4869.1  122.77  4880.4     122
  4890.8   121.3  4903.7  118.71  4927.3  119.58  4945.2  115.22  4950.9  112.36
  4956.3   110.8  4974.5  107.35  4997.1     104    5011  103.58  5033.9   104.3
  5041.2  102.36  5052.7  102.36  5056.7  103.93  5084.7  104.71  5106.4  108.16
  5122.4  112.18  5144.2  115.16  5159.7  116.71  5296.9  120.15  5312.4  119.79
  5371.9  121.29  5377.6  120.57  5387.9  120.54  5393.6  119.63  5438.7  120.38
#Mann= 4 ,-1 , 0
  4764.2     .11       0  4880.4    .125       0  4945.2     .03       0
  5144.2     .11       0
Bank Sta=4945.2,5144.2
XS Rating Curve= 0 ,0
Exp/Cntr=0.3,0.1

Type RM Length L Ch R = 1 ,7084    ,584,584,584
BEGIN DESCRIPTION:
TRADE CTR DITCH_COLLEGE PK DITCH 14.0
END DESCRIPTION:
XS GIS Cut Line= 3
       3840248.5     10078428.91      3840428.24     10078266.86
      3840628.44     10078045.86
#Sta/Elev= 30
    4758  122.27  4812.4  122.49  4826.6  122.03    4834  120.91  4840.8  121.78
  4848.2  119.47  4862.4  120.37  4869.2  119.09  4876.6  120.51  4890.8   117.4
    4905   119.1  4911.8  118.95    4926  114.71  4968.6  104.68  4982.8  103.35
    5004     103  5004.9  102.33  5016.5  102.33  5018.2  103.39  5024.9  103.75
  5081.7  103.49  5095.9  105.41    5131  114.94  5145.2  118.29  5166.9  117.11
  5187.8  118.91  5195.2  118.49  5216.2  120.13  5258.8  120.81  5298.2  122.73
#Mann= 3 , 0 , 0
    4758     .11       0    4926     .03       0    5131     .11       0
Bank Sta=4926,5131
XS Rating Curve= 0 ,0
Exp/Cntr=0.3,0.1

Type RM Length L Ch R = 1 ,6500    ,500,500,500
BEGIN DESCRIPTION:
TRADE CTR DITCH_COLLEGE PK DITCH 13.0
END DESCRIPTION:
XS GIS Cut Line= 3
      3840503.65     10078753.98      3840684.32     10078652.94
      3840876.88     10078517.89
#Sta/Elev= 30
    4793  122.69  4806.4  122.15  4833.8  122.45  4849.8  118.94  4870.3  119.87
    4878  118.27  4893.2  113.74  4909.2  108.58  4936.6   103.5  4974.3  102.41
  4975.3   101.8  4986.9   101.8  4990.2  103.17    4996  102.54  5017.3  102.47
  5032.1  103.74  5046.9  106.23  5061.7  111.04  5067.9  111.73  5076.6  114.07
  5082.7     115  5089.8  117.13  5097.5  117.93  5118.4  116.52  5133.2  118.84
  5162.9  119.31  5175.3  121.85  5183.8  121.07  5219.5  120.38  5235.2  122.02
#Mann= 4 ,-1 , 0
    4793     .11       0  4870.3    .125       0  4893.2     .03       0
  5076.6     .11       0
Bank Sta=4893.2,5076.6
XS Rating Curve= 0 ,0
Exp/Cntr=0.3,0.1

Type RM Length L Ch R = 1 ,6000    ,500,500,500
BEGIN DESCRIPTION:
TRADE CTR DITCH_COLLEGE PK DITCH 12.0
END DESCRIPTION:
XS GIS Cut Line= 3
      3840685.94     10079210.57      3840883.99     10079066.86
      3841117.84     10078861.08
#Sta/Elev= 30
  4755.3  122.17    4843  122.35  4849.2  121.57  4856.5  119.55  4863.9     119
  4878.6  119.94  4884.8  119.15  4920.3   109.2  4949.7  103.47  4955.9  103.11
  4958.5  101.52  4970.4  101.52  4985.3  102.36  5042.5  102.99  5063.4  106.43
    5071  109.05  5077.6  110.48  5091.9  115.63  5098.5  117.18  5106.1  118.38
    5127  116.77  5148.8  119.14    5163  119.97  5191.5  120.64  5212.4  121.96
  5220.1  121.45  5240.8   122.6  5283.5  122.59  5297.7  123.38  5311.5  123.34
#Mann= 4 ,-1 , 0
  4755.3    .125       0  4884.8     .03       0  5098.5    .125       0
  5220.1     .17       0
Bank Sta=4884.8,5098.5
XS Rating Curve= 0 ,0
Exp/Cntr=0.3,0.1