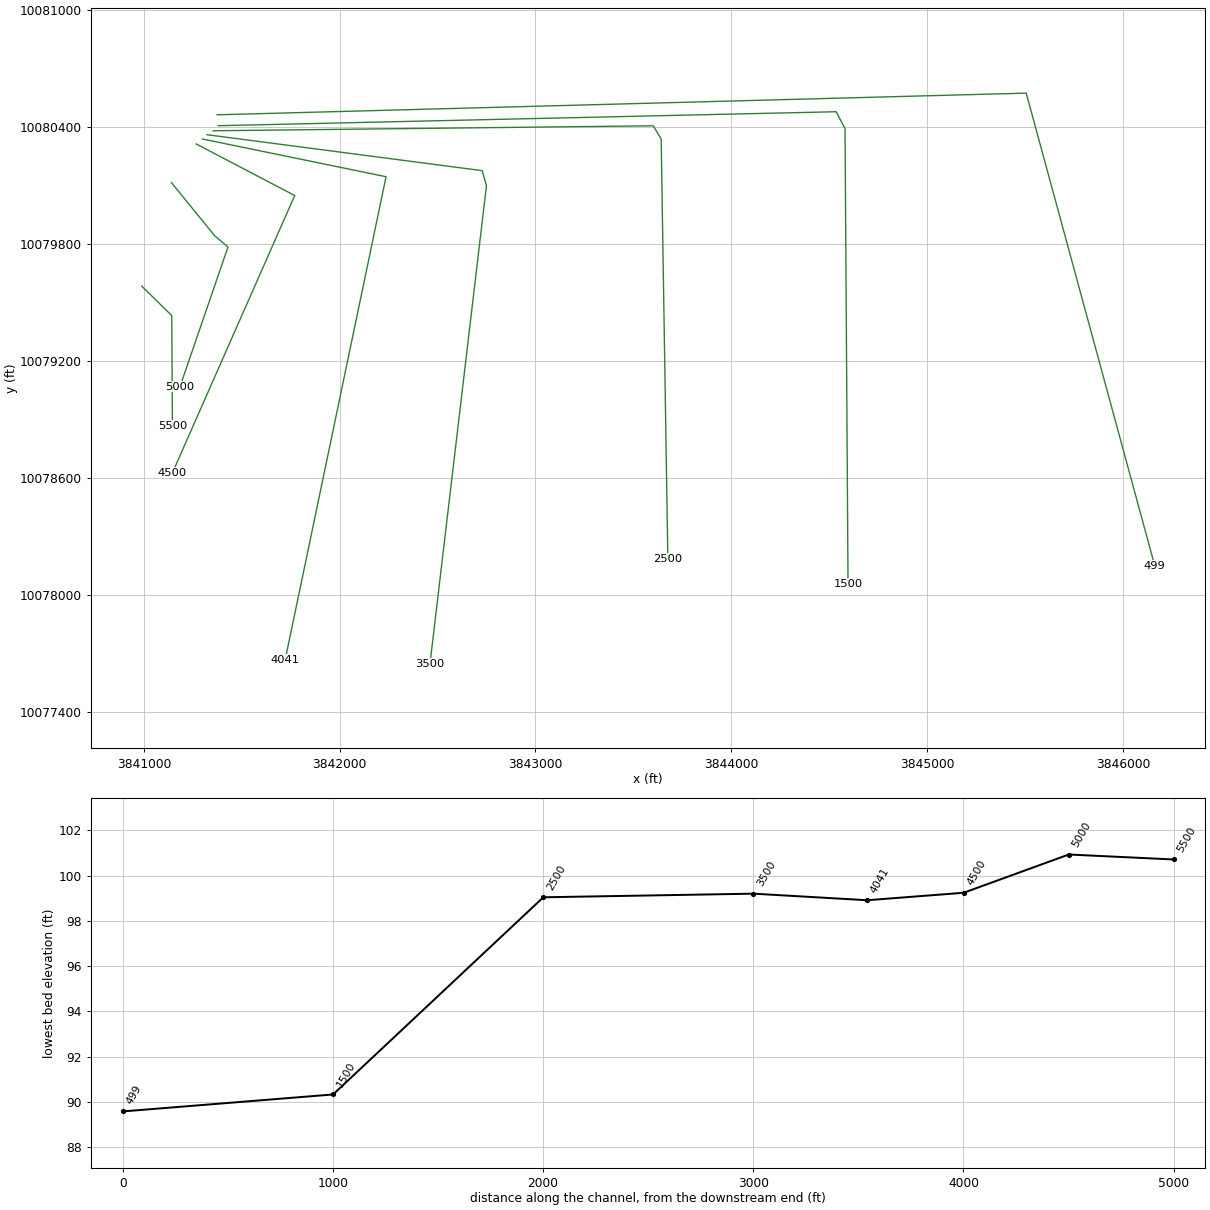
HEC-RAS study TRADE CTR DITCH_COLLEGE PK DITCH.prj: TRADE CTR DITCH_COLLEGE PK DITCH Base Level Engineering

--- TRADE CTR DITCH_COLLEGE PK DITCH.g01 (geometry) --- (continued)

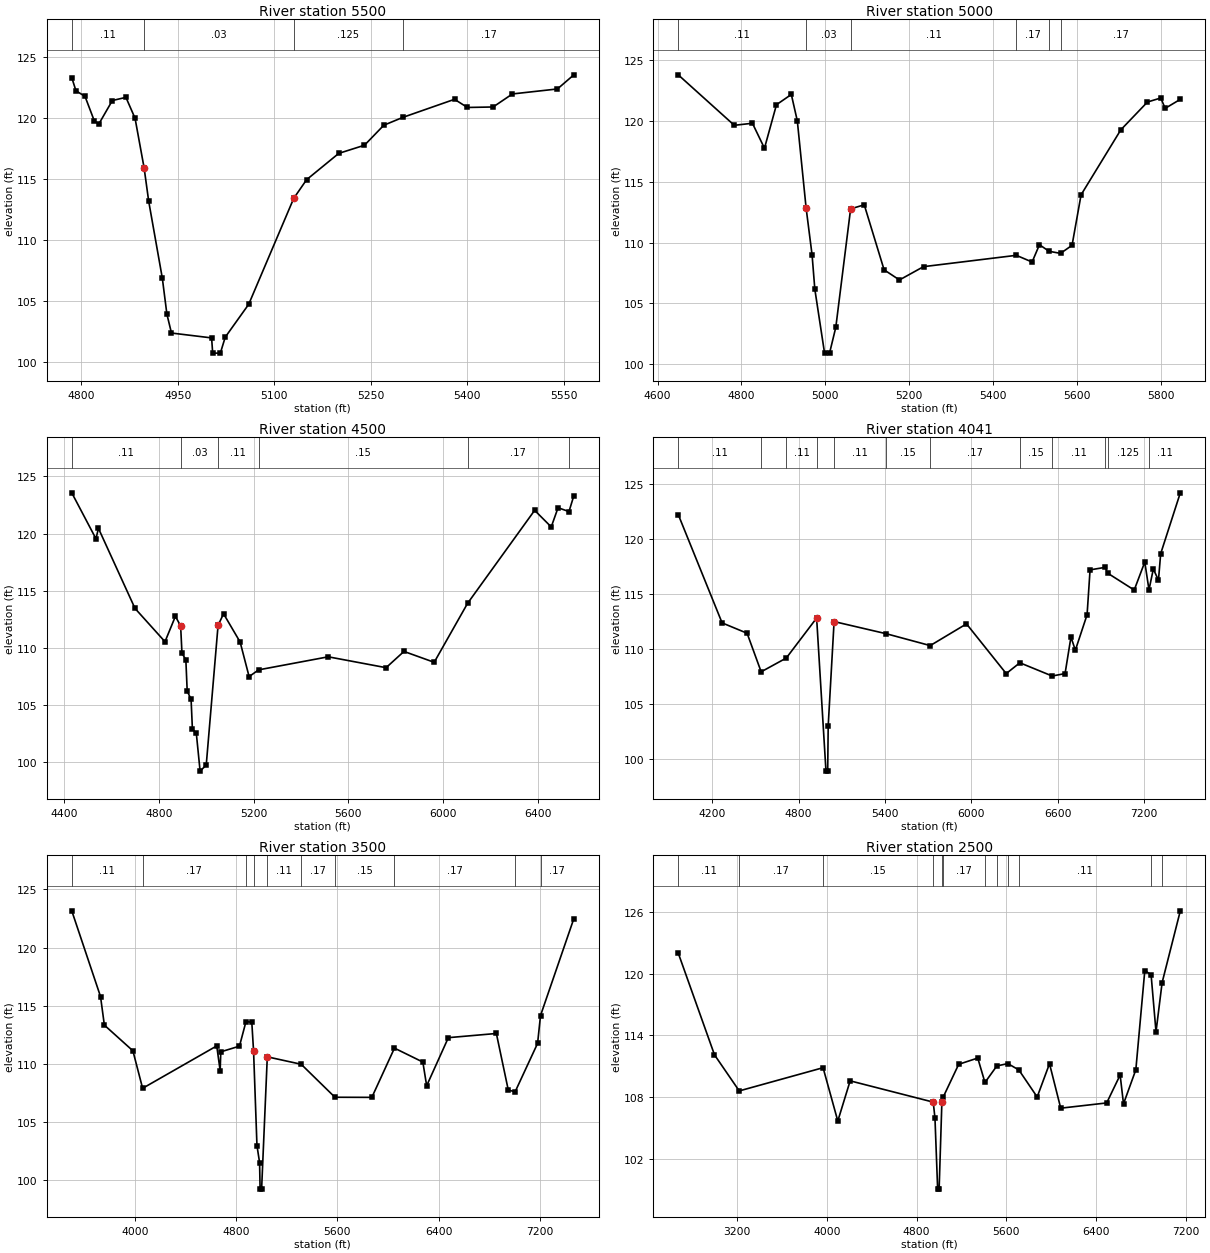
Type RM Length L Ch R = 1 ,5500    ,500,500,500
BEGIN DESCRIPTION:
TRADE CTR DITCH_COLLEGE PK DITCH 11.0
END DESCRIPTION:
XS GIS Cut Line= 3
      3840989.73     10079582.12      3841142.72     10079431.35
      3841145.97     10078865.56
#Sta/Elev= 30
  4785.2  123.33  4791.7  122.25  4805.8  121.79    4820  119.81    4827   119.5
  4848.3  121.45  4869.4  121.71  4883.6  119.99  4897.7  115.91  4904.8  113.18
    4926  106.86  4933.1  103.91  4940.2  102.36  5002.6  101.96  5004.3  100.71
  5016.2  100.71  5023.8  102.02  5060.3  104.72  5130.3  113.42  5150.3  114.95
  5200.3  117.11  5240.3  117.78  5270.3  119.42  5300.1  120.07  5380.3  121.55
  5400.3  120.88  5440.3  120.92  5470.3  121.99  5540.3   122.4  5565.8  123.56
#Mann= 4 ,-1 , 0
  4785.2     .11       0  4897.7     .03       0  5130.3    .125       0
  5300.1     .17       0
Bank Sta=4897.7,5130.3
XS Rating Curve= 0 ,0
Exp/Cntr=0.3,0.1

Type RM Length L Ch R = 1 ,5000    ,500,500,500
BEGIN DESCRIPTION:
TRADE CTR DITCH_COLLEGE PK DITCH 10.0
END DESCRIPTION:
XS GIS Cut Line= 4
       3841141.2     10080112.95      3841361.93     10079840.55
      3841429.83     10079783.08      3841184.62     10079066.96
#Sta/Elev= 30
  4649.4  123.75    4783  119.61  4826.2  119.78  4854.9  117.73  4883.5   121.3
  4918.9  122.14  4933.2  119.97  4954.1  112.84  4968.4  108.97  4974.9  106.17
  4998.1  100.93    5010  100.93  5024.9  103.05  5060.2  112.76  5092.7  113.09
    5140  107.76  5176.6  106.93  5233.9  108.02  5455.1  108.95  5492.7   108.4
  5510.2  109.82  5533.1  109.28  5560.4  109.11  5587.9  109.77  5609.4  113.91
  5704.1  119.24  5767.6  121.52  5799.3  121.85  5809.8     121  5845.9  121.74
#Mann= 6 ,-1 , 0
  4649.4     .11       0  4954.1     .03       0  5060.2     .11       0
  5455.1     .17       0  5533.1    .125       0  5560.4     .17       0
Bank Sta=4954.1,5060.2
XS Rating Curve= 0 ,0
Exp/Cntr=0.3,0.1

Type RM Length L Ch R = 1 ,4500    ,459,459,459
BEGIN DESCRIPTION:
TRADE CTR DITCH_COLLEGE PK DITCH 9.0
END DESCRIPTION:
XS GIS Cut Line= 3
      3841267.81     10080311.09      3841770.61     10080046.86
      3841145.95     10078625.14
#Sta/Elev= 30
    4432  123.56  4534.1  119.55  4544.8  120.45  4699.1  113.46  4825.8  110.55
  4869.8  112.77  4891.9  111.92  4897.5  109.54  4913.9  108.98  4919.6  106.23
    4936  105.52  4941.6  102.91    4958  102.57  4974.1   99.24    5000   99.77
    5050  111.98  5073.2  112.99  5143.2  110.52  5181.1   107.5  5221.3  108.09
  5515.4  109.23  5759.8  108.28  5835.3   109.7    5963  108.75  6103.9   113.9
  6387.3  122.03  6457.4  120.58  6486.2  122.26  6532.3  121.92  6552.9  123.31
#Mann= 6 ,-1 , 0
    4432     .11       0  4891.9     .03       0    5050     .11       0
  5221.3     .15       0  6103.9     .17       0  6532.3    .125       0
Bank Sta=4891.9,5050
XS Rating Curve= 0 ,0
Exp/Cntr=0.3,0.1

Type RM Length L Ch R = 1 ,4041    ,541,541,541
BEGIN DESCRIPTION:
TRADE CTR DITCH_COLLEGE PK DITCH 8.0
END DESCRIPTION:
XS GIS Cut Line= 3
      3841299.61     10080336.47      3842237.12     10080143.32
      3841721.94     10077667.66
#Sta/Elev= 30
  3964.7  122.19  4269.2  112.36  4442.8  111.42  4540.4  107.92  4714.9  109.17
  4925.6   112.8  4990.4   98.91  5002.3   98.91  5005.9  103.03  5046.8  112.48
  5410.6  111.37  5714.3   110.3  5966.1  112.27  6241.8  107.76  6336.6  108.74
  6560.9  107.54  6650.4  107.76  6691.3  111.07  6721.9  109.88  6803.3   113.1
    6824  117.17  6929.4   117.4  6945.2  116.88  7130.5  115.34  7203.9  117.88
  7233.1  115.36  7263.3  117.25  7298.9  116.23  7314.3  118.64  7450.6  124.16
#Mann= 12 ,-1 , 0
  3964.7     .11       0  4540.4     .17       0  4714.9     .11       0
  4925.6     .03       0  5046.8     .11       0  5410.6     .15       0
  5714.3     .17       0  6336.6     .15       0  6560.9     .11       0
  6929.4     .15       0  6945.2    .125       0  7233.1     .11       0
Bank Sta=4925.6,5046.8
XS Rating Curve= 0 ,0
Exp/Cntr=0.3,0.1

Type RM Length L Ch R = 1 ,3500    ,1000,1000,1000
BEGIN DESCRIPTION:
TRADE CTR DITCH_COLLEGE PK DITCH 7.0
END DESCRIPTION:
XS GIS Cut Line= 4
      3841322.67     10080358.59      3842728.15     10080174.37
       3842749.9     10080096.86      3842461.51     10077646.78
#Sta/Elev= 30
    3502  123.16  3729.1  115.78  3759.4  113.32  3984.7  111.11  4061.5  107.88
  4646.9  111.53  4673.8   109.4  4678.9  111.02  4826.4  111.51  4877.9  113.63
  4923.8  113.56  4937.7  111.08  4964.5  102.95  4985.2  101.49  4989.3    99.2
  5001.2    99.2  5046.1  110.59  5313.8  109.95  5580.3  107.11  5871.8   107.1
  6050.3  111.34  6274.5  110.14  6304.7   108.1  6475.9  112.24  6855.1   112.6
  6949.2  107.73  7003.3  107.58  7180.7  111.75  7203.7  114.14    7467  122.49
#Mann= 10 ,-1 , 0
    3502     .11       0  4061.5     .17       0  4877.9     .11       0
  4937.7     .03       0  5046.1     .11       0  5313.8     .17       0
  5580.3     .15       0  6050.3     .17       0  7003.3     .15       0
  7203.7     .17       0
Bank Sta=4937.7,5046.1
XS Rating Curve= 0 ,0
Exp/Cntr=0.3,0.1

Type RM Length L Ch R = 1 ,2500    ,1000,1000,1000
BEGIN DESCRIPTION:
TRADE CTR DITCH_COLLEGE PK DITCH 5.0
END DESCRIPTION:
XS GIS Cut Line= 4
       3841354.4      10080378.8      3843601.82     10080404.33
      3843642.21     10080336.86      3843676.42     10078184.33
#Sta/Elev= 30
  2673.8  122.02  2997.3  112.11    3218   108.6  3965.9  110.86  4097.3  105.67
  4207.4  109.58  4948.6  107.51  4964.1  105.95    4988   99.04  5001.2   99.04
  5025.8  107.53  5035.8  107.96  5175.8  111.19  5345.8   111.8    5410  109.42
    5516  111.03  5614.3  111.26  5712.6  110.64  5875.9  108.01  5985.9  111.25
  6085.9  106.92    6496  107.43    6616  110.15    6646  107.34    6756  110.66
    6836  120.31  6892.1  119.91    6936  114.35  6990.4  119.14  7152.8  126.13
#Mann= 12 ,-1 , 0
  2673.8     .11       0    3218     .17       0  3965.9     .15       0
  4948.6     .03       0  5025.8     .15       0  5035.8     .17       0
    5410     .15       0    5516     .17       0  5614.3     .15       0
  5712.6     .11       0  6892.1    .125       0  6990.4     .11       0
Bank Sta=4948.6,5025.8
XS Rating Curve= 0 ,0
Exp/Cntr=0.3,0.1

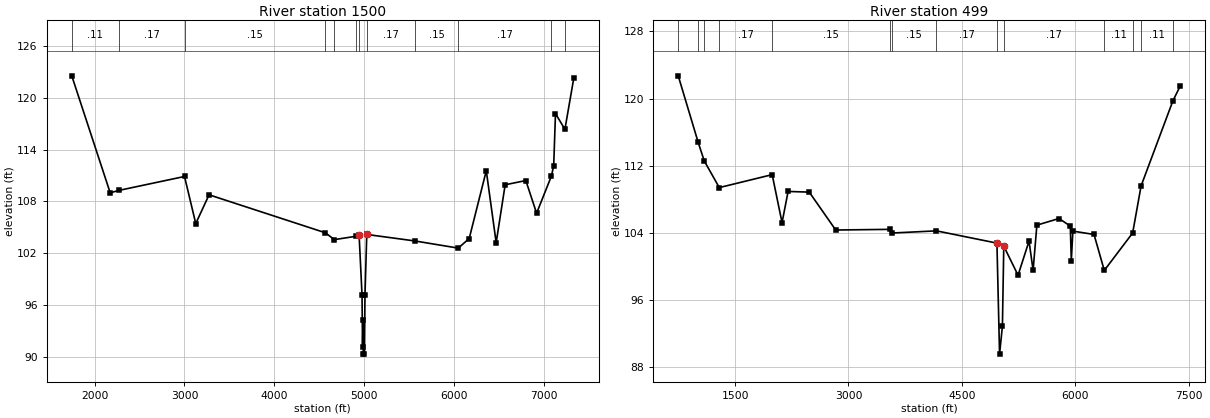
Type RM Length L Ch R = 1 ,1500    ,1001,1001,1001
BEGIN DESCRIPTION:
TRADE CTR DITCH_COLLEGE PK DITCH 3.0
END DESCRIPTION:
XS GIS Cut Line= 4
      3841380.47     10080404.84      3844535.97     10080476.43
      3844581.25     10080389.88      3844596.58     10078056.73
#Sta/Elev= 30
    1746  122.54  2173.5     109  2270.9  109.28  3000.7  110.89  3125.8  105.44
  3273.8  108.77  4569.5  104.37    4668  103.58  4913.9  103.98  4943.3  104.16
  4976.1   97.16  4981.8   91.18  4987.4   94.25  4989.8   90.33  5003.2   90.33
  5008.8   97.17  5028.8  104.18  5563.6  103.43  6046.9   102.6  6168.8  103.71
  6358.8  111.56  6468.8  103.23  6568.8  109.93  6798.8  110.42  6918.8  106.64
  7083.6  110.94  7108.9  112.14  7128.9  118.17  7233.7  116.35  7333.2  122.31
#Mann= 12 ,-1 , 0
    1746     .11       0  2270.9     .17       0  3000.7     .15       0
  4569.5     .17       0    4668     .15       0  4913.9     .17       0
  4943.3     .03       0  5028.8     .17       0  5563.6     .15       0
  6046.9     .17       0  7083.6     .11       0  7233.7    .125       0
Bank Sta=4943.3,5028.8
XS Rating Curve= 0 ,0
Exp/Cntr=0.3,0.1

Type RM Length L Ch R = 1 ,499     ,0,0,0
BEGIN DESCRIPTION:
TRADE CTR DITCH_COLLEGE PK DITCH 1.0
END DESCRIPTION:
XS GIS Cut Line= 3
      3841374.67     10080460.68       3845506.6     10080571.79
      3846163.13       10078149.
#Sta/Elev= 30
   747.5   122.7  1011.4  114.78  1091.4  112.58  1290.7   109.4  1990.5  110.94
  2121.2  105.23  2201.2  108.94  2481.3  108.86  2831.4  104.35  3550.8  104.43
  3572.7  103.99  4164.3  104.25  4964.6  102.79  4999.3   89.58  5037.1   92.91
  5055.2  102.43    5244   98.97  5389.3  103.03  5443.2   99.55    5493  104.93
  5786.2  105.72  5935.2  104.82  5948.8  100.72  5969.5  104.22  6249.3  103.82
  6385.1   99.54  6760.6     104  6872.1   109.6  7292.8  119.72  7391.1  121.51
#Mann= 14 ,-1 , 0
   747.5     .11       0  1011.4     .17       0  1091.4     .11       0
  1290.7     .17       0  1990.5     .15       0  3550.8     .17       0
  3572.7     .15       0  4164.3     .17       0  4964.6     .03       0
  5055.2     .17       0  6385.1     .11       0  6760.6     .17       0
  6872.1     .11       0  7292.8     .15       0
Bank Sta=4964.6,5055.2
XS Rating Curve= 0 ,0
Exp/Cntr=0.3,0.1

Chan Stop Cuts=-1
Use User Specified Reach Order=0
Composite Channel Slope=5

--- TRADE CTR DITCH_COLLEGE PK DITCH.g10 (geometry) ---

Geom Title=Existing Conditions
Program Version=4.10

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
River Reach=TRADE CTR DITCH_,Reach-1

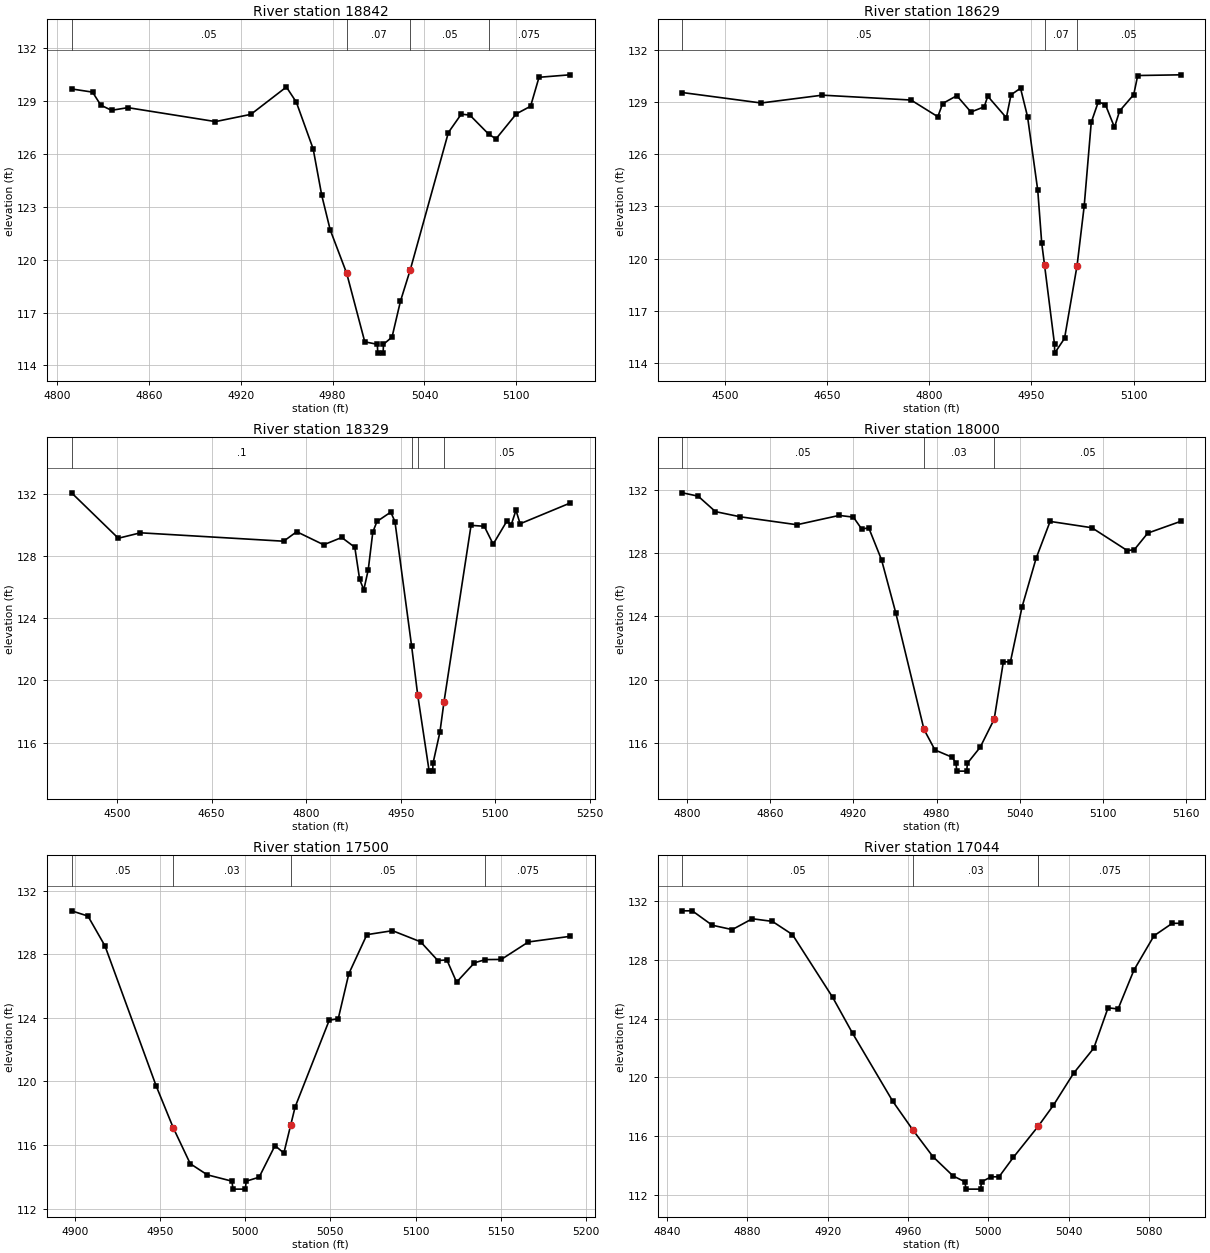
Type RM Length L Ch R = 1 ,18842   ,213,213,213
BEGIN DESCRIPTION:
TRADE CTR DITCH_COLLEGE PK DITCH 37.0
END DESCRIPTION:
XS GIS Cut Line= 3
      3833074.06      10075238.8      3833251.99     10075319.09
      3833369.21     10075375.52
#Sta/Elev= 30
  4809.5  129.67  4823.2  129.49  4828.6  128.75  4835.6  128.46  4846.3  128.61
  4903.5  127.82  4926.6  128.23  4949.8  129.78  4956.3  128.92  4967.3  126.27
  4972.9  123.64  4978.4  121.69  4989.2  119.22    5001  115.34  5009.2   115.2
  5009.5   114.7    5013   114.7  5013.2   115.2  5018.8  115.61  5024.3  117.64
 5030.74 119.431  5055.6   127.2    5064  128.24  5069.6  128.19  5081.9  127.11
  5086.7  126.84    5100  128.26  5109.3  128.69  5114.8  130.33  5134.8  130.47
#Mann= 4 ,-1 , 0
  4809.5     .05       0  4989.2     .07       0 5030.74     .05       0
  5081.9    .075       0
Bank Sta=4989.2,5030.74
XS Rating Curve= 0 ,0
Exp/Cntr=0.3,0.1

Type RM Length L Ch R = 1 ,18629   ,300,300,300
BEGIN DESCRIPTION:
Mapping XS 729a8b13
END DESCRIPTION:
XS GIS Cut Line= 2
      3832610.17     10075355.27      3833313.95     10075552.88
#Sta/Elev= 30
  4437.9  129.55  4553.4  128.95  4643.2   129.4  4773.4  129.12  4812.7  128.16
  4819.8  128.92  4840.6  129.37  4861.3  128.43  4880.8  128.73    4886  129.34
  4913.3   128.1  4920.1  129.42  4934.1   129.8  4944.4  128.16  4959.4  123.92
  4965.2  120.89 4969.29 119.639    4984  115.06  4984.2  114.56  4998.7  115.41
  5017.1   119.6  5027.5  123.01  5037.9  127.84  5048.3  129.02  5058.7  128.85
    5072  127.55  5079.5  128.49  5100.2  129.43  5106.1  130.53  5168.9  130.57
#Mann= 3 , 0 , 0
  4437.9     .05       0 4969.29     .07       0  5017.1     .05       0
Bank Sta=4969.29,5017.1
XS Rating Curve= 0 ,0
Exp/Cntr=0.3,0.1

Type RM Length L Ch R = 1 ,18329   ,329,329,329
BEGIN DESCRIPTION:
Mapping XS f0aa4bc0
END DESCRIPTION:
XS GIS Cut Line= 2
      3832690.02     10076157.38      3833290.78     10075643.43
#Sta/Elev= 30
  4427.6  132.06  4501.8  129.14  4536.9  129.49  4764.2  128.95    4785  129.56
  4827.8  128.72  4856.4  129.19  4877.2  128.56  4884.9  126.49  4891.5  125.83
  4898.5  127.11  4905.8  129.54  4912.4  130.22  4934.3  130.82  4940.9  130.21
  4967.4   122.2  4977.1  119.04  4995.2  114.17  5000.8  114.17  5001.3  114.67
  5012.3  116.68  5018.8  118.63  5061.7  129.97  5082.7  129.91  5096.8  128.76
  5118.7  130.25  5125.3  129.98    5133  130.94  5139.6  130.07  5218.2  131.39
#Mann= 4 ,-1 , 0
  4427.6      .1       0  4967.4     .05       0  4977.1     .07       0
  5018.8     .05       0
Bank Sta=4977.1,5018.8
XS Rating Curve= 0 ,0
Exp/Cntr=0.3,0.1

Type RM Length L Ch R = 1 ,18000   ,500,500,500
BEGIN DESCRIPTION:
TRADE CTR DITCH_COLLEGE PK DITCH 36.0
END DESCRIPTION:
XS GIS Cut Line= 3
      3833399.02     10076042.19      3833436.22     10075842.43
      3833418.55     10075687.63
#Sta/Elev= 30
  4796.8  131.83  4808.1  131.62  4820.6  130.64  4838.6  130.31  4879.3  129.81
  4909.8   130.4    4920  130.29    4926  129.54  4931.1  129.61  4940.3  127.59
  4950.5  124.25  4970.9  116.85  4978.8  115.55  4991.2  115.09    4994  114.71
  4994.5  114.21  5001.7  114.21  5002.2  114.71  5011.4  115.72  5021.5   117.5
  5028.1  121.13  5033.2  121.13  5041.6  124.61  5051.7  127.68  5061.8  130.02
  5091.9  129.62  5117.5  128.17  5122.5  128.23  5132.2  129.28  5155.8  130.02
#Mann= 3 , 0 , 0
  4796.8     .05       0  4970.9     .03       0  5021.5     .05       0
Bank Sta=4970.9,5021.5
XS Rating Curve= 0 ,0
Exp/Cntr=0.3,0.1

Type RM Length L Ch R = 1 ,17500   ,456,456,456
BEGIN DESCRIPTION:
TRADE CTR DITCH_COLLEGE PK DITCH 35.0
END DESCRIPTION:
XS GIS Cut Line= 3
      3833939.38     10075950.65      3833936.18      10075848.9
      3833995.38     10075668.04
#Sta/Elev= 30
  4898.2  130.74  4907.8  130.41  4917.8  128.53  4947.8  119.72  4957.8  117.09
  4967.8  114.82  4977.8  114.12  4992.3  113.72  4992.8  113.22  5000.1  113.22
  5000.6  113.72  5008.2  113.97  5017.5  115.96  5022.7  115.49 5026.65 117.226
  5029.3  118.39  5049.3  123.85  5054.6  123.95  5060.8  126.78  5071.4  129.24
  5086.4  129.49  5102.9  128.79    5113  127.61  5118.3  127.65    5124  126.25
  5134.5  127.47  5140.9  127.67  5150.2  127.68  5166.1  128.78  5190.3  129.13
#Mann= 4 ,-1 , 0
  4898.2     .05       0  4957.8     .03       0 5026.65     .05       0
  5140.9    .075       0
Bank Sta=4957.8,5026.65
XS Rating Curve= 0 ,0
Exp/Cntr=0.3,0.1

Type RM Length L Ch R = 1 ,17044   ,135,135,135
BEGIN DESCRIPTION:
TRADE CTR DITCH_COLLEGE PK DITCH 34.0
END DESCRIPTION:
XS GIS Cut Line= 3
      3834388.95     10076025.88      3834390.68     10075868.15
      3834394.15     10075777.86
#Sta/Elev= 30
  4847.6  131.36  4852.5  131.36  4862.4  130.38  4872.4  130.08  4882.4  130.82
  4892.4  130.64  4902.4  129.74  4922.4  125.47  4932.4     123  4952.4  118.37
  4962.4  116.42  4972.4   114.6  4982.4  113.29  4988.3  112.89  4988.8  112.39
  4996.1  112.39  4996.6  112.89  5001.4  113.23  5005.3  113.23  5012.4  114.55
  5024.9  116.69  5032.4  118.11  5042.4  120.28  5052.5     122  5059.6  124.75
  5064.6  124.67  5072.5  127.32  5082.5  129.66  5091.6  130.51  5095.7  130.51
#Mann= 4 ,-1 , 0
  4847.6     .05       0  4962.4     .03       0  5024.9     .05       0
  5024.9    .075       0
Bank Sta=4962.4,5024.9
XS Rating Curve= 0 ,0
Exp/Cntr=0.3,0.1

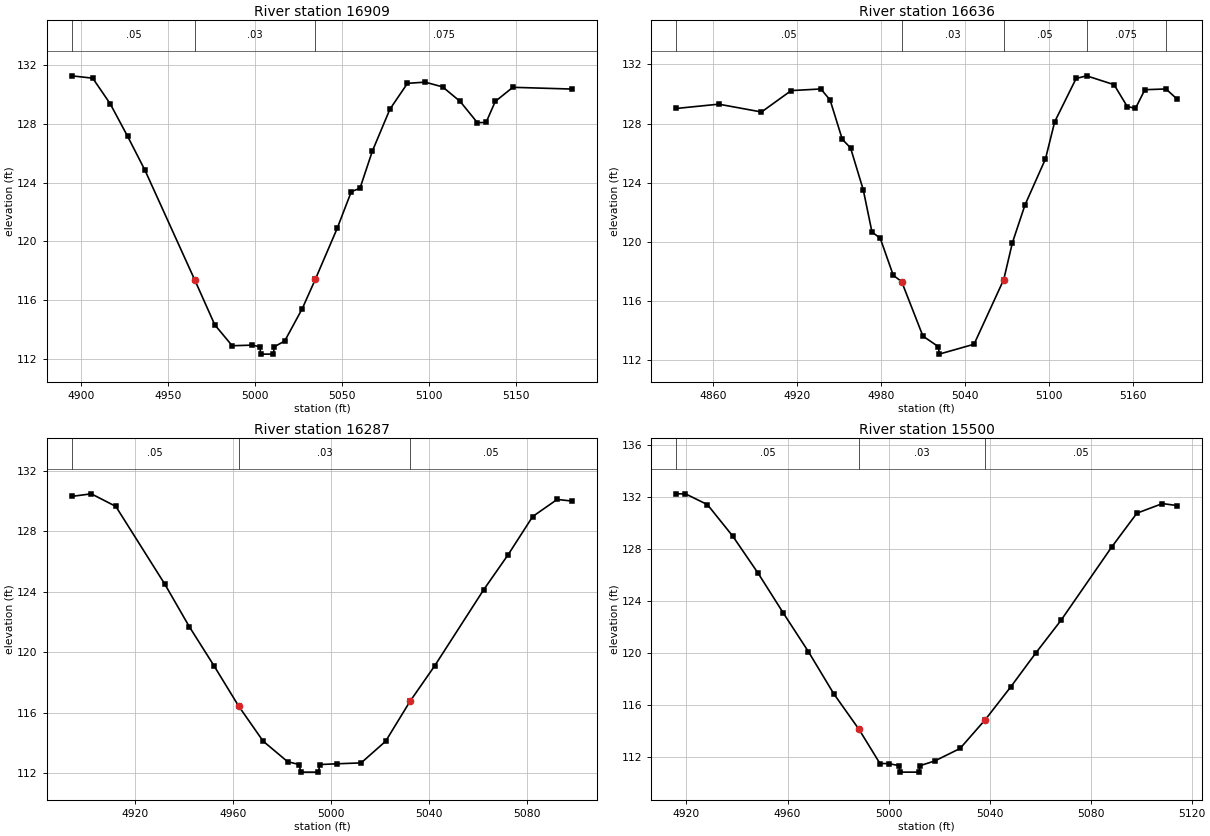
Type RM Length L Ch R = 1 ,16909   ,273,273,273
BEGIN DESCRIPTION:
TRADE CTR DITCH_COLLEGE PK DITCH 33.0
END DESCRIPTION:
XS GIS Cut Line= 3
      3834531.36     10075993.17       3834524.8     10075889.56
      3834549.54     10075707.25
#Sta/Elev= 30
  4894.5  131.25  4906.6  131.09  4916.6  129.36  4926.7  127.13  4936.7  124.82
  4965.4 117.347  4976.8  114.33  4986.8  112.91  4998.3  112.95  5002.7  112.84
  5003.2  112.34  5010.5  112.34    5011  112.84    5017  113.23  5027.1  115.43
  5034.6  117.42  5047.2  120.89  5055.3  123.38  5060.3  123.61  5067.4  126.13
  5077.5  128.98  5087.6  130.74  5097.7  130.82  5107.8   130.5  5117.9  129.51
  5127.8  128.07  5132.8  128.08  5138.1  129.51  5148.2  130.47  5182.3  130.35
#Mann= 3 , 0 , 0
  4894.5     .05       0  4965.4     .03       0  5034.6    .075       0
Bank Sta=4965.4,5034.6
XS Rating Curve= 0 ,0
Exp/Cntr=0.3,0.1

Type RM Length L Ch R = 1 ,16636   ,349,349,349
BEGIN DESCRIPTION:
Mapping XS 58514661
END DESCRIPTION:
XS GIS Cut Line= 2
      3834565.02     10076160.84      3834867.12     10075969.86
#Sta/Elev= 30
  4833.8  129.02  4864.1  129.31  4894.6  128.78  4915.8  130.23    4937  130.34
  4943.6  129.59  4952.3  126.93  4958.2  126.35  4967.3   123.5  4973.5  120.65
  4979.4  120.23  4988.7  117.72  4994.7  117.29  5009.9   113.6    5021  112.88
  5021.5  112.38  5046.4  113.05  5067.6  117.43  5073.8  119.93  5082.8  122.49
  5097.4   125.6    5104  128.12  5119.3  131.05  5126.8  131.23  5146.4  130.63
  5155.8  129.15  5161.7  129.03  5168.4  130.29  5183.5  130.34  5191.2  129.67
#Mann= 5 ,-1 , 0
  4833.8     .05       0  4994.7     .03       0  5067.6     .05       0
  5126.8    .075       0  5183.5     .05       0
Bank Sta=4994.7,5067.6
XS Rating Curve= 0 ,0
Exp/Cntr=0.3,0.1

Type RM Length L Ch R = 1 ,16287   ,787,787,787
BEGIN DESCRIPTION:
TRADE CTR DITCH_COLLEGE PK DITCH 32.0
END DESCRIPTION:
XS GIS Cut Line= 3
       3834619.9      10076408.7      3834720.61     10076414.85
      3834823.91     10076415.64
#Sta/Elev= 23
  4894.1   130.3  4902.1  130.47  4912.1  129.64  4932.1   124.5  4942.1  121.69
  4952.2   119.1  4962.2  116.45  4972.2  114.13  4982.2  112.77    4987  112.58
  4987.5  112.08  4994.8  112.08  4995.3  112.58  5002.2  112.63  5012.2  112.69
  5022.2  114.12  5032.2  116.77  5042.2   119.1  5062.2  124.13  5072.2  126.45
  5082.2  128.97  5092.2   130.1  5098.3  129.99
#Mann= 3 , 0 , 0
  4894.1     .05       0  4962.2     .03       0  5032.2     .05       0
Bank Sta=4962.2,5032.2
XS Rating Curve= 0 ,0
Exp/Cntr=0.3,0.1

Type RM Length L Ch R = 1 ,15500   ,500,500,500
BEGIN DESCRIPTION:
TRADE CTR DITCH_COLLEGE PK DITCH 31.0
END DESCRIPTION:
XS GIS Cut Line= 3
      3834575.59     10077200.71      3834659.58     10077199.54
      3834773.59     10077204.15
#Sta/Elev= 25
    4916  132.27  4919.6  132.27  4928.3  131.44  4938.3  129.02  4948.3  126.18
  4958.3  123.11  4968.3  120.12  4978.3  116.89  4988.3  114.15  4996.6  111.52
    5000  111.52  5004.1  111.36  5004.6  110.86    5012  110.86  5012.5  111.36
  5018.3  111.72  5028.3  112.68  5038.3   114.9  5048.3   117.4  5058.3  120.03
  5068.3  122.55  5088.3  128.17  5098.3  130.78  5108.4  131.52  5114.1  131.37
#Mann= 3 , 0 , 0
    4916     .05       0  4988.3     .03       0  5038.3     .05       0
Bank Sta=4988.3,5038.3
XS Rating Curve= 0 ,0
Exp/Cntr=0.3,0.1