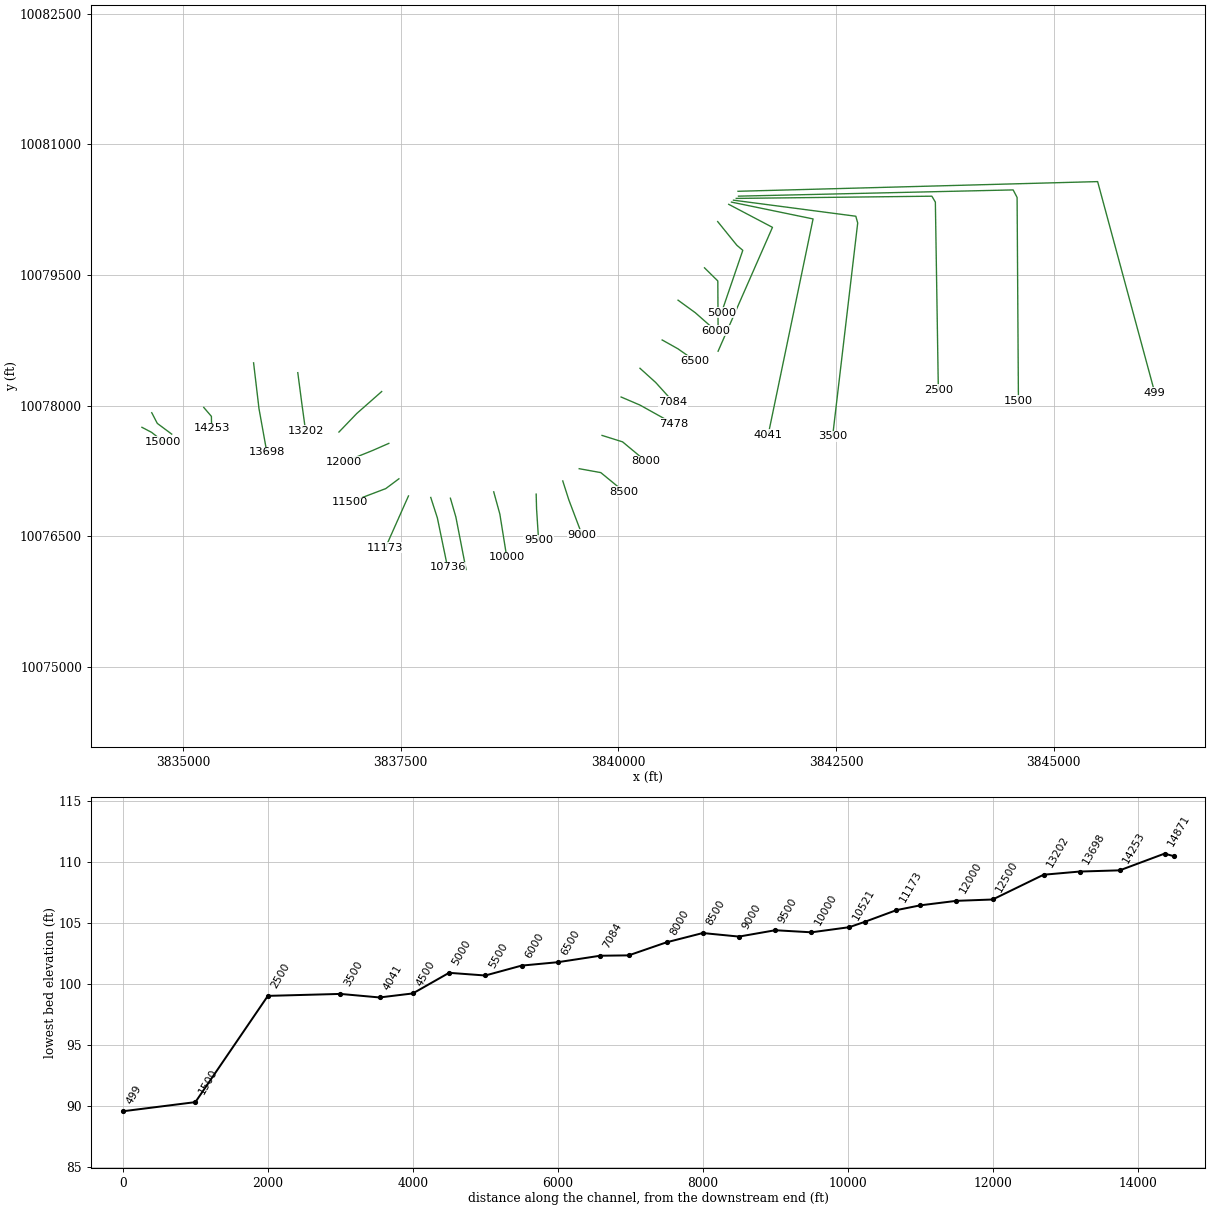
HEC-RAS study TRADE CTR DITCH_COLLEGE PK DITCH.prj: TRADE CTR DITCH_COLLEGE PK DITCH Base Level Engineering

--- TRADE CTR DITCH_COLLEGE PK DITCH.g10 (geometry) --- (continued)

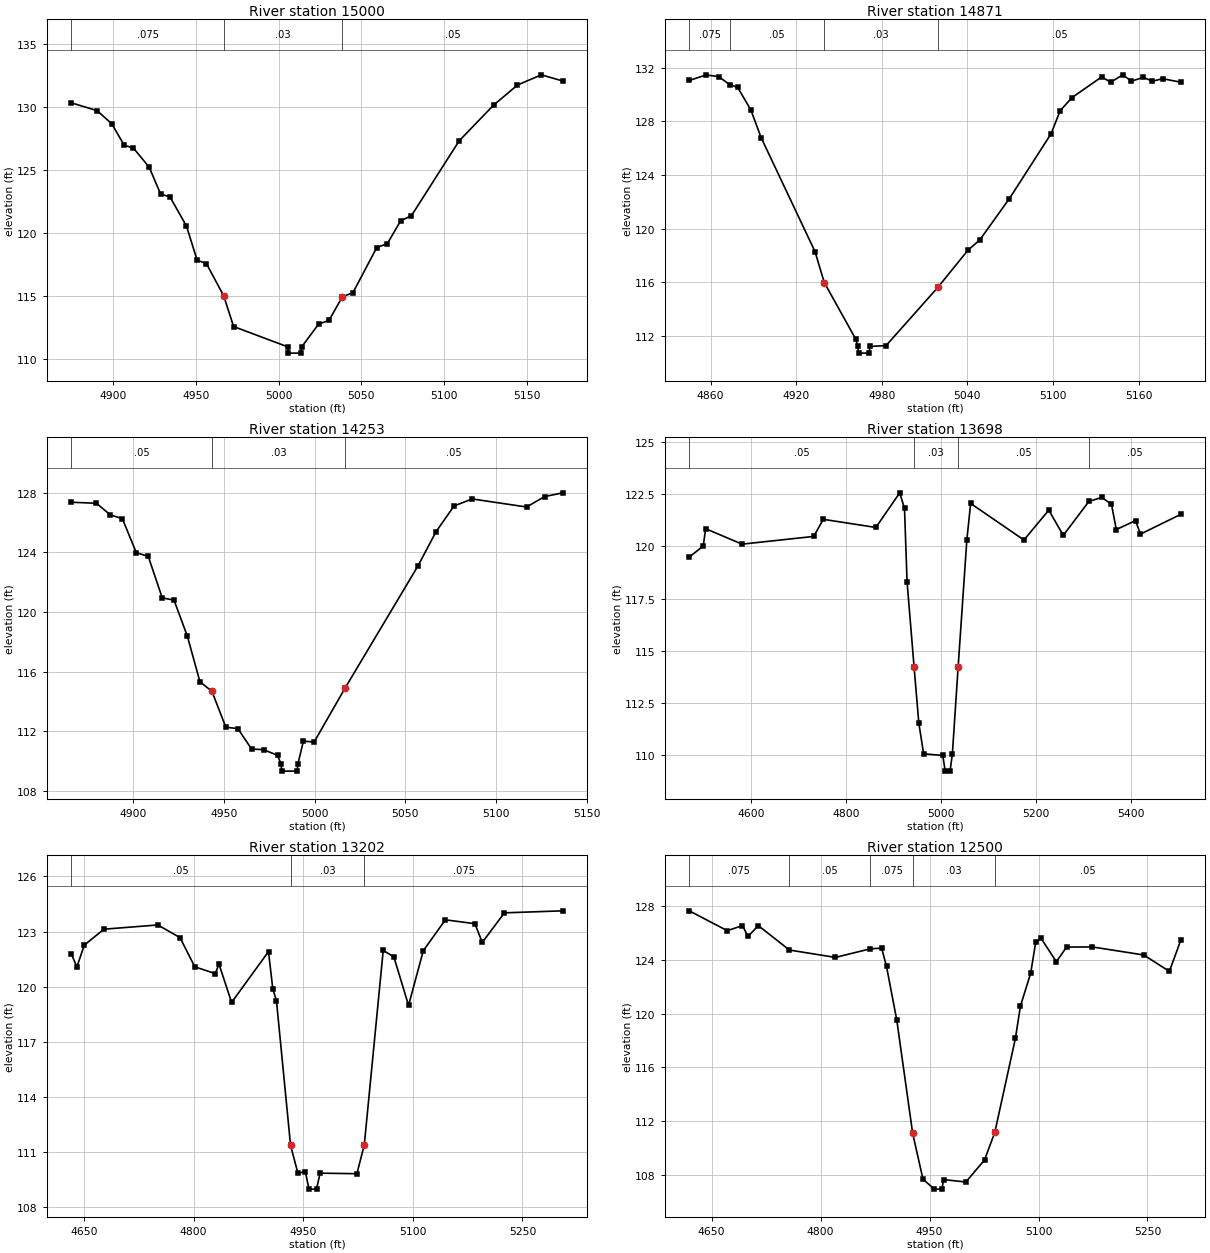
Type RM Length L Ch R = 1 ,15000   ,129,129,129
BEGIN DESCRIPTION:
TRADE CTR DITCH_COLLEGE PK DITCH 30.0
END DESCRIPTION:
XS GIS Cut Line= 3
      3834526.12     10077751.75      3834637.32     10077693.59
      3834772.62     10077587.71
#Sta/Elev= 30
  4874.5  130.35  4890.1  129.73    4899  128.69  4906.5  126.99  4912.1  126.76
  4921.6  125.25  4928.6   123.1  4934.2  122.89  4944.2  120.57  4950.6  117.88
  4956.3  117.58  4966.7  115.04  4972.7   112.6  5005.4  110.99  5005.9  110.49
  5013.4  110.49  5013.9  110.99  5024.1  112.79  5030.4  113.09  5038.5  114.96
  5044.9  115.29  5059.3  118.87  5065.7  119.18  5073.8     121  5080.2  121.38
  5109.1  127.33  5129.9  130.16  5144.4  131.76  5158.8  132.57  5171.8  132.08
#Mann= 3 , 0 , 0
  4874.5    .075       0  4966.7     .03       0  5038.5     .05       0
Bank Sta=4966.7,5038.5
XS Rating Curve= 0 ,0
Exp/Cntr=0.3,0.1

Type RM Length L Ch R = 1 ,14871   ,618,618,618
BEGIN DESCRIPTION:
TRADE CTR DITCH_COLLEGE PK DITCH 29.0
END DESCRIPTION:
XS GIS Cut Line= 3
      3834638.94     10077919.33      3834702.33     10077796.89
      3834868.15     10077673.61
#Sta/Elev= 30
  4845.1  131.05  4856.8  131.46  4865.7  131.34  4873.4  130.74    4879  130.53
  4888.2  128.86  4895.5  126.77  4933.2  118.28  4939.7  115.97  4961.9  111.72
  4963.2   111.2  4963.7   110.7  4971.2   110.7  4971.7   111.2    4983  111.26
  5019.4  115.62  5040.3  118.37  5048.7  119.15  5069.5  122.24  5098.7  127.08
    5105  128.79  5113.3  129.77  5134.2  131.32  5140.4  130.91  5148.8  131.47
    5155     131  5163.4  131.28  5169.6  130.99  5176.8  131.18  5189.6  130.92
#Mann= 4 ,-1 , 0
  4845.1    .075       0  4873.4     .05       0  4939.7     .03       0
  5019.4     .05       0
Bank Sta=4939.7,5019.4
XS Rating Curve= 0 ,0
Exp/Cntr=0.3,0.1

Type RM Length L Ch R = 1 ,14253   ,555,555,555
BEGIN DESCRIPTION:
TRADE CTR DITCH_COLLEGE PK DITCH 28.0
END DESCRIPTION:
XS GIS Cut Line= 3
       3835236.5     10077979.79       3835324.4     10077877.06
      3835326.57     10077741.09
#Sta/Elev= 30
  4865.7  127.35  4879.6  127.28  4887.3   126.5  4893.9  126.25  4901.6  123.97
  4908.2  123.72  4915.9  120.94  4922.4  120.79  4929.8  118.36  4936.7  115.32
  4943.3  114.68    4951  112.27  4957.6  112.18  4965.2  110.81  4971.8  110.77
  4979.5  110.39  4981.4  109.83  4981.9  109.33  4990.3  109.33  4990.8  109.83
  4993.8  111.34  4999.7  111.28  5016.9  114.92  5056.9  123.06  5066.9  125.36
  5076.9   127.1  5086.9  127.57  5116.9  127.03  5126.9  127.73  5136.9  127.98
#Mann= 3 , 0 , 0
  4865.7     .05       0  4943.3     .03       0  5016.9     .05       0
Bank Sta=4943.3,5016.9
XS Rating Curve= 0 ,0
Exp/Cntr=0.3,0.1

Type RM Length L Ch R = 1 ,13698   ,496,496,496
BEGIN DESCRIPTION:
TRADE CTR DITCH_COLLEGE PK DITCH 27.0
END DESCRIPTION:
XS GIS Cut Line= 3
      3835808.97     10078491.53      3835871.06     10077965.83
      3835960.89     10077467.21
#Sta/Elev= 30
  4469.6  119.49    4499  120.02    4504  120.85  4580.8  120.11  4731.9  120.48
    4752   121.3  4862.8  120.91  4913.1  122.57  4923.2  121.82  4928.6   118.3
  4943.3  114.24  4953.4  111.52  4963.5  110.06  5003.9  109.98  5008.9  109.23
  5019.2  109.23  5024.1  110.06 5036.17 114.204  5054.6  120.32  5062.6  122.06
  5174.9  120.31  5227.3  121.74  5257.8  120.53  5311.9  122.16  5339.1  122.35
  5359.4  122.02  5369.6  120.81  5410.2  121.24  5420.4  120.59  5505.6  121.54
#Mann= 4 ,-1 , 0
  4469.6     .05       0  4943.3     .03       0 5036.17     .05       0
  5311.9     .05       0
Bank Sta=4943.3,5036.17
XS Rating Curve= 0 ,0
Exp/Cntr=0.3,0.1

Type RM Length L Ch R = 1 ,13202   ,702,702,702
BEGIN DESCRIPTION:
TRADE CTR DITCH_COLLEGE PK DITCH 26.0
END DESCRIPTION:
XS GIS Cut Line= 3
      3836316.78     10078378.73      3836364.55     10078015.31
      3836406.22      10077711.9
#Sta/Elev= 30
  4632.5   121.8  4640.2  121.07  4650.3  122.26  4677.3  123.13    4751  123.36
  4781.4  122.67  4801.6  121.08  4829.7  120.71  4834.7  121.23    4852  119.14
  4902.5  121.91  4908.4  119.87  4913.4  119.23  4932.7  111.35  4942.8  109.83
  4952.9  109.93  4957.8  108.97  4968.2  108.97  4973.1  109.84  5023.5  109.81
  5033.6  111.38  5059.5  121.97    5074  121.63  5094.2  118.98  5114.4  121.96
  5144.6  123.64    5185  123.43  5195.1  122.41  5225.4  124.02  5305.3  124.13
#Mann= 3 , 0 , 0
  4632.5     .05       0  4932.7     .03       0  5033.6    .075       0
Bank Sta=4932.7,5033.6
XS Rating Curve= 0 ,0
Exp/Cntr=0.3,0.1

Type RM Length L Ch R = 1 ,12500   ,500,500,500
BEGIN DESCRIPTION:
TRADE CTR DITCH_COLLEGE PK DITCH 25.0
END DESCRIPTION:
XS GIS Cut Line= 3
      3837280.55       10078162.      3836994.71     10077910.39
      3836789.61      10077697.1
#Sta/Elev= 30
  4619.2  127.67  4671.5  126.19  4692.4  126.57    4700  125.76  4714.2  126.57
    4757  124.75  4820.4   124.2  4868.3  124.84    4884  124.89  4890.7  123.53
  4904.9  119.51  4926.7   111.1  4940.9  107.68  4956.5  106.94  4967.1  106.94
  4969.2  107.65    5000  107.47  5025.7  109.12  5039.8  111.17  5068.1  118.16
  5075.1  120.58  5089.2  123.03  5096.2  125.37  5103.4  125.63  5124.5  123.88
  5138.6  124.97  5174.1  124.98  5244.9  124.38  5280.1  123.16  5295.9  125.49
#Mann= 5 ,-1 , 0
  4619.2    .075       0    4757     .05       0  4868.3    .075       0
  4926.7     .03       0  5039.8     .05       0
Bank Sta=4926.7,5039.8
XS Rating Curve= 0 ,0
Exp/Cntr=0.3,0.1

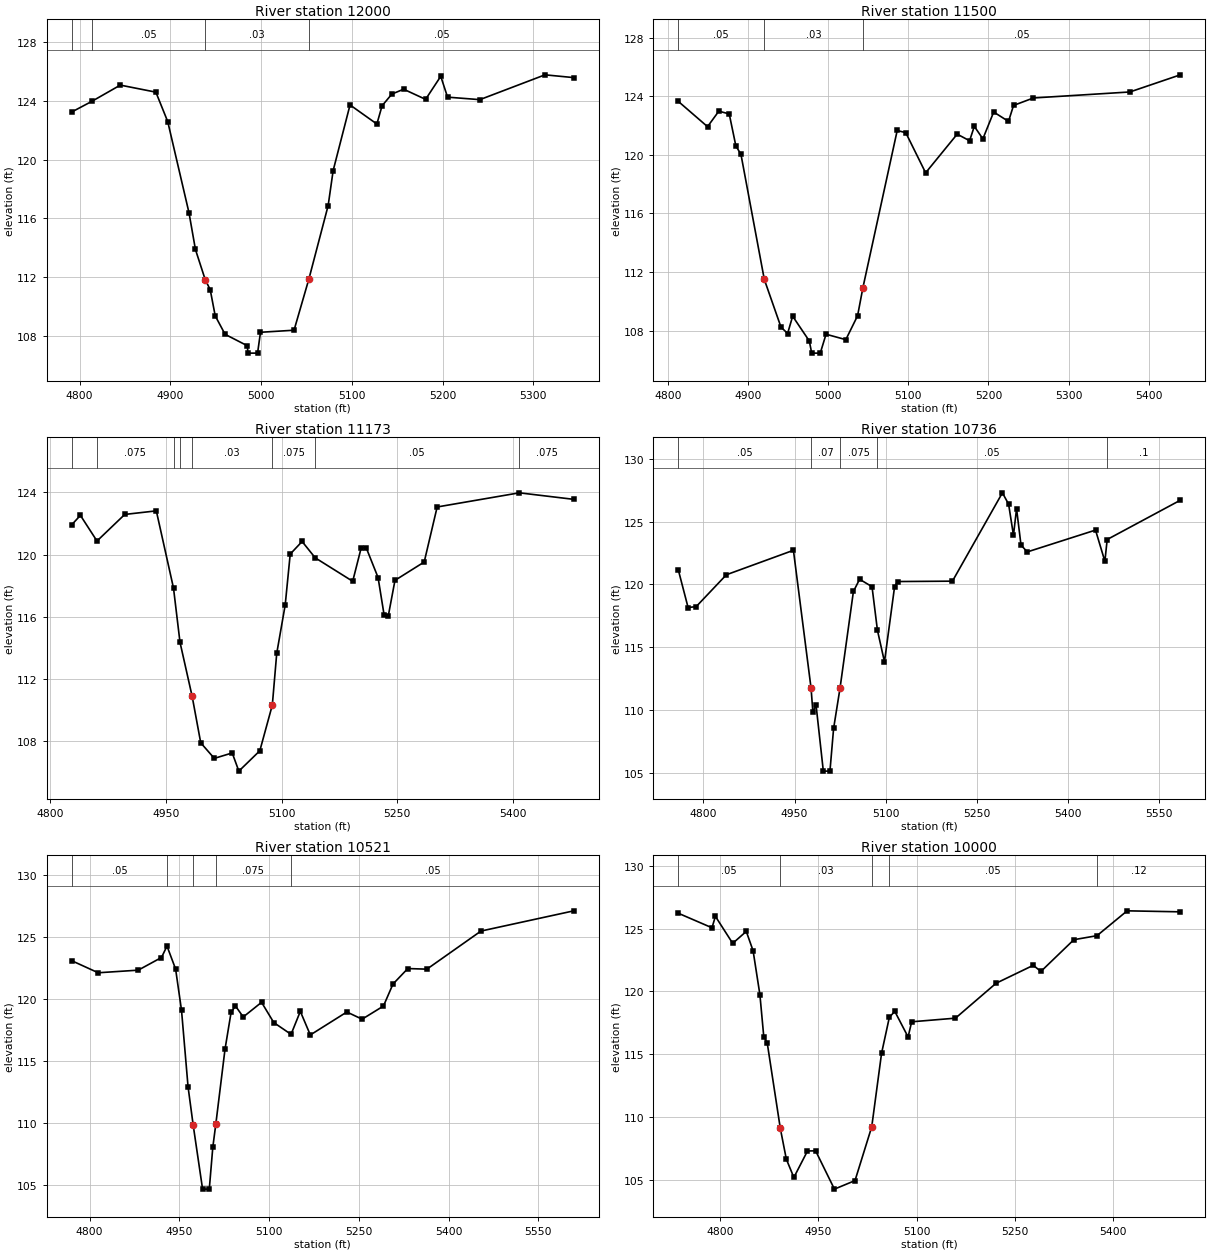
Type RM Length L Ch R = 1 ,12000   ,500,500,500
BEGIN DESCRIPTION:
TRADE CTR DITCH_COLLEGE PK DITCH 24.0
END DESCRIPTION:
XS GIS Cut Line= 3
      3837362.77     10077567.07      3837171.49     10077483.61
      3836851.74     10077354.85
#Sta/Elev= 30
  4791.3  123.25  4813.6  123.98  4844.8  125.08    4884   124.6  4897.1  122.59
  4920.5  116.39  4927.6  113.89  4938.4  111.83  4943.9  111.15  4949.4  109.37
  4960.3  108.11  4984.9  107.33  4985.4  106.83  4996.1  106.83  4999.3  108.25
  5036.3  108.39 5052.74 111.895  5073.9  116.88  5079.4  119.26    5098  123.73
  5127.6  122.43  5133.3  123.67  5144.1  124.47  5157.1   124.8  5181.3  124.11
    5198  125.68  5205.5  124.26  5241.1  124.09  5312.9  125.78  5344.7  125.59
#Mann= 4 ,-1 , 0
  4791.3    .075       0  4813.6     .05       0  4938.4     .03       0
 5052.74     .05       0
Bank Sta=4938.4,5052.74
XS Rating Curve= 0 ,0
Exp/Cntr=0.3,0.1

Type RM Length L Ch R = 1 ,11500   ,327,327,327
BEGIN DESCRIPTION:
TRADE CTR DITCH_COLLEGE PK DITCH 23.0
END DESCRIPTION:
XS GIS Cut Line= 3
      3837478.48      10077160.7      3837328.24     10077048.54
      3836917.28     10076892.46
#Sta/Elev= 30
  4812.5  123.65  4849.1  121.92  4863.2  122.98  4876.2  122.79  4884.5   120.6
  4890.8  120.04    4920  111.49  4940.8  108.24  4949.1   107.8  4955.4  108.98
  4976.2  107.29  4979.2  106.46  4989.9  106.46  4997.1  107.75  5021.8  107.38
  5036.5  109.01  5043.2  110.94    5086  121.66  5096.7  121.51  5121.5  118.77
  5160.9  121.41  5176.4  120.96  5182.3  121.94    5193  121.09  5206.5  122.92
    5225  122.28  5231.3  123.37  5256.1  123.88  5376.6  124.29  5439.6  125.46
#Mann= 3 , 0 , 0
  4812.5     .05       0    4920     .03       0  5043.2     .05       0
Bank Sta=4920,5043.2
XS Rating Curve= 0 ,0
Exp/Cntr=0.3,0.1

Type RM Length L Ch R = 1 ,11173   ,437,437,437
BEGIN DESCRIPTION:
Mapping XS c8a7ec25
END DESCRIPTION:
XS GIS Cut Line= 2
       3837588.5     10076963.82      3837323.74      10076369.2
#Sta/Elev= 30
  4827.9  121.92  4839.1  122.52  4860.6  120.87  4896.6  122.58  4937.5  122.81
  4959.8  117.84  4968.2  114.36    4984  110.87  4995.1  107.89  5012.7  106.89
  5035.9  107.24  5044.5  106.07  5071.7  107.38  5087.9  110.32  5093.6  113.64
  5104.6  116.76  5111.1  120.03  5126.5  120.84  5143.5  119.79  5192.1  118.28
  5203.1  120.43  5209.6  120.44    5225  118.52  5232.8  116.12  5238.3  116.07
  5246.9  118.34  5284.8  119.52  5301.6  123.06  5408.1  123.97  5478.8  123.55
#Mann= 8 ,-1 , 0
  4827.9     .05       0  4860.6    .075       0  4959.8     .05       0
  4968.2    .075       0    4984     .03       0  5087.9    .075       0
  5143.5     .05       0  5408.1    .075       0
Bank Sta=4984,5087.9
XS Rating Curve= 0 ,0
Exp/Cntr=0.3,0.1

Type RM Length L Ch R = 1 ,10736   ,215,215,215
BEGIN DESCRIPTION:
TRADE CTR DITCH_COLLEGE PK DITCH 22.0
END DESCRIPTION:
XS GIS Cut Line= 3
      3837844.55     10076946.45      3837920.28     10076712.32
      3838038.01     10076144.47
#Sta/Elev= 30
  4758.7  121.17  4774.9  118.15  4788.2  118.22  4837.9  120.76  4948.2  122.71
 4977.22 111.723  4980.2  109.83  4985.5  110.35  4997.4  105.11  5008.3  105.11
  5014.3  108.51 5024.88 111.725  5046.9  119.43  5057.1   120.4  5077.5  119.81
  5086.4  116.34    5098  113.82  5114.6   119.8  5119.7  120.22  5209.8  120.25
    5292  127.29  5302.2  126.39  5310.2  123.91  5315.3  126.02  5322.6  123.13
  5332.9  122.58  5445.2  124.32  5460.6  121.83  5464.4  123.57  5584.7   126.7
#Mann= 5 ,-1 , 0
  4758.7     .05       0 4977.22     .07       0 5024.88    .075       0
  5086.4     .05       0  5464.4      .1       0
Bank Sta=4977.22,5024.88
XS Rating Curve= 0 ,0
Exp/Cntr=0.3,0.1

Type RM Length L Ch R = 1 ,10521   ,521,521,521
BEGIN DESCRIPTION:
TRADE CTR DITCH_COLLEGE PK DITCH 21.0
END DESCRIPTION:
XS GIS Cut Line= 3
      3838070.26     10076937.72      3838133.02     10076722.07
      3838250.52      10076118.6
#Sta/Elev= 30
  4770.1  123.07  4814.3   122.1  4881.2  122.31  4920.1  123.33  4929.3  124.25
  4943.7   122.4  4953.6  119.07  4964.5  112.92 4972.98 109.862  4988.8  104.67
    5000  104.67  5005.9  108.05 5010.91 109.902  5026.3  115.94  5036.5  118.92
  5043.8  119.42  5056.8  118.54  5087.4  119.72  5107.8  118.09  5136.7  117.14
  5152.2  118.99  5168.9  117.09    5230  118.94  5255.5  118.36  5291.2  119.42
  5307.1  121.19  5331.9  122.44  5363.8  122.39  5454.2  125.46  5609.5  127.09
#Mann= 5 ,-1 , 0
  4770.1     .05       0  4929.3    .075       0 4972.98     .07       0
 5010.91    .075       0  5136.7     .05       0
Bank Sta=4972.98,5010.91
XS Rating Curve= 0 ,0
Exp/Cntr=0.3,0.1

Type RM Length L Ch R = 1 ,10000   ,500,500,500
BEGIN DESCRIPTION:
TRADE CTR DITCH_COLLEGE PK DITCH 20.0
END DESCRIPTION:
XS GIS Cut Line= 3
      3838567.84     10077011.12      3838638.16     10076756.86
      3838717.86     10076261.03
#Sta/Elev= 30
  4736.2  126.23  4787.7  125.07  4792.9  125.98  4819.3  123.83    4840  124.78
  4850.4  123.24  4860.8  119.74  4866.7  116.39  4871.9  115.92  4891.9   109.1
  4901.1  106.64  4912.6  105.18  4933.4  107.29  4945.8   107.3  4974.5  104.25
  5005.9  104.93 5031.41 109.214  5046.4  115.07  5058.3  117.94  5066.6  118.41
  5086.9  116.37  5092.3  117.58  5159.2  117.87  5221.1  120.65  5277.9  122.08
  5289.5  121.59  5339.8  124.12  5375.1  124.44  5421.1  126.42  5502.2  126.34
#Mann= 5 ,-1 , 0
  4736.2     .05       0  4891.9     .03       0 5031.41    .075       0
  5058.3     .05       0  5375.1     .12       0
Bank Sta=4891.9,5031.41
XS Rating Curve= 0 ,0
Exp/Cntr=0.3,0.1

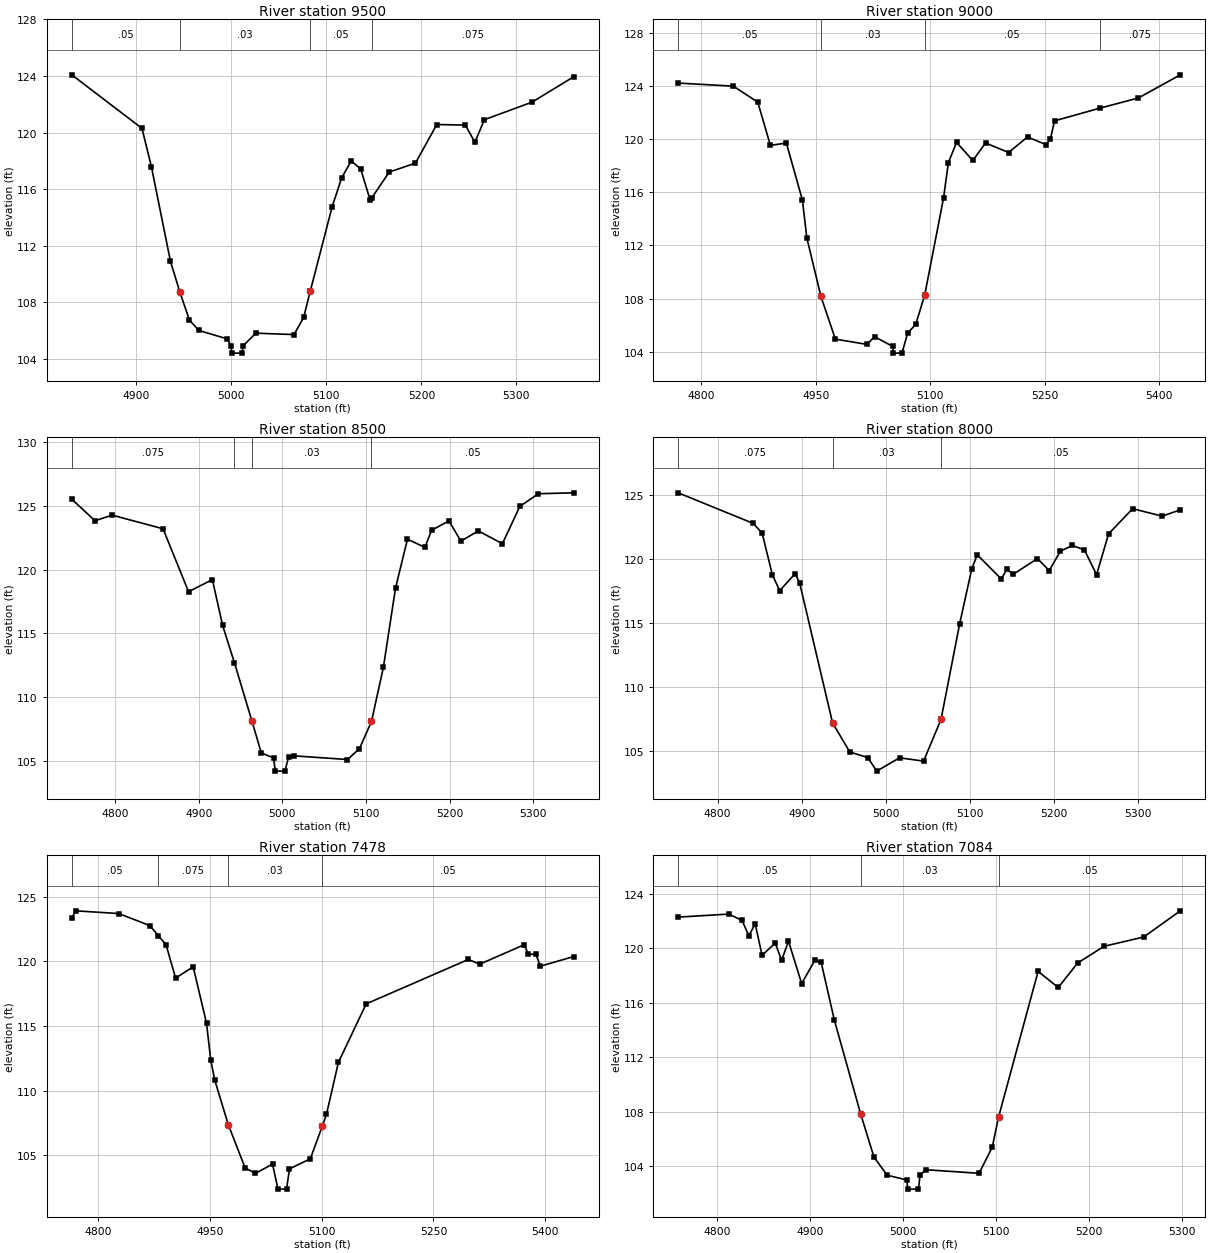
Type RM Length L Ch R = 1 ,9500    ,500,500,500
BEGIN DESCRIPTION:
TRADE CTR DITCH_COLLEGE PK DITCH 19.0
END DESCRIPTION:
XS GIS Cut Line= 3
       3839055.7      10076984.9      3839060.17     10076816.86
      3839083.48     10076457.12
#Sta/Elev= 30
  4831.9  124.08  4905.8   120.3  4915.8  117.57  4935.8  110.91  4945.8  108.71
  4955.8  106.75  4965.8  106.02  4995.4  105.43  4999.7  104.92  5000.2  104.42
  5011.5  104.42    5012  104.92  5025.8  105.83  5065.9  105.73    5076  106.94
 5082.94 108.786    5106  114.75    5116  116.79  5126.1     118  5136.1  117.43
  5146.1  115.22    5148  115.41  5166.1  117.21  5193.7  117.84  5216.2  120.57
  5246.3  120.53  5256.3  119.31  5266.3  120.91  5316.5  122.15  5360.5  123.95
#Mann= 4 ,-1 , 0
  4831.9     .05       0  4945.8     .03       0 5082.94     .05       0
    5148    .075       0
Bank Sta=4945.8,5082.94
XS Rating Curve= 0 ,0
Exp/Cntr=0.3,0.1

Type RM Length L Ch R = 1 ,9000    ,500,500,500
BEGIN DESCRIPTION:
TRADE CTR DITCH_COLLEGE PK DITCH 18.0
END DESCRIPTION:
XS GIS Cut Line= 3
      3839361.24     10077135.99      3839431.47     10076916.86
      3839583.17     10076516.97
#Sta/Elev= 30
  4769.9   124.2    4842  123.97  4874.1  122.77  4890.6  119.52  4911.6  119.69
  4932.6   115.4  4938.4  112.56 4956.85 108.158  4975.8  104.95  5016.9  104.56
  5027.2  105.13  5051.1   104.4  5051.6   103.9    5063   103.9  5070.4  105.39
  5081.1  106.07  5092.8  108.26  5117.6  115.59  5123.8  118.21  5134.5  119.74
  5155.9  118.38  5172.5   119.7  5202.7  118.98  5227.5  120.15  5252.2  119.56
  5257.6  120.02  5262.9  121.36    5322  122.31  5372.8  123.08  5427.7  124.82
#Mann= 4 ,-1 , 0
  4769.9     .05       0 4956.85     .03       0  5092.8     .05       0
    5322    .075       0
Bank Sta=4956.85,5092.8
XS Rating Curve= 0 ,0
Exp/Cntr=0.3,0.1

Type RM Length L Ch R = 1 ,8500    ,500,500,500
BEGIN DESCRIPTION:
TRADE CTR DITCH_COLLEGE PK DITCH 17.0
END DESCRIPTION:
XS GIS Cut Line= 3
      3839550.47     10077276.57      3839798.24     10077231.69
      3840067.87     10077011.05
#Sta/Elev= 30
  4748.2  125.53    4776  123.84  4796.4  124.28  4857.3  123.21  4887.8  118.27
  4916.3  119.22  4928.5  115.63  4942.7  112.69 4963.64 108.102  4974.8  105.61
  4989.4  105.23  4991.6  104.19    5003  104.19  5007.4   105.3  5013.9  105.39
  5077.8   105.1  5092.1  105.95  5106.5  108.09  5120.8  112.36  5135.2  118.55
  5149.5  122.39  5170.4  121.75  5178.3  123.09  5199.1  123.83  5213.4  122.24
  5234.2  123.04    5263  122.04  5283.8  124.96    5306  125.96  5348.4  126.03
#Mann= 4 ,-1 , 0
  4748.2    .075       0  4942.7     .05       0 4963.64     .03       0
  5106.5     .05       0
Bank Sta=4963.64,5106.5
XS Rating Curve= 0 ,0
Exp/Cntr=0.3,0.1

Type RM Length L Ch R = 1 ,8000    ,522,522,522
BEGIN DESCRIPTION:
TRADE CTR DITCH_COLLEGE PK DITCH 16.0
END DESCRIPTION:
XS GIS Cut Line= 3
      3839812.63     10077658.52      3840048.24      10077584.7
      3840317.86     10077361.07
#Sta/Elev= 30
  4753.1  125.15  4842.4  122.76  4852.9     122  4865.1  118.74  4873.8  117.52
  4892.3  118.85  4897.6  118.09  4936.7  107.19  4957.2  104.92  4978.6  104.49
  4989.2  103.43  5016.3  104.47  5044.9  104.21  5065.7  107.47  5087.9  114.95
  5102.2   119.2  5108.7  120.32  5137.4  118.42  5143.9  119.17  5151.7   118.8
  5180.4  120.02  5194.4  119.08  5207.7   120.6    5222  121.04  5236.3  120.69
  5250.7  118.76    5265  121.95  5293.6  123.91  5328.8  123.33  5350.3  123.82
#Mann= 3 , 0 , 0
  4753.1    .075       0  4936.7     .03       0  5065.7     .05       0
Bank Sta=4936.7,5065.7
XS Rating Curve= 0 ,0
Exp/Cntr=0.3,0.1

Type RM Length L Ch R = 1 ,7478    ,394,394,394
BEGIN DESCRIPTION:
TRADE CTR DITCH_COLLEGE PK DITCH 15.0
END DESCRIPTION:
XS GIS Cut Line= 3
      3840031.39     10078099.49      3840248.24     10078006.86
      3840631.79     10077793.92
#Sta/Elev= 30
  4764.2  123.34  4769.3  123.92  4827.4  123.71  4869.1  122.77  4880.4     122
  4890.8   121.3  4903.7  118.71  4927.3  119.58  4945.2  115.22  4950.9  112.36
  4956.3   110.8  4974.5  107.35  4997.1     104    5011  103.58  5033.9   104.3
  5041.2  102.36  5052.7  102.36  5056.7  103.93  5084.7  104.71  5100.7  107.23
  5106.4  108.16  5122.4  112.18  5159.7  116.71  5296.9  120.15  5312.4  119.79
  5371.9  121.29  5377.6  120.57  5387.9  120.54  5393.6  119.63  5438.7  120.38
#Mann= 4 ,-1 , 0
  4764.2     .05       0  4880.4    .075       0  4974.5     .03       0
  5100.7     .05       0
Bank Sta=4974.5,5100.7
XS Rating Curve= 0 ,0
Exp/Cntr=0.3,0.1

Type RM Length L Ch R = 1 ,7084    ,584,584,584
BEGIN DESCRIPTION:
TRADE CTR DITCH_COLLEGE PK DITCH 14.0
END DESCRIPTION:
XS GIS Cut Line= 3
       3840248.5     10078428.91      3840428.24     10078266.86
      3840628.44     10078045.86
#Sta/Elev= 30
    4758  122.27  4812.4  122.49  4826.6  122.03    4834  120.91  4840.8  121.78
  4848.2  119.47  4862.4  120.37  4869.2  119.09  4876.6  120.51  4890.8   117.4
    4905   119.1  4911.8  118.95    4926  114.71  4954.4  107.81  4968.6  104.68
  4982.8  103.35    5004     103  5004.9  102.33  5016.5  102.33  5018.2  103.39
  5024.9  103.75  5081.7  103.49  5095.9  105.41  5102.6   107.6  5145.2  118.29
  5166.9  117.11  5187.8  118.91  5216.2  120.13  5258.8  120.81  5298.2  122.73
#Mann= 3 , 0 , 0
    4758     .05       0  4954.4     .03       0  5102.6     .05       0
Bank Sta=4954.4,5102.6
XS Rating Curve= 0 ,0
Exp/Cntr=0.3,0.1

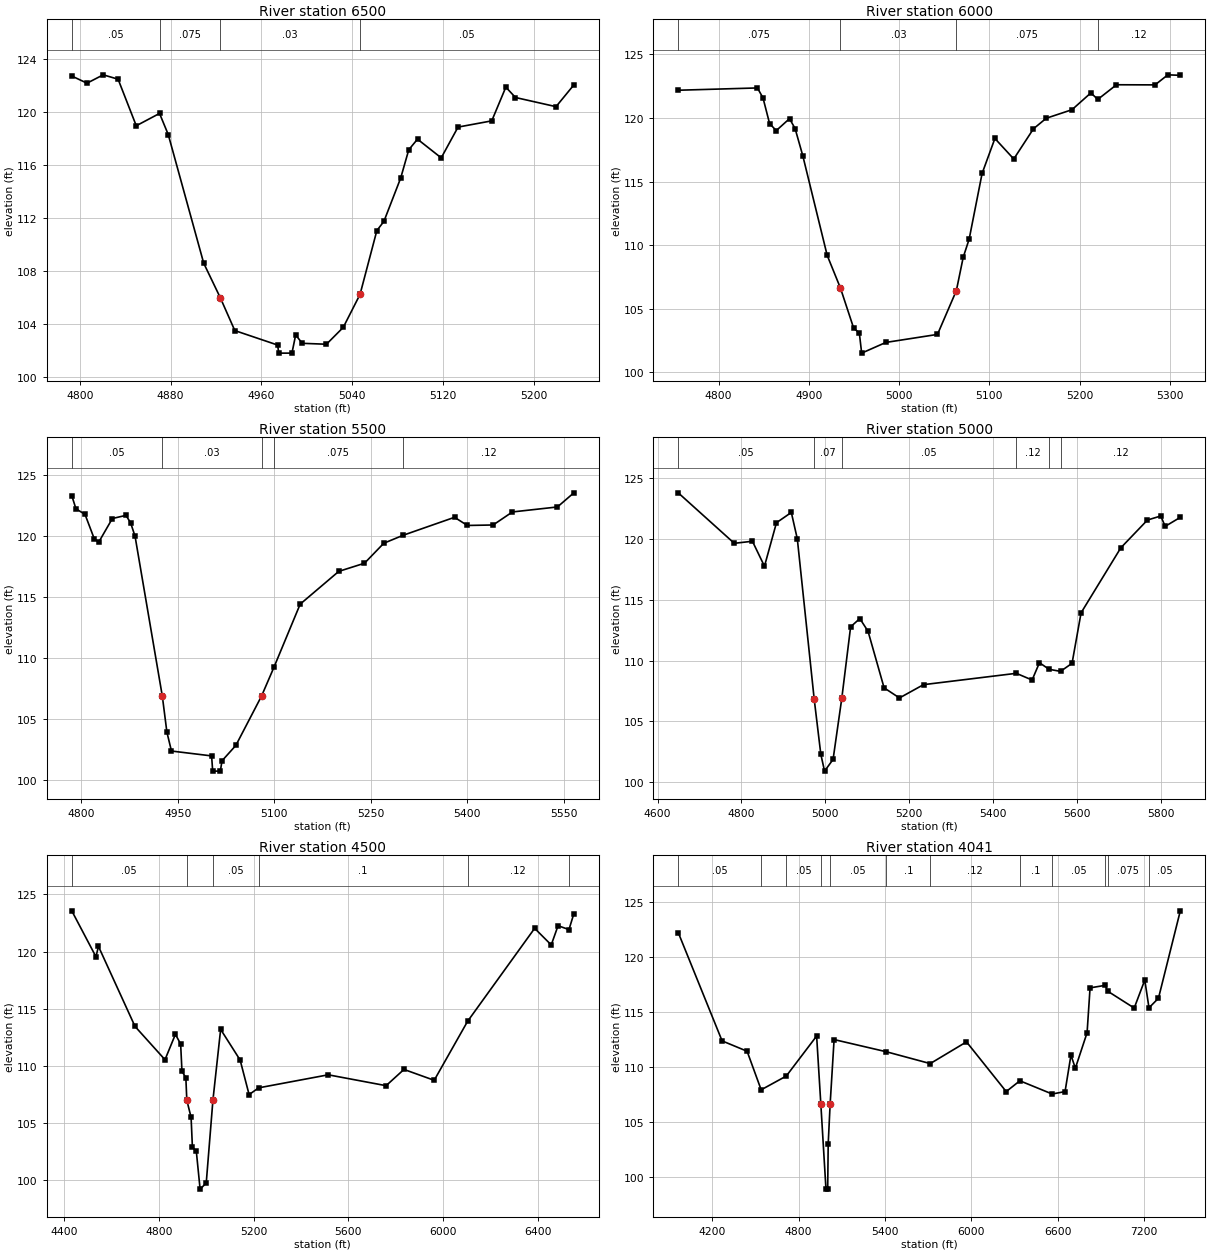
Type RM Length L Ch R = 1 ,6500    ,500,500,500
BEGIN DESCRIPTION:
TRADE CTR DITCH_COLLEGE PK DITCH 13.0
END DESCRIPTION:
XS GIS Cut Line= 3
      3840503.65     10078753.98      3840684.32     10078652.94
      3840876.88     10078517.89
#Sta/Elev= 30
    4793  122.69  4806.4  122.15  4820.7  122.78  4833.8  122.45  4849.8  118.94
  4870.3  119.87    4878  118.27  4909.2  108.58  4923.8  105.98  4936.6   103.5
  4974.3  102.41  4975.3   101.8  4986.9   101.8  4990.2  103.17    4996  102.54
  5017.3  102.47  5032.1  103.74  5046.9  106.23  5061.7  111.04  5067.9  111.73
  5082.7     115  5089.8  117.13  5097.5  117.93  5118.4  116.52  5133.2  118.84
  5162.9  119.31  5175.3  121.85  5183.8  121.07  5219.5  120.38  5235.2  122.02
#Mann= 4 ,-1 , 0
    4793     .05       0  4870.3    .075       0  4923.8     .03       0
  5046.9     .05       0
Bank Sta=4923.8,5046.9
XS Rating Curve= 0 ,0
Exp/Cntr=0.3,0.1

Type RM Length L Ch R = 1 ,6000    ,500,500,500
BEGIN DESCRIPTION:
TRADE CTR DITCH_COLLEGE PK DITCH 12.0
END DESCRIPTION:
XS GIS Cut Line= 3
      3840685.94     10079210.57      3840883.99     10079066.86
      3841117.84     10078861.08
#Sta/Elev= 30
  4755.3  122.17    4843  122.35  4849.2  121.57  4856.5  119.55  4863.9     119
  4878.6  119.94  4884.8  119.15  4893.3  117.02  4920.3   109.2    4935  106.63
  4949.7  103.47  4955.9  103.11  4958.5  101.52  4985.3  102.36  5042.5  102.99
  5063.4  106.43    5071  109.05  5077.6  110.48  5091.9  115.63  5106.1  118.38
    5127  116.77  5148.8  119.14    5163  119.97  5191.5  120.64  5212.4  121.96
  5220.1  121.45  5240.8   122.6  5283.5  122.59  5297.7  123.38  5311.5  123.34
#Mann= 4 ,-1 , 0
  4755.3    .075       0    4935     .03       0  5063.4    .075       0
  5220.1     .12       0
Bank Sta=4935,5063.4
XS Rating Curve= 0 ,0
Exp/Cntr=0.3,0.1

Type RM Length L Ch R = 1 ,5500    ,500,500,500
BEGIN DESCRIPTION:
TRADE CTR DITCH_COLLEGE PK DITCH 11.0
END DESCRIPTION:
XS GIS Cut Line= 3
      3840989.73     10079582.12      3841142.72     10079431.35
      3841145.97     10078865.56
#Sta/Elev= 30
  4785.2  123.33  4791.7  122.25  4805.8  121.79    4820  119.81    4827   119.5
  4848.3  121.45  4869.4  121.71  4876.6  121.11  4883.6  119.99    4926  106.86
  4933.1  103.91  4940.2  102.36  5002.6  101.96  5004.3  100.71  5016.2  100.71
  5018.8  101.56  5040.3  102.82  5080.3  106.88  5099.4  109.22  5140.3  114.42
  5200.3  117.11  5240.3  117.78  5270.3  119.42  5300.1  120.07  5380.3  121.55
  5400.3  120.88  5440.3  120.92  5470.3  121.99  5540.3   122.4  5565.8  123.56
#Mann= 5 ,-1 , 0
  4785.2     .05       0    4926     .03       0  5080.3     .05       0
  5099.4    .075       0  5300.1     .12       0
Bank Sta=4926,5080.3
XS Rating Curve= 0 ,0
Exp/Cntr=0.3,0.1

Type RM Length L Ch R = 1 ,5000    ,500,500,500
BEGIN DESCRIPTION:
TRADE CTR DITCH_COLLEGE PK DITCH 10.0
END DESCRIPTION:
XS GIS Cut Line= 4
       3841141.2     10080112.95      3841361.93     10079840.55
      3841429.83     10079783.08      3841184.62     10079066.96
#Sta/Elev= 30
  4649.4  123.75    4783  119.61  4826.2  119.78  4854.9  117.73  4883.5   121.3
  4918.9  122.14  4933.2  119.97 4973.25 106.881  4989.2  102.31  4998.1  100.93
  5018.4  101.89  5039.2  106.91  5060.2  112.76  5082.1  113.44  5101.7   112.4
    5140  107.76  5176.6  106.93  5233.9  108.02  5455.1  108.95  5492.7   108.4
  5510.2  109.82  5533.1  109.28  5560.4  109.11  5587.9  109.77  5609.4  113.91
  5704.1  119.24  5767.6  121.52  5799.3  121.85  5809.8     121  5845.9  121.74
#Mann= 6 ,-1 , 0
  4649.4     .05       0 4973.25     .07       0  5039.2     .05       0
  5455.1     .12       0  5533.1    .075       0  5560.4     .12       0
Bank Sta=4973.25,5039.2
XS Rating Curve= 0 ,0
Exp/Cntr=0.3,0.1

Type RM Length L Ch R = 1 ,4500    ,459,459,459
BEGIN DESCRIPTION:
TRADE CTR DITCH_COLLEGE PK DITCH 9.0
END DESCRIPTION:
XS GIS Cut Line= 3
      3841267.81     10080311.09      3841770.61     10080046.86
      3841145.95     10078625.14
#Sta/Elev= 30
    4432  123.56  4534.1  119.55  4544.8  120.45  4699.1  113.46  4825.8  110.55
  4869.8  112.77  4891.9  111.92  4897.5  109.54  4913.9  108.98    4918 107.002
    4936  105.52  4941.6  102.91    4958  102.57  4974.1   99.24    5000   99.77
  5028.2     107  5060.9   113.2  5143.2  110.52  5181.1   107.5  5221.3  108.09
  5515.4  109.23  5759.8  108.28  5835.3   109.7    5963  108.75  6103.9   113.9
  6387.3  122.03  6457.4  120.58  6486.2  122.26  6532.3  121.92  6552.9  123.31
#Mann= 6 ,-1 , 0
    4432     .05       0    4918     .07       0  5028.2     .05       0
  5221.3      .1       0  6103.9     .12       0  6532.3    .075       0
Bank Sta=4918,5028.2
XS Rating Curve= 0 ,0
Exp/Cntr=0.3,0.1

Type RM Length L Ch R = 1 ,4041    ,541,541,541
BEGIN DESCRIPTION:
TRADE CTR DITCH_COLLEGE PK DITCH 8.0
END DESCRIPTION:
XS GIS Cut Line= 3
      3841299.61     10080336.47      3842237.12     10080143.32
      3841721.94     10077667.66
#Sta/Elev= 30
  3964.7  122.19  4269.2  112.36  4442.8  111.42  4540.4  107.92  4714.9  109.17
  4925.6   112.8  4954.8  106.61  4990.4   98.91  5002.3   98.91  5005.9  103.03
  5019.3 106.609  5046.8  112.48  5410.6  111.37  5714.3   110.3  5966.1  112.27
  6241.8  107.76  6336.6  108.74  6560.9  107.54  6650.4  107.76  6691.3  111.07
  6721.9  109.88  6803.3   113.1    6824  117.17  6929.4   117.4  6945.2  116.88
  7130.5  115.34  7203.9  117.88  7233.1  115.36  7298.9  116.23  7450.6  124.16
#Mann= 12 ,-1 , 0
  3964.7     .05       0  4540.4     .12       0  4714.9     .05       0
  4954.8     .07       0  5019.3     .05       0  5410.6      .1       0
  5714.3     .12       0  6336.6      .1       0  6560.9     .05       0
  6929.4      .1       0  6945.2    .075       0  7233.1     .05       0
Bank Sta=4954.8,5019.3
XS Rating Curve= 0 ,0
Exp/Cntr=0.3,0.1

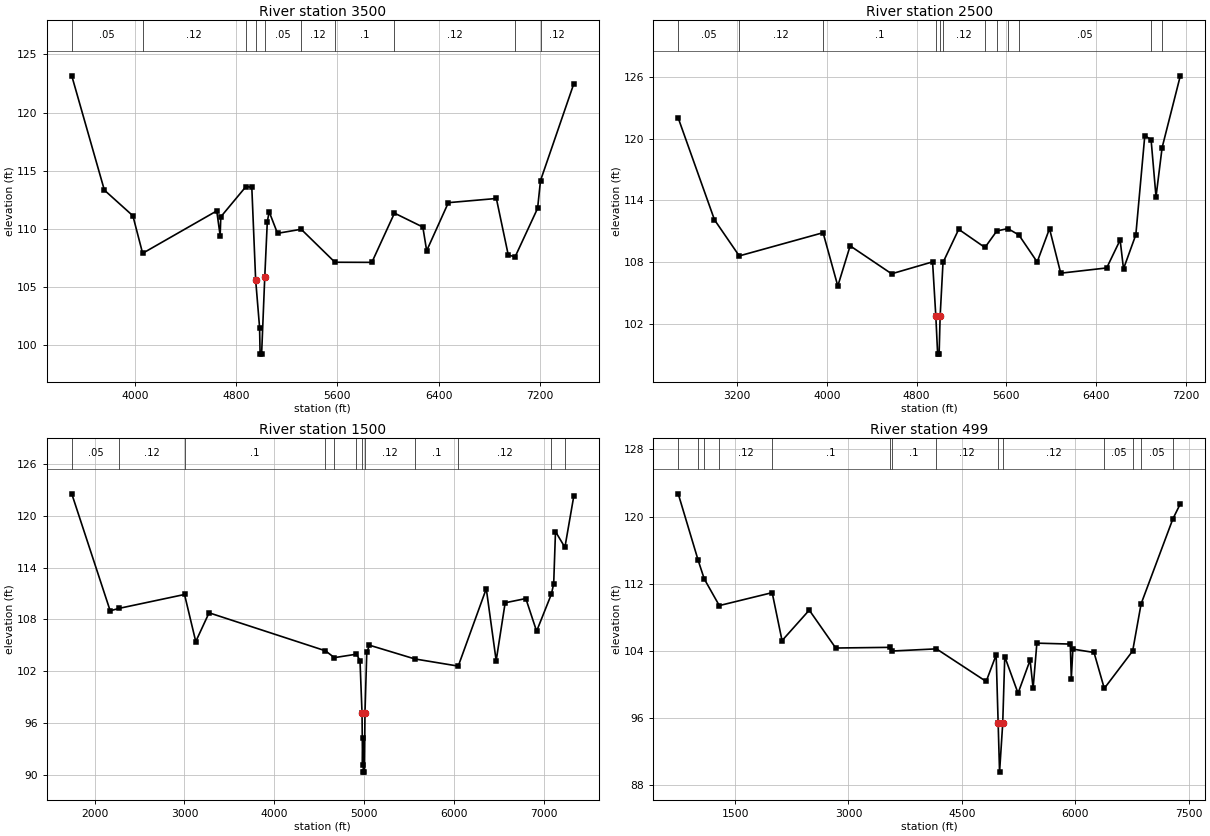
Type RM Length L Ch R = 1 ,3500    ,1000,1000,1000
BEGIN DESCRIPTION:
TRADE CTR DITCH_COLLEGE PK DITCH 7.0
END DESCRIPTION:
XS GIS Cut Line= 4
      3841322.67     10080358.59      3842728.15     10080174.37
       3842749.9     10080096.86      3842461.51     10077646.78
#Sta/Elev= 30
    3502  123.16  3759.4  113.32  3984.7  111.11  4061.5  107.88  4646.9  111.53
  4673.8   109.4  4678.9  111.02  4877.9  113.63  4923.8  113.56  4954.1   105.6
  4985.2  101.49  4989.3    99.2  5001.2    99.2    5026  105.81  5046.1  110.59
  5060.8  111.46  5126.7   109.6  5313.8  109.95  5580.3  107.11  5871.8   107.1
  6050.3  111.34  6274.5  110.14  6304.7   108.1  6475.9  112.24  6855.1   112.6
  6949.2  107.73  7003.3  107.58  7180.7  111.75  7203.7  114.14    7467  122.49
#Mann= 10 ,-1 , 0
    3502     .05       0  4061.5     .12       0  4877.9     .05       0
  4954.1     .07       0    5026     .05       0  5313.8     .12       0
  5580.3      .1       0  6050.3     .12       0  7003.3      .1       0
  7203.7     .12       0
Bank Sta=4954.1,5026
XS Rating Curve= 0 ,0
Exp/Cntr=0.3,0.1

Type RM Length L Ch R = 1 ,2500    ,1000,1000,1000
BEGIN DESCRIPTION:
TRADE CTR DITCH_COLLEGE PK DITCH 5.0
END DESCRIPTION:
XS GIS Cut Line= 4
       3841354.4      10080378.8      3843601.82     10080404.33
      3843642.21     10080336.86      3843676.42     10078184.33
#Sta/Elev= 30
  2673.8  122.02  2997.3  112.11    3218   108.6  3965.9  110.86  4097.3  105.67
  4207.4  109.58  4577.4  106.86  4942.7  108.02  4971.8  102.71    4988   99.04
  5001.2   99.04  5010.1 102.708  5035.8  107.96  5175.8  111.19    5410  109.42
    5516  111.03  5614.3  111.26  5712.6  110.64  5875.9  108.01  5985.9  111.25
  6085.9  106.92    6496  107.43    6616  110.15    6646  107.34    6756  110.66
    6836  120.31  6892.1  119.91    6936  114.35  6990.4  119.14  7152.8  126.13
#Mann= 12 ,-1 , 0
  2673.8     .05       0    3218     .12       0  3965.9      .1       0
  4971.8     .07       0  5010.1      .1       0  5035.8     .12       0
    5410      .1       0    5516     .12       0  5614.3      .1       0
  5712.6     .05       0  6892.1    .075       0  6990.4     .05       0
Bank Sta=4971.8,5010.1
XS Rating Curve= 0 ,0
Exp/Cntr=0.3,0.1

Type RM Length L Ch R = 1 ,1500    ,1001,1001,1001
BEGIN DESCRIPTION:
TRADE CTR DITCH_COLLEGE PK DITCH 3.0
END DESCRIPTION:
XS GIS Cut Line= 4
      3841380.47     10080404.84      3844535.97     10080476.43
      3844581.25     10080389.88      3844596.58     10078056.73
#Sta/Elev= 30
    1746  122.54  2173.5     109  2270.9  109.28  3000.7  110.89  3125.8  105.44
  3273.8  108.77  4569.5  104.37    4668  103.58  4913.9  103.98  4953.5  103.23
  4976.1   97.16  4981.8   91.18  4987.4   94.25  4989.8   90.33  5003.2   90.33
  5008.8   97.17  5028.8  104.18  5058.8  105.02  5563.6  103.43  6046.9   102.6
  6358.8  111.56  6468.8  103.23  6568.8  109.93  6798.8  110.42  6918.8  106.64
  7083.6  110.94  7108.9  112.14  7128.9  118.17  7233.7  116.35  7333.2  122.31
#Mann= 12 ,-1 , 0
    1746     .05       0  2270.9     .12       0  3000.7      .1       0
  4569.5     .12       0    4668      .1       0  4913.9     .12       0
  4976.1     .07       0  5008.8     .12       0  5563.6      .1       0
  6046.9     .12       0  7083.6     .05       0  7233.7    .075       0
Bank Sta=4976.1,5008.8
XS Rating Curve= 0 ,0
Exp/Cntr=0.3,0.1

Type RM Length L Ch R = 1 ,499     ,0,0,0
BEGIN DESCRIPTION:
TRADE CTR DITCH_COLLEGE PK DITCH 1.0
END DESCRIPTION:
XS GIS Cut Line= 3
      3841374.67     10080460.68       3845506.6     10080571.79
      3846163.13       10078149.
#Sta/Elev= 30
   747.5   122.7  1011.4  114.78  1091.4  112.58  1290.7   109.4  1990.5  110.94
  2121.2  105.23  2481.3  108.86  2831.4  104.35  3550.8  104.43  3572.7  103.99
  4164.3  104.25  4822.2  100.37  4954.2  103.53  4980.7   95.41  4999.3   89.58
 5041.18  95.378  5068.2  103.32    5244   98.97  5403.4  102.91  5443.2   99.55
    5493  104.93  5935.2  104.82  5948.8  100.72  5969.5  104.22  6249.3  103.82
  6385.1   99.54  6760.6     104  6872.1   109.6  7292.8  119.72  7391.1  121.51
#Mann= 14 ,-1 , 0
   747.5     .05       0  1011.4     .12       0  1091.4     .05       0
  1290.7     .12       0  1990.5      .1       0  3550.8     .12       0
  3572.7      .1       0  4164.3     .12       0  4980.7     .07       0
 5041.18     .12       0  6385.1     .05       0  6760.6     .12       0
  6872.1     .05       0  7292.8      .1       0
Bank Sta=4980.7,5041.18
XS Rating Curve= 0 ,0
Exp/Cntr=0.3,0.1