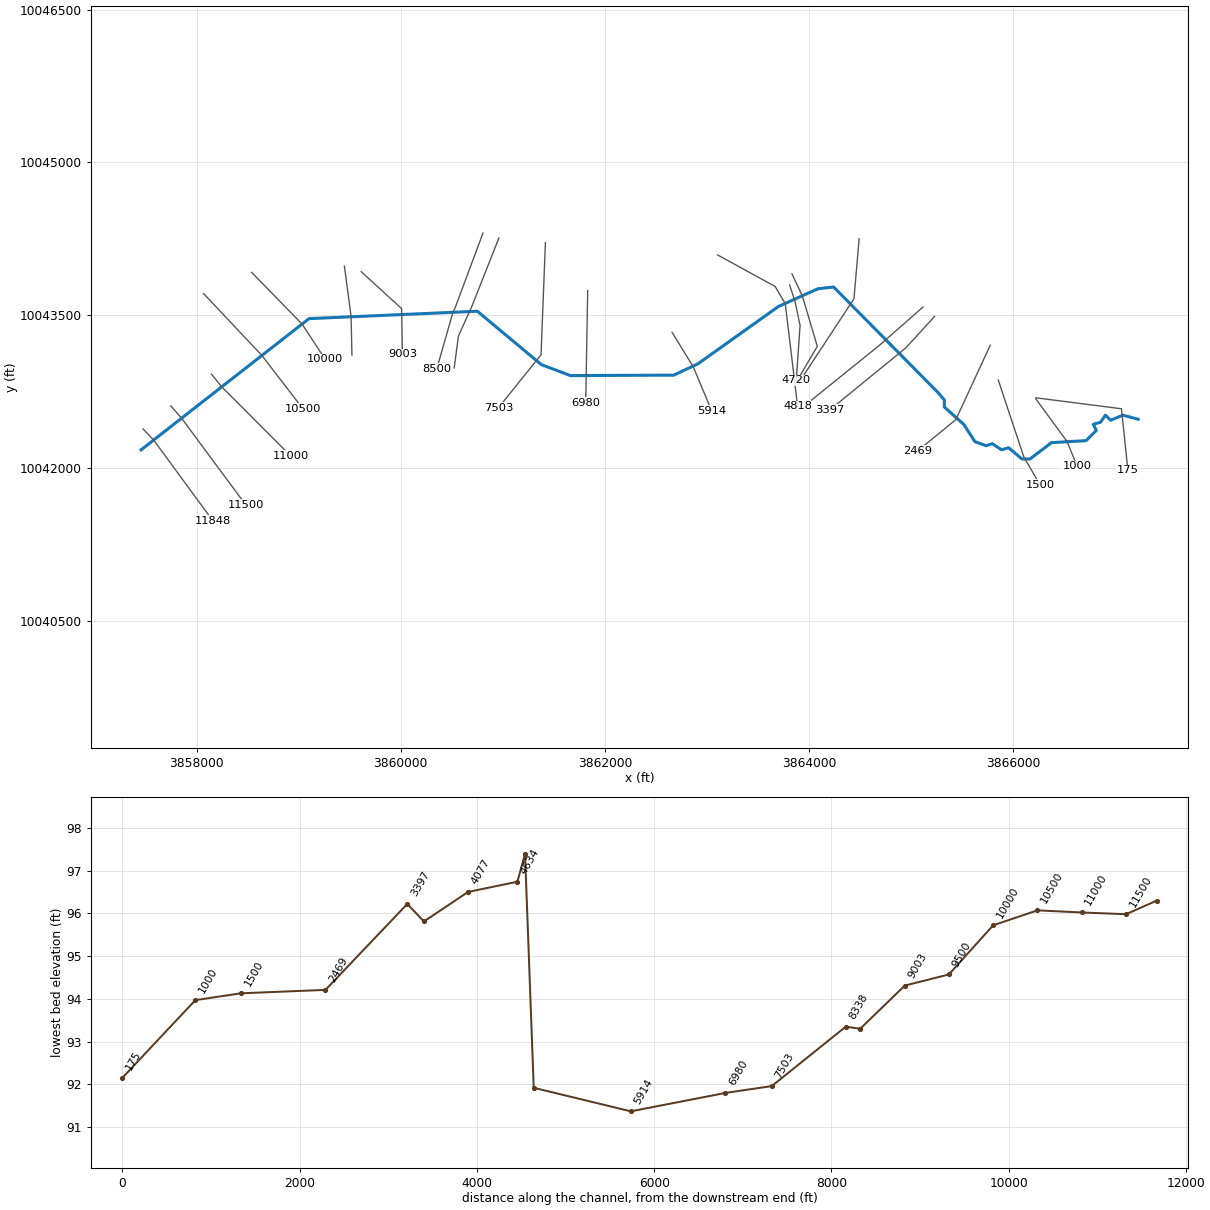
--- UNNAMED TRIB TO WOODSONS GULLY.prj (project) ---

Proj Title=UNNAMED TRIB TO WOODSONS GULLY Base Level Engineering
Current Plan=p01
Default Exp/Contr=0.3,0.1
English Units
Geom File=g01
Flow File=f01
Plan File=p01
Y Axis Title=Elevation
X Axis Title(PF)=Main Channel Distance
X Axis Title(XS)=Station
BEGIN DESCRIPTION:
UNNAMED TRIB TO WOODSONS GULLY
END DESCRIPTION:
DSS Export Rating Curves= 0
DSS Export Rating Curve Sorted= 0
DSS Export Volume Flow Curves= 0
DXF OffsetX= 0
DXF OffsetY= 0
DXF ScaleX= 1
DXF ScaleY= 10

--- UNNAMED TRIB TO WOODSONS GULLY.p01 (plan) ---

Plan Title=Multiple Run
Short Identifier=Multiple
Geom File=g01
Flow File=f01
Subcritical Flow
K Sum by GR= 0
Std Step Tol= 0.01
Critical Tol= 0.01
Num of Std Step Trials= 20
Max Error Tol= 0.3
Flow Tol Ratio= 0.001
Split Flow NTrial= 30
Split Flow Tol= 0.02
Split Flow Ratio= 0.02
Log Output Level= 0
Friction Slope Method= 1
Unsteady Friction Slope Method= 2
Unsteady Bridges Friction Slope Method= 1
Parabolic Critical Depth
Global Vel Dist=  1 , 1 , 1
Global Log Level= 0
CheckData=True
Encroach Param= -1, 0, 0, 0
BEGIN DESCRIPTION:
Multiple Run
END DESCRIPTION:

--- UNNAMED TRIB TO WOODSONS GULLY.f01 (steady flow) ---

Flow Title=Multiple
Program Version=4.10
Number of Profiles= 7
Profile Names=10-year,25-year,50-year,1pct_min,100-year,1pct_plu,500-year
River Rch & RM=UNNAMED TRIB TO,Reach-1         ,11848
     631     835    1112     487    1470    4439    2654
River Rch & RM=UNNAMED TRIB TO,Reach-1         ,8500
     881    1190    1605     712    2149    6490    3977
Boundary for River Rch & Prof#=UNNAMED TRIB TO,Reach-1         , 1
Up Type= 0
Dn Type= 3
Dn Slope=0.005
Boundary for River Rch & Prof#=UNNAMED TRIB TO,Reach-1         , 2
Up Type= 0
Dn Type= 3
Dn Slope=0.005
Boundary for River Rch & Prof#=UNNAMED TRIB TO,Reach-1         , 3
Up Type= 0
Dn Type= 3
Dn Slope=0.005
Boundary for River Rch & Prof#=UNNAMED TRIB TO,Reach-1         , 4
Up Type= 0
Dn Type= 3
Dn Slope=0.005
Boundary for River Rch & Prof#=UNNAMED TRIB TO,Reach-1         , 5
Up Type= 0
Dn Type= 3
Dn Slope=0.005
Boundary for River Rch & Prof#=UNNAMED TRIB TO,Reach-1         , 6
Up Type= 0
Dn Type= 3
Dn Slope=0.005
Boundary for River Rch & Prof#=UNNAMED TRIB TO,Reach-1         , 7
Up Type= 0
Dn Type= 3
Dn Slope=0.005
DSS Import GetInterval= 0
DSS Import GetPeak= 0
DSS Import FillOption= 0

--- UNNAMED TRIB TO WOODSONS GULLY.g01 (geometry) ---

Geom Title=Existing Conditions
Program Version=4.10

River Reach=UNNAMED TRIB TO ,Reach-1
Reach XY= 30
       3857453.7     10042175.92      3859100.57     10043464.95
      3860750.68     10043537.45      3861377.15     10043013.33
      3861663.87     10042905.32      3862677.59     10042910.35
      3862913.09     10043021.46      3863703.12     10043584.78
       3864089.9     10043758.41      3864242.88     10043775.64
      3865268.24     10042736.86      3865328.24     10042666.86
      3865328.24     10042596.86      3865518.24     10042426.86
      3865628.24     10042256.86      3865738.24     10042216.86
      3865798.24     10042236.86      3865888.24     10042176.86
      3865958.24     10042196.86      3866088.24     10042086.86
      3866168.24     10042086.86      3866378.24     10042246.86
      3866718.24     10042266.86      3866818.24     10042366.86
      3866788.24     10042426.86      3866858.24     10042446.86
      3866908.24     10042516.86      3866958.24     10042466.86
      3867078.24     10042516.86      3867228.24     10042476.86

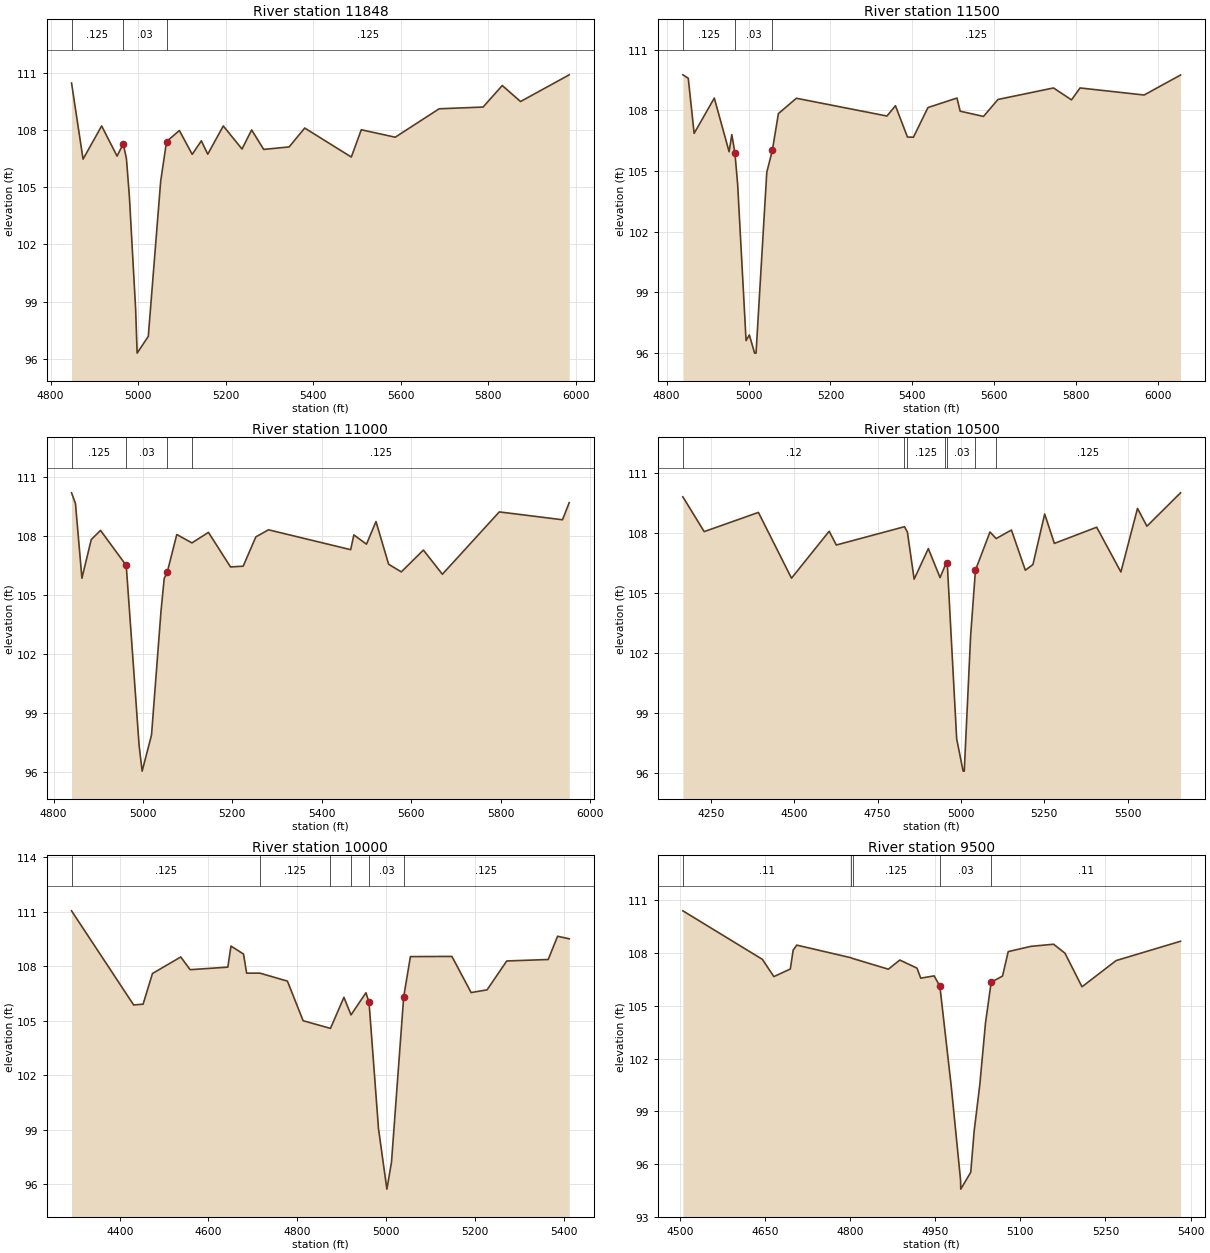
Type RM Length L Ch R = 1 ,11848   ,348,348,348
BEGIN DESCRIPTION:
UNNAMED TRIB TO WOODSONS GULLY 24.0
END DESCRIPTION:
XS GIS Cut Line= 3
      3857472.58     10042382.87      3857580.05     10042269.33
      3858159.41      10041477.6
#Sta/Elev= 30
    4848  110.46  4874.3  106.47  4916.8  108.21    4952  106.63  4966.1  107.27
  4973.4  106.51  4980.3  104.47  4994.5   98.59  4997.9    96.3  5023.4   97.18
  5051.7  105.31  5065.1  107.39  5094.4  107.97  5123.8  106.72  5144.6  107.43
  5159.3  106.73  5194.8  108.21  5237.6     107  5259.6     108  5287.2  106.98
  5345.3  107.11  5380.9   108.1  5487.4  106.58  5510.2  108.01  5587.8  107.62
  5688.2  109.11  5788.5   109.2  5832.4  110.33  5874.2  109.49  5985.4  110.89
#Mann= 3 , 0 , 0
    4848    .125       0  4966.1     .03       0  5065.1    .125       0
Bank Sta=4966.1,5065.1
XS Rating Curve= 0 ,0
Exp/Cntr=0.3,0.1

Type RM Length L Ch R = 1 ,11500   ,500,500,500
BEGIN DESCRIPTION:
UNNAMED TRIB TO WOODSONS GULLY 23.0
END DESCRIPTION:
XS GIS Cut Line= 3
        3857746.     10042608.14      3857851.07     10042486.94
      3858478.46     10041638.14
#Sta/Elev= 30
  4839.6  109.76  4852.8  109.59  4867.1  106.86  4916.4  108.61  4952.6  105.95
  4959.2   106.8  4966.8  105.88  4973.4  104.35    4994    96.6    5002   96.88
  5014.9   95.98  5018.4   95.98  5044.6  104.93  5058.4  106.04    5073  107.84
  5116.9   108.6  5338.2  107.72    5359  108.23  5388.3  106.68  5402.9  106.67
  5438.4  108.14  5509.3  108.61  5517.1  107.96  5574.1   107.7  5609.5  108.54
  5745.2  109.11  5789.1  108.52    5810  109.11  5966.5  108.76  6055.5  109.75
#Mann= 3 , 0 , 0
  4839.6    .125       0  4966.8     .03       0  5058.4    .125       0
Bank Sta=4966.8,5058.4
XS Rating Curve= 0 ,0
Exp/Cntr=0.3,0.1

Type RM Length L Ch R = 1 ,11000   ,500,500,500
BEGIN DESCRIPTION:
UNNAMED TRIB TO WOODSONS GULLY 22.0
END DESCRIPTION:
XS GIS Cut Line= 3
      3858144.44     10042919.35       3858244.8     10042795.12
      3858917.91     10042119.92
#Sta/Elev= 30
  4840.3  110.17  4849.1  109.62  4863.5  105.83  4884.3  107.79  4905.1  108.26
  4962.6  106.48  4991.4   97.33  4998.2   96.02  5019.2   97.86  5040.4  104.16
  5047.5  105.81  5054.5  106.15  5075.7  108.05  5109.6107.6239  5146.5  108.16
  5195.9   106.4  5224.2  106.44  5252.5  107.93  5280.8  108.29  5464.6  107.28
  5471.7  108.03    5500  107.56  5521.2  108.71  5549.5  106.54  5577.8  106.15
  5627.3  107.26  5669.7  106.03    5797   109.2  5938.4   108.8  5953.4  109.67
#Mann= 4 ,-1 , 0
  4840.3    .125       0  4962.6     .03       0  5054.5     .11       0
  5109.6    .125       0
Bank Sta=4962.6,5054.5
XS Rating Curve= 0 ,0
Exp/Cntr=0.3,0.1

Type RM Length L Ch R = 1 ,10500   ,500,500,500
BEGIN DESCRIPTION:
UNNAMED TRIB TO WOODSONS GULLY 21.0
END DESCRIPTION:
XS GIS Cut Line= 3
      3858067.23     10043710.62      3858638.53      10043103.3
      3859039.39     10042581.12
#Sta/Elev= 30
  4166.2  109.79  4230.1  108.05  4392.7  109.01  4491.9  105.72  4604.9  108.07
  4626.2  107.38  4830.6108.2952  4839.4108.0309  4859.6  105.67  4902.1   107.2
  4937.3  105.75  4951.9106.3299  4958.8   106.5  4987.1   97.69  5006.4   96.07
  5009.9   96.07  5028.9  102.82  5043.4  106.12    5087  108.03  5105.6107.7032
  5151.3  108.13    5193  106.12  5215.7   106.4    5251  108.93  5280.1  107.46
  5406.9  108.27  5479.5  106.03  5529.3  109.21  5557.5  108.32  5658.3  109.99
#Mann= 7 ,-1 , 0
  4166.2     .12       0  4830.6     .15       0  4839.4    .125       0
  4951.9     .11       0  4958.8     .03       0  5043.4     .11       0
  5105.6    .125       0
Bank Sta=4958.8,5043.4
XS Rating Curve= 0 ,0
Exp/Cntr=0.3,0.1

Type RM Length L Ch R = 1 ,10000   ,500,500,500
BEGIN DESCRIPTION:
UNNAMED TRIB TO WOODSONS GULLY 20.0
END DESCRIPTION:
XS GIS Cut Line= 3
      3858538.09     10043919.19      3859032.26     10043411.48
      3859258.62     10043066.28
#Sta/Elev= 30
  4291.5  111.04  4431.4  105.86  4452.7   105.9  4473.8  107.59  4537.6   108.5
  4558.7   107.8  4643.6  107.94  4650.7   109.1    4679  108.66    4686  107.61
  4716.2107.6084  4777.9  107.17  4813.3  104.99  4874.9104.5686  4905.2  106.28
  4921.2105.3107  4954.8  106.53  4961.8     106  4983.1   99.05    5002   95.72
  5012.4   97.21  5039.9  106.31    5055  108.52  5148.5  108.53  5191.8  106.54
  5227.7  106.69  5272.1  108.28  5365.5  108.36  5386.6  109.64  5412.8   109.5
#Mann= 6 ,-1 , 0
  4291.5    .125       0  4716.2    .125       0  4874.9     .11       0
  4921.2    .125       0  4961.8     .03       0  5039.9    .125       0
Bank Sta=4961.8,5039.9
XS Rating Curve= 0 ,0
Exp/Cntr=0.3,0.1

Type RM Length L Ch R = 1 ,9500    ,497,497,497
BEGIN DESCRIPTION:
UNNAMED TRIB TO WOODSONS GULLY 19.0
END DESCRIPTION:
XS GIS Cut Line= 3
       3859447.4     10043979.95      3859512.59     10043489.76
      3859521.19     10043107.56
#Sta/Elev= 30
  4505.5   110.4  4645.6  107.64  4665.8  106.66  4694.8  107.09  4699.8  108.16
  4706.1  108.45  4801.1107.7359  4804.4107.6935  4867.5  107.08  4887.7   107.6
    4918  107.14  4924.6  106.57  4948.2   106.7  4958.3  106.11  4978.5  100.37
  4994.8   95.07  4995.1   94.57  5012.7   95.53  5018.7   97.87  5028.7  100.52
  5038.7  104.03  5048.7  106.34  5068.7  106.69  5078.7  108.08  5118.7  108.38
  5158.7   108.5  5178.7  107.99  5208.7  106.08  5268.8  107.57  5382.3  108.67
#Mann= 5 ,-1 , 0
  4505.5     .11       0  4801.1     .11       0  4804.4    .125       0
  4958.3     .03       0  5048.7     .11       0
Bank Sta=4958.3,5048.7
XS Rating Curve= 0 ,0
Exp/Cntr=0.3,0.1

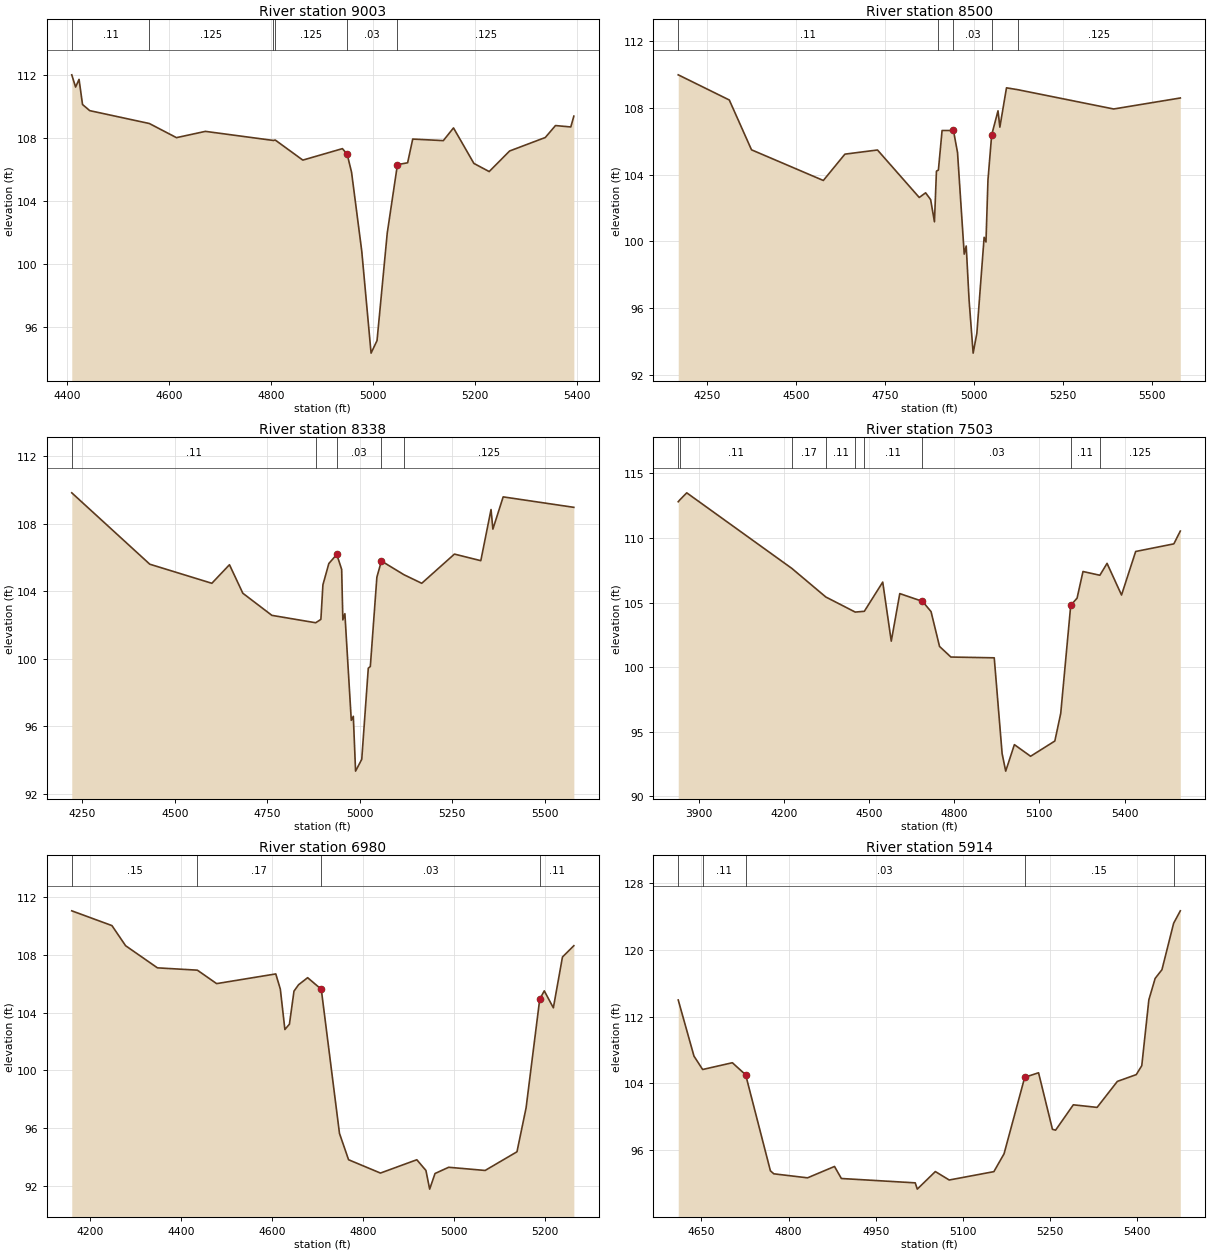
Type RM Length L Ch R = 1 ,9003    ,503,503,503
BEGIN DESCRIPTION:
UNNAMED TRIB TO WOODSONS GULLY 18.0
END DESCRIPTION:
XS GIS Cut Line= 3
       3859612.3      10043925.7      3860008.15     10043563.28
      3860015.96     10043115.05
#Sta/Elev= 30
  4408.9  112.03  4416.4  111.25  4423.2  111.74    4430  110.14  4444.1  109.75
  4561.1  108.93  4614.3  108.03  4671.1  108.43  4804.6  107.85    4808  107.88
  4862.2   106.6  4939.9  107.33  4949.2  106.97  4957.8  105.83  4977.8  100.81
  4996.1   94.31  5007.8   95.11  5027.8  101.95  5047.8  106.31  5067.8  106.43
  5077.8  107.94  5137.8  107.84  5157.8  108.65  5197.8  106.39  5227.8  105.87
  5267.9  107.18  5337.9  108.04  5357.9   108.8  5387.9  108.71  5393.9   109.4
#Mann= 6 ,-1 , 0
  4408.9     .11       0  4561.1    .125       0  4804.6     .11       0
    4808    .125       0  4949.2     .03       0  5047.8    .125       0
Bank Sta=4949.2,5047.8
XS Rating Curve= 0 ,0
Exp/Cntr=0.3,0.1

Type RM Length L Ch R = 1 ,8500    ,162,162,162
BEGIN DESCRIPTION:
UNNAMED TRIB TO WOODSONS GULLY 17.0
END DESCRIPTION:
XS GIS Cut Line= 4
      3860805.92     10044305.47      3860531.66     10043568.77
      3860511.85     10043528.25       3860352.6     10042971.68
#Sta/Elev= 30
  4168.8     110  4312.2  108.49  4374.6   105.5  4576.3  103.66  4636.9  105.24
  4728.4  105.49  4845.7  102.64  4863.6  102.92  4877.7  102.51  4888.4  101.18
    4894  104.22  4899.5104.2861  4909.8  106.66  4941.8  106.66  4953.2  105.34
    4972   99.24  4977.6   99.73  4985.7   96.47  4997.1    93.3  5007.5   94.49
  5027.9  100.25  5033.1   99.97  5038.7  103.69  5049.1  106.39  5066.9  107.84
  5072.1  106.86  5090.7  109.22  5123.4109.1044  5391.7  107.95  5578.9  108.61
#Mann= 5 ,-1 , 0
  4168.8     .11       0  4899.5     .11       0  4941.8     .03       0
  5049.1     .11       0  5123.4    .125       0
Bank Sta=4941.8,5049.1
XS Rating Curve= 0 ,0
Exp/Cntr=0.3,0.1

Type RM Length L Ch R = 1 ,8338    ,835,835,835
BEGIN DESCRIPTION:
UNNAMED TRIB TO WOODSONS GULLY 16.0
END DESCRIPTION:
XS GIS Cut Line= 5
      3860962.15     10044257.69       3860694.3     10043578.86
      3860676.07     10043540.32      3860565.02     10043293.03
      3860523.79     10042981.62
#Sta/Elev= 30
  4221.2  109.84  4432.2  105.61    4600  104.48  4647.6  105.58  4683.8  103.89
  4762.3  102.58  4880.7102.1415  4894.8  102.34  4900.3  104.39  4916.3  105.65
  4937.8  106.19    4951   105.3  4954.2  102.31  4959.7  102.68    4977   96.36
  4982.5    96.6  4988.6   93.35  5005.3   94.05    5023   99.45  5028.5   99.55
  5046.2  104.84  5058.5   105.8  5119.2  104.99  5167.5  104.48  5255.9  106.21
  5327.2  105.82  5354.9  108.85  5359.9  107.69  5387.7   109.6  5578.8  108.98
#Mann= 5 ,-1 , 0
  4221.2     .11       0  4880.7     .11       0  4937.8     .03       0
  5058.5     .11       0  5119.2    .125       0
Bank Sta=4937.8,5058.5
XS Rating Curve= 0 ,0
Exp/Cntr=0.3,0.1

Type RM Length L Ch R = 1 ,7503    ,523,523,523
BEGIN DESCRIPTION:
UNNAMED TRIB TO WOODSONS GULLY 15.0
END DESCRIPTION:
XS GIS Cut Line= 3
      3861417.85     10044211.07      3861374.86     10043110.02
      3860957.59      10042589.5
#Sta/Elev= 30
  3827.4  112.81  3833.3  112.96  3857.4   113.5  4227.7  107.65  4347.2  105.44
    4451  104.27  4483.1  104.33  4547.9  106.59    4578  102.02    4608   105.7
    4688   105.1  4718.1  104.31  4748.1  101.61  4788.1  100.79  4940.8  100.73
  4968.6   93.31  4981.2   91.96  5011.8   94.01  5068.9   93.11  5154.3   94.29
  5175.1   96.43  5210.3  104.79  5232.7  105.35  5253.5  107.41    5313  107.12
  5338.3  108.04  5389.3  105.59  5439.1  108.96  5573.6  109.55  5596.4  110.54
#Mann= 9 ,-1 , 0
  3827.4     .17       0  3833.3     .11       0  4227.7     .17       0
  4347.2     .11       0    4451     .15       0  4483.1     .11       0
    4688     .03       0  5210.3     .11       0    5313    .125       0
Bank Sta=4688,5210.3
XS Rating Curve= 0 ,0
Exp/Cntr=0.3,0.1

Type RM Length L Ch R = 1 ,6980    ,1066,1066,1066
BEGIN DESCRIPTION:
UNNAMED TRIB TO WOODSONS GULLY 14.0
END DESCRIPTION:
XS GIS Cut Line= 2
      3861832.23     10043739.38       3861812.7     10042636.05
#Sta/Elev= 30
  4159.1  111.03  4247.4  110.01  4277.4  108.62  4347.4  107.09  4435.1  106.93
  4477.5     106  4607.5  106.67  4617.5  105.62  4627.5  102.83  4637.5   103.2
  4647.5  105.48  4657.5  105.92  4677.5  106.41  4707.5  105.61  4747.5   95.65
  4767.5   93.83  4837.5   92.91  4917.5   93.83  4937.5   93.09  4945.7    91.8
  4957.5   92.88  4987.5   93.31  5067.6   93.09  5137.6   94.38  5157.6   97.41
  5187.6  104.92  5197.6   105.5  5217.6  104.33  5237.6  107.84  5262.6  108.62
#Mann= 4 ,-1 , 0
  4159.1     .15       0  4435.1     .17       0  4707.5     .03       0
  5187.6     .11       0
Bank Sta=4707.5,5187.6
XS Rating Curve= 0 ,0
Exp/Cntr=0.3,0.1

Type RM Length L Ch R = 1 ,5914    ,1096,1096,1096
BEGIN DESCRIPTION:
UNNAMED TRIB TO WOODSONS GULLY 11.0
END DESCRIPTION:
XS GIS Cut Line= 3
      3862659.49     10043330.51      3862867.82     10042990.23
      3863046.78     10042561.14
#Sta/Elev= 30
    4610  113.98  4637.1  107.27    4652  105.67  4703.1  106.48    4726  105.04
  4768.6   93.56  4774.5    93.2  4832.5   92.72  4878.9   94.08  4890.7   92.64
  5017.8   92.12  5021.3   91.37  5052.4   93.47  5076.3   92.46  5153.1   93.46
  5170.6   95.59  5206.2  104.74    5230  105.28  5253.9   98.52  5259.3   98.42
  5289.8  101.45  5330.7  101.14  5365.6  104.25  5398.1  105.06  5407.6  106.13
  5419.8  114.01  5430.6  116.56  5442.3   117.6  5462.4  123.15  5473.9  124.64
#Mann= 5 ,-1 , 0
    4610     .17       0    4652     .11       0    4726     .03       0
  5206.2     .15       0  5462.4     .11       0
#Block Obstruct= 2 , 0
                         5216.44          105.49
Bank Sta=4726,5206.2
XS Rating Curve= 0 ,0
Exp/Cntr=0.3,0.1

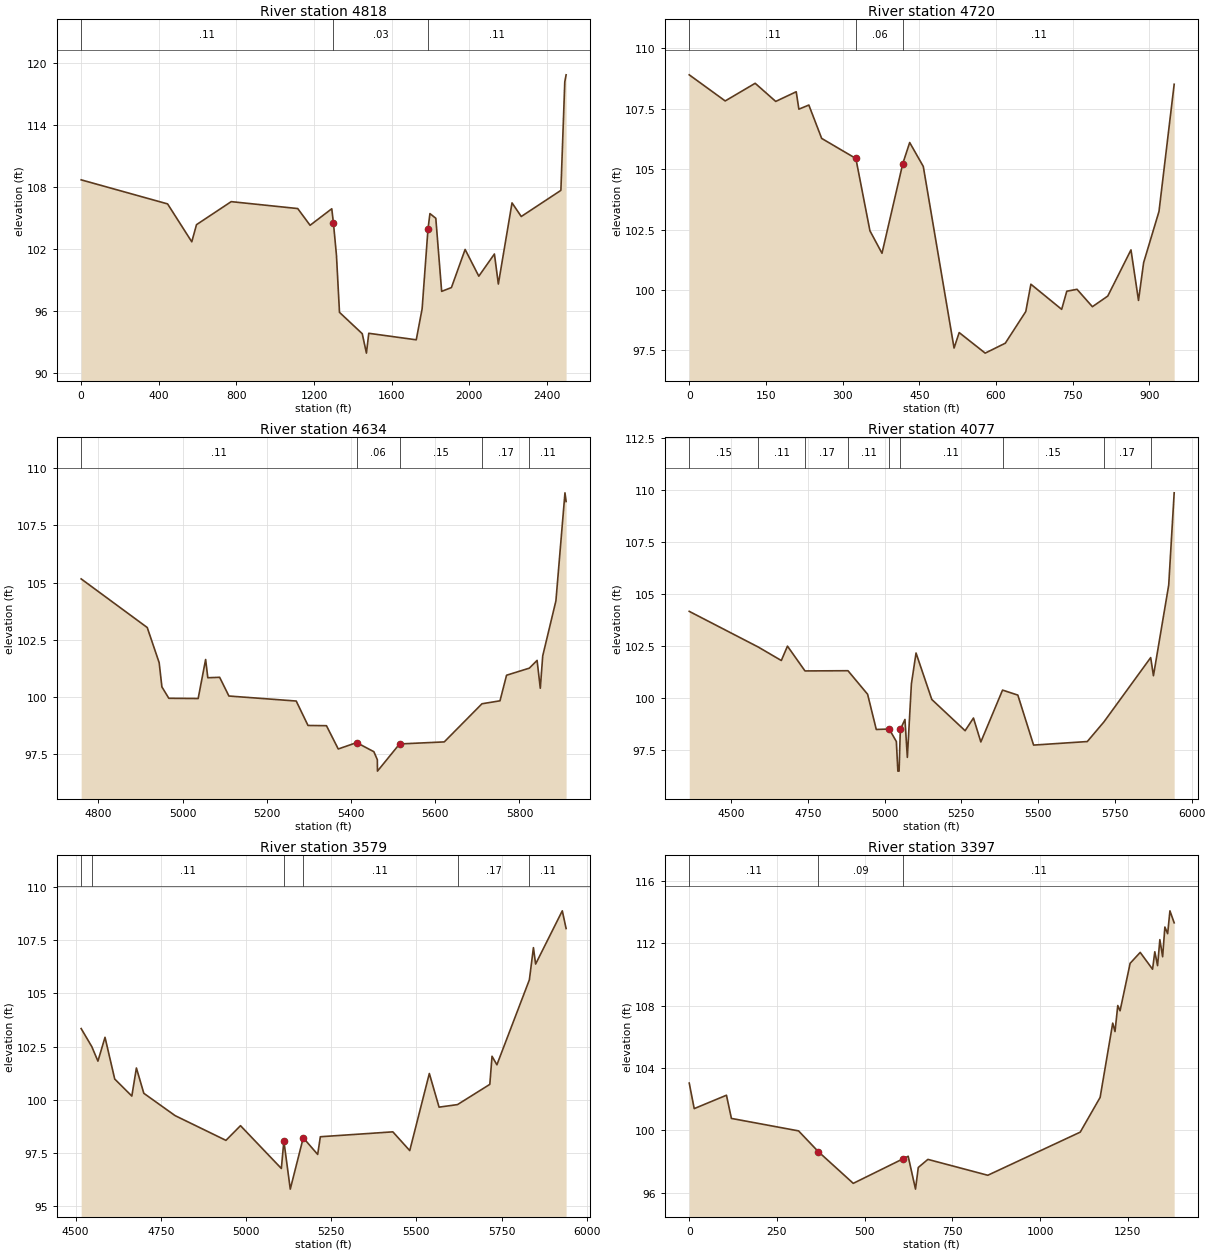
Type RM Length L Ch R = 1 ,4818    ,98,98,98
BEGIN DESCRIPTION:
UNNAMED TRIB TO WOODSONS GULLY 10.0
END DESCRIPTION:
XS GIS Cut Line= 4
      3863106.06      10044090.3      3863670.28     10043780.42
      3863769.23     10043611.17      3863890.13     10042604.37
#Sta/Elev= 30
       0   108.7   445.4  106.37     570   102.7   594.4  104.36   773.2  106.59
    1116  105.92  1179.7   104.3  1291.4   105.9  1299.8  104.56  1315.5  101.41
  1331.2   95.87  1448.5    93.8    1470   91.92  1482.1   93.84  1726.8   93.21
    1757   96.21  1787.2  103.93  1797.3  105.43  1827.5  104.98  1857.7    97.9
  1908.1   98.27  1978.6  101.96  2049.1   99.37  2129.6  101.52  2149.8   98.61
  2220.3  106.47  2267.9  105.15  2472.1  107.68  2492.2  118.19    2499  118.87
#Mann= 3 , 0 , 0
       0     .11       0  1299.8     .03       0  1787.2     .11       0
#Block Obstruct= 2 , 0
                         1824.41          105.46
Bank Sta=1299.8,1787.2
XS Rating Curve= 0 ,0
Exp/Cntr=0.3,0.1

Type RM Length L Ch R = 1 ,4720    ,86,86,86
BEGIN DESCRIPTION:
UNNAMED TRIB TO WOODSONS GULLY 9.0
END DESCRIPTION:
XS GIS Cut Line= 4
      3863811.78      10043795.3      3863864.71     10043632.87
      3863914.19     10043398.49      3863877.04     10042861.44
#Sta/Elev= 30
       0   108.9    70.4  107.82     129  108.55   169.2   107.8   209.3   108.2
   214.5  107.48     234  107.65   259.1  106.27     326  105.44   353.5  102.45
   377.1  101.52   417.8  105.23   431.3   106.1   457.9  105.11   518.1    97.6
   528.1   98.24     579   97.39   618.3    97.8   658.4   99.11   668.4  100.24
   728.6    99.2   738.6   99.95   758.6  100.03   788.7   99.31   818.8   99.75
   864.2  101.66   878.9   99.57   888.9  101.13     919  103.25   948.7  108.51
#Mann= 3 , 0 , 0
       0     .11       0     326     .06       0   417.8     .11       0
#Block Obstruct= 2 , 0
                          470.73          103.46
Bank Sta=326,417.8
XS Rating Curve= 0 ,0
Exp/Cntr=0.3,0.1

Type RM Length L Ch R = 1 ,4634    ,557,557,557
BEGIN DESCRIPTION:
UNNAMED TRIB TO WOODSONS GULLY 8.0
END DESCRIPTION:
XS GIS Cut Line= 4
      3863834.82     10043904.73      3863936.68     10043686.76
      3864083.04     10043192.59      3863882.67      10042851.7
#Sta/Elev= 30
  4759.4  105.16  4916.3  103.03  4944.6  101.49  4951.1  100.43  4967.5   99.93
  5037.2   99.92  5054.9  101.63  5060.1  100.83  5088.2  100.85  5110.2  100.03
    5270   99.81    5298   98.74  5341.8   98.73  5369.8   97.71  5413.5   97.99
  5454.4   97.59  5462.6   97.24  5462.9   96.74  5515.4   97.93  5621.5   98.02
    5711   99.69  5753.8   99.82  5769.4  100.94  5823.4  101.25  5841.9  101.59
  5849.5  100.37  5855.3  101.79  5886.6   104.2  5908.1  108.93  5910.8  108.55
#Mann= 5 ,-1 , 0
  4759.4     .11       0  5413.5     .06       0  5515.4     .15       0
    5711     .17       0  5823.4     .11       0
Bank Sta=5413.5,5515.4
XS Rating Curve= 0 ,0
Exp/Cntr=0.3,0.1

Type RM Length L Ch R = 1 ,4077    ,498,498,498
BEGIN DESCRIPTION:
UNNAMED TRIB TO WOODSONS GULLY 7.0
END DESCRIPTION:
XS GIS Cut Line= 3
      3864493.19     10044249.84      3864442.42     10043660.04
      3863900.87     10042834.61
#Sta/Elev= 30
  4363.9  104.17  4588.3  102.46  4663.8  101.81  4683.8   102.5  4740.9  101.31
  4880.8  101.32  4944.8  100.19    4973    98.5  5015.1   98.52  5038.4   97.92
  5043.3    96.5  5047.3    96.5  5051.3    98.5  5066.4   98.98  5074.2   97.16
  5087.4  100.69  5102.5  102.17  5153.8   99.94  5262.3   98.44  5289.5   99.05
  5313.5    97.9  5384.2  100.39    5434  100.15  5485.3   97.75  5660.2   97.92
  5714.7   98.87  5866.6  101.95  5875.6  101.08  5925.3  105.43  5943.1  109.86
#Mann= 9 ,-1 , 0
  4363.9     .15       0  4588.3     .11       0  4740.9     .17       0
  4880.8     .11       0  5015.1     .09       0  5051.3     .11       0
  5384.2     .15       0  5714.7     .17       0  5866.6     .11       0
Bank Sta=5015.1,5051.3
XS Rating Curve= 0 ,0
Exp/Cntr=0.3,0.1

Type RM Length L Ch R = 1 ,3579    ,187,187,187
BEGIN DESCRIPTION:
UNNAMED TRIB TO WOODSONS GULLY 6.0
END DESCRIPTION:
XS GIS Cut Line= 3
      3865119.52     10043578.74      3864690.56     10043201.67
      3864027.92     10042666.01
#Sta/Elev= 30
  4516.1  103.35  4547.4   102.5  4565.3  101.82  4586.1  102.94  4614.6  100.98
  4664.8  100.18  4678.2   101.5    4700  100.31    4792   99.26    4941    98.1
  4983.7   98.79  5103.6   96.78    5111   98.07  5129.8   95.81  5167.9   98.22
  5210.2   97.44  5218.1   98.27  5430.8    98.5  5480.4   97.62  5537.9  101.24
  5566.5   99.66  5620.6   99.78  5715.4  100.73  5721.9  102.05  5736.2  101.65
  5831.5  105.64  5843.4  107.15  5849.8  106.38  5928.1  108.88  5939.3  108.05
#Mann= 6 ,-1 , 0
  4516.1     .17       0  4547.4     .11       0    5111     .09       0
  5167.9     .11       0  5620.6     .17       0  5831.5     .11       0
Bank Sta=5111,5167.9
XS Rating Curve= 0 ,0
Exp/Cntr=0.3,0.1

Type RM Length L Ch R = 1 ,3397    ,923,923,923
XS GIS Cut Line= 3
      3865232.45     10043486.48      3864951.28     10043178.06
      3864204.53     10042567.58
#Sta/Elev= 30
       0  103.03    14.2  101.39   106.1  102.25   120.2  100.76   311.5   99.96
   368.2   98.62   467.4   96.59   609.6   98.17   623.9   98.33   644.8   96.22
   652.7   97.61   680.1   98.13   850.8   97.11  1114.2   99.88  1170.9  102.11
  1206.8  106.88  1213.3  106.34  1221.2  108.01  1227.7  107.67  1256.4  110.72
  1285.1  111.42  1320.3  110.34  1326.7  111.46  1334.6  110.57  1341.1  112.24
    1349  111.14  1355.4  113.05  1363.3  112.62  1369.8  114.09  1381.9  113.32
#Mann= 3 , 0 , 0
       0     .11       0   368.2     .09       0   609.6     .11       0
Bank Sta=368.2,609.6
XS Rating Curve= 0 ,0
Exp/Cntr=0.3,0.1

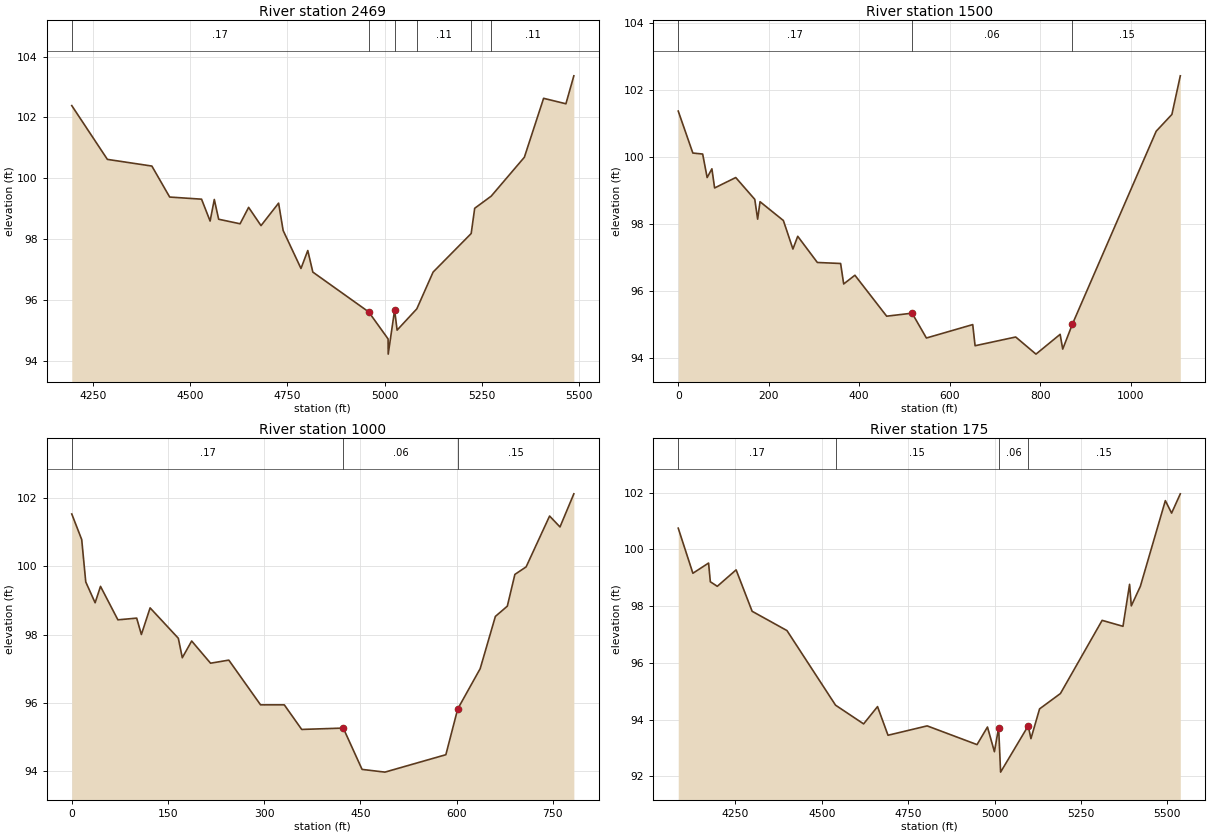
Type RM Length L Ch R = 1 ,2469    ,954,954,954
BEGIN DESCRIPTION:
UNNAMED TRIB TO WOODSONS GULLY 4.0
END DESCRIPTION:
XS GIS Cut Line= 3
       3865778.7     10043204.22      3865441.24     10042472.88
      3865064.87     10042164.99
#Sta/Elev= 30
  4195.3  102.39  4286.9  100.62  4401.4   100.4  4447.2   99.38  4529.2   99.31
  4551.2   98.59    4562    99.3  4573.2   98.65  4628.3    98.5  4650.3   99.04
  4682.2   98.44  4727.4   99.18  4739.1   98.28    4785   97.03  4802.5   97.62
  4815.5   96.91  4959.2    95.6  5009.1   94.71  5009.4   94.21  5025.9   95.66
  5032.3      95    5083    95.7  5124.9   96.91  5222.9   98.18  5231.9   99.01
  5274.4   99.41  5359.7  100.69  5409.2  102.63  5466.6  102.45    5487  103.37
#Mann= 6 ,-1 , 0
  4195.3     .17       0  4959.2     .06       0  5025.9     .15       0
    5083     .11       0  5222.9     .17       0  5274.4     .11       0
Bank Sta=4959.2,5025.9
XS Rating Curve= 0 ,0
Exp/Cntr=0.3,0.1

Type RM Length L Ch R = 1 ,1500    ,514,514,514
XS GIS Cut Line= 3
      3865857.29      10042861.7      3866107.74     10042106.37
      3866266.11     10041833.88
#Sta/Elev= 30
       0  101.37    32.3  100.12      54  100.09    63.9   99.39    74.4   99.65
    80.4   99.08   127.1   99.39   169.2   98.74   175.5   98.15   180.8   98.67
   232.4   98.11   253.5   97.26   264.1   97.64   307.5   96.86   358.9   96.83
   365.7   96.22   390.5   96.48   460.7   95.26   516.9   95.35   548.5   94.61
   650.9   95.01   656.1   94.38   745.9   94.64   790.7   94.13   844.1   94.72
   849.8   94.28   871.4   95.03  1056.4  100.77  1091.1  101.27  1109.7  102.42
#Mann= 3 , 0 , 0
       0     .17       0   516.9     .06       0   871.4     .15       0
Bank Sta=516.9,871.4
XS Rating Curve= 0 ,0
Exp/Cntr=0.3,0.1

Type RM Length L Ch R = 1 ,1000    ,825,825,825
XS GIS Cut Line= 3
      3866223.76     10042678.66      3866530.54     10042259.17
      3866630.69     10042016.12
#Sta/Elev= 30
       0  101.53    15.5  100.78    21.8   99.54    36.4   98.93    44.8   99.41
    71.9   98.43   101.2   98.48   108.5      98   122.1   98.78   166.1   97.89
   172.3   97.32   186.9   97.81   216.3   97.16   244.8   97.25   294.3   95.94
   331.3   95.94   358.4   95.22   423.2   95.26   452.5   94.05   488.1   93.97
   583.1   94.48   601.6   95.82   636.6      97   660.3   98.53   678.9   98.83
   690.7   99.76   708.2   99.98   744.8  101.47     761  101.15   782.6  102.12
#Mann= 3 , 0 , 0
       0     .17       0   423.2     .06       0   601.6     .15       0
Bank Sta=423.2,601.6
XS Rating Curve= 0 ,0
Exp/Cntr=0.3,0.1

Type RM Length L Ch R = 1 ,175     ,0,0,0
BEGIN DESCRIPTION:
UNNAMED TRIB TO WOODSONS GULLY 1.0
END DESCRIPTION:
XS GIS Cut Line= 3
      3866225.79     10042687.23      3867064.71     10042579.81
      3867127.66     10041976.05
#Sta/Elev= 30
  4084.6  100.75    4127   99.16  4172.4   99.52  4177.5   98.86  4197.6    98.7
  4252.1   99.28  4298.4   97.82  4399.2   97.14  4539.8   94.51    4621   93.85
  4661.3   94.46  4691.6   93.45  4804.9   93.78  4949.2   93.12  4979.4   93.74
  4999.5   92.87  5011.7   93.72  5017.4   92.15  5097.293.78001  5105.2   93.33
  5130.2   94.38  5190.5   94.92  5311.2    97.5  5371.5   97.29  5390.6   98.77
  5395.6   98.01  5421.8    98.7  5494.1  101.72  5512.2  101.28  5537.4  101.96
#Mann= 4 ,-1 , 0
  4084.6     .17       0  4539.8     .15       0  5011.7     .06       0
  5097.2     .15       0
Bank Sta=5011.7,5097.2
XS Rating Curve= 0 ,0
Exp/Cntr=0.3,0.1

Chan Stop Cuts=-1
Use User Specified Reach Order=0
Composite Channel Slope=5

--- UNNAMED TRIB TO WOODSONS GULLY.g10 (geometry) ---

Geom Title=Existing Conditions
Program Version=4.10

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
River Reach=UNNAMED TRIB TO ,Reach-1

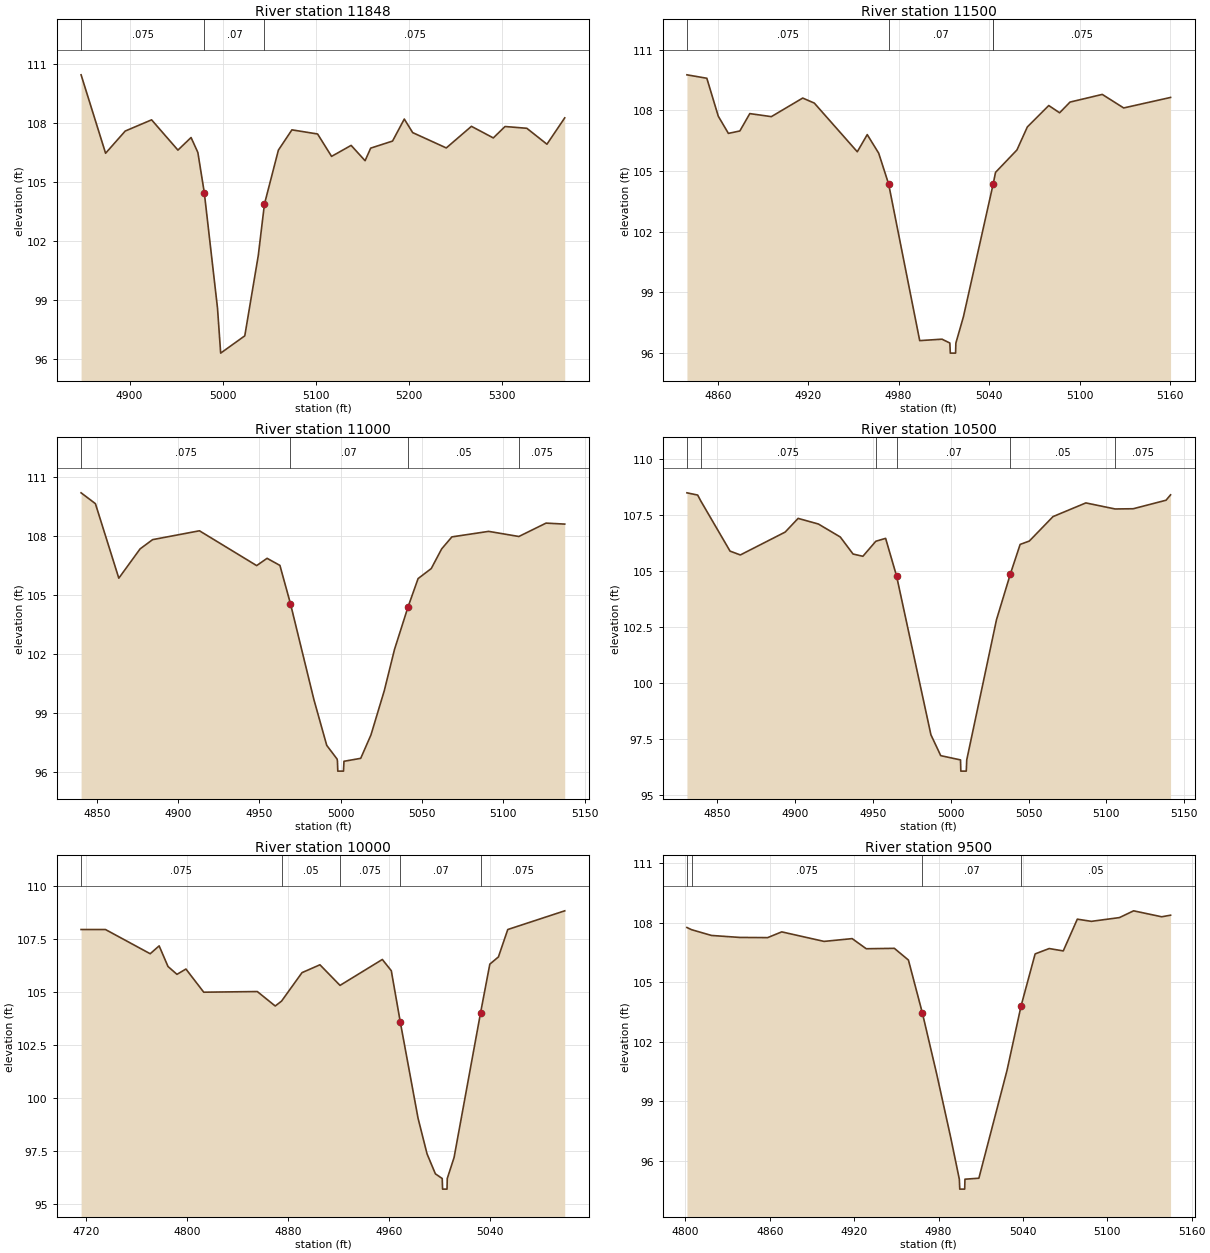
Type RM Length L Ch R = 1 ,11848   ,348,348,348
BEGIN DESCRIPTION:
UNNAMED TRIB TO WOODSONS GULLY 24.0
END DESCRIPTION:
XS GIS Cut Line= 3
      3857472.58     10042382.87      3857580.05     10042269.33
      3857781.44     10041967.24
#Sta/Elev= 30
    4848  110.46  4874.3  106.47  4895.4   107.6  4923.7  108.17    4952  106.63
  4966.1  107.27  4973.4  106.51  4980.3  104.47  4994.5   98.59  4997.9    96.3
  5023.8   97.18  5038.3  101.27  5044.9  103.88  5059.9  106.63  5074.4  107.66
    5102  107.45    5117  106.31    5138  106.87    5153  106.09    5159  106.73
  5182.5  107.09  5195.1  108.21  5204.1  107.52  5240.2  106.74  5267.2  107.84
  5290.7  107.25  5303.3  107.83  5326.7  107.74  5348.3  106.93  5367.4  108.27
#Mann= 3 , 0 , 0
    4848    .075       0  4980.3     .07       0  5044.9    .075       0
Bank Sta=4980.3,5044.9
XS Rating Curve= 0 ,0
Exp/Cntr=0.3,0.1

Type RM Length L Ch R = 1 ,11500   ,500,500,500
BEGIN DESCRIPTION:
UNNAMED TRIB TO WOODSONS GULLY 23.0
END DESCRIPTION:
XS GIS Cut Line= 3
        3857746.     10042608.14      3857851.07     10042486.94
      3857962.12      10042371.2
#Sta/Elev= 30
  4839.6  109.76  4852.8  109.59  4860.4  107.71  4867.1  106.86  4874.7  106.98
  4881.3  107.84  4895.6  107.69  4916.4  108.61  4924.1  108.36  4952.6  105.95
  4959.2   106.8  4966.8  105.88  4973.4  104.35    4994    96.6  5008.8   96.67
    5014   96.48  5014.3   95.98  5017.8   95.98    5018   96.48    5023   97.78
  5042.7  104.34  5044.3  104.93  5058.5  106.04  5065.4  107.18  5079.6  108.24
  5086.8  107.88  5093.7  108.41  5115.1  108.79  5129.3  108.12  5160.4  108.64
#Mann= 4 ,-1 , 0
  4839.6    .075       0  4973.4     .07       0  5042.7     .05       0
  5042.7    .075       0
Bank Sta=4973.4,5042.7
XS Rating Curve= 0 ,0
Exp/Cntr=0.3,0.1

Type RM Length L Ch R = 1 ,11000   ,500,500,500
BEGIN DESCRIPTION:
UNNAMED TRIB TO WOODSONS GULLY 22.0
END DESCRIPTION:
XS GIS Cut Line= 3
      3858144.44     10042919.35       3858244.8     10042795.12
      3858329.32     10042686.29
#Sta/Elev= 30
  4840.3  110.17  4849.1  109.62  4863.5  105.83  4876.6  107.32  4884.3  107.79
  4913.1  108.24  4948.3  106.47  4954.7  106.84  4962.6  106.48  4969.1  104.53
  4983.5   99.66  4991.4   97.33  4997.8   96.63    4998   96.52  4998.2   96.02
  5001.7   96.02    5002   96.52  5012.3   96.67  5018.6   97.86  5026.8  100.11
  5033.1  102.21  5041.3  104.34  5047.6  105.81  5055.7  106.32  5062.1  107.32
  5068.4  107.93    5091  108.21  5109.6  107.95  5126.3  108.63  5137.8  108.58
#Mann= 4 ,-1 , 0
  4840.3    .075       0  4969.1     .07       0  5041.3     .05       0
  5109.6    .075       0
Bank Sta=4969.1,5041.3
XS Rating Curve= 0 ,0
Exp/Cntr=0.3,0.1

Type RM Length L Ch R = 1 ,10500   ,500,500,500
BEGIN DESCRIPTION:
UNNAMED TRIB TO WOODSONS GULLY 21.0
END DESCRIPTION:
XS GIS Cut Line= 3
      3858536.33      10043238.4      3858638.53      10043103.3
      3858715.08     10042984.65
#Sta/Elev= 30
  4830.6  108.48  4837.5  108.38  4839.4  108.13  4858.3  105.88  4864.9  105.71
  4893.7  106.73    4902  107.34    4915  107.09  4929.1  106.51  4937.3  105.75
  4943.6  105.65  4951.9  106.32  4958.2  106.45  4965.2  104.78  4987.3   97.69
  4993.6   96.76  5006.3   96.57  5006.5   96.07    5010   96.07  5010.3   96.57
  5029.4  102.82  5038.4  104.88  5044.6  106.18  5050.5  106.33  5065.7  107.42
  5086.8  108.03  5105.6  107.76  5117.2  107.77  5138.3  108.15  5141.2  108.39
#Mann= 6 ,-1 , 0
  4830.6      .1       0  4839.4    .075       0  4951.9     .05       0
  4965.2     .07       0  5038.4     .05       0  5105.6    .075       0
Bank Sta=4965.2,5038.4
XS Rating Curve= 0 ,0
Exp/Cntr=0.3,0.1

Type RM Length L Ch R = 1 ,10000   ,500,500,500
BEGIN DESCRIPTION:
UNNAMED TRIB TO WOODSONS GULLY 20.0
END DESCRIPTION:
XS GIS Cut Line= 3
      3858830.84     10043611.41      3859032.26     10043411.48
      3859099.93     10043339.08
#Sta/Elev= 30
  4716.2  107.94  4735.5  107.94  4770.9   106.8    4778  107.17    4785   106.2
  4792.1  105.83  4799.2  106.08  4813.3  104.99  4855.7  105.02  4869.9  104.34
  4874.9  104.57  4891.1  105.91  4905.3  106.28  4921.2  105.31  4954.7  106.53
  4961.8     106  4968.9  103.59    4983   99.05  4990.1   97.38  4996.7   96.44
  5002.1   96.22  5002.4   95.72  5005.9   95.72  5006.1   96.22  5011.5   97.21
  5032.5  104.03  5039.8  106.31  5046.6  106.65    5054  107.94  5099.1  108.82
#Mann= 5 ,-1 , 0
  4716.2    .075       0  4874.9     .05       0  4921.2    .075       0
  4968.9     .07       0  5032.5    .075       0
Bank Sta=4968.9,5032.5
XS Rating Curve= 0 ,0
Exp/Cntr=0.3,0.1

Type RM Length L Ch R = 1 ,9500    ,496,496,496
BEGIN DESCRIPTION:
UNNAMED TRIB TO WOODSONS GULLY 19.0
END DESCRIPTION:
XS GIS Cut Line= 3
      3859502.51     10043688.41      3859512.59     10043489.76
       3859511.2     10043344.77
#Sta/Elev= 30
  4801.1  107.75  4804.4  107.64  4818.5  107.35  4838.5  107.25  4858.5  107.24
  4868.5  107.53  4898.6  107.05  4918.6  107.19  4928.6  106.68  4948.6   106.7
  4958.6  106.11  4968.6  103.42  4978.7  100.37  4988.7   97.16  4994.8   95.07
  4995.1   94.57  4998.6   94.57  4998.8   95.07  5008.7   95.12  5028.7  100.55
  5038.7   103.8  5048.7  106.42  5058.7  106.69  5068.7  106.57  5078.7  108.17
  5088.7  108.06  5108.7  108.25  5118.7  108.59  5138.7  108.29    5145  108.37
#Mann= 4 ,-1 , 0
  4801.1     .05       0  4804.4    .075       0  4968.6     .07       0
  5038.7     .05       0
Bank Sta=4968.6,5038.7
XS Rating Curve= 0 ,0
Exp/Cntr=0.3,0.1