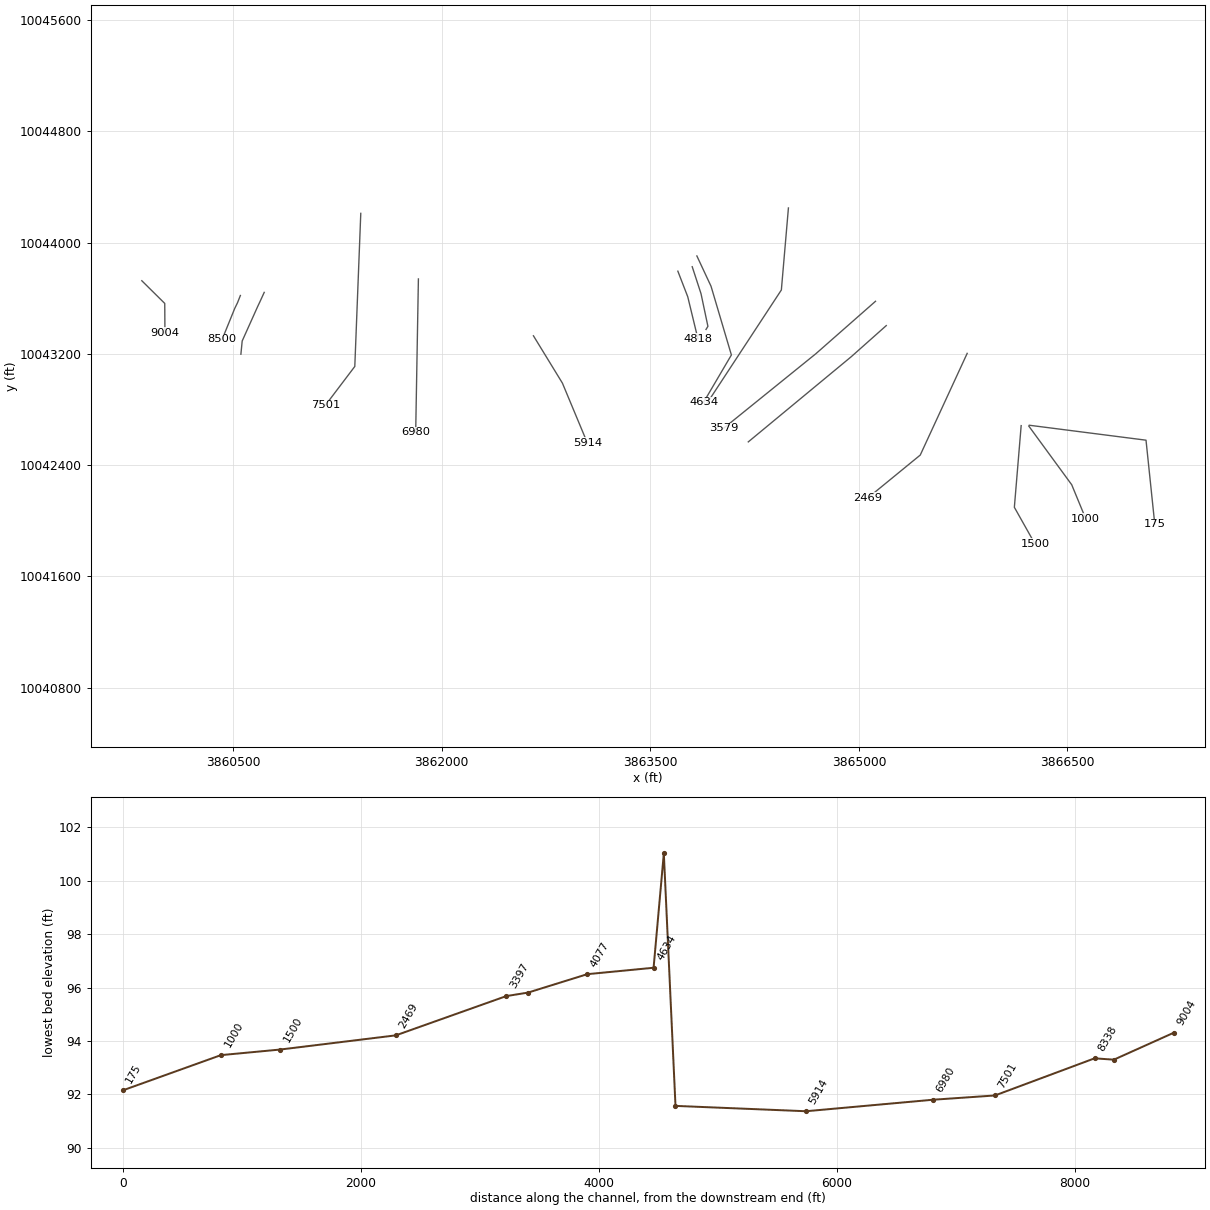
HEC-RAS study UNNAMED TRIB TO WOODSONS GULLY.prj: UNNAMED TRIB TO WOODSONS GULLY Base Level Engineering

--- UNNAMED TRIB TO WOODSONS GULLY.g10 (geometry) --- (continued)

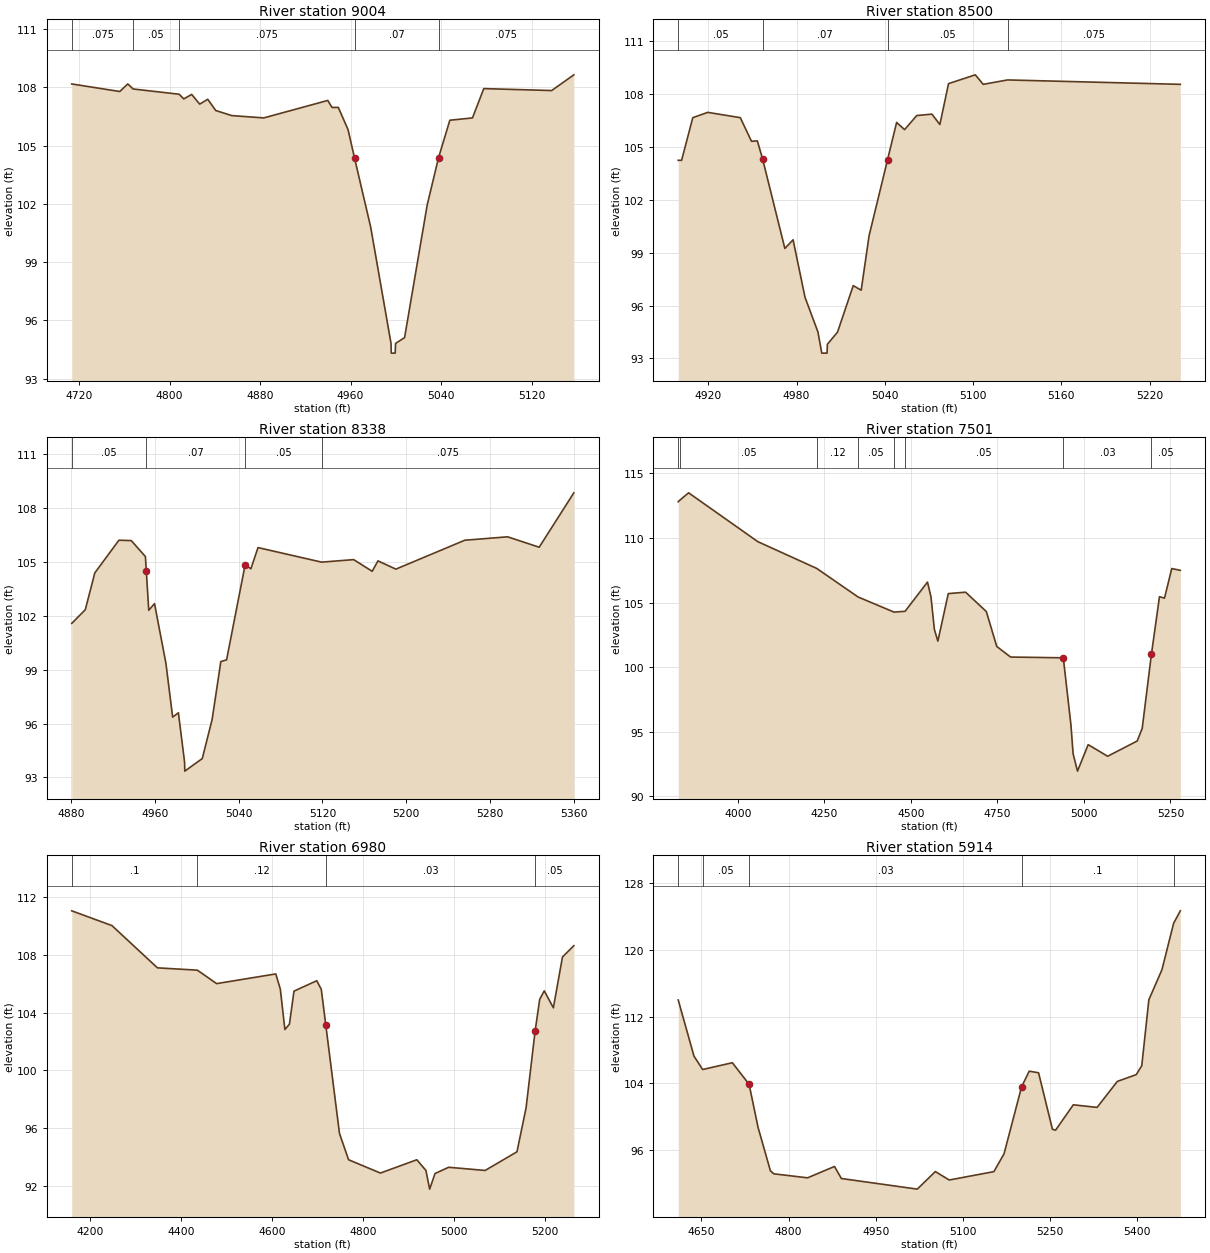
Type RM Length L Ch R = 1 ,9004    ,504,504,504
BEGIN DESCRIPTION:
UNNAMED TRIB TO WOODSONS GULLY 18.0
END DESCRIPTION:
XS GIS Cut Line= 3
      3859843.22     10043726.42      3860008.15     10043563.28
      3860009.53     10043351.47
#Sta/Elev= 30
  4713.6  108.18    4756  107.79  4763.1  108.18  4767.9  107.92  4808.5  107.65
  4812.6  107.41  4819.6  107.64  4826.7  107.14  4833.8  107.39  4840.9  106.81
    4855  106.55  4883.3  106.43  4939.9  107.33  4943.6  106.97  4949.2  106.97
  4957.8  105.83 4963.61 104.348  4977.8  100.81  4995.8   94.81    4996   94.31
  4999.5   94.31  4999.8   94.81  5007.8   95.11  5027.8  101.95  5037.8  104.38
  5047.8  106.31  5067.8  106.43  5077.8  107.94  5137.8  107.84  5157.4  108.65
#Mann= 5 ,-1 , 0
  4713.6    .075       0  4767.9     .05       0  4808.5    .075       0
 4963.61     .07       0  5037.8    .075       0
Bank Sta=4963.61,5037.8
XS Rating Curve= 0 ,0
Exp/Cntr=0.3,0.1

Type RM Length L Ch R = 1 ,8500    ,162,162,162
BEGIN DESCRIPTION:
UNNAMED TRIB TO WOODSONS GULLY 17.0
END DESCRIPTION:
XS GIS Cut Line= 4
      3860552.02     10043620.29      3860531.66     10043568.77
      3860511.85     10043528.25      3860421.01     10043305.13
#Sta/Elev= 30
  4899.5  104.24  4901.8  104.24  4909.4  106.66  4919.6  106.96  4941.7  106.66
  4949.3  105.32  4953.3  105.34 4956.82 104.332    4972   99.24  4977.6   99.73
  4985.7   96.47  4994.5    94.5  4997.1    93.3  5000.7    93.3  5000.9    93.8
  5007.8   94.49  5018.5   97.13  5023.9   96.87  5029.3   99.97  5041.8 104.261
    5048  106.39  5053.4  105.98  5061.7  106.78    5072  106.86  5077.4  106.27
  5083.3  108.59  5101.5  109.09  5106.9  108.55  5123.4   108.8  5240.9  108.55
#Mann= 4 ,-1 , 0
  4899.5     .05       0 4956.82     .07       0  5041.8     .05       0
  5123.4    .075       0
Bank Sta=4956.82,5041.8
XS Rating Curve= 0 ,0
Exp/Cntr=0.3,0.1

Type RM Length L Ch R = 1 ,8338    ,837,837,837
BEGIN DESCRIPTION:
UNNAMED TRIB TO WOODSONS GULLY 16.0
END DESCRIPTION:
XS GIS Cut Line= 5
      3860723.51     10043642.76       3860694.3     10043578.86
      3860676.07     10043540.32      3860565.02     10043293.03
      3860555.76     10043198.15
#Sta/Elev= 30
  4880.7  101.58  4893.6  102.34  4902.7  104.39  4925.7  106.21  4937.5  106.19
    4951   105.3 4951.85 104.506  4954.2  102.31  4959.7  102.68  4970.6   99.35
    4977   96.36  4982.5    96.6  4988.4   93.85  4988.6   93.35  5005.3   94.05
  5014.7   96.23    5023   99.45  5028.5   99.55  5046.2  104.84  5051.7  104.62
  5058.5   105.8  5119.2  104.99  5149.8  105.13  5167.5  104.48    5173  105.06
  5190.1   104.6  5255.9  106.21  5296.8   106.4  5326.9  105.82    5360  108.85
#Mann= 4 ,-1 , 0
  4880.7     .05       0 4951.85     .07       0  5046.2     .05       0
  5119.2    .075       0
Bank Sta=4951.85,5046.2
XS Rating Curve= 0 ,0
Exp/Cntr=0.3,0.1

Type RM Length L Ch R = 1 ,7501    ,521,521,521
BEGIN DESCRIPTION:
UNNAMED TRIB TO WOODSONS GULLY 15.0
END DESCRIPTION:
XS GIS Cut Line= 3
      3861417.85     10044211.03      3861374.86     10043110.02
      3861163.94      10042831.4
#Sta/Elev= 30
  3827.3  112.81  3833.2  112.96  3857.3   113.5  4057.4  109.72  4227.6  107.65
  4347.1  105.44  4450.9  104.27    4483  104.33  4547.8  106.59  4557.8  105.46
  4567.8  102.92  4577.8  102.02  4607.9   105.7  4657.9  105.81  4717.9  104.31
    4748  101.61    4788  100.79  4940.4  100.73  4962.4   95.55  4968.7   93.31
  4981.4   91.96  5012.3   94.01  5068.5   93.11  5153.9   94.29  5168.4   95.26
  5195.1 100.999  5218.4  105.46  5232.9  105.35  5253.9  107.64  5278.6   107.5
#Mann= 8 ,-1 , 0
  3827.3     .12       0  3833.2     .05       0  4227.6     .12       0
  4347.1     .05       0  4450.9      .1       0    4483     .05       0
  4940.4     .03       0  5195.1     .05       0
Bank Sta=4940.4,5195.1
XS Rating Curve= 0 ,0
Exp/Cntr=0.3,0.1

Type RM Length L Ch R = 1 ,6980    ,1066,1066,1066
BEGIN DESCRIPTION:
UNNAMED TRIB TO WOODSONS GULLY 14.0
END DESCRIPTION:
XS GIS Cut Line= 2
      3861832.23     10043739.38       3861812.7     10042636.05
#Sta/Elev= 30
  4159.1  111.03  4247.4  110.01  4347.4  107.09  4435.1  106.93  4477.5     106
  4607.5  106.67  4617.5  105.62  4627.5  102.83  4637.5   103.2  4647.5  105.48
  4697.5   106.2  4707.5  105.61  4717.5  103.12  4747.5   95.65  4767.5   93.83
  4837.5   92.91  4917.5   93.83  4937.5   93.09  4945.7    91.8  4957.5   92.88
  4987.5   93.31  5067.6   93.09  5137.6   94.38  5157.6   97.41  5177.6  102.75
  5187.6  104.92  5197.6   105.5  5217.6  104.33  5237.6  107.84  5262.6  108.62
#Mann= 4 ,-1 , 0
  4159.1      .1       0  4435.1     .12       0  4717.5     .03       0
  5177.6     .05       0
Bank Sta=4717.5,5177.6
XS Rating Curve= 0 ,0
Exp/Cntr=0.3,0.1

Type RM Length L Ch R = 1 ,5914    ,1096,1096,1096
BEGIN DESCRIPTION:
UNNAMED TRIB TO WOODSONS GULLY 11.0
END DESCRIPTION:
XS GIS Cut Line= 3
      3862659.49     10043330.51      3862867.82     10042990.23
      3863046.78     10042561.14
#Sta/Elev= 30
    4610  113.98  4637.1  107.27    4652  105.67  4703.1  106.48  4731.9  103.91
  4747.3   98.77  4768.6   93.56  4774.5    93.2  4832.5   92.72  4878.9   94.08
  4890.7   92.64  5021.3   91.37  5052.4   93.47  5076.3   92.46  5153.1   93.46
  5170.6   95.59  5200.8   103.6  5213.9  105.47    5230  105.28  5253.9   98.52
  5259.3   98.42  5289.8  101.45  5330.7  101.14  5365.6  104.25  5398.1  105.06
  5407.6  106.13  5419.8  114.01  5442.3   117.6  5462.4  123.15  5473.9  124.64
#Mann= 5 ,-1 , 0
    4610     .12       0    4652     .05       0  4731.9     .03       0
  5200.8      .1       0  5462.4     .05       0
Bank Sta=4731.9,5200.8
XS Rating Curve= 0 ,0
Exp/Cntr=0.3,0.1

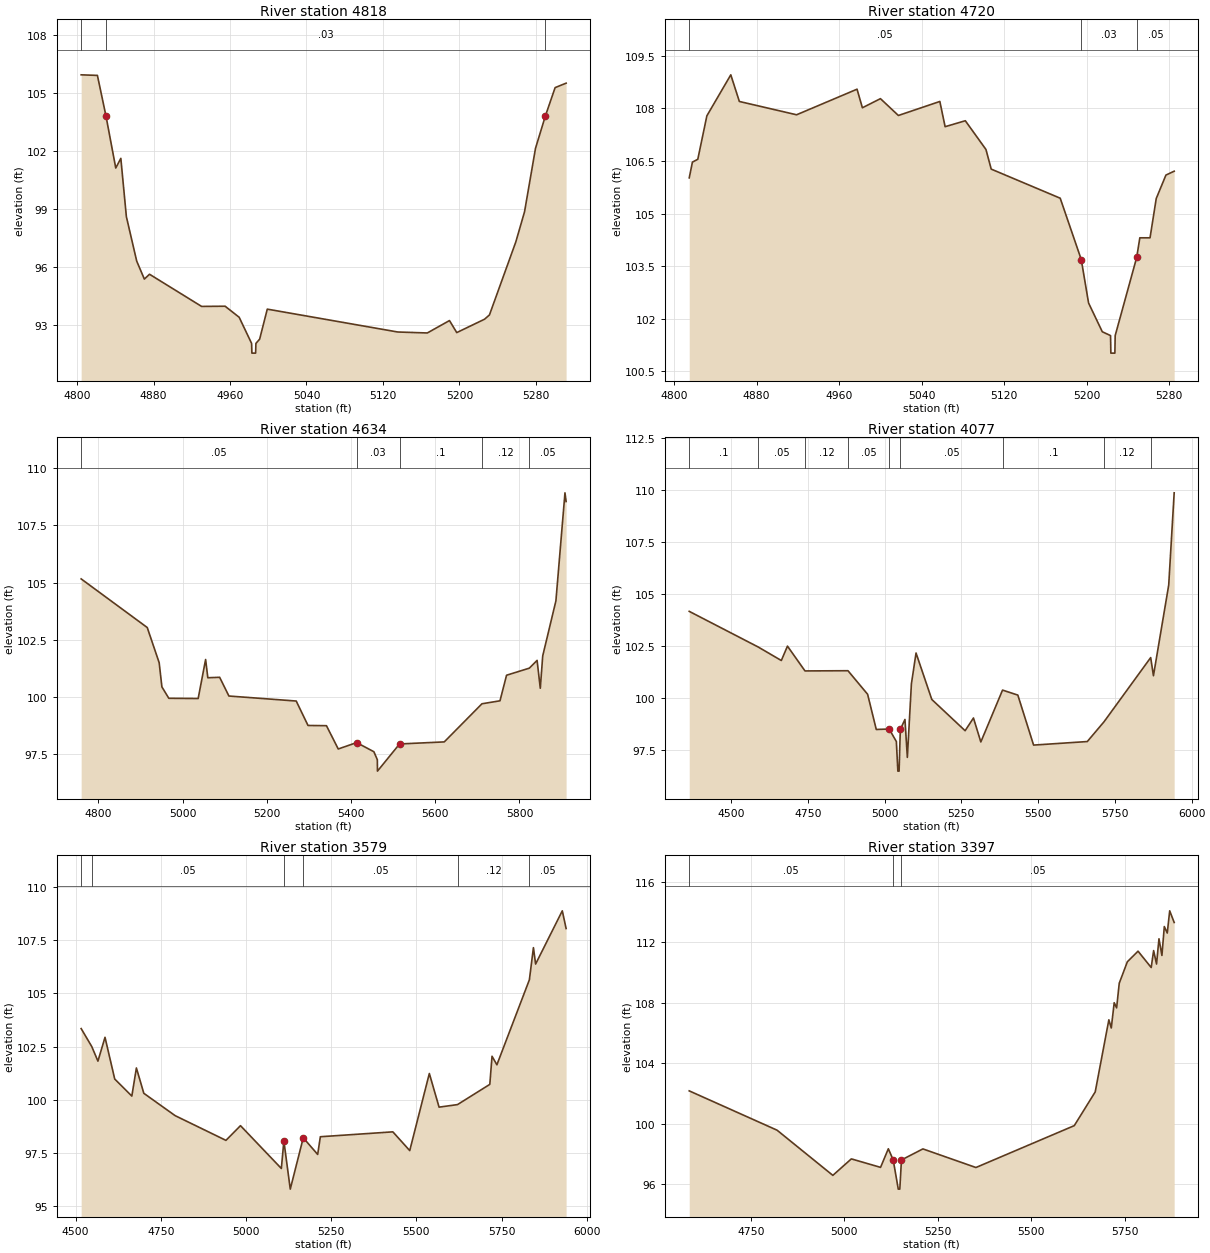
Type RM Length L Ch R = 1 ,4818    ,98,98,98
BEGIN DESCRIPTION:
UNNAMED TRIB TO WOODSONS GULLY 10.0
END DESCRIPTION:
XS GIS Cut Line= 3
      3863698.03     10043795.23      3863769.23     10043611.17
      3863842.15     10043309.92
#Sta/Elev= 30
  4804.3  105.93  4821.3   105.9  4830.2  103.82  4840.5  101.12  4845.8  101.62
  4851.6   98.61  4862.4   96.32  4870.4   95.39  4875.8   95.64  4930.3   93.98
  4954.9   93.99  4969.6   93.42  4982.6   92.07  4982.9   91.57  4986.8   91.57
  4987.1   92.07    4991   92.29    4999   93.84  5135.5   92.66  5166.4   92.61
  5189.6   93.25  5197.2   92.63  5226.3   93.32  5231.4   93.54    5259   97.31
  5268.1   98.86  5279.6  102.14  5289.8  103.79  5300.1  105.27  5311.6   105.5
#Mann= 3 , 0 , 0
  4804.3     .05       0  4830.2     .03       0  5289.8      .1       0
Bank Sta=4830.2,5289.8
XS Rating Curve= 0 ,0
Exp/Cntr=0.3,0.1

Type RM Length L Ch R = 1 ,4720    ,86,86,86
BEGIN DESCRIPTION:
UNNAMED TRIB TO WOODSONS GULLY 9.0
END DESCRIPTION:
XS GIS Cut Line= 4
      3863801.34     10043827.32      3863864.71     10043632.87
      3863914.19     10043398.49      3863900.54      10043376.2
#Sta/Elev= 30
  4814.7  106.02  4817.8  106.47    4823  106.55  4831.8  107.79    4855  108.96
  4863.3   108.2  4918.8  107.82  4977.4  108.55  4982.6  108.02  5000.1  108.28
  5017.5   107.8  5057.7   108.2  5062.8  107.48  5082.4  107.65  5102.4  106.83
  5107.5  106.27  5174.4  105.44  5194.8  103.69  5201.9  102.45  5215.2  101.63
  5223.2  101.52  5223.5  101.02  5227.4  101.02  5227.7  101.52 5248.56  103.75
  5251.6  104.31  5261.5  104.31  5267.5  105.43  5276.9   106.1  5284.9  106.21
#Mann= 3 , 0 , 0
  4814.7     .05       0  5194.8     .03       0 5248.56     .05       0
Bank Sta=5194.8,5248.56
XS Rating Curve= 0 ,0
Exp/Cntr=0.3,0.1

Type RM Length L Ch R = 1 ,4634    ,557,557,557
BEGIN DESCRIPTION:
UNNAMED TRIB TO WOODSONS GULLY 8.0
END DESCRIPTION:
XS GIS Cut Line= 4
      3863834.82     10043904.73      3863936.68     10043686.76
      3864083.04     10043192.59      3863882.67      10042851.7
#Sta/Elev= 30
  4759.4  105.16  4916.3  103.03  4944.6  101.49  4951.1  100.43  4967.5   99.93
  5037.2   99.92  5054.9  101.63  5060.1  100.83  5088.2  100.85  5110.2  100.03
    5270   99.81    5298   98.74  5341.8   98.73  5369.8   97.71  5413.5   97.99
  5454.4   97.59  5462.6   97.24  5462.9   96.74  5515.4   97.93  5621.5   98.02
    5711   99.69  5753.8   99.82  5769.4  100.94  5823.4  101.25  5841.9  101.59
  5849.5  100.37  5855.3  101.79  5886.6   104.2  5908.1  108.93  5910.8  108.55
#Mann= 5 ,-1 , 0
  4759.4     .05       0  5413.5     .03       0  5515.4      .1       0
    5711     .12       0  5823.4     .05       0
Bank Sta=5413.5,5515.4
XS Rating Curve= 0 ,0
Exp/Cntr=0.3,0.1

Type RM Length L Ch R = 1 ,4077    ,498,498,498
BEGIN DESCRIPTION:
UNNAMED TRIB TO WOODSONS GULLY 7.0
END DESCRIPTION:
XS GIS Cut Line= 3
      3864493.19     10044249.84      3864442.42     10043660.04
      3863900.87     10042834.61
#Sta/Elev= 30
  4363.9  104.17  4588.3  102.46  4663.8  101.81  4683.8   102.5  4740.9  101.31
  4880.8  101.32  4944.8  100.19    4973    98.5  5015.1   98.52  5038.4   97.92
  5043.3    96.5  5047.3    96.5  5051.3    98.5  5066.4   98.98  5074.2   97.16
  5087.4  100.69  5102.5  102.17  5153.8   99.94  5262.3   98.44  5289.5   99.05
  5313.5    97.9  5384.2  100.39    5434  100.15  5485.3   97.75  5660.2   97.92
  5714.7   98.87  5866.6  101.95  5875.6  101.08  5925.3  105.43  5943.1  109.86
#Mann= 9 ,-1 , 0
  4363.9      .1       0  4588.3     .05       0  4740.9     .12       0
  4880.8     .05       0  5015.1     .07       0  5051.3     .05       0
  5384.2      .1       0  5714.7     .12       0  5866.6     .05       0
Bank Sta=5015.1,5051.3
XS Rating Curve= 0 ,0
Exp/Cntr=0.3,0.1

Type RM Length L Ch R = 1 ,3579    ,182,182,182
BEGIN DESCRIPTION:
UNNAMED TRIB TO WOODSONS GULLY 6.0
END DESCRIPTION:
XS GIS Cut Line= 3
      3865119.52     10043578.74      3864690.56     10043201.67
      3864027.92     10042666.01
#Sta/Elev= 30
  4516.1  103.35  4547.4   102.5  4565.3  101.82  4586.1  102.94  4614.6  100.98
  4664.8  100.18  4678.2   101.5    4700  100.31    4792   99.26    4941    98.1
  4983.7   98.79  5103.6   96.78    5111   98.07  5129.8   95.81  5167.9   98.22
  5210.2   97.44  5218.1   98.27  5430.8    98.5  5480.4   97.62  5537.9  101.24
  5566.5   99.66  5620.6   99.78  5715.4  100.73  5721.9  102.05  5736.2  101.65
  5831.5  105.64  5843.4  107.15  5849.8  106.38  5928.1  108.88  5939.3  108.05
#Mann= 6 ,-1 , 0
  4516.1     .12       0  4547.4     .05       0    5111     .07       0
  5167.9     .05       0  5620.6     .12       0  5831.5     .05       0
Bank Sta=5111,5167.9
XS Rating Curve= 0 ,0
Exp/Cntr=0.3,0.1

Type RM Length L Ch R = 1 ,3397    ,928,928,928
BEGIN DESCRIPTION:
UNNAMED TRIB TO WOODSONS GULLY 5.0
END DESCRIPTION:
XS GIS Cut Line= 3
      3865196.75     10043403.77      3864945.64     10043180.65
      3864204.56      10042567.6
#Sta/Elev= 30
  4585.2  102.18  4820.2   99.58  4969.5   96.59    5019   97.68  5097.2   97.12
    5118   98.35  5131.1  97.604  5144.6   95.68  5148.7   95.68  5153.1   97.61
  5210.5   98.34  5352.4   97.11  5615.6   99.88  5671.6  102.11  5708.1  106.88
  5714.6  106.34  5722.4  108.01  5728.9  107.67  5735.9   109.3  5757.6  110.72
  5786.2  111.42  5821.4  110.34  5827.9  111.46  5835.7  110.57  5842.2  112.24
  5850.1  111.14  5856.5  113.05  5864.4  112.62  5870.9  114.09  5882.9  113.32
#Mann= 3 , 0 , 0
  4585.2     .05       0  5131.1     .07       0  5153.1     .05       0
Bank Sta=5131.1,5153.1
XS Rating Curve= 0 ,0
Exp/Cntr=0.3,0.1

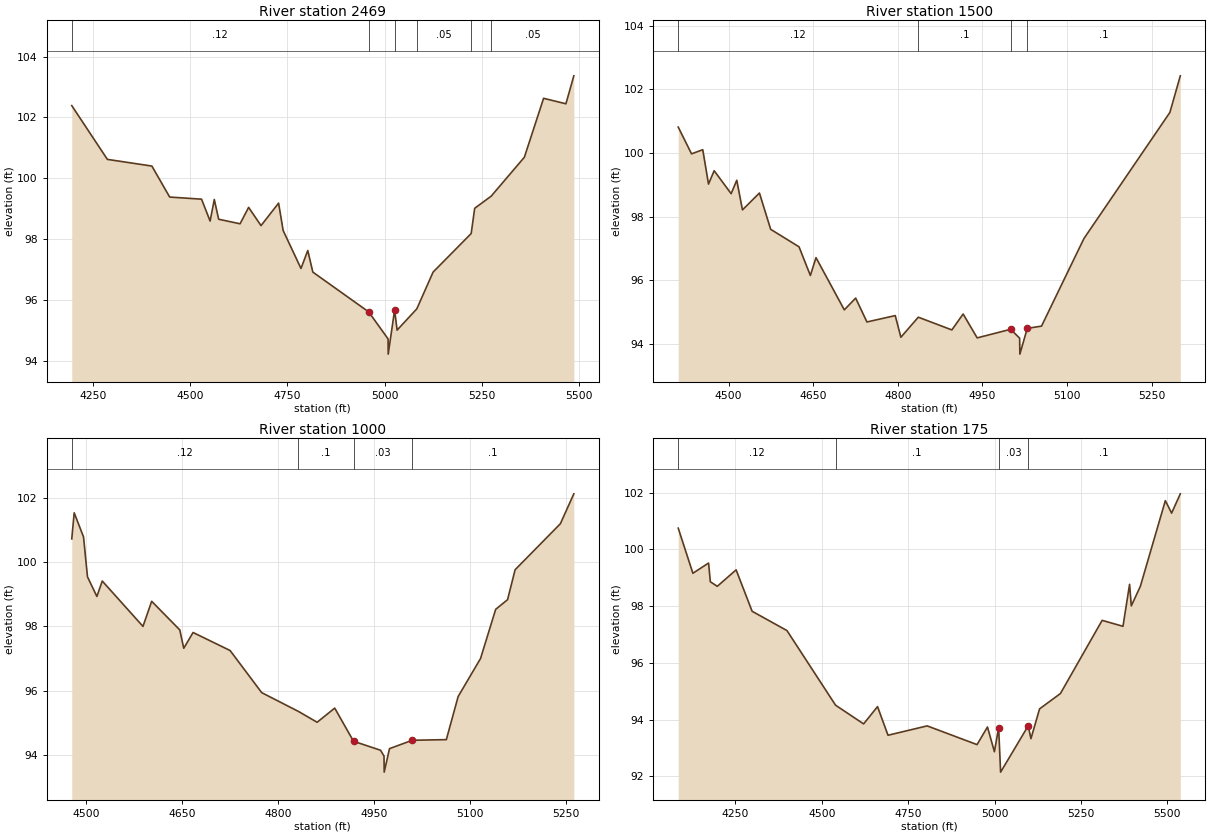
Type RM Length L Ch R = 1 ,2469    ,969,969,969
BEGIN DESCRIPTION:
UNNAMED TRIB TO WOODSONS GULLY 4.0
END DESCRIPTION:
XS GIS Cut Line= 3
       3865778.7     10043204.22      3865441.24     10042472.88
      3865064.87     10042164.99
#Sta/Elev= 30
  4195.3  102.39  4286.9  100.62  4401.4   100.4  4447.2   99.38  4529.2   99.31
  4551.2   98.59    4562    99.3  4573.2   98.65  4628.3    98.5  4650.3   99.04
  4682.2   98.44  4727.4   99.18  4739.1   98.28    4785   97.03  4802.5   97.62
  4815.5   96.91  4959.2    95.6  5009.1   94.71  5009.4   94.21  5025.9   95.66
  5032.3      95    5083    95.7  5124.9   96.91  5222.9   98.18  5231.9   99.01
  5274.4   99.41  5359.7  100.69  5409.2  102.63  5466.6  102.45    5487  103.37
#Mann= 6 ,-1 , 0
  4195.3     .12       0  4959.2     .03       0  5025.9      .1       0
    5083     .05       0  5222.9     .12       0  5274.4     .05       0
Bank Sta=4959.2,5025.9
XS Rating Curve= 0 ,0
Exp/Cntr=0.3,0.1

Type RM Length L Ch R = 1 ,1500    ,500,500,500
BEGIN DESCRIPTION:
UNNAMED TRIB TO WOODSONS GULLY 3.0
END DESCRIPTION:
XS GIS Cut Line= 3
      3866166.86     10042684.56      3866117.91     10042097.19
       3866265.5     10041834.98
#Sta/Elev= 30
  4410.6  100.81  4434.2   99.97  4454.1   100.1  4464.3   99.02  4474.3   99.44
  4504.4   98.72  4514.4   99.14  4524.5   98.21  4554.6   98.74  4574.5    97.6
  4624.8   97.05  4644.9   96.15  4654.9   96.71  4705.1   95.07  4725.2   95.44
  4745.2   94.69  4795.4   94.89  4805.4   94.21  4836.3   94.84  4895.8   94.44
  4915.8   94.94  4940.7   94.19    5000   94.46    5016   94.18  5016.4   93.68
  5029.5  94.489  5054.8   94.56    5130   97.31  5282.4  101.27  5300.9  102.42
#Mann= 4 ,-1 , 0
  4410.6     .12       0  4836.3      .1       0    5000     .03       0
  5029.5      .1       0
Bank Sta=5000,5029.5
XS Rating Curve= 0 ,0
Exp/Cntr=0.3,0.1

Type RM Length L Ch R = 1 ,1000    ,825,825,825
BEGIN DESCRIPTION:
UNNAMED TRIB TO WOODSONS GULLY 2.0
END DESCRIPTION:
XS GIS Cut Line= 3
      3866221.99     10042680.95      3866530.54     10042259.17
       3866630.7      10042016.1
#Sta/Elev= 30
  4477.4  100.72  4481.2  101.53  4495.8  100.78    4502   99.54  4516.7   98.93
  4525.1   99.41  4588.8      98  4602.4   98.78  4646.4   97.89  4652.6   97.32
  4667.2   97.81  4725.1   97.25  4774.6   95.94  4831.7   95.36  4861.3   95.02
  4888.8   95.46  4918.2   94.43  4960.5   94.15  4965.9   93.97  4966.2   93.47
  4974.5    94.2  5010.1   94.46  5063.4   94.48  5081.9   95.82  5116.9      97
  5140.6   98.53  5159.2   98.83    5171   99.76  5241.8  101.19  5262.9  102.12
#Mann= 4 ,-1 , 0
  4477.4     .12       0  4831.7      .1       0  4918.2     .03       0
  5010.1      .1       0
Bank Sta=4918.2,5010.1
XS Rating Curve= 0 ,0
Exp/Cntr=0.3,0.1

Type RM Length L Ch R = 1 ,175     ,0,0,0
BEGIN DESCRIPTION:
UNNAMED TRIB TO WOODSONS GULLY 1.0
END DESCRIPTION:
XS GIS Cut Line= 3
      3866225.79     10042687.23      3867064.71     10042579.81
      3867127.66     10041976.05
#Sta/Elev= 30
  4084.6  100.75    4127   99.16  4172.4   99.52  4177.5   98.86  4197.6    98.7
  4252.1   99.28  4298.4   97.82  4399.2   97.14  4539.8   94.51    4621   93.85
  4661.3   94.46  4691.6   93.45  4804.9   93.78  4949.2   93.12  4979.4   93.74
  4999.5   92.87  5011.7   93.72  5017.4   92.15  5097.2   93.78  5105.2   93.33
  5130.2   94.38  5190.5   94.92  5311.2    97.5  5371.5   97.29  5390.6   98.77
  5395.6   98.01  5421.8    98.7  5494.1  101.72  5512.2  101.28  5537.4  101.96
#Mann= 4 ,-1 , 0
  4084.6     .12       0  4539.8      .1       0  5011.7     .03       0
  5097.2      .1       0
Bank Sta=5011.7,5097.2
XS Rating Curve= 0 ,0
Exp/Cntr=0.3,0.1