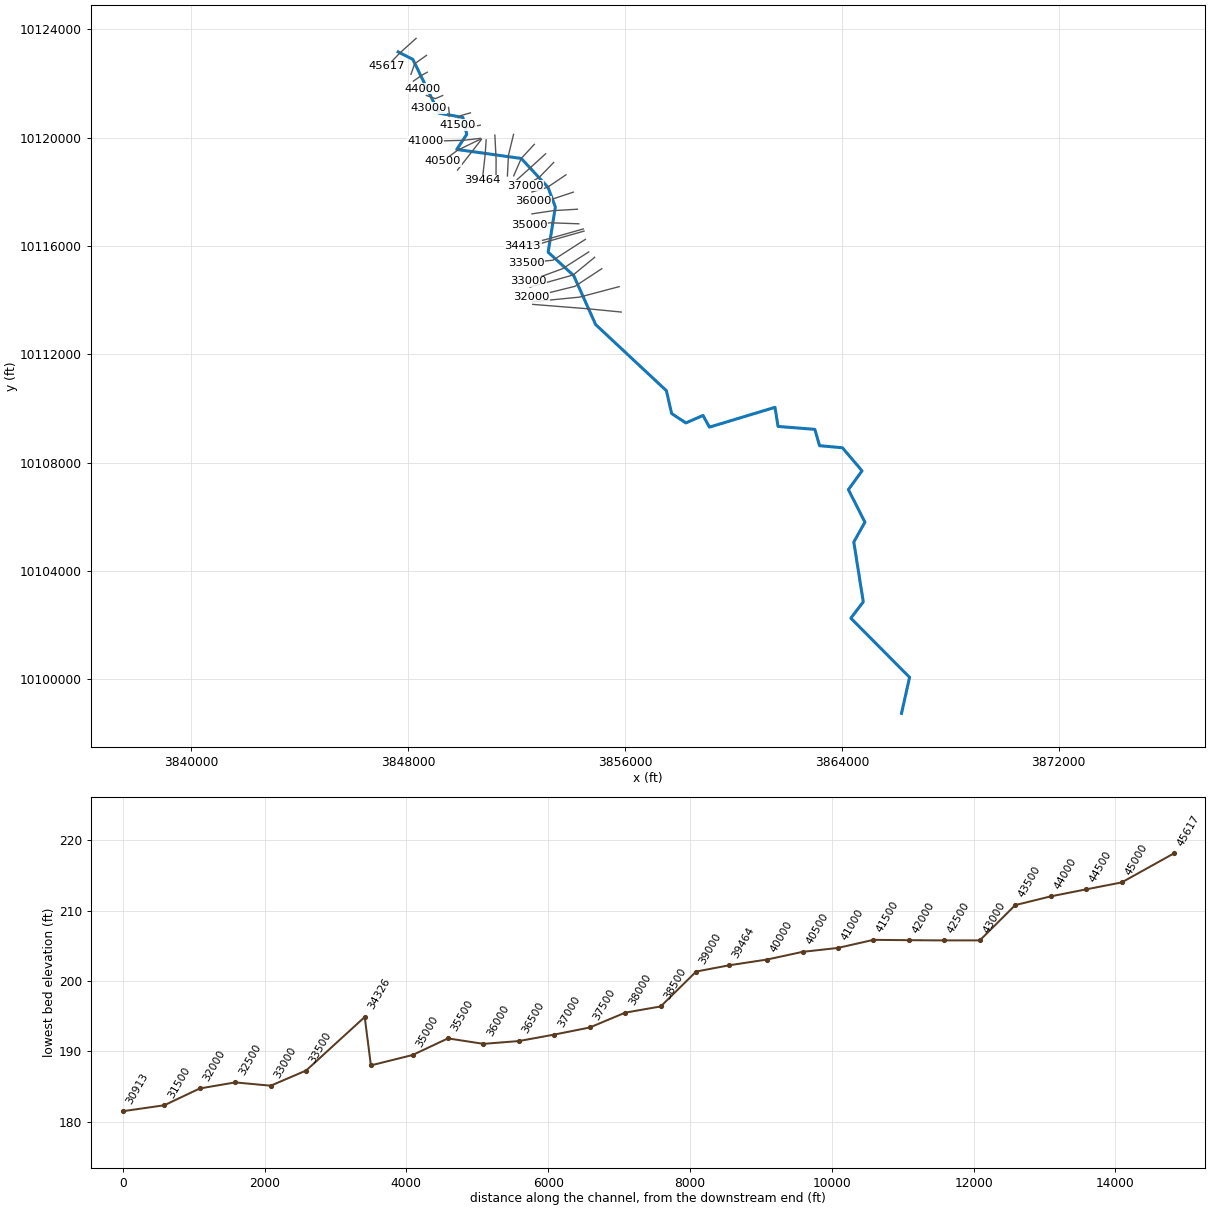
--- WEST FORK OF CRYSTAL CREEK.prj (project) ---

Proj Title=WEST FORK OF CRYSTAL CREEK Base Level Engineering
Current Plan=p01
Default Exp/Contr=0.3,0.1
English Units
Geom File=g01
Flow File=f01
Plan File=p01
Y Axis Title=Elevation
X Axis Title(PF)=Main Channel Distance
X Axis Title(XS)=Station
BEGIN DESCRIPTION:
WEST FORK OF CRYSTAL CREEK
END DESCRIPTION:
DSS Export Rating Curves= 0
DSS Export Rating Curve Sorted= 0
DSS Export Volume Flow Curves= 0
DXF OffsetX= 0
DXF OffsetY= 0
DXF ScaleX= 1
DXF ScaleY= 10

--- WEST FORK OF CRYSTAL CREEK.p01 (plan) ---

Plan Title=Multiple Run
Short Identifier=Multiple
Geom File=g01
Flow File=f01
Subcritical Flow
K Sum by GR= 0
Std Step Tol= 0.01
Critical Tol= 0.01
Num of Std Step Trials= 20
Max Error Tol= 0.3
Flow Tol Ratio= 0.001
Split Flow NTrial= 30
Split Flow Tol= 0.02
Split Flow Ratio= 0.02
Log Output Level= 0
Friction Slope Method= 1
Unsteady Friction Slope Method= 2
Unsteady Bridges Friction Slope Method= 1
Parabolic Critical Depth
Global Vel Dist=  1 , 1 , 1
Global Log Level= 0
CheckData=True
Encroach Param= -1, 0, 0, 0
BEGIN DESCRIPTION:
Multiple Run
END DESCRIPTION:

--- WEST FORK OF CRYSTAL CREEK.f01 (steady flow) ---

Flow Title=Multiple
Program Version=4.10
Number of Profiles= 7
Profile Names=10-year,25-year,50-year,1pct_min,100-year,1pct_plu,500-year
River Rch & RM=WEST FORK OF CRY,Reach-1         ,45617
     536     703     929     403    1218    3678    2167
River Rch & RM=WEST FORK OF CRY,Reach-1         ,45000
     874    1172    1573     692    2090    6312    3820
River Rch & RM=WEST FORK OF CRY,Reach-1         ,38500
    1074    1450    1955     863    2607    7873    4794
River Rch & RM=WEST FORK OF CRY,Reach-1         ,30752
    1308    1793    2440    1088    3286    9924    6166
River Rch & RM=WEST FORK OF CRY,Reach-1         ,25500
    1861    2592    3566    1606    4850   14647    9283
River Rch & RM=WEST FORK OF CRY,Reach-1         ,25000
    1861    2592    3566    1606    4850   14647    9283
River Rch & RM=WEST FORK OF CRY,Reach-1         ,19076
    2221    3117    4310    1950    5889   17784   11371
River Rch & RM=WEST FORK OF CRY,Reach-1         ,15038
    2368    3328    4609    2087    6304   19038   12202
River Rch & RM=WEST FORK OF CRY,Reach-1         ,14000
    2368    3328    4609    2087    6304   19038   12202
River Rch & RM=WEST FORK OF CRY,Reach-1         ,12568
    2389    3351    4632    2094    6323   19095   12190
River Rch & RM=WEST FORK OF CRY,Reach-1         ,6500
    2607    3670    5086    2305    6960   21019   13481
River Rch & RM=WEST FORK OF CRY,Reach-1         ,2000
    2624    3693    5120    2320    7006   21158   13569
Boundary for River Rch & Prof#=WEST FORK OF CRY,Reach-1         , 1
Up Type= 0
Dn Type= 3
Dn Slope=0.005
Boundary for River Rch & Prof#=WEST FORK OF CRY,Reach-1         , 2
Up Type= 0
Dn Type= 3
Dn Slope=0.005
Boundary for River Rch & Prof#=WEST FORK OF CRY,Reach-1         , 3
Up Type= 0
Dn Type= 3
Dn Slope=0.005
Boundary for River Rch & Prof#=WEST FORK OF CRY,Reach-1         , 4
Up Type= 0
Dn Type= 3
Dn Slope=0.005
Boundary for River Rch & Prof#=WEST FORK OF CRY,Reach-1         , 5
Up Type= 0
Dn Type= 3
Dn Slope=0.005
Boundary for River Rch & Prof#=WEST FORK OF CRY,Reach-1         , 6
Up Type= 0
Dn Type= 3
Dn Slope=0.005
Boundary for River Rch & Prof#=WEST FORK OF CRY,Reach-1         , 7
Up Type= 0
Dn Type= 3
Dn Slope=0.005
DSS Import GetInterval= 0
DSS Import GetPeak= 0
DSS Import FillOption= 0

--- WEST FORK OF CRYSTAL CREEK.g01 (geometry) ---

Geom Title=Existing Conditions
Program Version=4.10

River Reach=WEST FORK OF CRY,Reach-1
Reach XY= 30
      3847625.36       10123172.      3848169.85     10122894.27
      3849131.79      10120909.8      3850013.77     10120753.01
       3850156.7     10120127.44      3849787.35     10119570.19
      3852168.67      10119236.9      3853156.21     10118169.69
       3853426.1     10117444.67      3853160.89     10115776.04
      3854104.14     10114909.98       3854912.6     10113103.45
      3857523.34     10110661.68       3857716.5     10109818.35
      3858242.54       10109472.      3858875.35     10109748.04
      3859109.73     10109315.75      3861528.24     10110046.86
      3861643.38     10109341.91        3863000.     10109234.04
       3863174.5     10108631.33      3864019.83     10108553.74
      3864742.42     10107702.42      3864238.77     10107009.74
      3864848.67     10105806.81      3864437.86     10105074.22
      3864787.96      10102864.9      3864328.88     10102262.08
      3866495.71     10100077.63      3866198.24     10098746.86

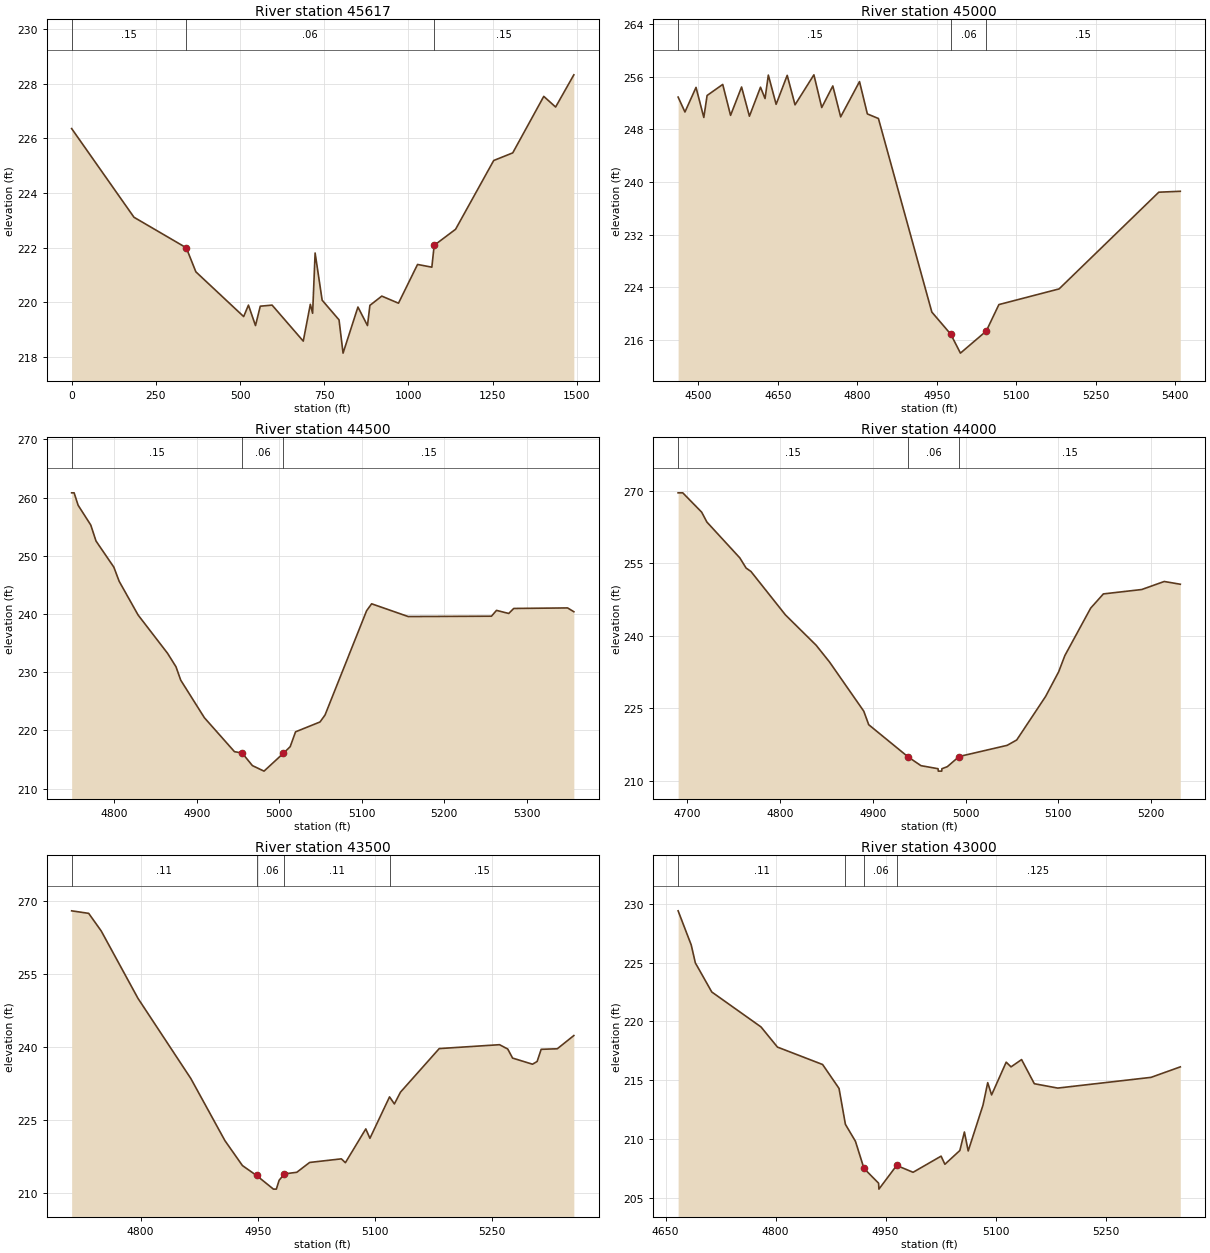
Type RM Length L Ch R = 1 ,45617   ,737,737,737
XS GIS Cut Line= 3
      3848287.87      10123672.3       3847687.6     10123129.03
      3847214.95     10122637.58
#Sta/Elev= 30
       0  226.36   185.1  223.11   340.5  221.99   368.9  221.11   510.9  219.47
   525.1  219.89     546  219.14   560.2  219.85   595.3  219.89   687.9  218.57
   708.9  219.92   715.7  219.59   723.1   221.8     744  220.07   794.1  219.35
   806.1  218.13   850.3  219.82   878.6  219.14   885.8  219.88   921.1  220.22
   970.7  219.96  1027.3  221.38  1069.8  221.28  1076.7  222.08  1140.3  222.67
  1253.5  225.19  1310.1  225.47  1402.2  227.54  1437.4  227.15  1491.5  228.33
#Mann= 3 , 0 , 0
       0     .15       0   340.5     .06       0  1076.7     .15       0
Bank Sta=340.5,1076.7
XS Rating Curve= 0 ,0
Exp/Cntr=0.3,0.1

Type RM Length L Ch R = 1 ,45000   ,500,500,500
BEGIN DESCRIPTION:
WEST FORK OF CRYSTAL CREEK 90.0
END DESCRIPTION:
XS GIS Cut Line= 3
      3848672.29     10123044.29      3848233.99      10122732.3
      3848100.67     10122344.69
#Sta/Elev= 30
    4462  252.92  4474.9  250.65  4495.8  254.39  4510.5  249.82  4516.7  253.16
  4546.2  254.84    4561  250.14  4581.8  254.45  4596.6  250.01  4617.5  254.42
  4626.1   252.7  4632.3  256.26    4647  251.82  4667.9  256.22  4682.7  251.74
  4718.3   256.3  4733.1  251.33    4754  254.61  4768.8  249.91  4804.4  255.27
  4819.2  250.36  4840.1  249.66  4940.9  220.24  4976.6  216.88  4994.9     214
  5043.6  217.35  5067.5  221.38  5181.1  223.76  5369.3  238.46  5409.9   238.6
#Mann= 3 , 0 , 0
    4462     .15       0  4976.6     .06       0  5043.6     .15       0
Bank Sta=4976.6,5043.6
XS Rating Curve= 0 ,0
Exp/Cntr=0.3,0.1

Type RM Length L Ch R = 1 ,44500   ,500,500,500
BEGIN DESCRIPTION:
WEST FORK OF CRYSTAL CREEK 89.0
END DESCRIPTION:
XS GIS Cut Line= 3
       3848698.1     10122420.72      3848478.68      10122297.8
       3848187.8     10122090.83
#Sta/Elev= 30
  4748.5  260.82  4751.5  260.82  4756.3   258.7  4771.7  255.28    4778  252.55
  4799.6  248.06  4806.1  245.62    4829  239.84  4864.7  233.26  4874.9  230.95
  4880.7  228.64  4909.3   222.2  4945.8  216.36  4955.1  216.13  4967.5  213.97
  4981.6  213.02  5005.1  216.09  5013.3  217.22  5019.8  219.77  5049.4  221.46
  5055.5  222.65  5105.9  240.57    5112  241.76  5156.3  239.57  5257.2  239.63
  5263.3  240.63  5278.1   240.1  5284.2  240.96  5349.4  241.05    5357   240.4
#Mann= 3 , 0 , 0
  4748.5     .15       0  4955.1     .06       0  5005.1     .15       0
Bank Sta=4955.1,5005.1
XS Rating Curve= 0 ,0
Exp/Cntr=0.3,0.1

Type RM Length L Ch R = 1 ,44000   ,500,500,500
BEGIN DESCRIPTION:
WEST FORK OF CRYSTAL CREEK 88.0
END DESCRIPTION:
XS GIS Cut Line= 3
      3849042.56     10121943.31      3848741.03     10121872.16
      3848517.85     10121811.07
#Sta/Elev= 30
  4690.2  269.56  4695.2  269.56  4715.6  265.56  4721.2  263.52  4756.7  256.11
  4763.5     254  4768.7   253.3  4805.9  244.31  4838.9  238.06  4853.3   234.6
  4890.3  224.41  4895.6  221.62    4938  214.97  4951.9  213.15  4970.3  212.52
  4970.6  212.02  4974.3  212.02  4974.5  212.52  4980.3  212.94    4993  215.04
  5044.8  217.35  5055.1  218.46  5086.2  227.45  5100.3  232.55    5107  235.92
  5134.8  245.72  5148.5  248.66  5189.9  249.57  5214.1  251.23  5231.4  250.66
#Mann= 3 , 0 , 0
  4690.2     .15       0    4938     .06       0    4993     .15       0
Bank Sta=4938,4993
XS Rating Curve= 0 ,0
Exp/Cntr=0.3,0.1

Type RM Length L Ch R = 1 ,43500   ,500,500,500
BEGIN DESCRIPTION:
WEST FORK OF CRYSTAL CREEK 87.0
END DESCRIPTION:
XS GIS Cut Line= 3
      3849267.85     10121561.07      3849003.39     10121446.52
      3848667.81     10121561.09
#Sta/Elev= 30
  4711.8  267.95  4733.6  267.43  4749.7   263.8  4796.7  249.97  4864.4  233.49
    4908  220.74  4930.4  215.62  4948.5  213.58  4970.1  210.78  4973.8  210.78
  4977.4  212.61  4984.2  213.91    5000  214.24  5016.4  216.26    5057     217
  5062.2  216.21  5088.3  223.15  5093.6  221.22  5118.7  229.73  5124.9  228.28
  5132.7   230.7  5182.3  239.65  5259.5  240.45    5270  239.56  5276.2   237.7
  5301.7  236.44  5307.6     237  5312.8   239.5  5333.4  239.61  5354.6  242.33
#Mann= 4 ,-1 , 0
  4711.8     .11       0  4948.5     .06       0  4984.2     .11       0
  5118.7     .15       0
Bank Sta=4948.5,4984.2
XS Rating Curve= 0 ,0
Exp/Cntr=0.3,0.1

Type RM Length L Ch R = 1 ,43000   ,500,500,500
BEGIN DESCRIPTION:
WEST FORK OF CRYSTAL CREEK 86.0
END DESCRIPTION:
XS GIS Cut Line= 3
      3849374.85     10121136.06      3849076.63     10120987.88
      3848742.18     10121097.63
#Sta/Elev= 30
    4667  229.39  4684.9  226.49  4690.5  224.97  4712.9   222.5  4780.1  219.53
  4802.5  217.82  4864.1  216.34  4886.5  214.31  4895.2  211.26  4908.9  209.82
  4920.5  207.52  4940.5  206.26  4940.9  205.76  4965.1  207.77  4987.5  207.19
  5025.7  208.56  5030.9  207.87  5051.3  209.04  5057.5  210.61  5062.7     209
  5082.9   212.9  5089.3   214.8  5094.6  213.76  5114.5  216.54  5121.1  216.14
  5135.5  216.76  5152.9  214.71  5184.8  214.34  5312.1  215.25    5352  216.14
#Mann= 4 ,-1 , 0
    4667     .11       0  4895.2    .125       0  4920.5     .06       0
  4965.1    .125       0
Bank Sta=4920.5,4965.1
XS Rating Curve= 0 ,0
Exp/Cntr=0.3,0.1

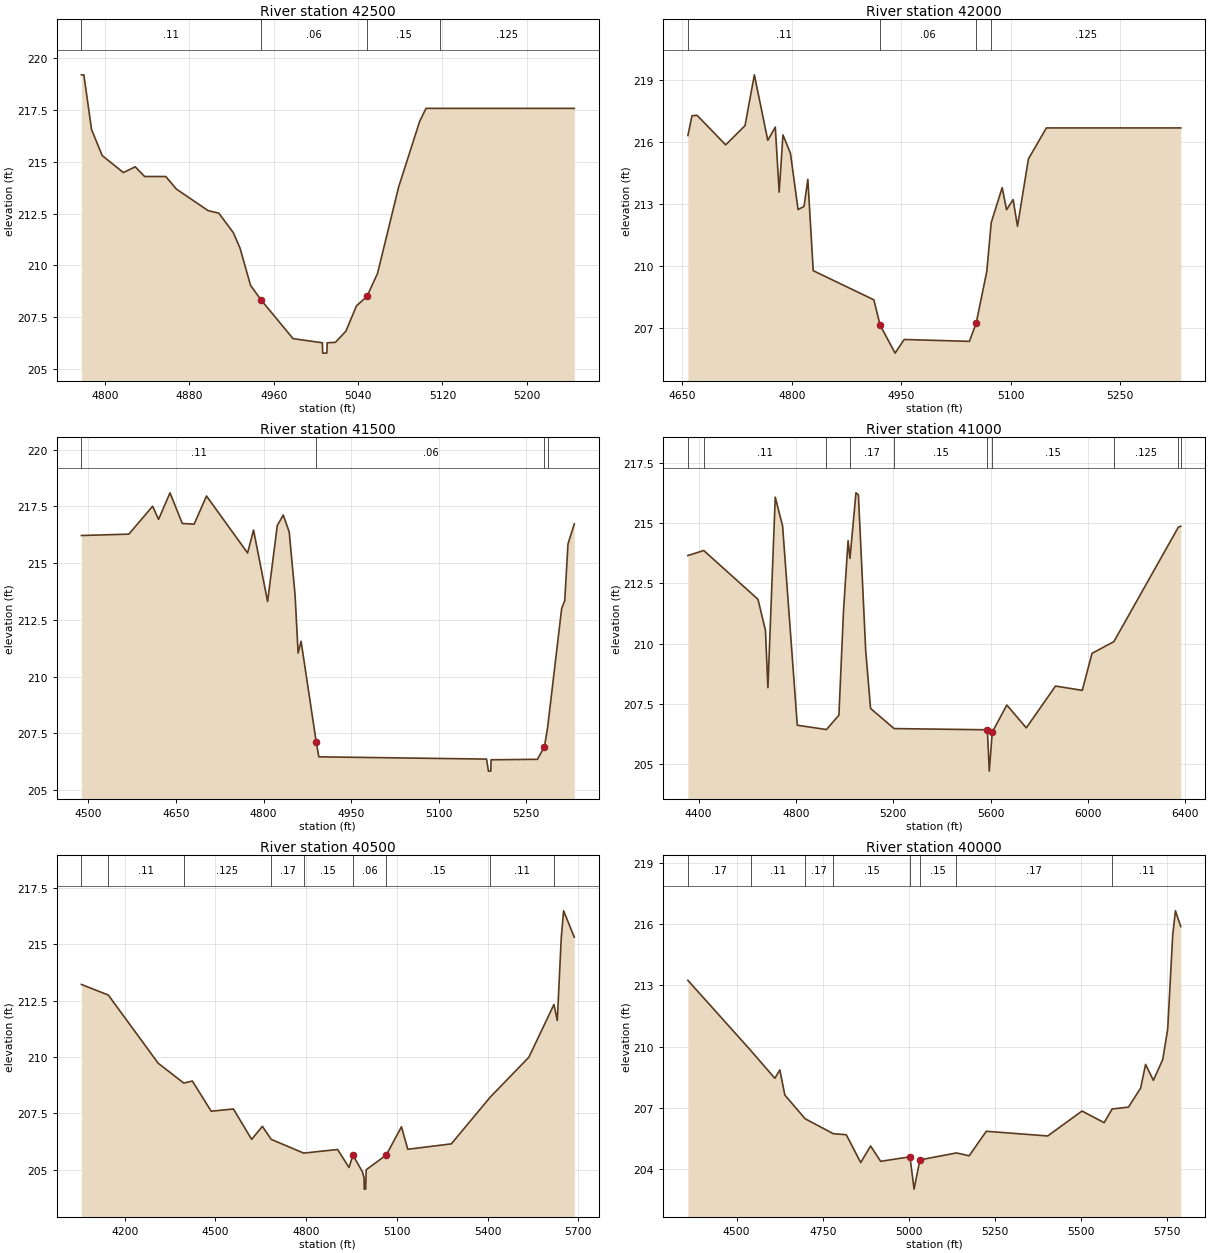
Type RM Length L Ch R = 1 ,42500   ,500,500,500
BEGIN DESCRIPTION:
WEST FORK OF CRYSTAL CREEK 85.0
END DESCRIPTION:
XS GIS Cut Line= 3
      3849487.92     10121120.63      3849511.22     10120899.46
      3849509.49     10120795.07
#Sta/Elev= 30
  4777.6   219.2  4779.9   219.2  4787.2  216.56  4797.3   215.3  4817.4  214.48
  4828.6  214.76  4837.5  214.29  4857.6  214.29  4867.7  213.68  4897.8  212.64
  4907.9  212.52  4921.6  211.58    4928  210.83    4938  209.03  4948.1  208.32
  4978.3  206.46  5006.1  206.26  5006.4  205.76  5010.3  205.76  5010.7  206.26
  5018.4  206.28  5028.4  206.82  5038.4  208.04  5048.4   208.5  5058.4  209.61
  5078.4  213.78  5098.4  216.96  5104.4  217.58  5117.6  217.58    5245  217.58
#Mann= 4 ,-1 , 0
  4777.6     .11       0  4948.1     .06       0  5048.4     .15       0
  5117.6    .125       0
Bank Sta=4948.1,5048.4
XS Rating Curve= 0 ,0
Exp/Cntr=0.3,0.1

Type RM Length L Ch R = 1 ,42000   ,500,500,500
BEGIN DESCRIPTION:
WEST FORK OF CRYSTAL CREEK 84.0
END DESCRIPTION:
XS GIS Cut Line= 3
      3850293.22     10120919.97       3849963.7     10120827.31
      3849837.62     10120742.05
#Sta/Elev= 30
  4657.7  216.32  4663.3  217.28  4670.3   217.3  4709.5  215.87    4736   216.8
  4748.8  219.26  4767.2  216.09  4777.5  216.73  4782.8  213.58    4788  216.35
  4798.3  215.46  4808.7  212.74  4816.9  212.89  4822.1   214.2  4829.5  209.78
  4912.6  208.37  4921.1207.1522  4941.7  205.79  4954.1  206.45  5043.6  206.36
  5052.9207.2477  5067.4  209.74  5073.5  212.11  5088.5   213.8  5094.5  212.73
  5103.5  213.22  5109.5  211.93  5124.5  215.19  5149.1  216.69  5333.3  216.69
#Mann= 4 ,-1 , 0
  4657.7     .11       0  4921.1     .06       0  5052.9     .11       0
  5073.5    .125       0
Bank Sta=4921.1,5052.9
XS Rating Curve= 0 ,0
Exp/Cntr=0.3,0.1

Type RM Length L Ch R = 1 ,41500   ,500,500,500
BEGIN DESCRIPTION:
WEST FORK OF CRYSTAL CREEK 83.0
END DESCRIPTION:
XS GIS Cut Line= 3
      3850657.72     10120465.09      3850154.53     10120369.96
      3849837.61      10120471.2
#Sta/Elev= 30
  4487.9  216.22  4569.2  216.28  4609.9  217.51  4620.1  216.93  4639.7   218.1
  4660.8  216.75  4681.1  216.72  4702.3  217.96  4772.7  215.45  4782.9  216.46
    4807  213.31  4823.6  216.66  4833.8  217.12    4844  216.38  4854.1  213.59
  4859.3  211.04  4864.4  211.56 4890.33 207.125  4894.8  206.47  5182.3  206.37
  5185.5  205.84  5189.6  205.84    5190  206.34  5269.5  206.36  5281.5  206.92
  5286.9  207.75    5311     213  5316.3  213.35  5321.9  215.85  5332.7  216.73
#Mann= 4 ,-1 , 0
  4487.9     .11       0 4890.33     .06       0  5281.5    .125       0
  5286.9     .17       0
Bank Sta=4890.33,5281.5
XS Rating Curve= 0 ,0
Exp/Cntr=0.3,0.1

Type RM Length L Ch R = 1 ,41000   ,500,500,500
BEGIN DESCRIPTION:
WEST FORK OF CRYSTAL CREEK 82.0
END DESCRIPTION:
XS GIS Cut Line= 3
      3850664.67     10119978.99      3850024.76     10119906.52
      3848643.04     10119870.14
#Sta/Elev= 30
    4356  213.66  4421.1  213.87  4644.1  211.84  4674.8  210.55  4684.9  208.16
  4715.1  216.09  4745.3  214.89  4805.7   206.6  4925.6  206.42  4976.8  207.02
  4995.9  211.39  5014.5  214.28  5022.2  213.54  5046.9  216.27  5056.9  216.19
  5086.9  209.71  5106.9   207.3  5203.8  206.46  5587.1  206.41    5595  204.69
  5607.1  206.31  5667.1  207.44  5747.2  206.49  5867.2  208.23  5977.2  208.05
  6017.3  209.59  6107.3  210.08  6372.2  214.84  6381.8  214.88  6382.2  214.88
#Mann= 10 ,-1 , 0
    4356     .17       0  4421.1     .11       0  4925.6    .125       0
  5022.2     .17       0  5203.8     .15       0  5587.1     .09       0
  5607.1     .15       0  6107.3    .125       0  6372.2     .15       0
  6381.8    .125       0
Bank Sta=5587.1,5607.1
XS Rating Curve= 0 ,0
Exp/Cntr=0.3,0.1

Type RM Length L Ch R = 1 ,40500   ,500,500,500
BEGIN DESCRIPTION:
WEST FORK OF CRYSTAL CREEK 81.0
END DESCRIPTION:
XS GIS Cut Line= 3
      3850675.14     10119954.69      3849825.29     10119544.87
      3849273.18     10119135.87
#Sta/Elev= 30
  4056.5  213.22  4145.4  212.75  4310.5  209.72  4395.1  208.84  4423.5  208.93
  4485.8  207.59  4559.2  207.69  4619.7  206.34  4655.2  206.92  4684.2  206.34
  4791.7  205.73    4904  205.89  4941.7  205.09  4954.7  205.64  4986.1   204.9
  4991.6  204.63    4992  204.13  4996.8  204.13  4998.6  204.99  5065.2  205.65
  5115.3   206.9  5136.2   205.9  5280.2  206.14  5409.2  208.22  5536.9  209.99
  5619.8  212.33  5630.8  211.62    5644   215.3  5651.7  216.49  5687.1  215.32
#Mann= 9 ,-1 , 0
  4056.5     .17       0  4145.4     .11       0  4395.1    .125       0
  4684.2     .17       0  4791.7     .15       0  4954.7     .06       0
  5065.2     .15       0  5409.2     .11       0  5619.8    .125       0
Bank Sta=4954.7,5065.2
XS Rating Curve= 0 ,0
Exp/Cntr=0.3,0.1

Type RM Length L Ch R = 1 ,40000   ,536,536,536
BEGIN DESCRIPTION:
WEST FORK OF CRYSTAL CREEK 80.0
END DESCRIPTION:
XS GIS Cut Line= 3
      3850695.96     10119937.34       3850303.1     10119430.46
      3849817.48     10118808.86
#Sta/Elev= 30
  4358.7  213.25  4541.1  209.82    4611  208.46  4625.5  208.87    4640  207.64
    4699  206.48  4780.6  205.75  4818.3   205.7  4860.1  204.34  4888.9  205.15
  4917.9   204.4    5003  204.62    5015  203.04  5031.9  204.47  5137.9  204.81
  5174.8  204.67  5224.6  205.87  5402.7  205.64  5502.2  206.86  5566.4  206.29
  5589.6  206.96    5637  207.05  5672.3  207.98  5686.7  209.14  5709.3  208.36
  5736.5  209.38  5750.9  210.87  5765.4  215.46  5773.3  216.65  5788.8  215.88
#Mann= 8 ,-1 , 0
  4358.7     .17       0  4541.1     .11       0    4699     .17       0
  4780.6     .15       0    5003     .09       0  5031.9     .15       0
  5137.9     .17       0  5589.6     .11       0
Bank Sta=5003,5031.9
XS Rating Curve= 0 ,0
Exp/Cntr=0.3,0.1

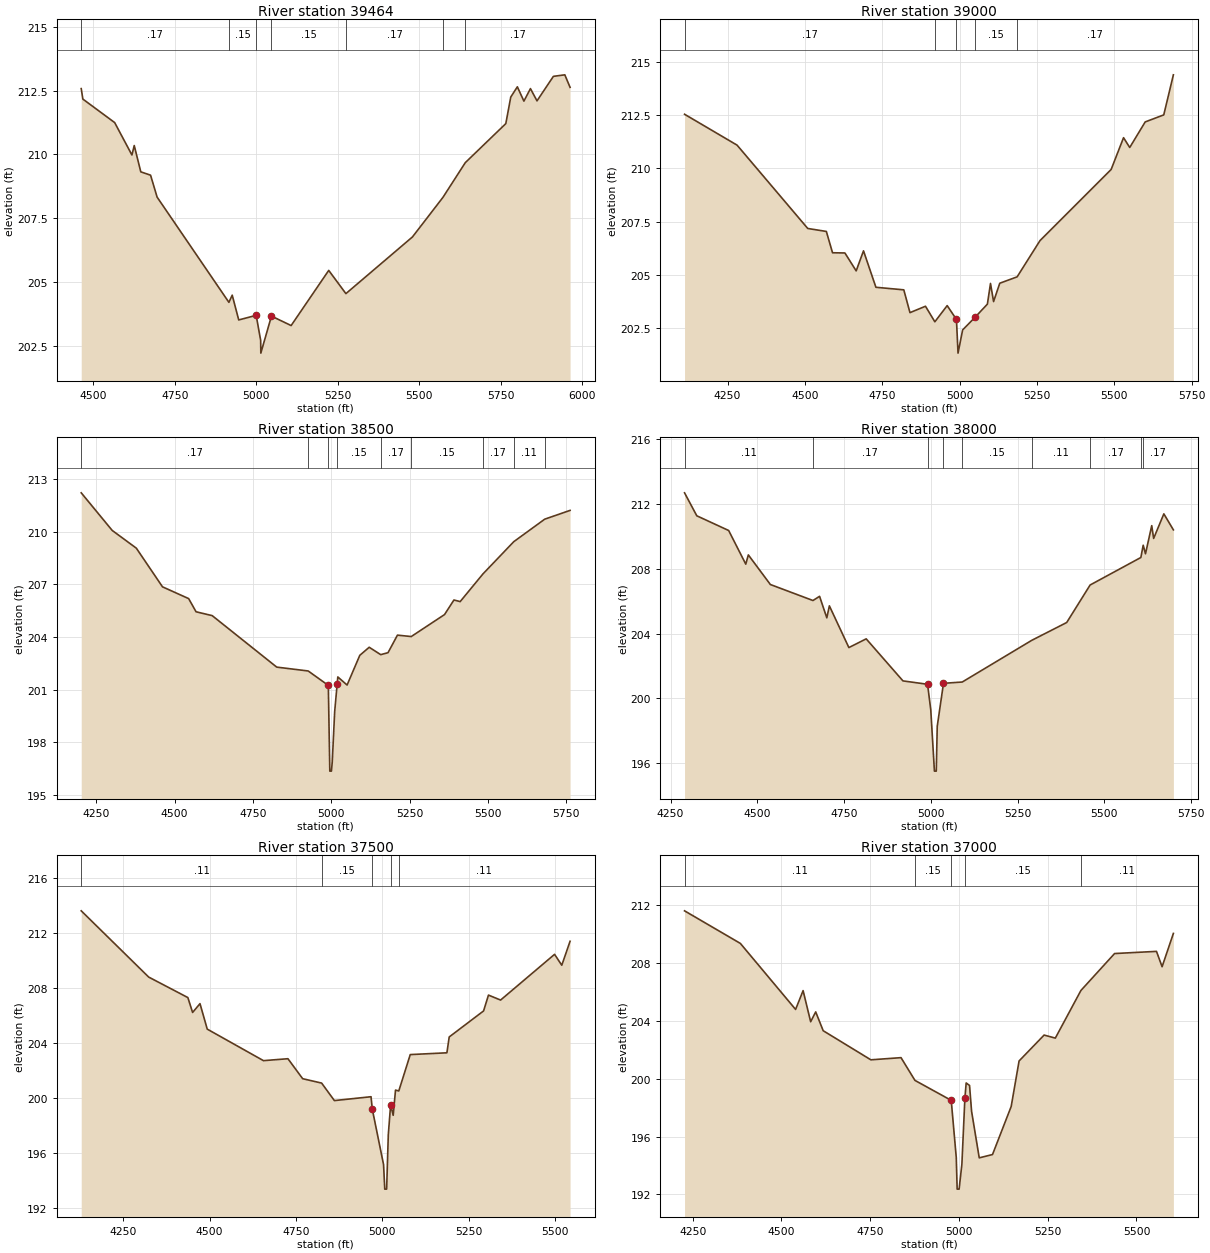
Type RM Length L Ch R = 1 ,39464   ,464,464,464
BEGIN DESCRIPTION:
WEST FORK OF CRYSTAL CREEK 79.0
END DESCRIPTION:
XS GIS Cut Line= 3
      3850873.03     10119923.44       3850837.4     10119387.73
      3850731.07     10118430.21
#Sta/Elev= 30
  4463.1  212.58  4468.1  212.17  4565.7  211.25  4618.7  209.98  4625.8  210.35
  4645.9  209.32  4675.9  209.19    4696  208.33  4916.3  204.21  4926.5  204.49
  4946.5  203.52    5000   203.7  5013.8  202.72  5014.3  202.22  5046.9  203.67
  5107.3   203.3  5222.7  205.46  5275.4  204.55  5479.6  206.77  5573.2  208.32
  5641.8  209.68  5766.2  211.21  5781.4  212.25  5801.6  212.65  5821.7  212.09
  5841.8  212.58  5861.9   212.1  5912.2  213.06  5947.3  213.12  5963.4  212.63
#Mann= 7 ,-1 , 0
  4463.1     .17       0  4916.3     .15       0    5000     .09       0
  5046.9     .15       0  5275.4     .17       0  5573.2     .15       0
  5641.8     .17       0
Bank Sta=5000,5046.9
XS Rating Curve= 0 ,0
Exp/Cntr=0.3,0.1

Type RM Length L Ch R = 1 ,39000   ,500,500,500
BEGIN DESCRIPTION:
WEST FORK OF CRYSTAL CREEK 78.0
END DESCRIPTION:
XS GIS Cut Line= 3
      3851194.29     10120098.72      3851239.95     10119210.99
      3851236.83       10118520.
#Sta/Elev= 30
  4111.1  212.54  4280.9  211.09  4509.3  207.18  4569.4  207.04  4589.4  206.04
  4629.4  206.03  4665.8  205.19  4689.5  206.13  4729.6  204.42  4819.7   204.3
  4839.7  203.23  4889.8  203.53  4920.1   202.8  4959.9  203.56  4989.9  202.91
    4995  201.33  5009.9  202.42  5049.9  203.01  5089.9  203.63  5099.9   204.6
  5109.9  203.75  5129.9  204.61    5186  204.91  5259.9  206.61  5489.9  209.95
  5529.9  211.44  5549.9  210.98  5599.9  212.18  5659.9  212.51    5691  214.39
#Mann= 5 ,-1 , 0
  4111.1     .17       0  4920.1     .15       0  4989.9     .09       0
  5049.9     .15       0    5186     .17       0
Bank Sta=4989.9,5049.9
XS Rating Curve= 0 ,0
Exp/Cntr=0.3,0.1

Type RM Length L Ch R = 1 ,38500   ,500,500,500
BEGIN DESCRIPTION:
WEST FORK OF CRYSTAL CREEK 77.0
END DESCRIPTION:
XS GIS Cut Line= 3
       3851884.4     10120127.11      3851695.59     10119351.77
      3851657.52     10118590.93
#Sta/Elev= 30
    4202  212.21  4300.8  210.07  4377.8  209.06  4461.3  206.86  4544.7  206.19
  4568.4  205.44  4619.9  205.22  4825.8  202.29  4926.2  202.07  4990.4  201.25
  4995.2  196.37  5000.3  196.37  5002.9  196.87  5010.7  199.76 5018.63201.3221
  5020.7  201.73  5050.3  201.27  5090.8  202.96  5120.9  203.42  5157.5     203
  5180.9  203.11    5211  204.11    5255  204.03  5361.2  205.28  5391.2  206.11
  5411.2  206.02  5483.6  207.59  5582.2  209.43  5680.9  210.71  5761.8  211.21
#Mann= 9 ,-1 , 0
    4202     .17       0  4926.2     .15       0  4990.4     .09       0
 5018.63     .15       0  5157.5     .17       0    5255     .15       0
  5483.6     .17       0  5582.2     .11       0  5680.9     .17       0
Bank Sta=4990.4,5018.63
XS Rating Curve= 0 ,0
Exp/Cntr=0.3,0.1

Type RM Length L Ch R = 1 ,38000   ,500,500,500
BEGIN DESCRIPTION:
WEST FORK OF CRYSTAL CREEK 76.0
END DESCRIPTION:
XS GIS Cut Line= 3
      3852650.15     10119758.42      3852168.66      10119236.9
      3851889.23     10118595.86
#Sta/Elev= 30
  4290.2   212.7  4325.5  211.28  4417.4  210.37  4466.7  208.29  4474.1  208.86
  4537.6  207.03  4660.4  206.04  4679.4   206.3  4700.3  204.97  4707.7  205.71
  4763.9  203.13  4813.8  203.67  4919.8  201.07  4990.7  200.86    5000  199.27
  5010.5  195.49  5015.8  195.49  5018.6  198.26  5036.6  200.92  5090.7     201
  5291.2  203.58  5391.8  204.68  5459.3     207  5605.5   208.7  5612.3  209.46
  5618.9  208.93  5636.9  210.67  5642.4  209.88  5671.8   211.4  5699.3  210.41
#Mann= 9 ,-1 , 0
  4290.2     .11       0  4660.4     .17       0  4990.7     .09       0
  5036.6     .17       0  5090.7     .15       0  5291.2     .11       0
  5459.3     .17       0  5605.5     .11       0  5612.3     .17       0
Bank Sta=4990.7,5036.6
XS Rating Curve= 0 ,0
Exp/Cntr=0.3,0.1

Type RM Length L Ch R = 1 ,37500   ,500,500,500
BEGIN DESCRIPTION:
WEST FORK OF CRYSTAL CREEK 75.0
END DESCRIPTION:
XS GIS Cut Line= 3
       3853066.1     10119408.63       3852422.1     10118821.16
      3852016.73     10118458.53
#Sta/Elev= 30
  4128.3  213.59  4323.6  208.78  4437.1  207.29  4450.8  206.21  4472.2  206.85
  4493.2     205    4656  202.71  4726.9  202.85  4769.5   201.4  4824.5  201.08
  4861.4  199.81  4967.5  200.09 4971.18199.1849  5003.8  195.16  5007.3  193.38
  5012.7  193.38  5017.5  197.32  5024.2  199.49  5031.7  198.74  5038.4  200.57
  5047.9  200.51  5081.1  203.15  5187.2  203.28  5193.9  204.43  5293.4  206.32
  5307.6  207.47  5342.7  207.11    5499  210.43  5519.9  209.64  5543.9  211.38
#Mann= 5 ,-1 , 0
  4128.3     .11       0  4824.5     .15       0 4971.18     .09       0
  5024.2     .15       0  5047.9     .11       0
Bank Sta=4971.18,5024.2
XS Rating Curve= 0 ,0
Exp/Cntr=0.3,0.1

Type RM Length L Ch R = 1 ,37000   ,500,500,500
BEGIN DESCRIPTION:
WEST FORK OF CRYSTAL CREEK 74.0
END DESCRIPTION:
XS GIS Cut Line= 3
       3853363.9     10119087.22      3852825.56     10118532.77
      3852301.57     10118232.35
#Sta/Elev= 30
  4227.2  211.59  4384.4  209.34    4540  204.78  4561.1  206.08  4582.4  203.93
  4596.6  204.61  4617.7  203.31    4752   201.3  4836.9  201.45  4876.1  199.88
  4978.3   198.5  4992.5  194.55    4995  192.37  5000.5  192.37  5008.3  194.08
 5016.75198.6397  5020.4   199.7  5029.9  199.53  5035.6  197.75  5057.2  194.53
  5094.6  194.76  5147.2  198.08  5169.4  201.22  5239.9  203.01  5271.5   202.8
  5343.6  206.09  5438.4  208.64  5556.4  208.79  5572.2  207.73    5604  210.03
#Mann= 5 ,-1 , 0
  4227.2     .11       0  4876.1     .15       0  4978.3     .09       0
 5016.75     .15       0  5343.6     .11       0
Bank Sta=4978.3,5016.75
XS Rating Curve= 0 ,0
Exp/Cntr=0.3,0.1

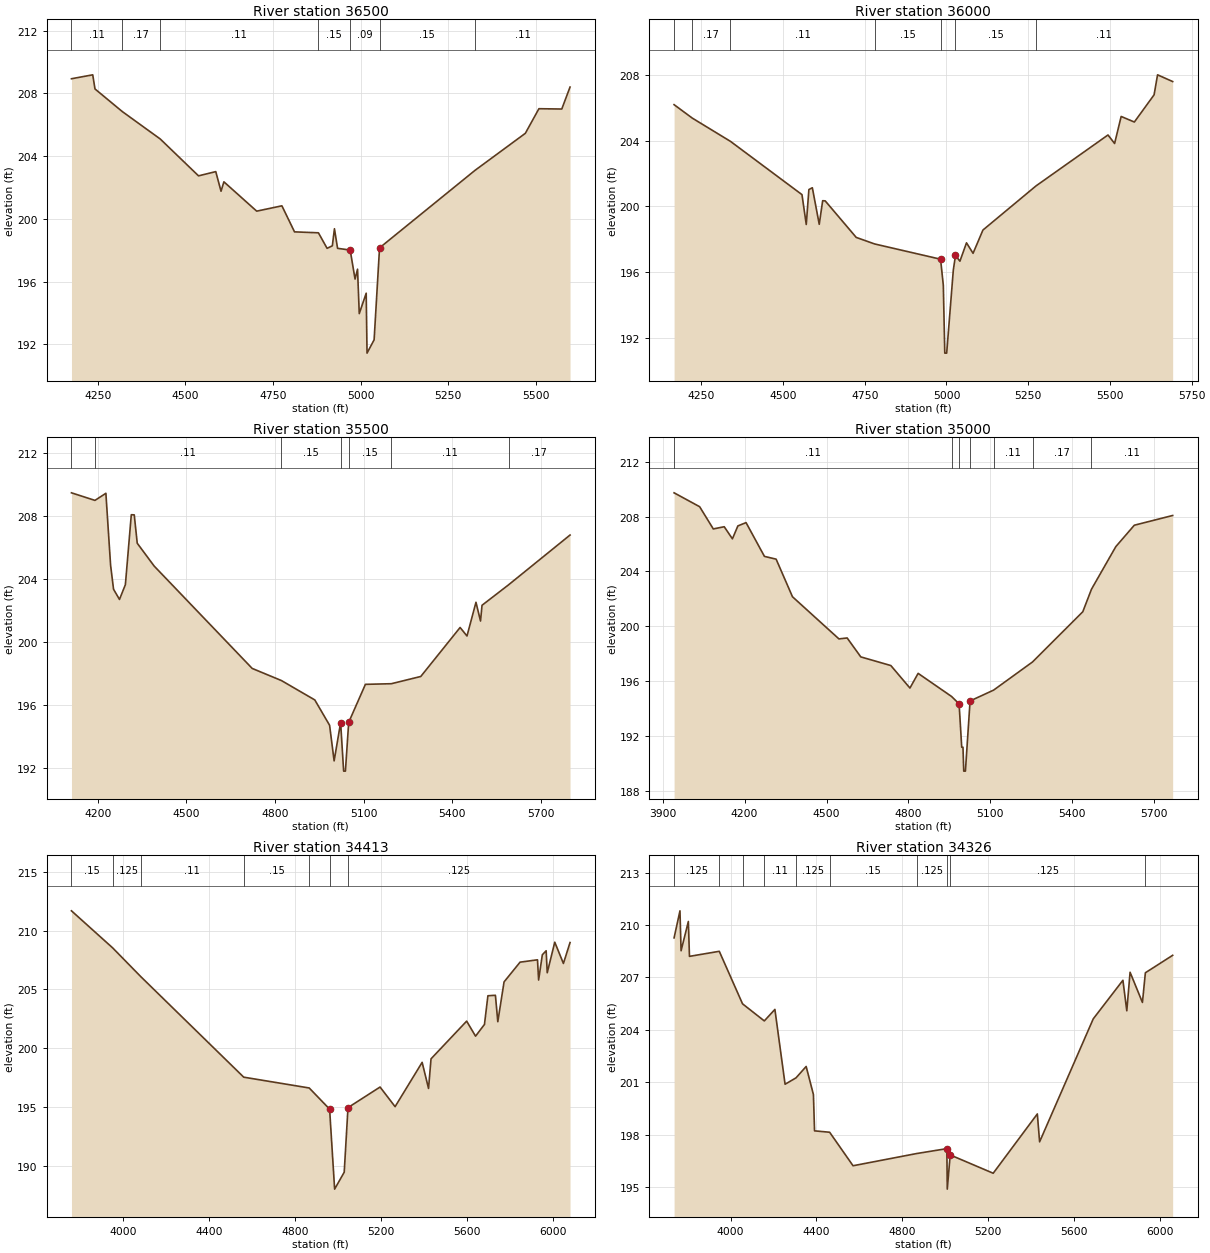
Type RM Length L Ch R = 1 ,36500   ,500,500,500
BEGIN DESCRIPTION:
WEST FORK OF CRYSTAL CREEK 73.0
END DESCRIPTION:
XS GIS Cut Line= 3
      3853818.11     10118633.85      3853134.72     10118171.68
      3852562.89     10117998.43
#Sta/Elev= 30
    4175  208.94  4235.7  209.19  4242.1  208.29  4319.9  206.85  4428.3   205.1
  4537.5  202.75  4586.7  203.02  4601.7  201.77  4609.9  202.37  4703.5   200.5
  4775.4  200.84  4811.4  199.18  4879.6  199.12  4904.3  198.13  4919.3  198.29
  4925.3  199.38  4934.2  198.13  4970.2  198.02  4984.1  196.17  4991.2   196.8
  4996.1  193.97  5015.9  195.27  5018.3  191.45  5038.5   192.3    5054  198.16
  5326.3   203.1  5469.9  205.46  5508.7  207.03  5573.9  207.01  5597.5  208.41
#Mann= 7 ,-1 , 0
    4175     .11       0  4319.9     .17       0  4428.3     .11       0
  4879.6     .15       0  4970.2     .09       0    5054     .15       0
  5326.3     .11       0
Bank Sta=4970.2,5054
XS Rating Curve= 0 ,0
Exp/Cntr=0.3,0.1

Type RM Length L Ch R = 1 ,36000   ,500,500,500
BEGIN DESCRIPTION:
WEST FORK OF CRYSTAL CREEK 72.0
END DESCRIPTION:
XS GIS Cut Line= 3
      3854088.96     10117993.23      3853298.74     10117729.41
      3852611.38     10117650.28
#Sta/Elev= 30
  4166.9  206.21  4222.5  205.39  4339.4  203.97  4558.1  200.72  4571.2   198.9
  4579.2  201.03  4589.8  201.14  4610.9  198.91  4621.4  200.35  4629.1  200.34
    4724  198.11  4780.5  197.71    4982  196.78  4990.4  195.19  4994.9  191.05
  5000.7  191.05    5021  196.12  5027.6  197.01  5041.2  196.66  5061.3  197.78
  5081.4  197.14  5111.6  198.56  5273.8  201.25  5494.1  204.36  5514.3  203.84
  5534.4  205.49  5574.7  205.15  5635.1  206.81  5645.7  208.03  5691.9  207.62
#Mann= 7 ,-1 , 0
  4166.9     .11       0  4222.5     .17       0  4339.4     .11       0
  4780.5     .15       0    4982     .09       0  5027.6     .15       0
  5273.8     .11       0
Bank Sta=4982,5027.6
XS Rating Curve= 0 ,0
Exp/Cntr=0.3,0.1

Type RM Length L Ch R = 1 ,35500   ,500,500,500
BEGIN DESCRIPTION:
WEST FORK OF CRYSTAL CREEK 71.0
END DESCRIPTION:
XS GIS Cut Line= 3
      3854240.01     10117363.02      3853352.42     10117309.61
      3852562.95     10117191.15
#Sta/Elev= 30
  4110.8   209.5  4190.3  209.02  4227.3  209.47  4243.2  204.91  4253.2  203.38
  4273.3  202.73  4293.3  203.67  4313.3  208.11  4323.3   208.1  4333.4   206.3
  4390.7  204.85  4722.5  198.35  4821.5  197.58  4934.4  196.35  4984.5  194.74
  4999.8  192.48  5021.8  194.91    5032  191.83    5038  191.83  5049.1 194.926
  5105.7  197.34  5193.5  197.38  5293.1  197.84  5426.2  200.95  5449.5  200.41
  5479.9  202.55  5495.3  201.36  5500.4  202.36  5590.3  203.66  5798.3  206.82
#Mann= 7 ,-1 , 0
  4110.8    .125       0  4190.3     .11       0  4821.5     .15       0
  5021.8     .09       0  5049.1     .15       0  5193.5     .11       0
  5590.3     .17       0
Bank Sta=5021.8,5049.1
XS Rating Curve= 0 ,0
Exp/Cntr=0.3,0.1

Type RM Length L Ch R = 1 ,35000   ,587,587,587
BEGIN DESCRIPTION:
WEST FORK OF CRYSTAL CREEK 70.0
END DESCRIPTION:
XS GIS Cut Line= 3
      3854291.43     10116824.34      3853233.69     10116861.61
      3852471.03      10116769.5
#Sta/Elev= 30
  3941.6  209.73  4035.2  208.72  4085.3   207.1  4125.3  207.26  4155.3  206.38
  4175.3  207.32  4205.3  207.56  4272.6   205.1  4315.4   204.9  4375.4  202.16
  4545.6  199.09  4575.6  199.16  4625.6  197.78  4735.7  197.15  4805.7  195.51
  4835.7  196.58    4958   194.9  4985.8  194.36  4995.4   191.2    5000   191.2
  5002.8  189.46  5008.9  189.46    5026  194.57  5112.2  195.36  5254.7  197.41
    5439  201.07  5470.8  202.71  5559.9  205.81  5627.7  207.37  5768.2  208.08
#Mann= 7 ,-1 , 0
  3941.6     .11       0    4958     .15       0  4985.8     .09       0
    5026     .15       0  5112.2     .11       0  5254.7     .17       0
  5470.8     .11       0
Bank Sta=4985.8,5026
XS Rating Curve= 0 ,0
Exp/Cntr=0.3,0.1

Type RM Length L Ch R = 1 ,34413   ,87,87,87
BEGIN DESCRIPTION:
WEST FORK OF CRYSTAL CREEK 69.0
END DESCRIPTION:
XS GIS Cut Line= 3
      3854457.38     10116634.22       3853264.2     10116294.84
      3852223.38     10116018.06
#Sta/Elev= 30
  3759.5  211.68  3951.3  208.52  4081.1  206.09  4560.2  197.52  4864.6   196.6
  4959.4   194.8  4982.7  187.99  5027.3  189.43 5044.86194.9281  5193.9  196.68
  5263.8  195.01  5389.5  198.78  5419.3  196.56  5430.8  199.08  5596.4  202.29
  5637.8  201.01  5679.2  202.01  5695.2  204.45  5730.1  204.49  5741.2  202.24
  5770.3  205.63  5844.7  207.31  5925.7  207.51  5930.9  205.79  5948.2  207.94
  5965.9  208.28    5971  206.41    6006  209.01  6046.2   207.2    6077  208.98
#Mann= 7 ,-1 , 0
  3759.5     .15       0  3951.3    .125       0  4081.1     .11       0
  4560.2     .15       0  4864.6    .125       0  4959.4     .09       0
 5044.86    .125       0
Bank Sta=4959.4,5044.86
XS Rating Curve= 0 ,0
Exp/Cntr=0.3,0.1

Type RM Length L Ch R = 1 ,34326   ,826,826,826
BEGIN DESCRIPTION:
WEST FORK OF CRYSTAL CREEK 68.0
END DESCRIPTION:
XS GIS Cut Line= 3
      3854485.48     10116554.66      3853270.47     10116208.34
      3852252.64     10115910.19
#Sta/Elev= 30
  3736.6  209.27    3764  210.82  3769.2  208.53  3803.1  210.21  3808.3  208.21
  3947.3   208.5  4055.7  205.49  4157.2  204.51  4206.5  205.17    4254  200.88
  4305.2  201.25  4352.2   201.9  4386.1  200.29  4391.3  198.21  4461.7  198.13
  4570.8  196.21  4867.6  196.91    5008  197.19    5010  194.87  5023.6  196.83
  5224.1  195.78  5429.8  199.18  5440.4  197.58  5690.5  204.63  5828.7  206.84
  5846.8  205.09  5862.1   207.3  5919.7  205.57  5933.4  207.27  6060.6  208.27
#Mann= 10 ,-1 , 0
  3736.6    .125       0  3947.3     .15       0  4055.7    .125       0
  4157.2     .11       0  4305.2    .125       0  4461.7     .15       0
  4867.6    .125       0    5008     .09       0  5023.6    .125       0
  5933.4     .15       0
Bank Sta=5008,5023.6
XS Rating Curve= 0 ,0
Exp/Cntr=0.3,0.1

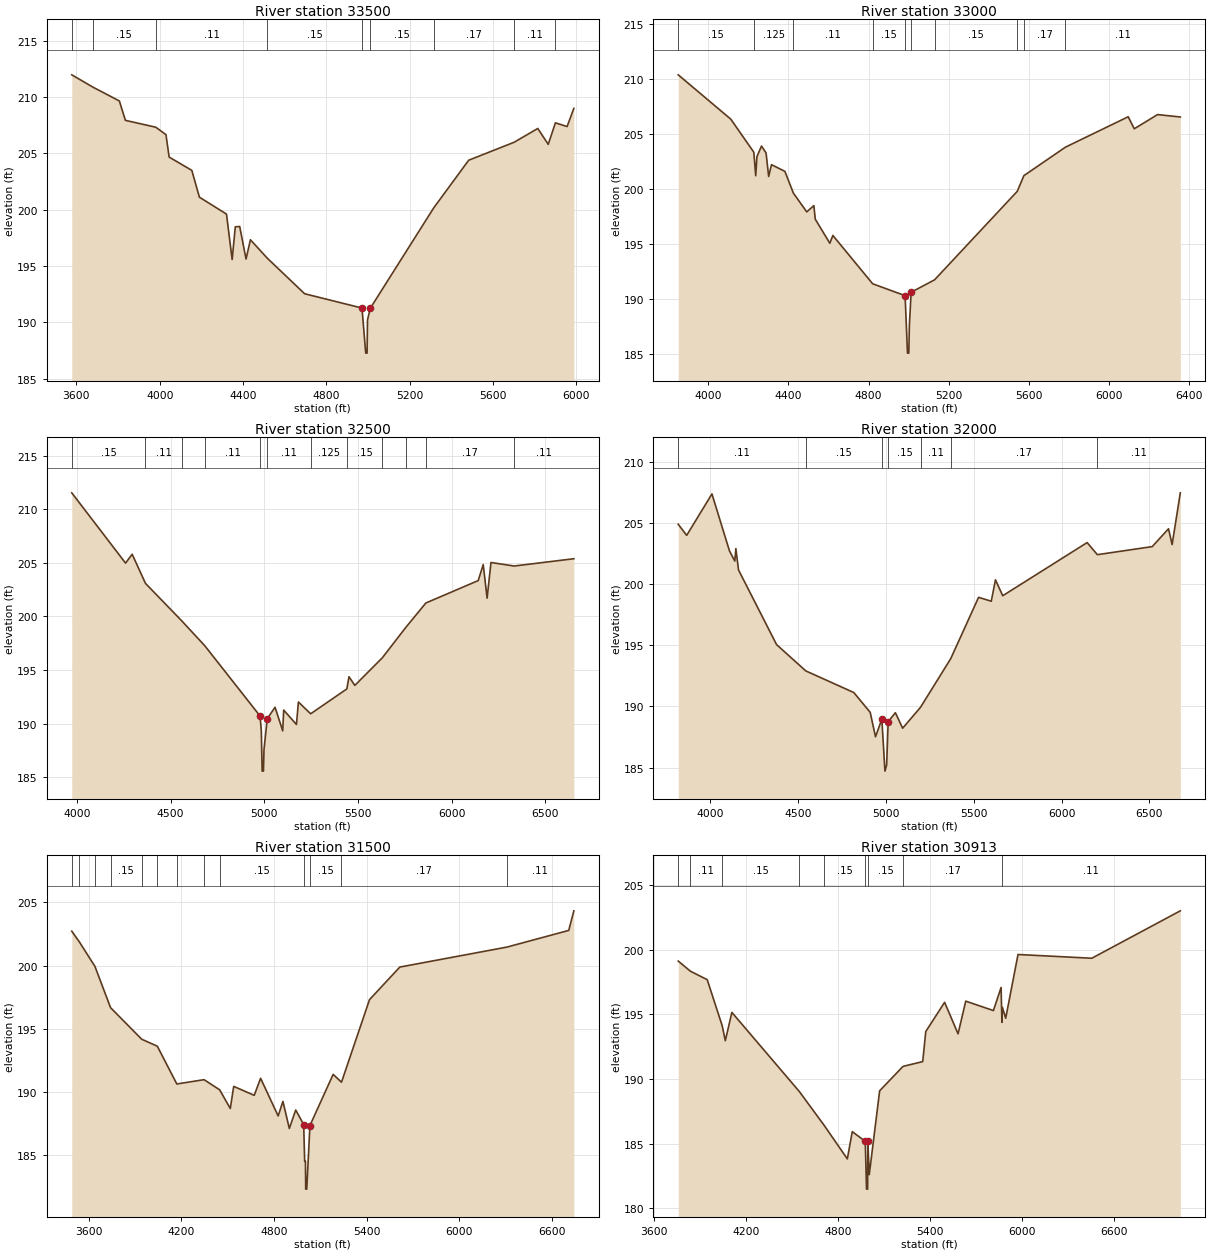
Type RM Length L Ch R = 1 ,33500   ,500,500,500
BEGIN DESCRIPTION:
WEST FORK OF CRYSTAL CREEK 67.0
END DESCRIPTION:
XS GIS Cut Line= 3
      3854534.37     10116250.01      3853338.58      10115480.3
      3852355.58     10115381.97
#Sta/Elev= 30
  3577.9  211.96  3679.3  210.87  3806.3  209.64  3835.4  207.92  3981.3  207.31
  4030.1  206.65  4045.3  204.66  4154.2  203.48  4190.6   201.1  4320.6   199.6
  4347.7  195.57  4362.9  198.47    4384   198.5  4414.4  195.61  4435.5  197.32
  4516.8  195.68  4695.7  192.53    4971  191.26  4988.9  187.26  4995.4  187.26
  4997.5  190.21  5010.8  191.24  5315.3  200.15  5483.1  204.38  5701.9  205.98
  5814.8   207.2    5865  205.79  5899.4   207.7  5955.5  207.37  5987.9  208.98
#Mann= 9 ,-1 , 0
  3577.9    .125       0  3679.3     .15       0  3981.3     .11       0
  4516.8     .15       0    4971     .09       0  5010.8     .15       0
  5315.3     .17       0  5701.9     .11       0  5899.4     .15       0
Bank Sta=4971,5010.8
XS Rating Curve= 0 ,0
Exp/Cntr=0.3,0.1

Type RM Length L Ch R = 1 ,33000   ,500,500,500
BEGIN DESCRIPTION:
WEST FORK OF CRYSTAL CREEK 66.0
END DESCRIPTION:
XS GIS Cut Line= 3
      3854657.86      10115784.8      3853689.47     10115165.47
       3852418.3     10114696.27
#Sta/Elev= 30
  3850.5  210.38  4112.8  206.35  4227.6  203.35  4237.1  201.21    4243  202.95
    4266  203.91  4288.7  203.28  4301.6  201.15  4315.8  202.22  4382.6  201.61
  4424.8  199.64  4491.5  197.93  4527.1   198.5    4534  197.27  4606.7  195.08
  4621.9  195.79  4820.4   191.4  4982.2  190.32  4994.1   185.1  5000.7   185.1
  5003.5  187.64  5012.4  190.63  5129.3  191.76  5541.8   199.8  5574.6  201.22
  5782.1  203.81    6095  206.57  6125.4  205.48  6241.8  206.77    6355  206.55
#Mann= 10 ,-1 , 0
  3850.5     .15       0  4227.6    .125       0  4424.8     .11       0
  4820.4     .15       0  4982.2     .09       0  5012.4     .11       0
  5129.3     .15       0  5541.8     .11       0  5574.6     .17       0
  5782.1     .11       0
Bank Sta=4982.2,5012.4
XS Rating Curve= 0 ,0
Exp/Cntr=0.3,0.1

Type RM Length L Ch R = 1 ,32500   ,500,500,500
BEGIN DESCRIPTION:
WEST FORK OF CRYSTAL CREEK 65.0
END DESCRIPTION:
XS GIS Cut Line= 3
      3854876.64     10115586.91      3854082.81     10114933.75
      3852492.04     10114488.16
#Sta/Elev= 30
    3972  211.54  4259.2  204.98  4294.4  205.81  4365.5  203.09  4558.7   199.6
  4682.6  197.26  4977.3  190.71  4983.8   189.3  4988.3  185.57    4995  185.57
  4998.1  187.58  5015.5  190.47  5057.1  191.53    5098  189.33  5103.2  191.27
  5171.3  189.92  5181.8  192.02  5247.2  190.92  5440.3  193.24  5451.7  194.38
  5482.9  193.57  5629.9  196.15  5754.1  198.96  5862.1  201.26  6141.5  203.35
  6168.3  204.84    6189  201.71  6209.7  205.04  6333.3  204.71    6652  205.39
#Mann= 12 ,-1 , 0
    3972     .15       0  4365.5     .11       0  4558.7    .125       0
  4682.6     .11       0  4977.3     .09       0  5015.5     .11       0
  5247.2    .125       0  5440.3     .15       0  5629.9    .125       0
  5754.1     .11       0  5862.1     .17       0  6333.3     .11       0
Bank Sta=4977.3,5015.5
XS Rating Curve= 0 ,0
Exp/Cntr=0.3,0.1

Type RM Length L Ch R = 1 ,32000   ,500,500,500
BEGIN DESCRIPTION:
WEST FORK OF CRYSTAL CREEK 64.0
END DESCRIPTION:
XS GIS Cut Line= 3
      3855138.26     10115165.69      3854149.78     10114515.23
      3852522.66     10114112.98
#Sta/Elev= 30
  3816.7  204.91  3864.8     204  4008.7  207.39  4108.8  202.72  4138.9   201.9
  4144.9  202.92    4160  201.17  4376.9  195.06  4543.2  192.91  4816.7  191.14
    4910  189.52  4940.2  187.52  4976.3  188.96    4994  184.71  5003.6  185.21
  5012.3  188.75  5053.5  189.49  5094.7  188.22  5196.9  189.94  5368.5  193.91
  5527.3  198.93  5599.4  198.61  5623.4  200.36  5664.8  199.06  6145.4  203.41
  6203.8  202.42  6516.2  203.08  6608.9  204.54  6629.5  203.25  6676.1  207.48
#Mann= 7 ,-1 , 0
  3816.7     .11       0  4543.2     .15       0  4976.3     .09       0
  5012.3     .15       0  5196.9     .11       0  5368.5     .17       0
  6203.8     .11       0
Bank Sta=4976.3,5012.3
XS Rating Curve= 0 ,0
Exp/Cntr=0.3,0.1

Type RM Length L Ch R = 1 ,31500   ,587,587,587
BEGIN DESCRIPTION:
WEST FORK OF CRYSTAL CREEK 63.0
END DESCRIPTION:
XS GIS Cut Line= 3
      3855781.33     10114503.91      3854320.38     10114117.05
      3852584.97     10113946.27
#Sta/Elev= 30
  3488.7  202.73    3538  201.88  3639.1  199.94  3740.1  196.68  3942.2  194.18
  4043.3  193.63  4169.8  190.64  4346.4  190.98  4447.4  190.18  4516.4   188.7
  4538.7  190.45  4671.6  189.74    4713  191.09  4826.8  188.11  4857.8  189.26
  4899.2  187.12  4940.6  188.58  4992.3  187.43  4998.7  184.52  5003.8  184.52
  5005.3  182.32  5012.2  182.32  5032.7  187.35  5183.4   191.4  5237.4  190.78
    5419  197.31  5615.5  199.89  6309.6  201.47  6710.8  202.79  6743.8  204.34
#Mann= 13 ,-1 , 0
  3488.7    .125       0    3538     .15       0  3639.1    .125       0
  3740.1     .15       0  3942.2    .125       0  4043.3     .15       0
  4169.8    .125       0  4346.4     .11       0  4447.4     .15       0
  4992.3     .09       0  5032.7     .15       0  5237.4     .17       0
  6309.6     .11       0
Bank Sta=4992.3,5032.7
XS Rating Curve= 0 ,0
Exp/Cntr=0.3,0.1

Type RM Length L Ch R = 1 ,30913   ,161,161,161
BEGIN DESCRIPTION:
WEST FORK OF CRYSTAL CREEK 62.0
END DESCRIPTION:
XS GIS Cut Line= 3
      3855856.15     10113565.96      3854618.24     10113686.86
      3852592.09     10113848.75
#Sta/Elev= 30
  3756.2  199.12  3835.3  198.34  3945.4  197.68  4043.3  194.11  4063.4  192.96
  4106.2  195.15  4546.8  189.02  4708.8   186.4  4859.7  183.81  4891.9  185.92
 4976.67185.1702    4985  181.47  4992.2  181.47  4993.6   185.2  5002.7  182.59
  5070.6  189.08  5223.1  190.97  5351.5  191.34  5371.7  193.67  5494.6  195.93
  5582.2  193.49  5632.4  196.02    5813  195.29  5863.1  197.08  5868.5  194.38
  5871.8  195.53  5893.2   194.7  5973.5  199.63    6455  199.34  7032.6  203.01
#Mann= 9 ,-1 , 0
  3756.2    .125       0  3835.3     .11       0  4043.3     .15       0
  4546.8     .11       0  4708.8     .15       0 4976.67     .09       0
  4993.6     .15       0  5223.1     .17       0  5871.8     .11       0
Bank Sta=4976.67,4993.6
XS Rating Curve= 0 ,0
Exp/Cntr=0.3,0.1