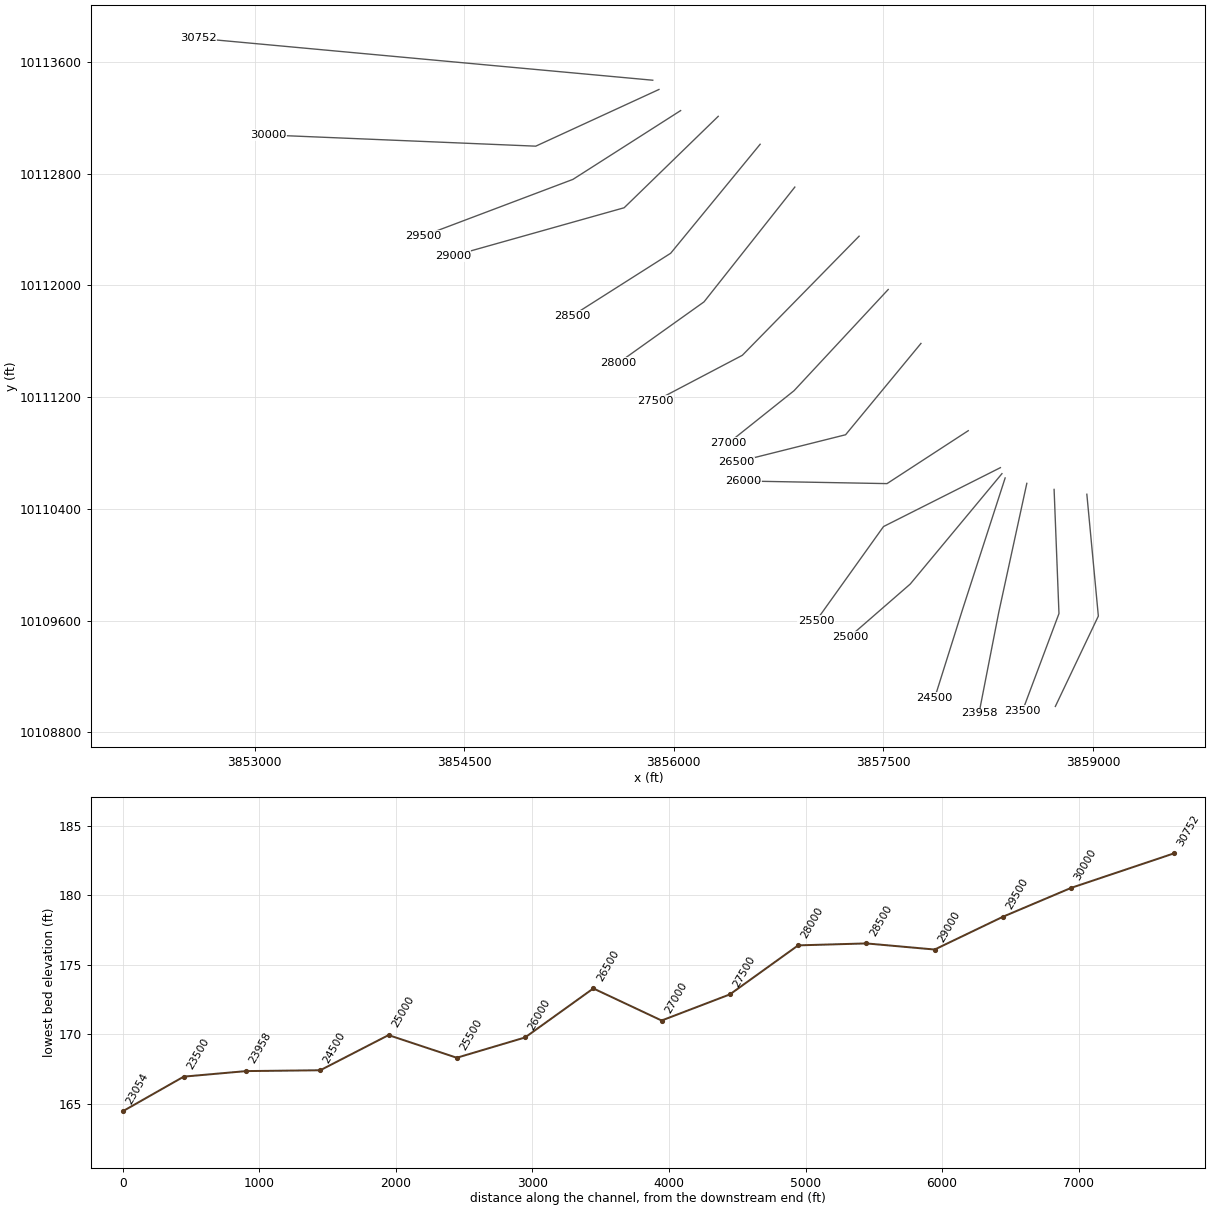
HEC-RAS study WEST FORK OF CRYSTAL CREEK.prj: WEST FORK OF CRYSTAL CREEK Base Level Engineering

--- WEST FORK OF CRYSTAL CREEK.g01 (geometry) --- (continued)

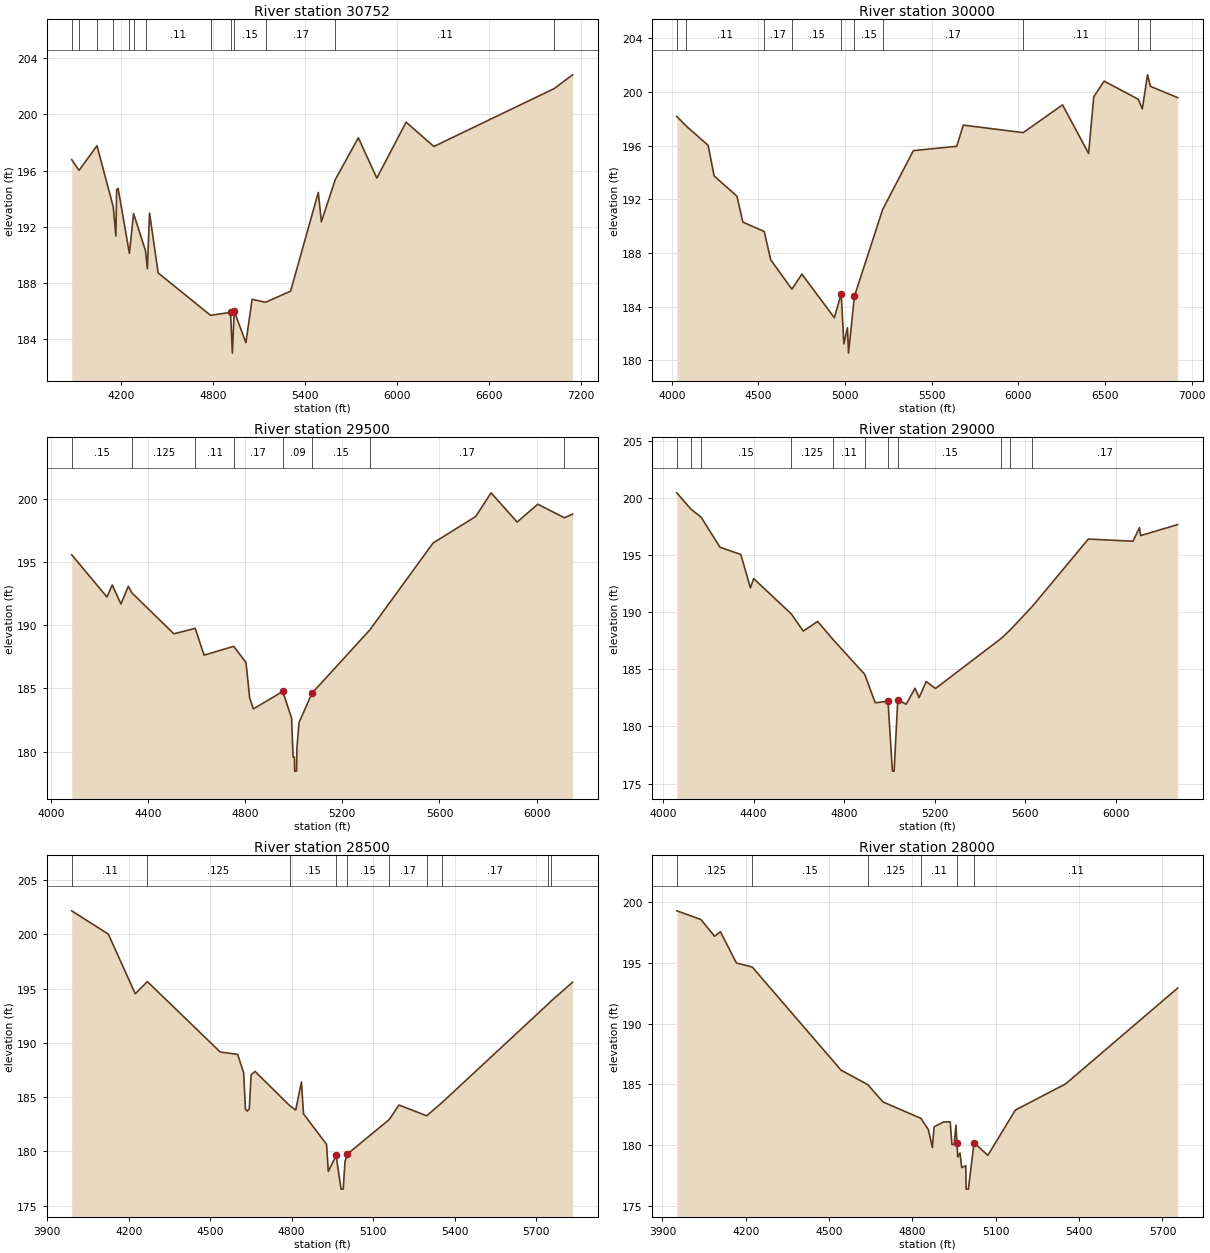
Type RM Length L Ch R = 1 ,30752   ,752,752,752
BEGIN DESCRIPTION:
WEST FORK OF CRYSTAL CREEK 61.0
END DESCRIPTION:
XS GIS Cut Line= 3
       3855849.2     10113469.62      3854732.51     10113572.38
      3852596.91     10113769.67
#Sta/Elev= 30
  3878.6  196.78  3926.4  196.02  4043.5  197.77  4149.9  193.41  4166.7  191.34
  4171.7  194.65  4181.2  194.74  4254.8  190.11    4282  192.95  4359.9  190.29
    4372  189.02  4386.3  192.98  4442.3  188.72    4784   185.7  4914.3  185.91
  4926.4  183.01  4938.3186.0003  5014.7  183.75  5054.9  186.84  5142.6  186.63
    5306  187.42  5486.7  194.45  5506.8  192.36  5597.2  195.36  5747.8  198.34
  5868.3  195.47  6059.2  199.45  6240.4  197.72  7024.9  201.84  7144.7  202.82
#Mann= 13 ,-1 , 0
  3878.6    .125       0  3926.4     .11       0  4043.5     .15       0
  4149.9     .11       0  4254.8     .17       0    4282     .15       0
  4359.9     .11       0    4784     .15       0  4914.3     .09       0
  4938.3     .15       0  5142.6     .17       0  5597.2     .11       0
  7024.9    .125       0
Bank Sta=4914.3,4938.3
XS Rating Curve= 0 ,0
Exp/Cntr=0.3,0.1

Type RM Length L Ch R = 1 ,30000   ,500,500,500
BEGIN DESCRIPTION:
WEST FORK OF CRYSTAL CREEK 60.0
END DESCRIPTION:
XS GIS Cut Line= 3
      3855893.52     10113403.33      3855011.79     10112997.36
      3853094.07      10113077.8
#Sta/Elev= 30
  4029.3  198.18  4081.3  197.49  4210.1  196.02  4244.7  193.74  4376.4  192.23
  4410.3   190.3  4533.7   189.6  4571.1  187.49  4693.3   185.3  4751.1  186.42
  4938.3  183.17    4978  184.95  4993.3  181.22  5013.9  182.42  5020.1  180.53
    5054  184.76  5216.8  191.23  5394.3  195.63  5644.5  195.95  5682.3  197.53
  6028.2  196.97    6255  199.04  6405.5  195.42  6435.2  199.64  6495.2  200.81
  6692.1  199.46  6715.4  198.74  6745.5  201.28  6762.5  200.42  6919.4  199.58
#Mann= 10 ,-1 , 0
  4029.3    .125       0  4081.3     .11       0  4533.7     .17       0
  4693.3     .15       0    4978     .09       0    5054     .15       0
  5216.8     .17       0  6028.2     .11       0  6692.1     .17       0
  6762.5     .11       0
Bank Sta=4978,5054
XS Rating Curve= 0 ,0
Exp/Cntr=0.3,0.1

Type RM Length L Ch R = 1 ,29500   ,500,500,500
BEGIN DESCRIPTION:
WEST FORK OF CRYSTAL CREEK 59.0
END DESCRIPTION:
XS GIS Cut Line= 3
      3856048.63     10113252.01      3855277.97      10112759.5
      3854204.02     10112353.57
#Sta/Elev= 30
  4085.4  195.56  4230.5  192.22  4252.5  193.17  4288.1  191.67  4318.5  193.07
  4333.1  192.55  4506.3  189.31  4594.1  189.74  4630.6  187.62  4752.6  188.32
  4803.2  187.04  4818.4  184.24  4833.6  183.37  4954.6  184.75    4991  182.64
  4997.1  179.56  5002.7  179.56  5003.7  178.45  5011.4  178.45  5012.9  180.26
  5021.5  182.29    5075  184.61  5313.7  189.63  5573.7  196.49  5749.4  198.59
  5812.6  200.46  5919.8  198.15    6005  199.56    6114  198.49  6148.1  198.77
#Mann= 8 ,-1 , 0
  4085.4     .15       0  4333.1    .125       0  4594.1     .11       0
  4752.6     .17       0  4954.6     .09       0    5075     .15       0
  5313.7     .17       0    6114    .125       0
Bank Sta=4954.6,5075
XS Rating Curve= 0 ,0
Exp/Cntr=0.3,0.1

Type RM Length L Ch R = 1 ,29000   ,500,500,500
BEGIN DESCRIPTION:
WEST FORK OF CRYSTAL CREEK 58.0
END DESCRIPTION:
XS GIS Cut Line= 3
      3856317.88      10113211.1      3855644.48     10112556.27
      3854417.83     10112211.06
#Sta/Elev= 30
  4060.7  200.47  4121.7  199.07  4168.2  198.33  4251.7   195.7  4343.6  195.07
    4386  192.14  4400.2  192.96  4567.3  189.85  4619.3  188.36  4683.1   189.2
  4749.3  187.66  4891.1  184.57  4937.7  182.08  4994.2  182.21  5013.4  176.09
  5021.2  176.09 5037.24182.3309  5074.5  181.95  5113.7  183.36  5131.5  182.52
  5162.7  183.94  5204.3  183.33  5495.3  187.73  5535.2  188.48  5632.2  190.53
  5879.5  196.42  6076.9  196.23  6105.5  197.42  6110.7  196.72  6274.3  197.69
#Mann= 11 ,-1 , 0
  4060.7     .15       0  4121.7    .125       0  4168.2     .15       0
  4567.3    .125       0  4749.3     .11       0  4891.1     .15       0
  4994.2     .09       0 5037.24     .15       0  5495.3     .17       0
  5535.2     .15       0  5632.2     .17       0
Bank Sta=4994.2,5037.24
XS Rating Curve= 0 ,0
Exp/Cntr=0.3,0.1

Type RM Length L Ch R = 1 ,28500   ,500,500,500
BEGIN DESCRIPTION:
WEST FORK OF CRYSTAL CREEK 57.0
END DESCRIPTION:
XS GIS Cut Line= 3
      3856617.83     10113011.05      3855977.58     10112230.43
      3855273.97     10111783.22
#Sta/Elev= 30
  3990.4  202.17  4125.3  200.02  4224.3  194.53  4268.9  195.65  4537.2  189.16
  4601.1  188.95  4623.3  187.24  4629.8  183.88    4637  183.72  4644.1  183.94
  4650.6  187.06    4665  187.38    4792  184.24  4814.9  183.82  4835.8   186.4
  4843.6  183.46  4928.3  180.66  4934.8  178.16  4963.5  179.63  4981.8  176.53
  4989.7  176.53  4996.4   179.1 5005.07179.7644    5159  182.94  5194.9  184.28
  5296.9  183.29    5354  184.52  5743.9  193.59  5753.5  193.83  5833.7  195.59
#Mann= 10 ,-1 , 0
  3990.4     .11       0  4268.9    .125       0    4792     .15       0
  4963.5     .09       0 5005.07     .15       0    5159     .17       0
  5296.9     .15       0    5354     .17       0  5743.9     .11       0
  5753.5     .17       0
Bank Sta=4963.5,5005.07
XS Rating Curve= 0 ,0
Exp/Cntr=0.3,0.1

Type RM Length L Ch R = 1 ,28000   ,500,500,500
BEGIN DESCRIPTION:
WEST FORK OF CRYSTAL CREEK 56.0
END DESCRIPTION:
XS GIS Cut Line= 3
      3856866.02     10112704.24      3856216.03     10111882.04
      3855601.59     10111443.81
#Sta/Elev= 30
  3951.9  199.27  4038.2  198.56  4087.9  197.18  4108.9  197.55  4166.5  194.98
  4223.4  194.65  4543.1  186.17  4639.4  184.98  4693.8  183.56  4830.6  182.21
  4857.3  181.28  4871.8  179.82  4878.1  181.52  4913.4  181.92  4935.9  181.92
  4942.2  180.05  4950.2  180.08  4956.7  181.65 4960.26180.1928  4963.1  179.03
  4971.1  179.36  4977.5  178.16  4991.9  178.32  4993.4  176.39  5001.4  176.39
  5021.8  180.21  5071.5  179.17  5170.6  182.89  5351.3  185.04  5754.7  192.92
#Mann= 6 ,-1 , 0
  3951.9    .125       0  4223.4     .15       0  4639.4    .125       0
  4830.6     .11       0 4960.26     .09       0  5021.8     .11       0
Bank Sta=4960.26,5021.8
XS Rating Curve= 0 ,0
Exp/Cntr=0.3,0.1

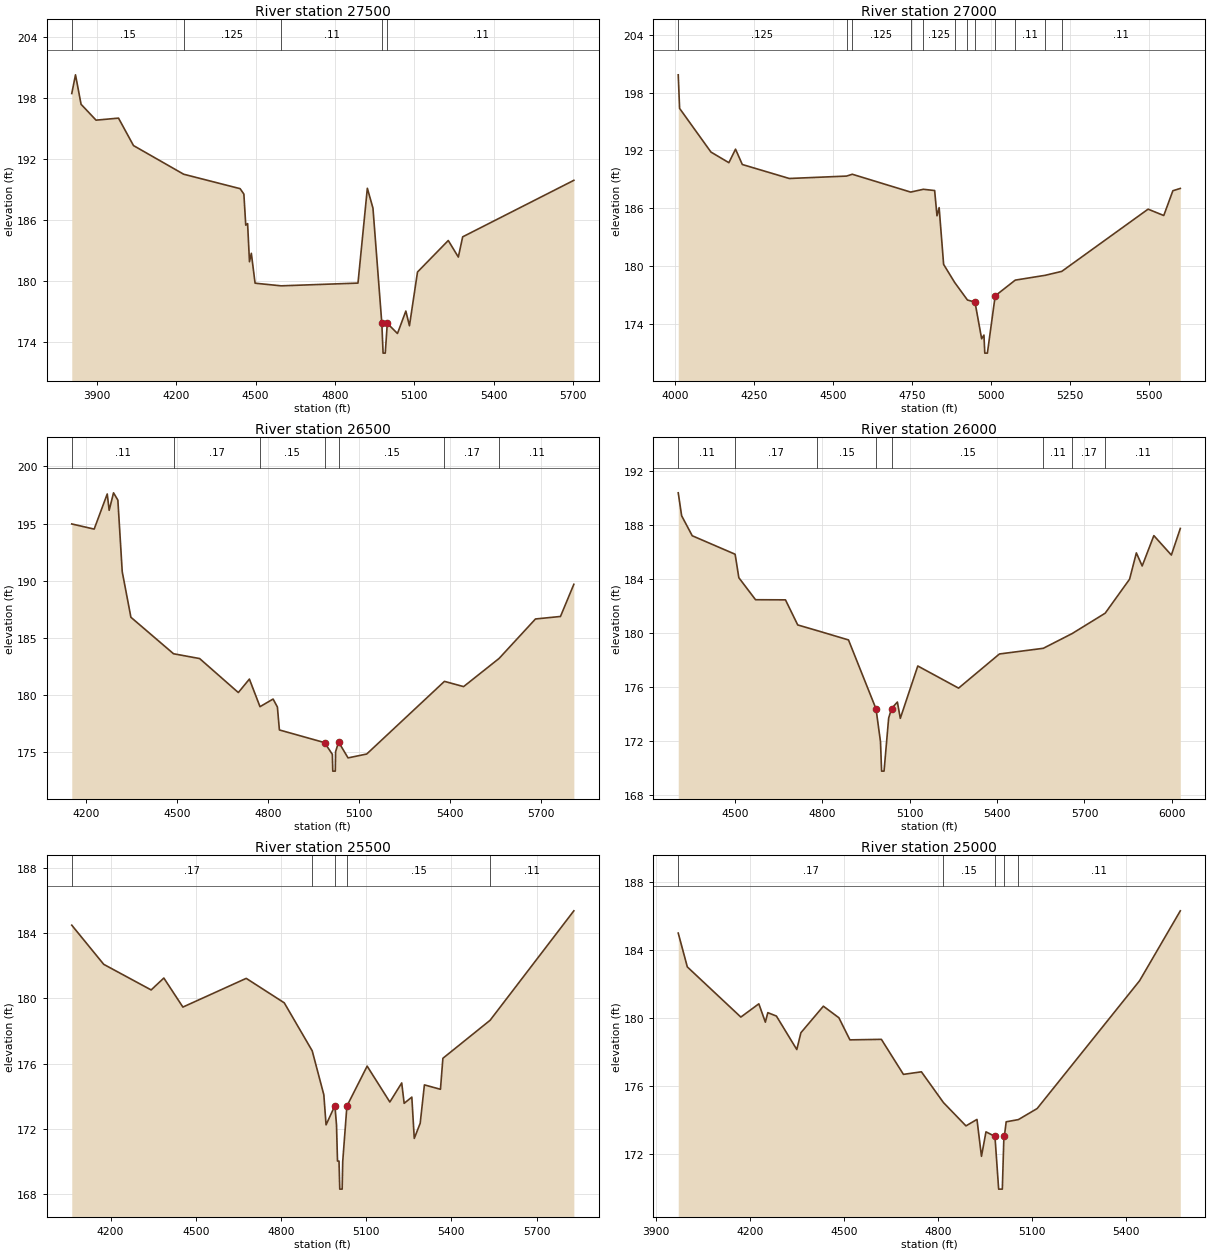
Type RM Length L Ch R = 1 ,27500   ,500,500,500
BEGIN DESCRIPTION:
WEST FORK OF CRYSTAL CREEK 55.0
END DESCRIPTION:
XS GIS Cut Line= 3
       3857326.1     10112352.69      3856490.23     10111499.37
       3855867.8     10111172.15
#Sta/Elev= 30
  3805.5   198.4  3819.6  200.24  3840.7  197.34  3897.3  195.78  3982.2  195.98
  4038.8  193.28  4228.5  190.46  4441.8  189.04    4456  188.51  4463.1  185.45
  4470.1   185.6  4477.2  181.85  4484.2  182.68  4498.4  179.74  4597.1  179.48
  4887.3  179.75  4922.7  189.08  4943.9  187.13 4977.44175.7881  4982.2  172.86
  4990.4  172.86  4998.1  175.79  5036.6  174.79  5068.2     177  5081.8  175.55
  5112.3  180.84  5228.6  183.94  5266.6  182.31    5283   184.3  5703.2  189.86
#Mann= 5 ,-1 , 0
  3805.5     .15       0  4228.5    .125       0  4597.1     .11       0
 4977.44     .09       0  4998.1     .11       0
#Block Obstruct= 2 , 0
         4919.68  188.97
Bank Sta=4977.44,4998.1
XS Rating Curve= 0 ,0
Exp/Cntr=0.3,0.1

Type RM Length L Ch R = 1 ,27000   ,500,500,500
BEGIN DESCRIPTION:
WEST FORK OF CRYSTAL CREEK 54.0
END DESCRIPTION:
XS GIS Cut Line= 3
      3857534.43     10111970.74      3856860.38     10111245.79
      3856392.94     10110872.66
#Sta/Elev= 30
  4010.1  199.84  4014.4  196.36  4113.6  191.83  4170.3  190.73  4191.3  192.13
  4212.8  190.54  4361.4  189.09  4542.6  189.34  4560.6  189.53  4745.2  187.68
  4785.6  187.97  4821.1  187.84  4828.5  185.22  4835.3  186.07  4849.5  180.18
  4884.4  178.31  4924.8  176.49  4948.7  176.27  4969.7  172.47    4977  172.85
  4979.7  170.98  4987.9  170.98  5012.6  176.92    5076  178.55  5170.7  179.05
  5223.3  179.46  5496.2  185.91  5545.8  185.25  5574.6  187.82  5598.1  188.06
#Mann= 12 ,-1 , 0
  4010.1    .125       0  4542.6     .15       0  4560.6    .125       0
  4745.2     .11       0  4785.6    .125       0  4884.4     .17       0
  4924.8     .15       0  4948.7     .09       0  5012.6     .15       0
    5076     .11       0  5170.7     .15       0  5223.3     .11       0
Bank Sta=4948.7,5012.6
XS Rating Curve= 0 ,0
Exp/Cntr=0.3,0.1

Type RM Length L Ch R = 1 ,26500   ,500,500,500
BEGIN DESCRIPTION:
WEST FORK OF CRYSTAL CREEK 53.0
END DESCRIPTION:
XS GIS Cut Line= 3
       3857768.8     10111584.45      3857229.38      10110930.4
      3856445.05     10110733.77
#Sta/Elev= 30
  4152.2  194.96  4226.1  194.51  4269.2  197.59  4275.6  196.16    4290  197.69
  4304.3  197.05  4318.7  190.77  4347.3  186.78    4488  183.58    4574  183.16
  4701.7  180.18  4738.2  181.36  4773.2  178.94  4816.4  179.61  4830.6  178.91
  4837.2   176.9  4986.2  175.79  5011.9  174.76  5013.3  173.29  5021.6  173.29
  5022.6  174.99  5032.5  175.84  5063.7  174.45  5125.3  174.79  5381.7  181.16
  5444.9   180.7    5562  183.17    5682  186.63  5764.5  186.85  5808.6  189.67
#Mann= 7 ,-1 , 0
  4152.2     .11       0    4488     .17       0  4773.2     .15       0
  4986.2     .09       0  5032.5     .15       0  5381.7     .17       0
    5562     .11       0
Bank Sta=4986.2,5032.5
XS Rating Curve= 0 ,0
Exp/Cntr=0.3,0.1

Type RM Length L Ch R = 1 ,26000   ,500,500,500
BEGIN DESCRIPTION:
WEST FORK OF CRYSTAL CREEK 52.0
END DESCRIPTION:
XS GIS Cut Line= 3
      3858107.34     10110959.45      3857525.84     10110580.46
      3856497.11     10110599.22
#Sta/Elev= 30
  4305.9  190.38  4317.6  188.68  4353.9   187.2  4501.1  185.83  4513.9  184.09
  4571.2  182.46  4673.9  182.45    4716  180.59  4781.4  180.18  4890.2  179.48
  4984.7  174.37    5000  171.94  5003.8  169.76  5012.2  169.76    5028  173.69
    5038   174.4    5058  174.88    5068  173.67    5128  177.55    5268  175.91
  5408.1  178.44  5558.7  178.86  5657.5  179.95    5771  181.46  5854.8  183.98
  5878.1  185.93  5898.1  184.96  5938.1  187.21  5998.2  185.77  6028.9  187.74
#Mann= 8 ,-1 , 0
  4305.9     .11       0  4501.1     .17       0  4781.4     .15       0
  4984.7     .09       0    5038     .15       0  5558.7     .11       0
  5657.5     .17       0    5771     .11       0
Bank Sta=4984.7,5038
XS Rating Curve= 0 ,0
Exp/Cntr=0.3,0.1

Type RM Length L Ch R = 1 ,25500   ,500,500,500
BEGIN DESCRIPTION:
WEST FORK OF CRYSTAL CREEK 51.0
END DESCRIPTION:
XS GIS Cut Line= 3
      3858337.38      10110694.7      3857500.89     10110272.93
      3857017.91     10109596.58
#Sta/Elev= 30
  4063.2  184.48  4175.7  182.08  4342.7  180.51  4387.4  181.24  4454.5  179.46
  4677.5  181.22  4811.4  179.72  4909.8  176.78  4950.8  174.08  4958.6  172.24
  4989.8  173.42  4995.4  172.23  4998.9  170.02  5004.2  170.02  5006.9   168.3
  5015.3   168.3  5017.3  169.99    5032  173.39  5103.3  175.84  5183.2  173.64
    5225  174.81  5233.6  173.56  5260.6  173.94  5269.2  171.41  5290.1  172.34
  5304.9  174.69  5361.4  174.42    5370  176.32  5536.2  178.65  5831.1  185.36
#Mann= 5 ,-1 , 0
  4063.2     .17       0  4909.8     .15       0  4989.8     .09       0
    5032     .15       0  5536.2     .11       0
Bank Sta=4989.8,5032
XS Rating Curve= 0 ,0
Exp/Cntr=0.3,0.1

Type RM Length L Ch R = 1 ,25000   ,500,500,500
BEGIN DESCRIPTION:
WEST FORK OF CRYSTAL CREEK 50.0
END DESCRIPTION:
XS GIS Cut Line= 3
      3858348.52     10110651.82      3857691.93     10109860.95
      3857260.15     10109485.18
#Sta/Elev= 30
  3972.1  184.99  4001.1     183  4171.7  180.05    4229  180.83  4249.8  179.75
  4257.6  180.31    4285  180.11    4350  178.14  4363.1  179.13  4434.7  180.69
  4484.2  180.01  4519.3  178.71  4619.6  178.74  4689.9  176.68  4747.2  176.83
  4817.5  175.02  4889.2  173.65  4924.3  174.03  4938.6  171.86    4953   173.3
  4981.6  173.03  4993.4  169.93  5005.1  169.93  5009.7  172.76 5011.84 173.074
  5017.4  173.89  5056.3  174.02  5116.1  174.67  5442.7  182.19  5572.4   186.3
#Mann= 5 ,-1 , 0
  3972.1     .17       0  4817.5     .15       0  4981.6     .09       0
 5011.84     .15       0  5056.3     .11       0
Bank Sta=4981.6,5011.84
XS Rating Curve= 0 ,0
Exp/Cntr=0.3,0.1

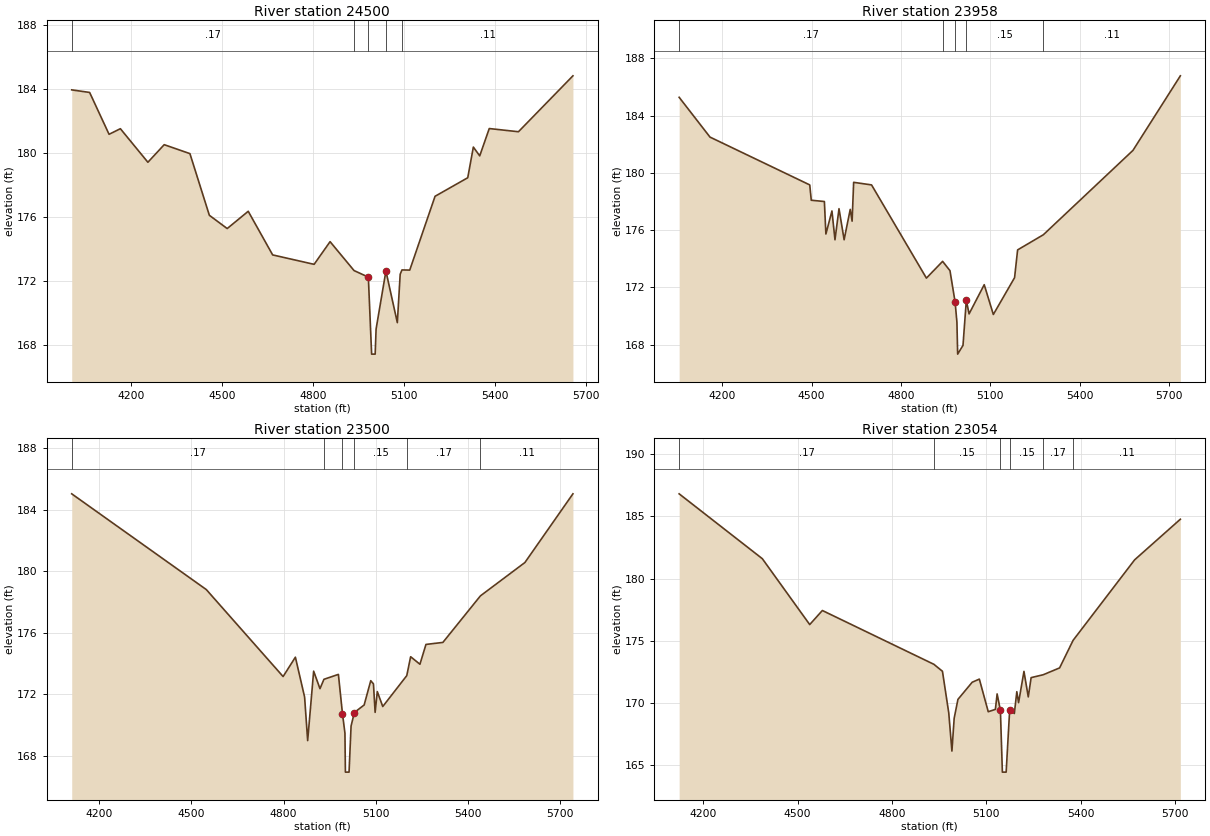
Type RM Length L Ch R = 1 ,24500   ,542,542,542
BEGIN DESCRIPTION:
WEST FORK OF CRYSTAL CREEK 49.0
END DESCRIPTION:
XS GIS Cut Line= 3
      3858371.41     10110620.99      3858065.01     10109674.35
      3857867.95     10109048.12
#Sta/Elev= 30
    4005  183.94    4064  183.78    4128  181.16  4165.3  181.51    4256  179.41
  4309.7  180.51  4394.5  179.95  4458.5  176.09  4517.3  175.26  4586.6  176.34
  4667.1  173.61  4803.7  173.02  4856.3  174.44  4935.3  172.63  4982.4  172.22
  4993.2   167.4  5004.9   167.4  5007.9  168.97  5040.3   172.6  5077.9  169.37
  5087.3   172.4  5093.2  172.67  5118.8  172.66  5202.2  177.28  5309.9  178.44
  5328.4  180.36  5349.4  179.81  5380.8  181.52    5477  181.32  5656.5  184.82
#Mann= 5 ,-1 , 0
    4005     .17       0  4935.3     .15       0  4982.4     .09       0
  5040.3     .15       0  5093.2     .11       0
Bank Sta=4982.4,5040.3
XS Rating Curve= 0 ,0
Exp/Cntr=0.3,0.1

Type RM Length L Ch R = 1 ,23958   ,458,458,458
BEGIN DESCRIPTION:
WEST FORK OF CRYSTAL CREEK 48.0
END DESCRIPTION:
XS GIS Cut Line= 3
      3858526.47     10110582.35      3858325.87      10109659.5
      3858184.17     10108934.82
#Sta/Elev= 30
  4055.6  185.28  4159.2   182.5  4494.1  179.16  4499.2  178.09  4543.2     178
  4548.3  175.73  4568.6  177.34  4578.8  175.33  4592.3   177.5  4609.5  175.33
    4630  177.45  4636.3  176.63  4641.5  179.34  4701.6  179.16  4885.8  172.65
  4940.2  173.82  4964.9  173.17  4982.1170.9836  4988.2  169.58  4990.7  167.34
  5008.6  167.95  5019.8   171.1    5029  170.15  5079.9  172.19  5110.5  170.11
  5181.8  172.68    5192  174.62  5278.5  175.68  5579.2  181.57  5738.4  186.78
#Mann= 5 ,-1 , 0
  4055.6     .17       0  4940.2     .15       0  4982.1     .09       0
  5019.8     .15       0  5278.5     .11       0
Bank Sta=4982.1,5019.8
XS Rating Curve= 0 ,0
Exp/Cntr=0.3,0.1

Type RM Length L Ch R = 1 ,23500   ,446,446,446
BEGIN DESCRIPTION:
WEST FORK OF CRYSTAL CREEK 47.0
END DESCRIPTION:
XS GIS Cut Line= 3
      3858721.78     10110539.01      3858756.68      10109649.8
      3858496.21     10108954.37
#Sta/Elev= 30
  4110.1  185.05  4548.4  178.82  4798.6  173.16  4838.6  174.42  4868.6  171.83
  4878.6  168.99  4898.1  173.51  4918.7  172.37  4931.6  172.98  4978.7   173.3
 4991.99170.7374    5000  169.48  5001.5  166.94  5013.4  166.94    5020  169.94
  5030.7  170.82  5062.6  171.31  5084.1  172.89  5092.9  172.68  5098.3  170.83
  5105.4  172.18  5123.2  171.21  5201.4  173.22    5214  174.45  5244.3  173.96
  5263.9  175.25    5319  175.38  5441.3  178.41  5586.2  180.58  5742.6  185.05
#Mann= 6 ,-1 , 0
  4110.1     .17       0  4931.6     .15       0 4991.99     .09       0
  5030.7     .15       0  5201.4     .17       0  5441.3     .11       0
Bank Sta=4991.99,5030.7
XS Rating Curve= 0 ,0
Exp/Cntr=0.3,0.1

Type RM Length L Ch R = 1 ,23054   ,554,554,554
BEGIN DESCRIPTION:
WEST FORK OF CRYSTAL CREEK 46.0
END DESCRIPTION:
XS GIS Cut Line= 3
      3858956.16     10110504.26       3859038.5     10109631.84
      3858730.65     10108984.51
#Sta/Elev= 30
  4123.7   186.8  4388.1  181.59  4538.7   176.3  4578.9  177.43  4933.3  173.11
  4960.6  172.55  4980.7   169.2  4990.7  166.14  4997.9  168.78  5009.8  170.29
  5055.2  171.67  5077.9  171.92  5106.2   169.3  5128.9  169.49  5134.4  170.73
  5144.8  169.41  5151.1  164.45  5163.1  164.45  5174.3  169.46  5189.1  169.16
    5197  170.91  5202.6  170.03  5219.7  172.54  5233.4  170.49  5242.5  172.04
  5280.9  172.27    5333  172.82  5375.8  175.03  5571.5   181.5  5716.8  184.76
#Mann= 6 ,-1 , 0
  4123.7     .17       0  4933.3     .15       0  5144.8     .09       0
  5174.3     .15       0  5280.9     .17       0  5375.8     .11       0
Bank Sta=5144.8,5174.3
XS Rating Curve= 0 ,0
Exp/Cntr=0.3,0.1