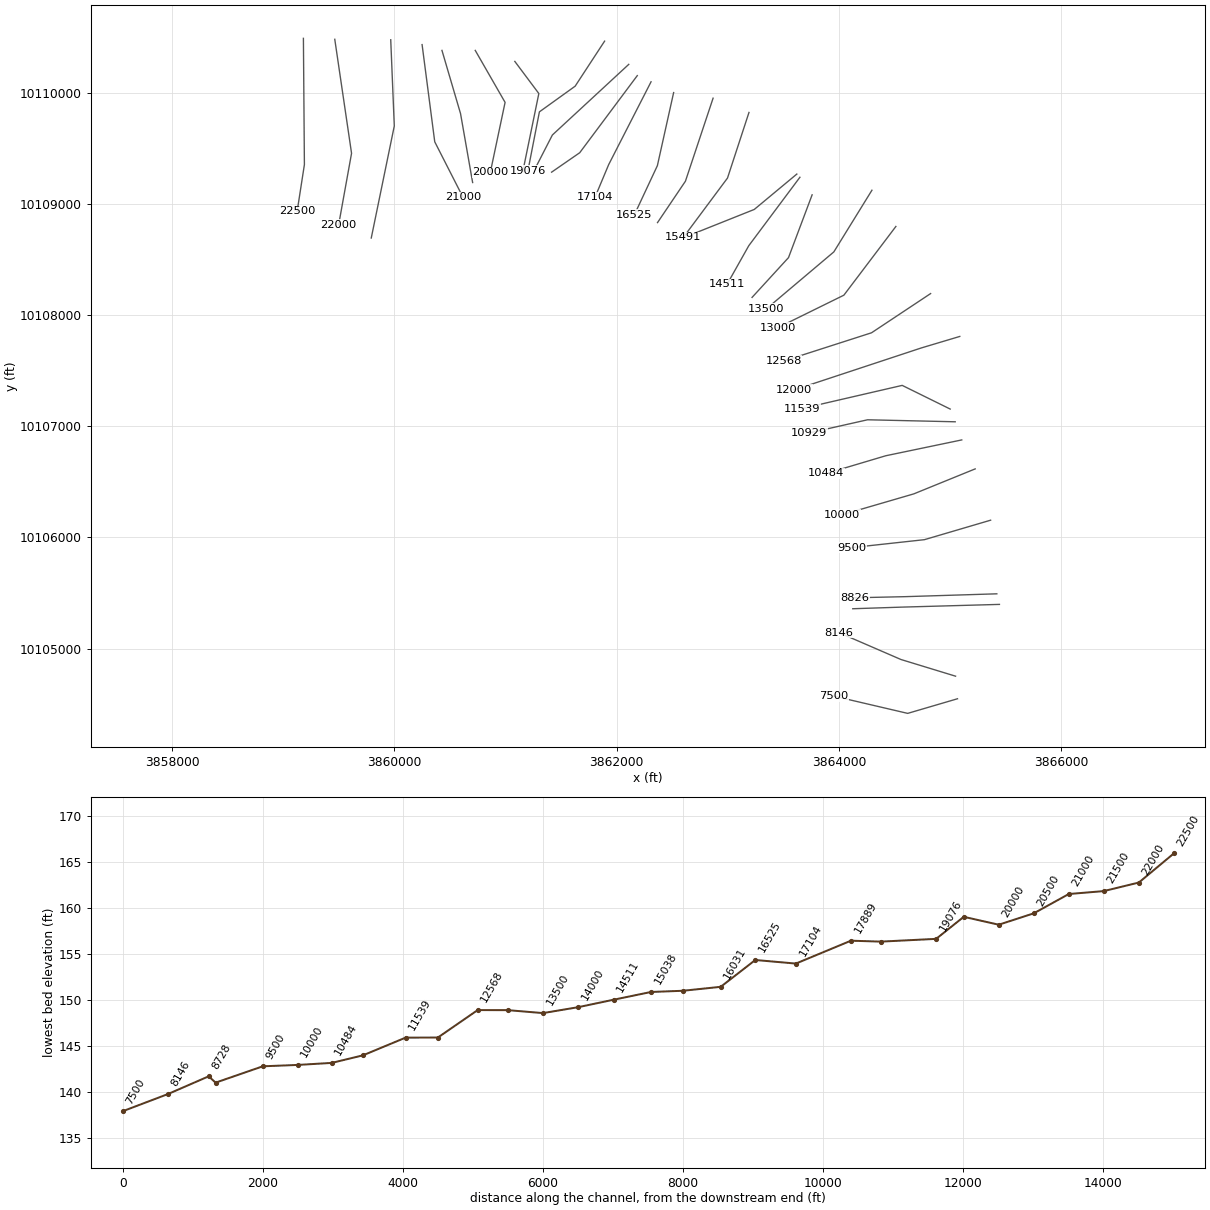
HEC-RAS study WEST FORK OF CRYSTAL CREEK.prj: WEST FORK OF CRYSTAL CREEK Base Level Engineering

--- WEST FORK OF CRYSTAL CREEK.g01 (geometry) --- (continued)

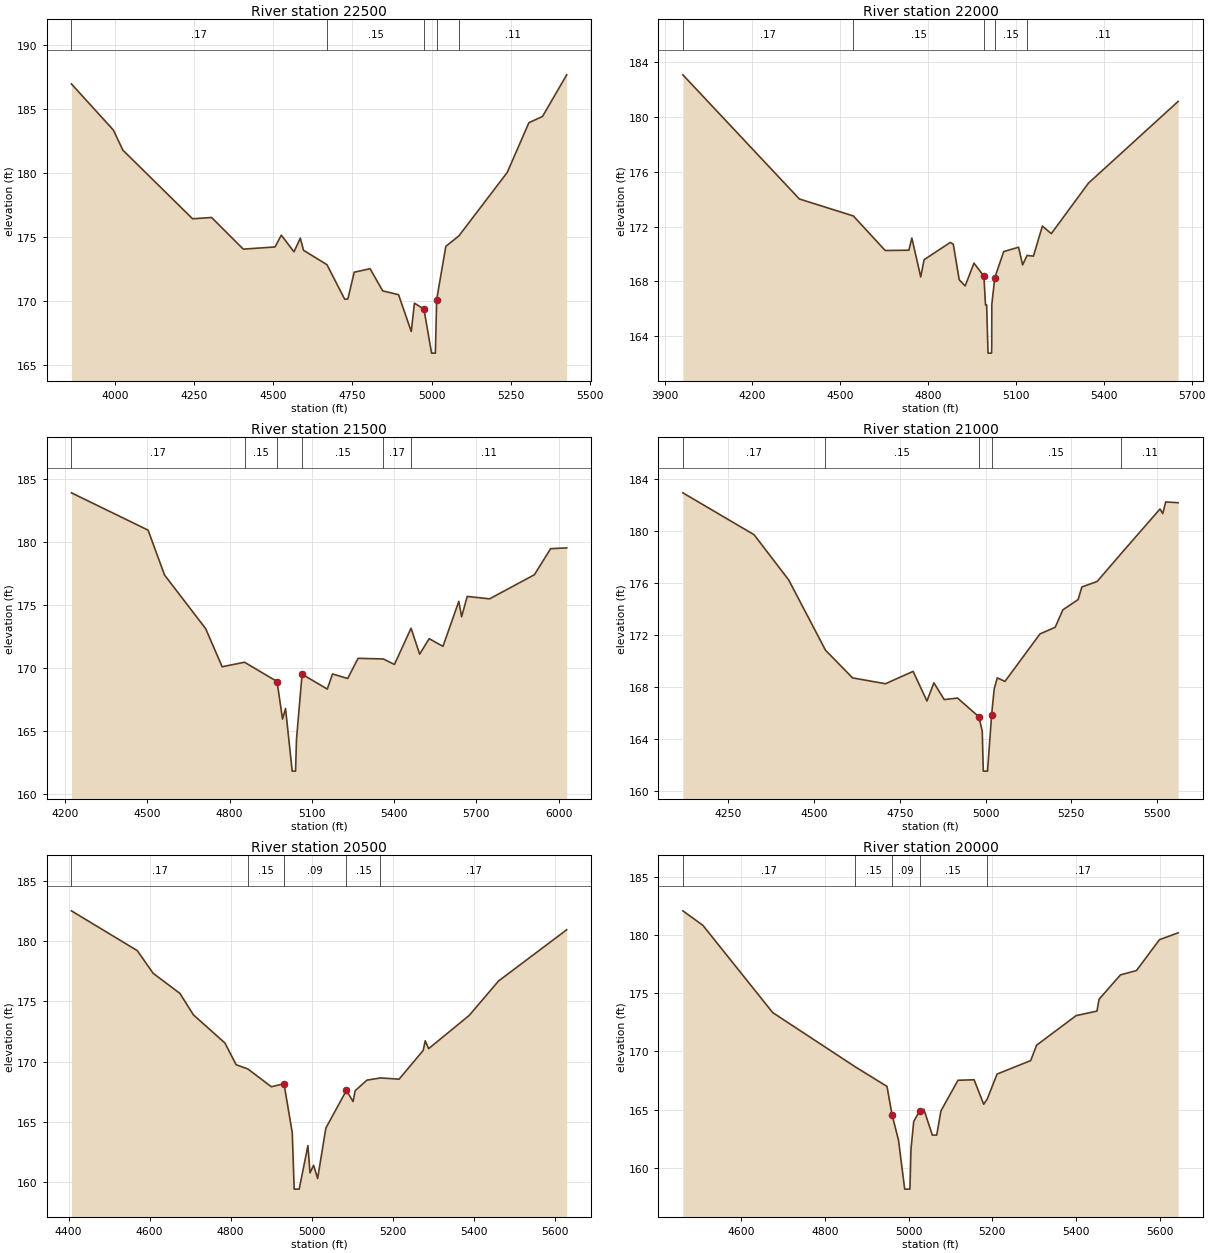
Type RM Length L Ch R = 1 ,22500   ,500,500,500
BEGIN DESCRIPTION:
WEST FORK OF CRYSTAL CREEK 45.0
END DESCRIPTION:
XS GIS Cut Line= 3
      3859181.31     10110493.38      3859190.22     10109356.62
      3859124.95     10108935.65
#Sta/Elev= 30
  3863.2  186.96  3995.5  183.36  4025.5  181.79  4245.5  176.43  4305.5  176.53
  4405.5  174.06  4505.5  174.23  4525.5  175.15  4565.5  173.85  4585.5  174.92
  4595.5  173.97  4669.4  172.85  4725.5  170.15  4735.5  170.17  4755.5  172.26
  4805.5  172.53  4845.5   170.8  4895.5   170.5  4935.5  167.63  4945.5  169.84
  4975.5  169.38  4999.6  165.94  5011.6  165.94  5015.7  170.12  5044.6  174.28
  5085.3  175.08  5238.4  180.05  5306.7  183.93  5349.7  184.42    5426  187.67
#Mann= 5 ,-1 , 0
  3863.2     .17       0  4669.4     .15       0  4975.5     .09       0
  5015.7     .15       0  5085.3     .11       0
Bank Sta=4975.5,5015.7
XS Rating Curve= 0 ,0
Exp/Cntr=0.3,0.1

Type RM Length L Ch R = 1 ,22000   ,500,500,500
BEGIN DESCRIPTION:
WEST FORK OF CRYSTAL CREEK 44.0
END DESCRIPTION:
XS GIS Cut Line= 3
      3859463.43     10110484.72      3859614.44     10109458.37
      3859498.36     10108814.86
#Sta/Elev= 30
  3962.6  183.08  4360.5  174.02  4544.8  172.78  4653.6  170.26  4734.5  170.28
  4744.6  171.17  4774.9  168.33  4786.5  169.59    4876  170.85  4886.1  170.72
  4906.3  168.13  4926.5  167.67  4956.8  169.34  4990.6  168.38  4996.1  166.29
    5000  166.29  5004.7  162.77  5016.8  162.77  5017.3  163.27  5017.6  166.31
  5027.7  168.27  5058.2  170.18    5109   170.5  5122.9  169.21  5138.1   169.9
  5159.8  169.85  5190.3  172.04  5220.8  171.49  5347.4  175.17  5653.9  181.14
#Mann= 5 ,-1 , 0
  3962.6     .17       0  4544.8     .15       0  4990.6     .09       0
  5027.7     .15       0  5138.1     .11       0
Bank Sta=4990.6,5027.7
XS Rating Curve= 0 ,0
Exp/Cntr=0.3,0.1

Type RM Length L Ch R = 1 ,21500   ,500,500,500
BEGIN DESCRIPTION:
WEST FORK OF CRYSTAL CREEK 43.0
END DESCRIPTION:
XS GIS Cut Line= 3
       3859966.9     10110480.39      3859998.94     10109704.35
      3859791.68     10108695.62
#Sta/Elev= 30
  4223.3  183.92  4502.9  180.96  4562.9   177.4    4713  173.14  4773.1  170.12
  4854.7  170.48  4973.3  168.95  4993.3  165.97  5004.2  166.81  5028.6  161.84
  5040.8  161.84  5044.2  164.36  5064.6  169.53  5156.5  168.35  5175.6  169.55
    5231  169.19  5268.8  170.79    5361  170.74  5401.5   170.3  5462.1  173.18
  5493.4  171.12  5528.1  172.35  5578.5  171.74  5636.3  175.31  5646.5  174.09
  5666.9   175.7  5748.6  175.51  5911.9  177.42  5971.2  179.49  6029.8  179.55
#Mann= 6 ,-1 , 0
  4223.3     .17       0  4854.7     .15       0  4973.3     .09       0
  5064.6     .15       0    5361     .17       0  5462.1     .11       0
Bank Sta=4973.3,5064.6
XS Rating Curve= 0 ,0
Exp/Cntr=0.3,0.1

Type RM Length L Ch R = 1 ,21000   ,500,500,500
BEGIN DESCRIPTION:
WEST FORK OF CRYSTAL CREEK 42.0
END DESCRIPTION:
XS GIS Cut Line= 3
      3860249.01     10110437.01      3860362.92     10109561.69
      3860617.86     10109061.06
#Sta/Elev= 30
  4117.3  182.92    4325   179.7  4425.8  176.23  4533.3  170.82  4612.2  168.69
  4708.2  168.24  4788.9  169.19  4829.2  166.91  4849.4  168.31  4879.6  167.02
  4918.4  167.14  4980.5   165.7  4990.5   164.6  4993.5  161.52  5005.9  161.52
 5017.84165.8521  5025.3  167.84  5034.4  168.69  5056.8  168.42  5158.8  172.07
  5203.2  172.58  5225.5  173.92    5270  174.71    5281  175.68  5325.5   176.1
    5395  178.23    5509  181.68  5516.9  181.32  5525.6  182.22  5561.8  182.16
#Mann= 5 ,-1 , 0
  4117.3     .17       0  4533.3     .15       0  4980.5     .09       0
 5017.84     .15       0    5395     .11       0
Bank Sta=4980.5,5017.84
XS Rating Curve= 0 ,0
Exp/Cntr=0.3,0.1

Type RM Length L Ch R = 1 ,20500   ,500,500,500
BEGIN DESCRIPTION:
WEST FORK OF CRYSTAL CREEK 41.0
END DESCRIPTION:
XS GIS Cut Line= 3
      3860427.83     10110384.72      3860594.98     10109815.66
      3860703.75     10109195.33
#Sta/Elev= 30
  4406.9   182.5  4569.5   179.2  4608.7  177.32  4674.8  175.65  4708.2  173.87
  4785.9  171.54  4813.5  169.74  4842.8  169.38  4900.6  167.91  4931.8  168.16
  4952.2  164.09  4956.9  159.42  4969.3  159.42  4990.8  163.03    4996  160.77
  5004.9   161.4  5014.8   160.3  5035.1  164.48  5085.9  167.61  5102.3  166.68
  5107.4  167.58  5136.6  168.46    5170  168.64    5216  168.54  5275.4  170.92
  5280.5  171.72  5288.9  171.07  5389.2  173.83  5461.5  176.68  5629.8  180.93
#Mann= 5 ,-1 , 0
  4406.9     .17       0  4842.8     .15       0  4931.8     .09       0
  5085.9     .15       0    5170     .17       0
Bank Sta=4931.8,5085.9
XS Rating Curve= 0 ,0
Exp/Cntr=0.3,0.1

Type RM Length L Ch R = 1 ,20000   ,500,500,500
BEGIN DESCRIPTION:
WEST FORK OF CRYSTAL CREEK 40.0
END DESCRIPTION:
XS GIS Cut Line= 3
       3860727.3     10110384.73      3860995.73     10109916.86
      3860862.83     10109286.21
#Sta/Elev= 30
  4460.6  182.08  4508.6  180.83  4675.4  173.34  4872.4  168.69  4948.6     167
  4960.6  164.57    4976   162.4  4990.9  158.18  5003.4  158.18  5005.9  161.62
  5012.5     164  5026.4  164.88  5036.6  165.04    5057  162.82  5067.4  162.82
  5077.5   164.9  5118.3  167.53  5156.8  167.57  5179.7  165.47  5187.9   165.9
  5211.7  168.06  5292.1  169.22  5306.2  170.54  5400.7  173.08  5450.4  173.47
  5455.6  174.49  5506.7  176.58  5544.9  176.95  5599.8   179.6  5644.5  180.19
#Mann= 5 ,-1 , 0
  4460.6     .17       0  4872.4     .15       0  4960.6     .09       0
  5026.4     .15       0  5187.9     .17       0
Bank Sta=4960.6,5026.4
XS Rating Curve= 0 ,0
Exp/Cntr=0.3,0.1

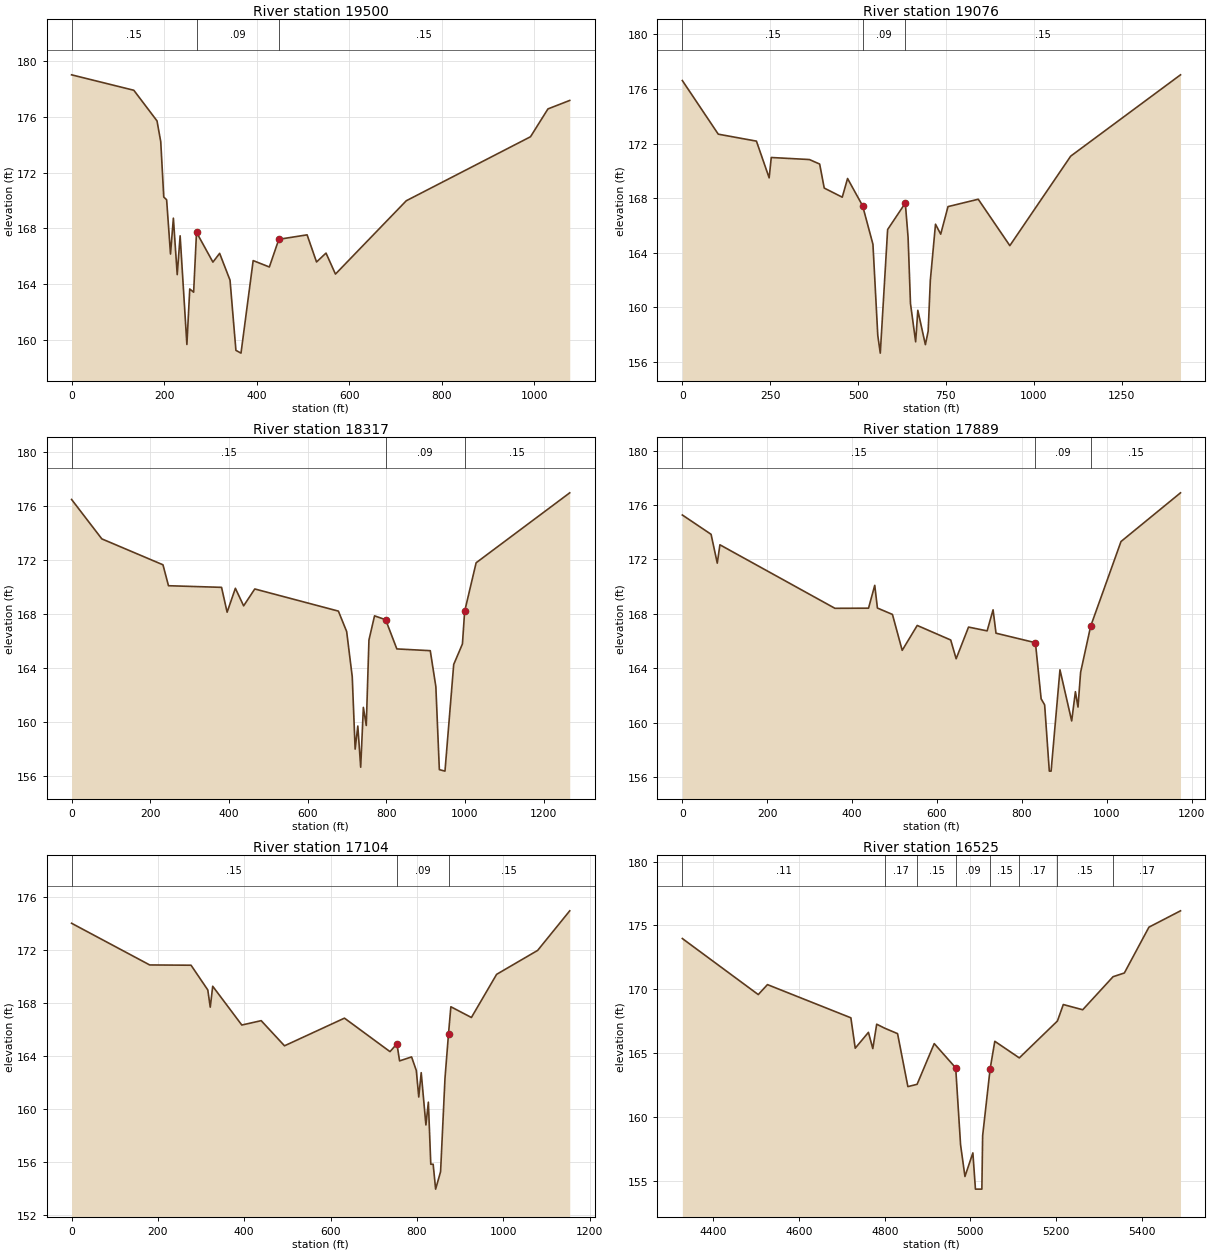
Type RM Length L Ch R = 1 ,19500   ,394,394,394
XS GIS Cut Line= 3
      3861083.44     10110285.49       3861299.4     10109996.47
      3861155.17     10109293.77
#Sta/Elev= 30
       0  179.04   134.6  177.93   184.7  175.73   192.8  174.23   199.3  170.26
   205.5  170.06   213.9  166.16   220.1  168.74   228.4  164.68   234.7  167.47
   249.3  159.66   255.5  163.65   263.9  163.42   270.1  167.72   305.6  165.58
   320.1  166.21   342.6  164.28   355.3  159.24   366.3  159.04   392.6  165.69
   427.6  165.23   448.1  167.22   509.2  167.54   529.6  165.59   550.1  166.23
   570.5  164.72   723.6  169.99   992.2  174.59  1029.9  176.59    1077   177.2
#Mann= 3 , 0 , 0
       0     .15       0   270.1     .09       0   448.1     .15       0
Bank Sta=270.1,448.1
XS Rating Curve= 0 ,0
Exp/Cntr=0.3,0.1

Type RM Length L Ch R = 1 ,19076   ,789,789,789
XS GIS Cut Line= 4
      3861891.04     10110468.09      3861626.12     10110062.68
      3861304.47     10109831.44      3861201.44     10109302.66
#Sta/Elev= 30
       0  176.62   102.2  172.69   210.8  172.18     247  169.49     253  170.98
   361.5  170.83   390.7   170.5   403.7  168.74     455  168.07   470.1  169.44
   512.9  167.44   542.3  164.62   556.1  157.93   563.2  156.64   584.1   165.7
   634.4  167.64   642.3  165.12   649.1  160.28   663.8  157.47     670  159.78
   691.5  157.26   699.4  158.25   705.6  161.98   720.3  166.09   735.1  165.36
   755.9  167.38   841.9  167.92   931.8  164.52    1105  171.08  1417.4  177.04
#Mann= 3 , 0 , 0
       0     .15       0   512.9     .09       0   634.4     .15       0
Bank Sta=512.9,634.4
XS Rating Curve= 0 ,0
Exp/Cntr=0.3,0.1

Type RM Length L Ch R = 1 ,18317   ,428,428,428
XS GIS Cut Line= 3
      3862108.41     10110259.05      3861421.18     10109623.18
       3861270.4     10109329.26
#Sta/Elev= 30
       0  176.46    76.9  173.54   232.4  171.62   246.4  170.07   381.3  169.95
   395.5  168.11   416.5  169.88   437.5  168.58   465.8  169.83   678.4  168.19
   699.4  166.68   713.6  163.34     721  157.97   727.8  159.68   735.1  156.63
   741.9  161.06   749.3  159.72   756.1  166.05   770.3  167.84   798.6  167.55
     827  165.39     912  165.26   926.2   162.6   935.1  156.45   949.4  156.34
   971.6  164.24   993.8  165.76   999.4  168.17  1028.6  171.77  1266.6  176.95
#Mann= 3 , 0 , 0
       0     .15       0   798.6     .09       0   999.4     .15       0
Bank Sta=798.6,999.4
XS Rating Curve= 0 ,0
Exp/Cntr=0.3,0.1

Type RM Length L Ch R = 1 ,17889   ,786,786,786
XS GIS Cut Line= 3
      3862185.14     10110157.83      3861667.17     10109463.57
      3861414.29     10109288.61
#Sta/Elev= 30
       0  175.27    67.7  173.85    82.3  171.73    88.5  173.08   359.5  168.41
   438.7  168.42   453.3   170.1   459.6  168.43     495  167.96     518  165.32
   553.4  167.15   632.3  166.08   645.1   164.7   674.3  167.03   718.1  166.75
   732.1   168.3     739  166.58   831.9  165.88   845.3  161.76   853.6  161.31
   864.6  156.44   868.8  156.44   889.7  163.89   917.3  160.13   926.1  162.28
   932.2  161.15   938.3   163.7   961.9  167.08  1033.5  173.32  1173.7   176.9
#Mann= 3 , 0 , 0
       0     .15       0   831.9     .09       0   961.9     .15       0
Bank Sta=831.9,961.9
XS Rating Curve= 0 ,0
Exp/Cntr=0.3,0.1

Type RM Length L Ch R = 1 ,17104   ,579,579,579
XS GIS Cut Line= 3
      3862309.06      10110102.2       3861927.7     10109356.38
      3861804.76     10109062.91
#Sta/Elev= 30
       0  174.04     181  170.89   276.8  170.87   315.6     169   321.3   167.7
     327  169.28   394.4  166.35   439.3  166.68   493.3  164.78   632.2  166.87
   737.7  164.34   753.8  164.93   759.9  163.64   787.7  163.94   798.7  162.91
   804.3  160.91     810  162.75   820.9   158.8   826.6  160.52   832.2  155.83
   837.7  155.83   843.4  153.95   854.9  155.27   865.1  162.32   873.3   165.7
   878.7  167.73   926.3  166.92   984.7  170.18  1079.8  171.99  1154.1  174.98
#Mann= 3 , 0 , 0
       0     .15       0   753.8     .09       0   873.3     .15       0
Bank Sta=753.8,873.3
XS Rating Curve= 0 ,0
Exp/Cntr=0.3,0.1

Type RM Length L Ch R = 1 ,16525   ,494,494,494
BEGIN DESCRIPTION:
WEST FORK OF CRYSTAL CREEK 33.0
END DESCRIPTION:
XS GIS Cut Line= 3
      3862512.18     10110005.08      3862365.96     10109347.24
      3862158.73     10108904.31
#Sta/Elev= 30
  4327.6  173.97  4504.8  169.58  4526.3  170.36    4721  167.76  4731.2  165.38
    4762  166.62  4772.2  165.35  4781.3  167.26  4800.4  166.94    4830  166.52
  4854.1  162.37  4875.6  162.55  4915.6  165.74  4965.7  163.84  4977.1  157.81
  4987.3  155.33  5005.8  157.18  5011.8  154.34  5026.8  154.34  5028.6  158.52
 5046.03163.7452    5057  165.92  5114.2  164.62  5203.2  167.51  5216.9   168.8
  5262.2  168.39  5333.1  170.98  5359.4  171.27  5416.8  174.86  5490.5  176.14
#Mann= 8 ,-1 , 0
  4327.6     .11       0  4800.4     .17       0  4875.6     .15       0
  4965.7     .09       0 5046.03     .15       0  5114.2     .17       0
  5203.2     .15       0  5333.1     .17       0
Bank Sta=4965.7,5046.03
XS Rating Curve= 0 ,0
Exp/Cntr=0.3,0.1

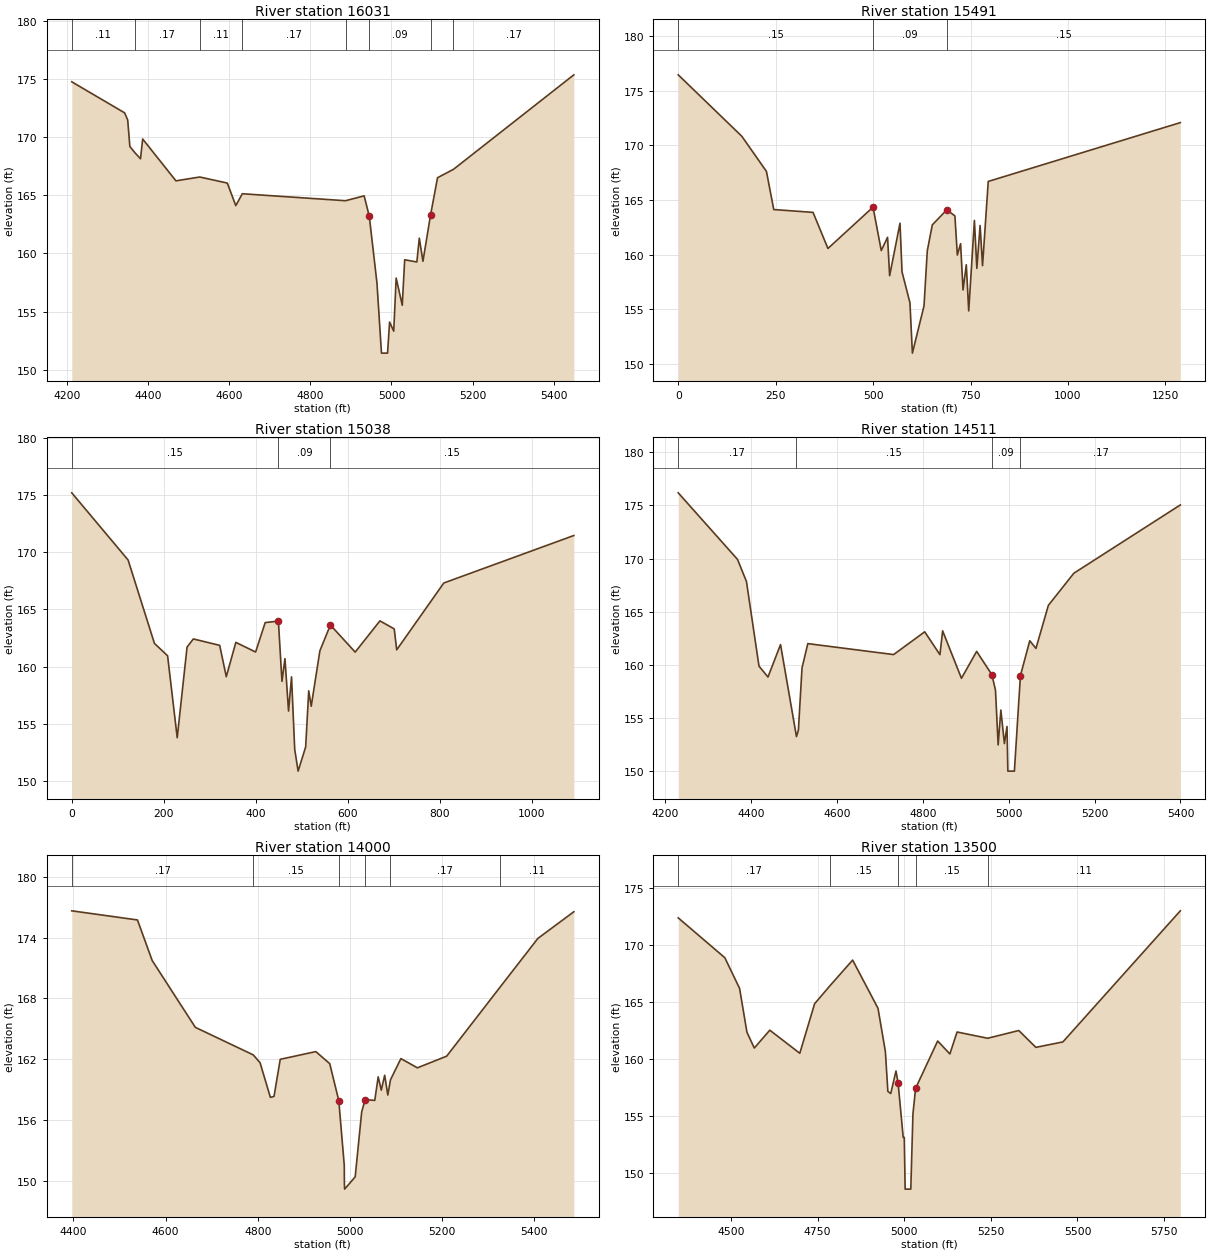
Type RM Length L Ch R = 1 ,16031   ,540,540,540
BEGIN DESCRIPTION:
WEST FORK OF CRYSTAL CREEK 32.0
END DESCRIPTION:
XS GIS Cut Line= 3
       3862867.1     10109954.62      3862618.27     10109207.15
      3862367.21     10108834.54
#Sta/Elev= 30
  4212.2  174.76  4342.4  172.09    4350  171.48  4355.3   169.2    4368  168.65
  4381.6  168.14  4386.9  169.84  4468.9  166.24  4527.5  166.57  4595.4  166.05
  4616.4  164.11  4632.4  165.13  4886.7  164.53  4932.6  164.95 4945.27163.1964
  4964.2  157.45  4975.3  151.42  4990.3  151.42  4995.3  154.09  5005.5  153.31
  5011.5  157.88  5026.5  155.54  5032.5  159.45  5062.5  159.26  5068.5  161.31
  5077.5  159.32 5096.21 163.297  5113.5  166.51  5152.7  167.23  5449.3  175.36
#Mann= 8 ,-1 , 0
  4212.2     .11       0    4368     .17       0  4527.5     .11       0
  4632.4     .17       0  4886.7     .15       0 4945.27     .09       0
 5096.21     .15       0  5152.7     .17       0
Bank Sta=4945.27,5096.21
XS Rating Curve= 0 ,0
Exp/Cntr=0.3,0.1

Type RM Length L Ch R = 1 ,15491   ,454,454,454
XS GIS Cut Line= 3
      3863190.02     10109826.14      3862996.77     10109235.53
      3862598.74     10108700.54
#Sta/Elev= 30
       0  176.44   163.2  170.82   226.3  167.61   245.1  164.12   345.9  163.86
   384.1  160.56   499.8  164.34   520.9  160.37   537.1  161.58   542.4  158.07
     569  162.87   574.2  158.42   594.5   155.6   600.8  150.99   630.6  155.31
     639  160.34   651.9  162.72     689  164.09   709.9  163.54   716.1  159.96
   724.5     161   730.7  156.77   739.1  159.07   745.3  154.85   759.9  163.12
   766.2  158.74   774.5  162.66   780.8  158.99   795.4  166.69  1288.2  172.07
#Mann= 3 , 0 , 0
       0     .15       0   499.8     .09       0     689     .15       0
Bank Sta=499.8,689
XS Rating Curve= 0 ,0
Exp/Cntr=0.3,0.1

Type RM Length L Ch R = 1 ,15038   ,533,533,533
XS GIS Cut Line= 3
      3863620.57     10109271.45      3863237.74     10108953.02
      3862686.33     10108732.71
#Sta/Elev= 30
       0  175.18   122.5  169.31   179.8  162.02   208.4  160.94   229.3  153.78
   250.7   161.7   264.4  162.41   321.7  161.85     336  159.11   356.8  162.11
   399.8  161.27   420.6  163.84   449.3  163.97   457.1  158.71   463.6  160.69
   471.4  156.11   477.9   159.1   484.8  152.77   492.2  150.86   508.6  152.97
   515.3  157.88   520.7  156.53   539.6  161.38   562.4  163.63   616.3  161.26
   670.1  163.99   701.2  163.29   706.6  161.46     809   167.3  1091.8  171.45
#Mann= 3 , 0 , 0
       0     .15       0   449.3     .09       0   562.4     .15       0
Bank Sta=449.3,562.4
XS Rating Curve= 0 ,0
Exp/Cntr=0.3,0.1

Type RM Length L Ch R = 1 ,14511   ,511,511,511
BEGIN DESCRIPTION:
WEST FORK OF CRYSTAL CREEK 29.0
END DESCRIPTION:
XS GIS Cut Line= 3
      3863648.32     10109242.76      3863188.29     10108626.54
      3862992.48      10108278.2
#Sta/Elev= 30
    4231  176.19    4369  169.93  4389.8  167.85    4419  159.89  4439.9  158.87
  4469.1  161.92  4506.2  153.27  4510.7  153.87  4519.1  159.72  4532.6  162.01
  4732.3  160.98  4804.7  163.12  4840.1  160.97  4846.4  163.21  4890.2  158.75
  4925.6  161.28    4961  159.09  4969.4  157.64  4975.6  152.49  4981.9  155.76
  4990.2  152.61  4996.2  154.22  4998.2  150.02  5013.4  150.02  5027.5  159.01
  5049.2  162.28  5063.6  161.56  5092.5  165.61  5151.8  168.63  5399.6  175.05
#Mann= 4 ,-1 , 0
    4231     .17       0  4506.2     .15       0    4961     .09       0
  5027.5     .17       0
Bank Sta=4961,5027.5
XS Rating Curve= 0 ,0
Exp/Cntr=0.3,0.1

Type RM Length L Ch R = 1 ,14000   ,500,500,500
BEGIN DESCRIPTION:
WEST FORK OF CRYSTAL CREEK 28.0
END DESCRIPTION:
XS GIS Cut Line= 3
      3863758.13     10109084.43      3863545.71     10108519.33
      3863217.87      10108161.1
#Sta/Elev= 30
  4396.3  176.64  4538.8  175.74  4570.8  171.74  4664.4  165.15  4789.9  162.44
  4804.8  161.67  4827.2  158.25  4835.1  158.34  4848.6     162  4925.8  162.76
    4956  161.57  4975.6  157.93  4987.5  151.56  4987.8   149.7  4988.3   149.2
  5011.2  150.41  5025.3  156.81  5032.7  158.02  5053.7  157.95  5061.1  160.27
  5067.8  158.96  5075.2  160.43    5082  158.48  5087.8  159.98  5110.4  162.07
  5146.2  161.16  5209.7  162.31  5324.6  169.06  5407.6  173.92  5485.6  176.55
#Mann= 6 ,-1 , 0
  4396.3     .17       0  4789.9     .15       0  4975.6     .09       0
  5032.7     .15       0  5087.8     .17       0  5324.6     .11       0
Bank Sta=4975.6,5032.7
XS Rating Curve= 0 ,0
Exp/Cntr=0.3,0.1

Type RM Length L Ch R = 1 ,13500   ,500,500,500
BEGIN DESCRIPTION:
WEST FORK OF CRYSTAL CREEK 27.0
END DESCRIPTION:
XS GIS Cut Line= 3
      3864296.29     10109126.02      3863953.58     10108570.77
      3863344.89     10108056.58
#Sta/Elev= 30
  4347.5   172.4    4482   168.9  4524.6   166.2  4545.8  162.35  4567.1  160.96
  4611.8  162.53  4698.4   160.5  4741.1  164.85  4786.5  166.47  4850.9  168.69
  4924.2  164.45  4945.5  160.64  4952.6  157.15  4960.9  156.96  4976.1  158.94
  4982.2  157.87  4996.9  153.11    5000  153.11  5002.5  148.56  5018.8  148.56
    5025  155.16  5032.7  157.42  5096.4  161.58  5131.6  160.44  5152.4  162.37
  5240.8  161.82  5330.5   162.5  5379.9  161.02  5457.9   161.5  5796.8  173.02
#Mann= 5 ,-1 , 0
  4347.5     .17       0  4786.5     .15       0  4982.2     .09       0
  5032.7     .15       0  5240.8     .11       0
Bank Sta=4982.2,5032.7
XS Rating Curve= 0 ,0
Exp/Cntr=0.3,0.1

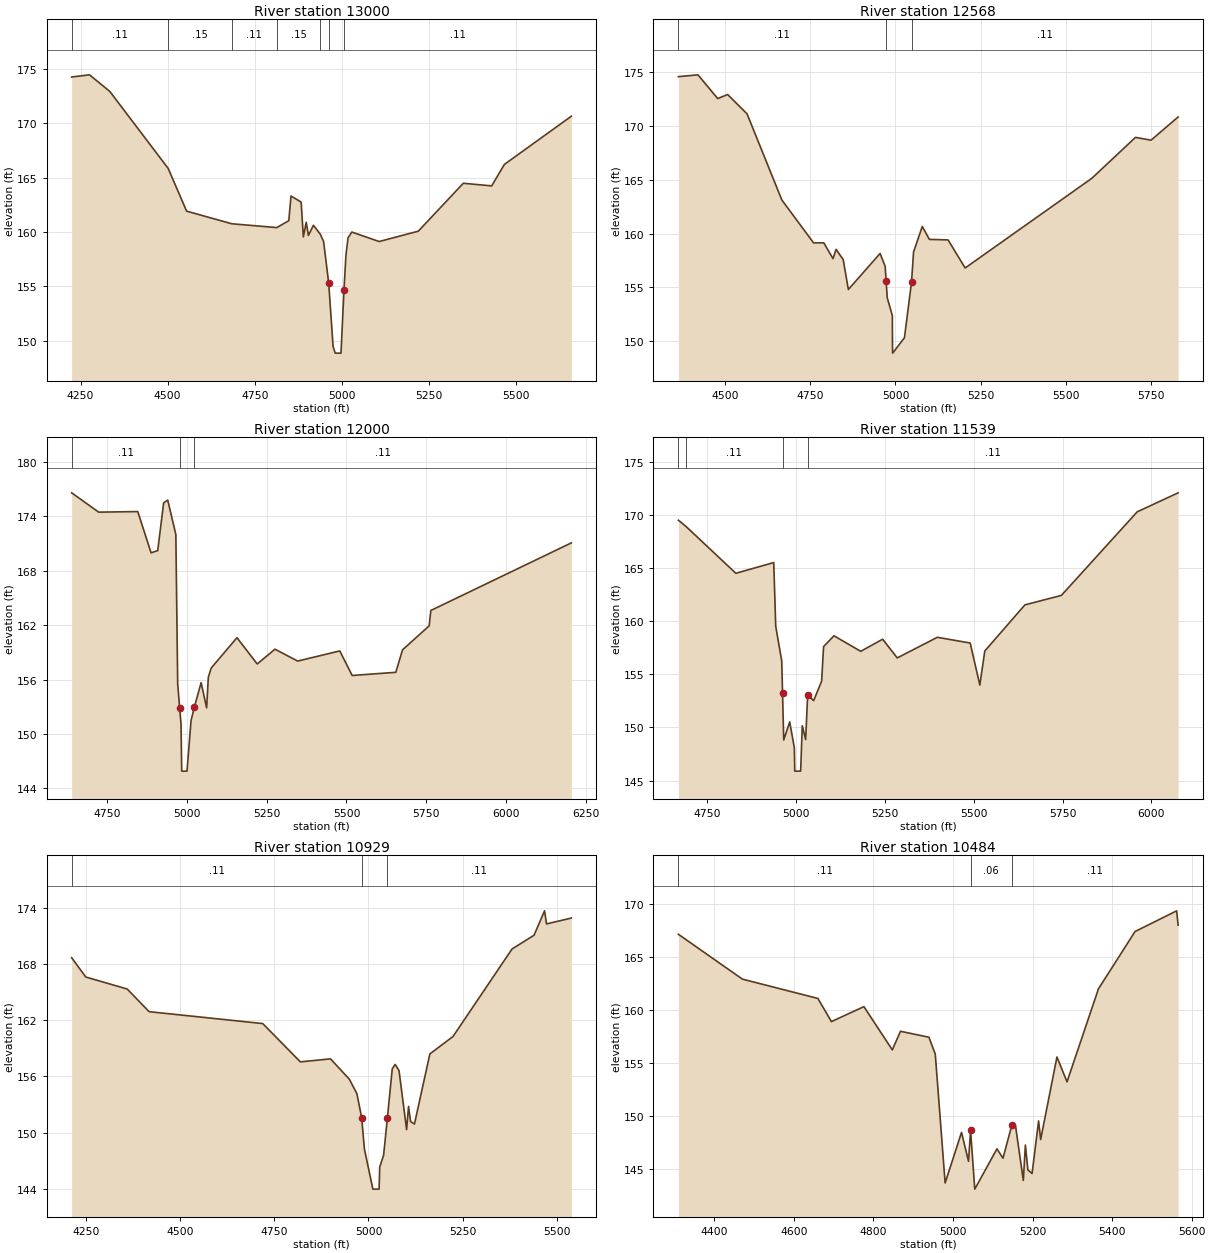
Type RM Length L Ch R = 1 ,13000   ,432,432,432
BEGIN DESCRIPTION:
WEST FORK OF CRYSTAL CREEK 26.0
END DESCRIPTION:
XS GIS Cut Line= 3
      3864511.62      10108799.7      3864043.78     10108181.09
      3863452.67       10107890.
#Sta/Elev= 30
  4224.4  174.24  4275.6  174.44  4333.8  172.92  4501.6  165.84  4554.4  161.92
  4684.1  160.76  4813.1  160.41  4847.8  161.04  4854.1  163.31  4883.2  162.75
  4889.5  159.56  4897.8   160.9    4904  159.69  4918.6  160.62    4938  159.81
  4947.7  159.13  4962.3  155.31  4974.9  149.48  4981.1  148.88  4997.6  148.88
  5006.2  154.71  5011.8  157.88  5017.8  159.47  5028.7     160  5107.2  159.13
  5219.5  160.08  5348.7  164.48  5430.2  164.24  5466.6  166.21  5658.9  170.64
#Mann= 7 ,-1 , 0
  4224.4     .11       0  4501.6     .15       0  4684.1     .11       0
  4813.1     .15       0    4938     .11       0  4962.3     .09       0
  5006.2     .11       0
Bank Sta=4962.3,5006.2
XS Rating Curve= 0 ,0
Exp/Cntr=0.3,0.1

Type RM Length L Ch R = 1 ,12568   ,568,568,568
BEGIN DESCRIPTION:
WEST FORK OF CRYSTAL CREEK 25.0
END DESCRIPTION:
XS GIS Cut Line= 3
       3864824.1     10108195.51      3864292.72     10107842.58
      3863502.06     10107588.14
#Sta/Elev= 30
  4362.1  174.61  4419.5  174.78  4477.6  172.57  4506.7  172.95  4563.8  171.15
    4666  163.14  4759.2  159.15  4789.3  159.15  4816.4  157.68  4825.4  158.54
  4846.4  157.59  4861.5  154.81  4954.7  158.16  4969.7  156.96 4972.56 155.573
  4975.7  154.05  4990.8  152.38  4991.2  149.39  4991.7  148.89  5026.3  150.32
  5047.1  155.48  5053.1  158.29  5078.7  160.67  5099.7  159.47  5154.6  159.42
  5204.7  156.81  5576.9  165.15  5705.2  168.96    5751   168.7  5830.6  170.86
#Mann= 3 , 0 , 0
  4362.1     .11       0 4972.56     .09       0  5047.1     .11       0
Bank Sta=4972.56,5047.1
XS Rating Curve= 0 ,0
Exp/Cntr=0.3,0.1

Type RM Length L Ch R = 1 ,12000   ,461,461,461
BEGIN DESCRIPTION:
WEST FORK OF CRYSTAL CREEK 24.0
END DESCRIPTION:
XS GIS Cut Line= 3
      3865086.61     10107809.63      3864739.61     10107705.81
      3863594.92     10107327.44
#Sta/Elev= 30
  4637.8   176.6  4722.6  174.47  4845.3  174.53    4887  169.98  4907.9  170.23
  4926.4  175.49  4939.2   175.8  4964.7  172.01  4970.5  155.53  4976.7152.8787
    4981  151.04  4983.1   145.9  4999.7   145.9  5012.4  151.48  5022.9  152.98
    5044  155.66  5061.3  152.88  5066.6  156.25  5075.6  157.27  5156.5  160.62
    5220  157.72  5275.7  159.35  5346.9  158.04  5479.1  159.16  5517.9  156.45
  5654.8   156.8  5675.9  159.28  5759.4  161.92  5764.7  163.62  6205.6  171.08
#Mann= 3 , 0 , 0
  4637.8     .11       0  4976.7     .09       0  5022.9     .11       0
Bank Sta=4976.7,5022.9
XS Rating Curve= 0 ,0
Exp/Cntr=0.3,0.1

Type RM Length L Ch R = 1 ,11539   ,610,610,610
BEGIN DESCRIPTION:
WEST FORK OF CRYSTAL CREEK 23.0
END DESCRIPTION:
XS GIS Cut Line= 3
      3865000.33     10107155.84      3864568.48     10107368.98
      3863667.82     10107160.77
#Sta/Elev= 30
  4669.3  169.49  4690.2  168.92  4830.9   164.5  4937.5  165.51  4943.1  159.51
    4960  156.25 4962.26153.2518  4965.6  148.82  4982.4  150.52  4995.5  148.08
  4996.6  145.89  5013.2  145.89  5017.8  150.16  5027.3  148.86  5032.9  153.03
  5049.8  152.52  5072.2  154.35  5077.8  157.61    5107  158.62  5182.3  157.16
  5243.9   158.3    5285  156.54  5397.9  158.48  5490.2  157.94  5517.4  153.99
  5531.3  157.19  5644.2  161.53  5746.8  162.42  5960.1  170.28  6075.3  172.07
#Mann= 4 ,-1 , 0
  4669.3     .17       0  4690.2     .11       0 4962.26     .09       0
  5032.9     .11       0
Bank Sta=4962.26,5032.9
XS Rating Curve= 0 ,0
Exp/Cntr=0.3,0.1

Type RM Length L Ch R = 1 ,10929   ,445,445,445
BEGIN DESCRIPTION:
WEST FORK OF CRYSTAL CREEK 22.0
END DESCRIPTION:
XS GIS Cut Line= 3
      3865045.44     10107041.28      3864256.95     10107059.39
      3863731.12     10106940.95
#Sta/Elev= 30
  4211.3  168.67  4248.9  166.61  4358.9  165.33  4417.1  162.91    4719  161.64
    4819  157.55  4899.1  157.87  4949.1   155.7  4969.1  154.16 4981.81151.6061
  4989.1  148.26  5011.6  143.96  5028.2  143.96  5029.8  146.32  5040.1  147.57
  5050.3  151.59  5063.1   156.8  5070.8  157.28  5081.1  156.62  5101.3  150.31
  5106.4  152.79  5111.8  151.18  5122.1  150.91  5163.1   158.4  5224.6  160.26
  5381.3   169.6  5439.8  171.07  5467.8  173.68    5473  172.28    5539  172.91
#Mann= 3 , 0 , 0
  4211.3     .11       0 4981.81     .09       0  5050.3     .11       0
Bank Sta=4981.81,5050.3
XS Rating Curve= 0 ,0
Exp/Cntr=0.3,0.1

Type RM Length L Ch R = 1 ,10484   ,484,484,484
BEGIN DESCRIPTION:
WEST FORK OF CRYSTAL CREEK 21.0
END DESCRIPTION:
XS GIS Cut Line= 3
      3865104.45     10106878.08      3864420.98     10106735.56
      3863885.83     10106576.03
#Sta/Elev= 30
  4309.5  167.13  4470.4  162.91  4660.3  161.09  4694.2  158.91  4775.9  160.32
  4847.4  156.25  4867.9     158  4939.4  157.44  4955.4  155.85  4980.2  143.72
  5021.4  148.48    5039  145.76  5044.2  148.66  5054.7  143.14  5110.5  146.93
  5125.7  146.05 5147.85149.1504    5157  149.15  5176.8  143.96    5182  147.29
  5188.3  144.95  5198.8  144.61  5215.2  149.56  5220.4  147.81  5261.4  155.58
  5286.7  153.24  5365.7  161.99  5457.7  167.39  5562.4  169.34  5566.1  167.99
#Mann= 3 , 0 , 0
  4309.5     .11       0  5044.2     .06       0 5147.85     .11       0
Bank Sta=5044.2,5147.85
XS Rating Curve= 0 ,0
Exp/Cntr=0.3,0.1

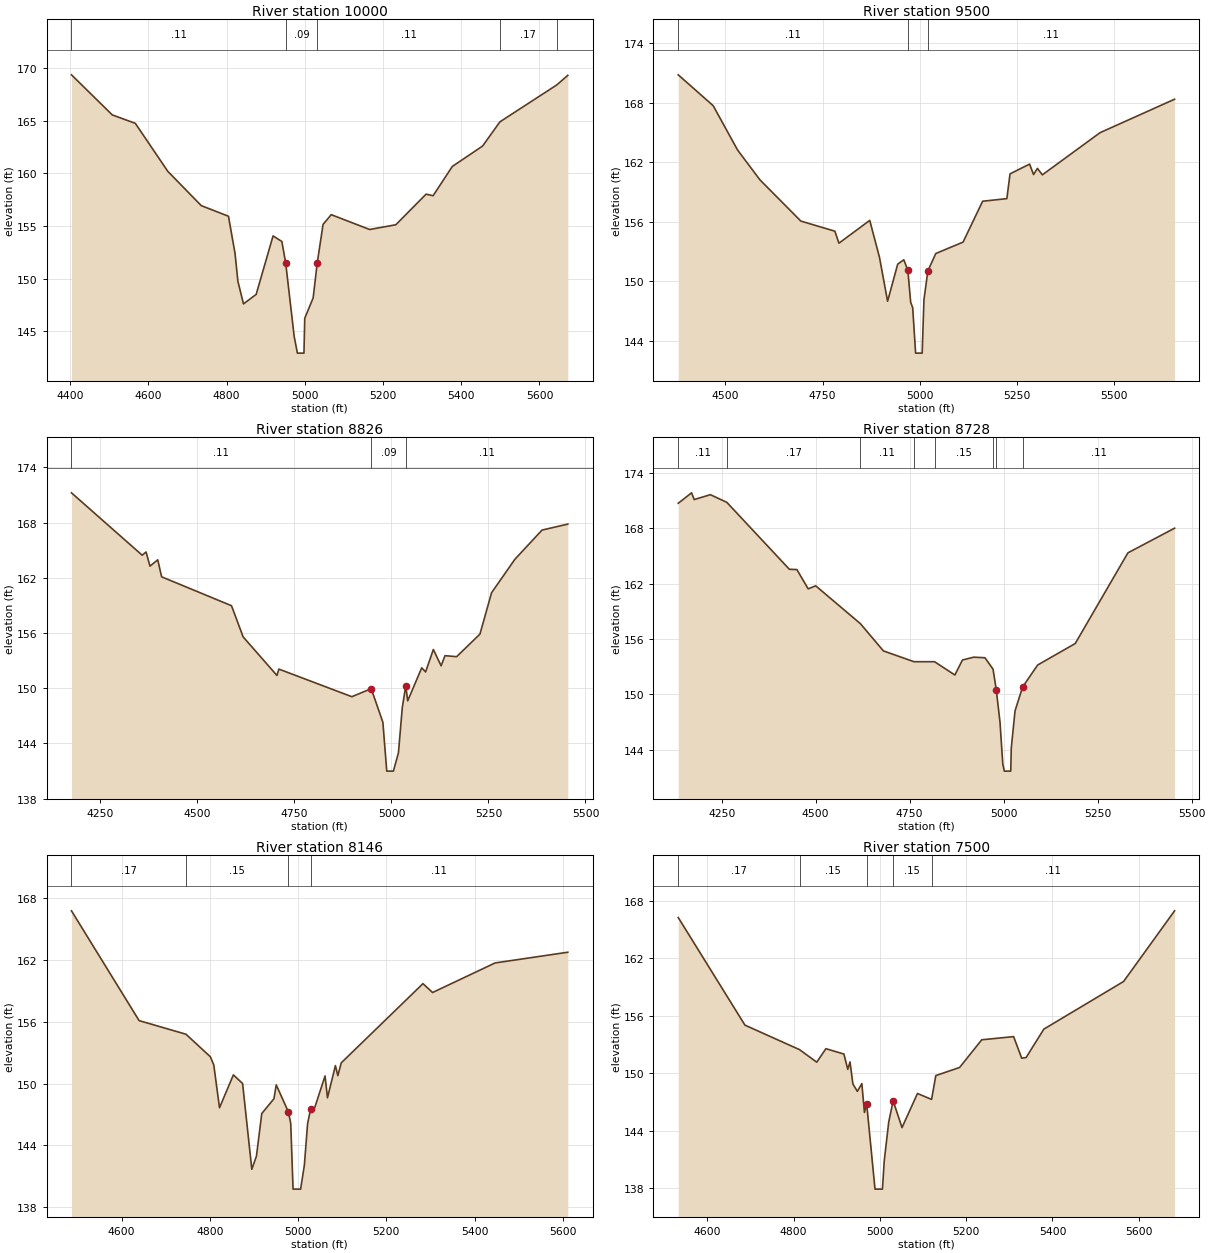
Type RM Length L Ch R = 1 ,10000   ,500,500,500
BEGIN DESCRIPTION:
WEST FORK OF CRYSTAL CREEK 20.0
END DESCRIPTION:
XS GIS Cut Line= 3
      3865225.09     10106617.21      3864672.84     10106392.28
      3864027.22     10106204.04
#Sta/Elev= 30
  4403.7  169.37    4508  165.56  4566.9  164.76  4649.9   160.2  4735.4  156.94
    4805  155.93  4821.8   152.4  4829.1  149.75  4843.4   147.6  4875.8   148.5
    4919  154.06  4941.5  153.53  4951.4  151.46    4973  144.51  4981.2  142.92
    4998  142.92    5000  146.23  5021.5  148.17 5031.81151.4609  5046.9  155.16
  5067.7  156.08  5165.9  154.67  5232.8  155.12  5310.2  158.03  5328.1  157.88
  5377.2  160.66  5454.6   162.6  5498.9   164.9  5644.3  168.41  5672.5  169.32
#Mann= 5 ,-1 , 0
  4403.7     .11       0  4951.4     .09       0 5031.81     .11       0
  5498.9     .17       0  5644.3     .11       0
Bank Sta=4951.4,5031.81
XS Rating Curve= 0 ,0
Exp/Cntr=0.3,0.1

Type RM Length L Ch R = 1 ,9500    ,674,674,674
BEGIN DESCRIPTION:
WEST FORK OF CRYSTAL CREEK 19.0
END DESCRIPTION:
XS GIS Cut Line= 3
      3865364.01     10106155.42       3864768.4     10105980.01
      3864117.48     10105908.89
#Sta/Elev= 30
  4379.1  170.82  4468.9  167.71  4531.5  163.25    4589  160.24  4694.2  156.08
  4781.7  155.06  4792.1  153.85  4871.3  156.15  4896.3  152.43  4917.2     148
  4943.2  151.74  4958.9  152.18  4969.3   151.1  4976.5   147.9  4981.7  147.35
  4989.2  142.77  5006.1  142.77  5010.6  148.13  5020.7  151.06  5041.1  152.81
  5111.2  153.96  5161.5  158.08  5223.7  158.34  5231.9  160.84  5282.2  161.82
  5292.3  160.77  5302.3  161.39    5315  160.74  5463.3  164.99  5654.8  168.36
#Mann= 3 , 0 , 0
  4379.1     .11       0  4969.3     .09       0  5020.7     .11       0
Bank Sta=4969.3,5020.7
XS Rating Curve= 0 ,0
Exp/Cntr=0.3,0.1

Type RM Length L Ch R = 1 ,8826    ,98,98,98
BEGIN DESCRIPTION:
WEST FORK OF CRYSTAL CREEK 18.0
END DESCRIPTION:
XS GIS Cut Line= 3
      3865420.01     10105492.55       3864595.8     10105466.99
      3864141.42     10105456.83
#Sta/Elev= 30
  4175.4  171.24  4357.6  164.46  4367.6  164.81  4377.7  163.27  4397.7  163.96
  4407.7  162.11  4587.8  158.97  4617.8  155.58  4704.9  151.39  4709.9  152.08
  4897.9  149.08  4947.9  149.95  4977.9   146.3  4987.9  140.99    5005  140.99
    5018  142.98    5028  147.92  5036.9  150.27  5041.9  148.63    5078  152.22
    5088  151.77    5108  154.21    5128  152.44    5138  153.54    5168  153.43
    5228  155.88    5258  160.38    5318  164.01    5388  167.19  5454.5  167.84
#Mann= 3 , 0 , 0
  4175.4     .11       0  4947.9     .09       0  5036.9     .11       0
Bank Sta=4947.9,5036.9
XS Rating Curve= 0 ,0
Exp/Cntr=0.3,0.1

Type RM Length L Ch R = 1 ,8728    ,582,582,582
BEGIN DESCRIPTION:
WEST FORK OF CRYSTAL CREEK 17.0
END DESCRIPTION:
XS GIS Cut Line= 3
      3865443.35     10105397.31      3864578.18     10105373.21
      3864123.83     10105358.24
#Sta/Elev= 30
  4134.5  170.69    4170  171.82    4177  171.09    4220  171.62  4263.7  170.79
  4430.1  163.54  4450.1  163.51  4480.1  161.42  4500.1  161.75    4619  157.65
  4680.2   154.7  4761.6  153.53  4816.2  153.53  4870.3  152.09  4890.3  153.71
  4920.3  154.02  4950.3  153.96  4971.8  152.72  4980.3  150.52  4990.3  146.98
  4997.7  142.46  5001.8  141.68  5018.9  141.68  5020.3   144.2  5030.3  148.21
  5050.4  150.79  5090.4  153.17  5190.4   155.5  5330.5  165.32  5454.6  167.99
#Mann= 8 ,-1 , 0
  4134.5     .11       0  4263.7     .17       0    4619     .11       0
  4761.6     .17       0  4816.2     .15       0  4971.8     .11       0
  4980.3     .09       0  5050.4     .11       0
Bank Sta=4980.3,5050.4
XS Rating Curve= 0 ,0
Exp/Cntr=0.3,0.1

Type RM Length L Ch R = 1 ,8146    ,646,646,646
BEGIN DESCRIPTION:
WEST FORK OF CRYSTAL CREEK 16.0
END DESCRIPTION:
XS GIS Cut Line= 3
      3865048.72     10104751.03      3864557.64     10104901.11
      3863996.67     10105144.25
#Sta/Elev= 30
  4486.5  166.77  4639.8  156.11  4745.9  154.79  4801.1  152.61    4809  151.81
    4822  147.65  4853.4  150.84  4874.3  150.01  4895.2  141.68  4905.7  142.95
  4917.8  147.09  4945.4  148.53  4950.6  149.87  4978.2  147.24  4983.4  146.14
  4988.7  139.75  5005.8  139.75  5014.3  142.07  5021.6   146.1  5028.6  147.55
  5037.8  147.66  5061.2  150.74  5066.7  148.62  5084.7  151.74  5090.2  150.77
  5097.9  152.01  5283.1   159.7  5304.9  158.84  5446.6  161.71  5611.4  162.75
#Mann= 4 ,-1 , 0
  4486.5     .17       0  4745.9     .15       0  4978.2     .09       0
  5028.6     .11       0
Bank Sta=4978.2,5028.6
XS Rating Curve= 0 ,0
Exp/Cntr=0.3,0.1

Type RM Length L Ch R = 1 ,7500    ,500,500,500
BEGIN DESCRIPTION:
WEST FORK OF CRYSTAL CREEK 15.0
END DESCRIPTION:
XS GIS Cut Line= 3
      3865066.14      10104547.9      3864617.88     10104416.23
      3863952.83     10104571.77
#Sta/Elev= 30
  4532.8  166.25  4687.4  155.01  4813.9  152.45  4853.8  151.14    4875  152.55
  4916.7  151.99  4925.7  150.39  4930.9  151.17  4937.5  148.87  4947.9  148.09
  4958.3   148.9  4964.3  145.89  4969.5  146.79  4988.8  137.88    5006  137.88
  5010.3  140.88  5020.6  144.89  5030.8   147.1  5051.4  144.31  5087.2  147.87
  5119.9  147.25  5129.7  149.74  5184.9  150.59  5236.2  153.48    5310  153.81
  5328.7  151.56  5338.9  151.62    5380  154.59  5564.9  159.57    5683  166.95
#Mann= 5 ,-1 , 0
  4532.8     .17       0  4813.9     .15       0  4969.5     .09       0
  5030.8     .15       0  5119.9     .11       0
Bank Sta=4969.5,5030.8
XS Rating Curve= 0 ,0
Exp/Cntr=0.3,0.1