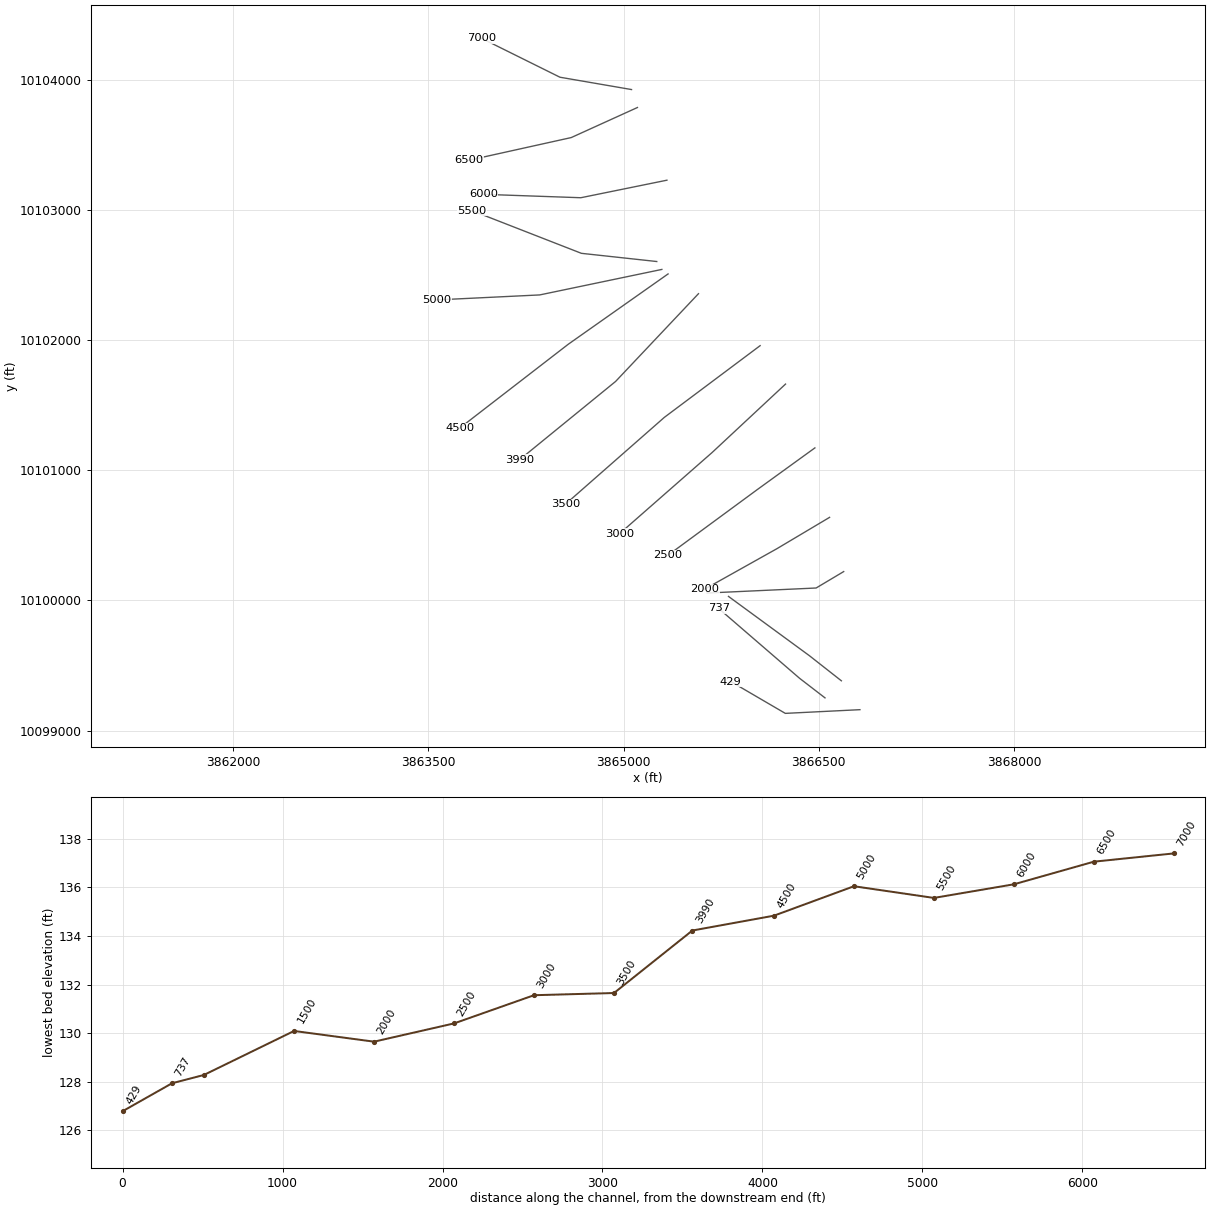
HEC-RAS study WEST FORK OF CRYSTAL CREEK.prj: WEST FORK OF CRYSTAL CREEK Base Level Engineering

--- WEST FORK OF CRYSTAL CREEK.g01 (geometry) --- (continued)

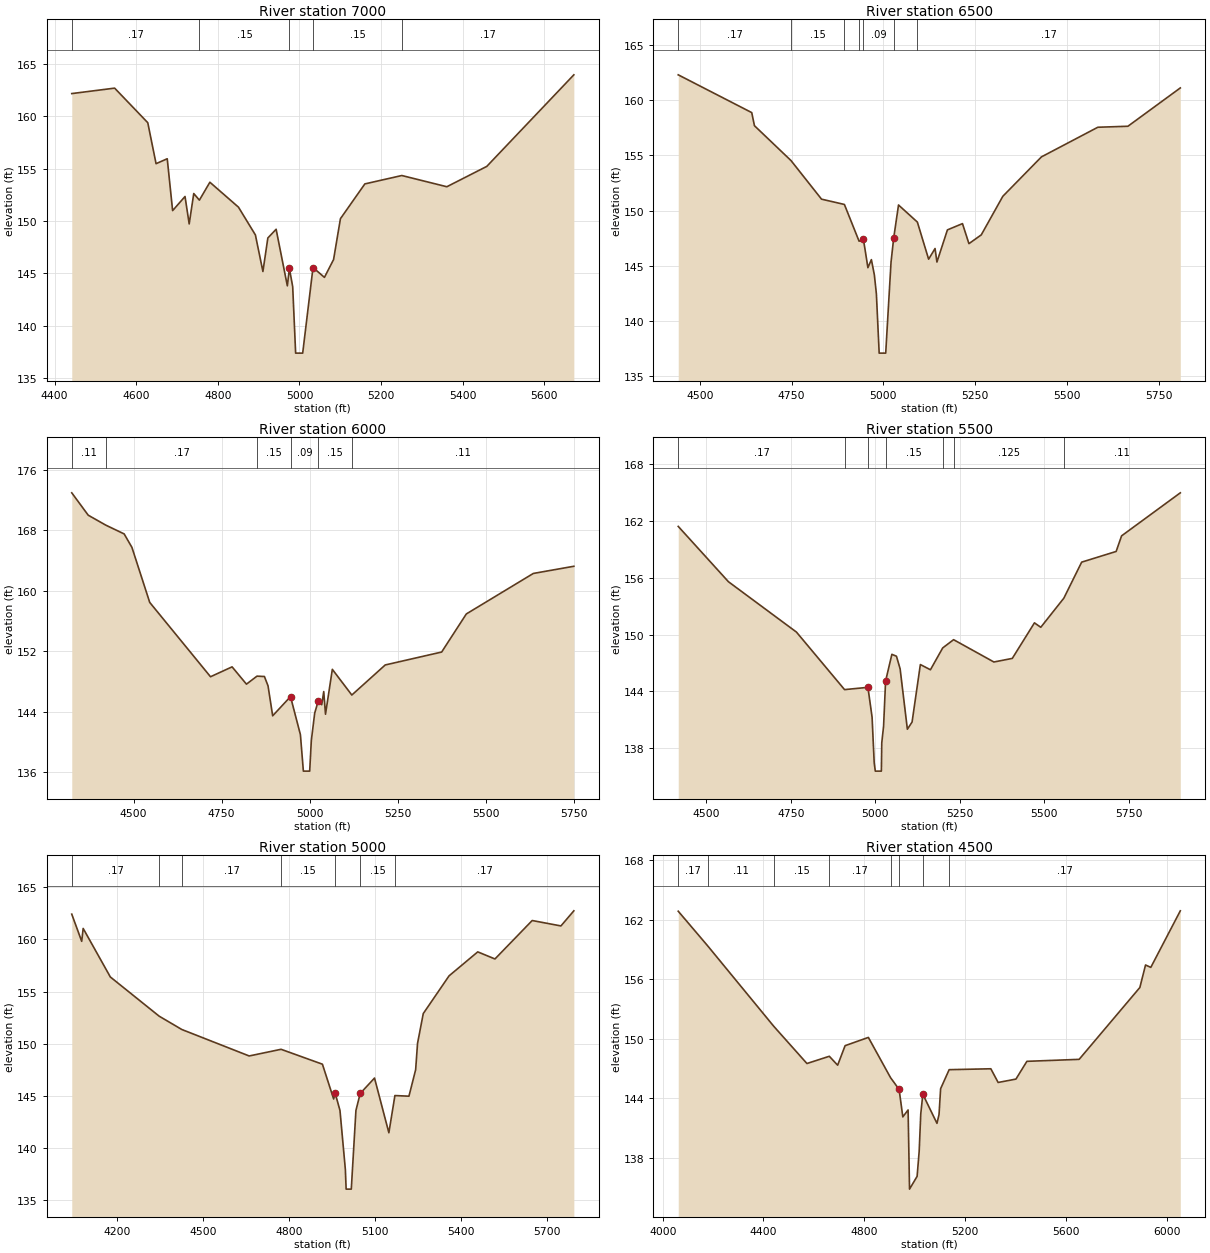
Type RM Length L Ch R = 1 ,7000    ,500,500,500
BEGIN DESCRIPTION:
WEST FORK OF CRYSTAL CREEK 14.0
END DESCRIPTION:
XS GIS Cut Line= 3
      3865061.45     10103925.99      3864511.45     10104020.76
        3863909.      10104319.6
#Sta/Elev= 30
  4441.9  162.16    4547  162.68  4628.2  159.38  4648.5  155.47  4675.9  155.94
  4689.1  150.99  4719.5  152.34  4729.7  149.72  4740.9  152.62  4754.7  151.99
  4780.4   153.7  4850.5  151.32    4892  148.67  4910.4  145.18  4922.5  148.38
  4942.8  149.21  4970.3  143.81  4975.3  145.48  4983.4  143.73  4990.6  137.39
  5007.9  137.39  5033.2  145.56  5061.2  144.62  5083.6  146.32  5100.4  150.22
  5160.3  153.54  5250.9  154.34  5361.2  153.27  5459.1  155.21  5672.5  163.95
#Mann= 5 ,-1 , 0
  4441.9     .17       0  4754.7     .15       0  4975.3     .09       0
  5033.2     .15       0  5250.9     .17       0
Bank Sta=4975.3,5033.2
XS Rating Curve= 0 ,0
Exp/Cntr=0.3,0.1

Type RM Length L Ch R = 1 ,6500    ,500,500,500
BEGIN DESCRIPTION:
WEST FORK OF CRYSTAL CREEK 13.0
END DESCRIPTION:
XS GIS Cut Line= 3
       3865106.9     10103788.05      3864598.11     10103556.97
      3863808.58     10103381.95
#Sta/Elev= 30
  4441.2  162.32  4641.4  158.89  4648.8   157.7  4748.5  154.53  4831.5  151.03
  4893.8  150.55  4933.8  147.21  4945.4  147.43  4957.8  144.81  4967.3  145.54
  4975.4  144.15  4980.9  142.43  4988.5  137.05  5006.3  137.05  5020.8  145.31
  5028.1147.5144  5041.2   150.5  5092.5  148.95  5123.2  145.58  5140.7  146.55
  5145.8  145.32  5174.4  148.24  5215.4  148.81    5233  146.99  5266.6  147.79
  5325.3  151.29  5430.5  154.87  5584.1  157.56    5666  157.65  5808.7  161.13
#Mann= 7 ,-1 , 0
  4441.2     .17       0  4748.5     .15       0  4893.8     .17       0
  4933.8     .15       0  4945.4     .09       0  5028.1     .15       0
  5092.5     .17       0
Bank Sta=4945.4,5028.1
XS Rating Curve= 0 ,0
Exp/Cntr=0.3,0.1

Type RM Length L Ch R = 1 ,6000    ,500,500,500
BEGIN DESCRIPTION:
WEST FORK OF CRYSTAL CREEK 12.0
END DESCRIPTION:
XS GIS Cut Line= 3
      3865333.59     10103229.42      3864671.87     10103094.65
      3863922.93      10103120.9
#Sta/Elev= 30
  4324.7  172.95  4371.4  169.99  4421.4  168.67  4473.4  167.51  4495.4  165.73
  4545.9  158.45  4718.4  148.61  4779.6  149.92  4820.4  147.63  4850.3  148.69
  4871.4  148.64  4881.6  147.41  4894.8  143.44  4945.4  145.98  4973.5  140.95
  4981.9  136.12  4999.8  136.12  5004.5  140.17    5014  143.79    5024  145.39
    5034  144.91  5039.7  146.65  5044.7  143.65  5064.1  149.59  5119.4  146.19
  5214.2  150.17  5374.3  151.88  5444.3  156.92  5634.4  162.28  5749.4  163.23
#Mann= 6 ,-1 , 0
  4324.7     .11       0  4421.4     .17       0  4850.3     .15       0
  4945.4     .09       0    5024     .15       0  5119.4     .11       0
Bank Sta=4945.4,5024
XS Rating Curve= 0 ,0
Exp/Cntr=0.3,0.1

Type RM Length L Ch R = 1 ,5500    ,500,500,500
BEGIN DESCRIPTION:
WEST FORK OF CRYSTAL CREEK 11.0
END DESCRIPTION:
XS GIS Cut Line= 3
      3865255.39     10102604.41       3864676.2     10102667.39
      3863836.14     10102995.04
#Sta/Elev= 30
  4417.4  161.44  4565.8  155.59    4767  150.26  4909.1  144.18  4978.2  144.42
  4990.5  141.26  4996.7  136.46    5000  135.56  5017.9  135.56  5019.1  138.55
  5024.5  140.32  5030.4  145.08    5049  147.91  5062.6  147.71  5073.4  146.37
  5094.8  139.99  5108.7  140.75  5133.2  146.83    5163  146.28  5199.3  148.59
  5231.5  149.46  5350.6   147.1    5405  147.48  5470.5  151.24  5489.2  150.77
  5557.4  153.85  5610.1  157.66    5712  158.79  5728.1  160.44  5901.7  164.99
#Mann= 7 ,-1 , 0
  4417.4     .17       0  4909.1     .15       0  4978.2     .09       0
  5030.4     .15       0  5199.3     .11       0  5231.5    .125       0
  5557.4     .11       0
Bank Sta=4978.2,5030.4
XS Rating Curve= 0 ,0
Exp/Cntr=0.3,0.1

Type RM Length L Ch R = 1 ,5000    ,500,500,500
BEGIN DESCRIPTION:
WEST FORK OF CRYSTAL CREEK 10.0
END DESCRIPTION:
XS GIS Cut Line= 3
      3865294.51     10102543.65      3864356.06      10102347.7
      3863562.78     10102309.28
#Sta/Elev= 30
  4041.3  162.43    4076  159.82  4081.1  161.06    4176   156.4  4346.4  152.64
  4425.5  151.36  4660.7  148.82    4772  149.46  4916.4  148.03  4955.6  144.69
  4960.7  145.27  4977.7  143.59  4996.5  137.92  4999.2  136.04  5017.2  136.04
  5033.4  143.59  5048.3  145.22  5098.3   146.7  5148.4  141.45  5169.5  145.02
  5218.5  144.96  5241.9   147.5  5248.5  150.03  5268.5  152.89  5358.6  156.51
  5458.7  158.81  5518.8  158.13  5648.8  161.82  5749.1   161.3  5794.2  162.75
#Mann= 7 ,-1 , 0
  4041.3     .17       0  4346.4     .11       0  4425.5     .17       0
    4772     .15       0  4960.7     .09       0  5048.3     .15       0
  5169.5     .17       0
Bank Sta=4960.7,5048.3
XS Rating Curve= 0 ,0
Exp/Cntr=0.3,0.1

Type RM Length L Ch R = 1 ,4500    ,510,510,510
BEGIN DESCRIPTION:
WEST FORK OF CRYSTAL CREEK 9.0
END DESCRIPTION:
XS GIS Cut Line= 3
      3865342.24     10102508.94      3864575.08      10101968.5
      3863740.68     10101324.05
#Sta/Elev= 30
  4061.6  162.84  4178.8  159.34  4440.5  151.25  4572.4  147.49  4661.2  148.22
  4694.3  147.32  4723.9  149.29  4816.2  150.12  4904.4  146.06  4938.2  144.88
    4953  142.11  4973.9  142.81  4979.6  134.83  5009.7  136.12  5017.9  138.65
  5024.2  142.42  5032.4  144.39  5088.5  141.46  5096.7  142.35    5103  144.95
  5136.9  146.87  5302.3  146.96  5331.3  145.58  5401.9  145.92  5445.4  147.71
  5652.8  147.91  5893.7  155.15  5916.3  157.42  5937.2  157.18  6054.3  162.88
#Mann= 8 ,-1 , 0
  4061.6     .17       0  4178.8     .11       0  4440.5     .15       0
  4661.2     .17       0  4904.4     .15       0  4938.2     .09       0
  5032.4     .15       0  5136.9     .17       0
Bank Sta=4938.2,5032.4
XS Rating Curve= 0 ,0
Exp/Cntr=0.3,0.1

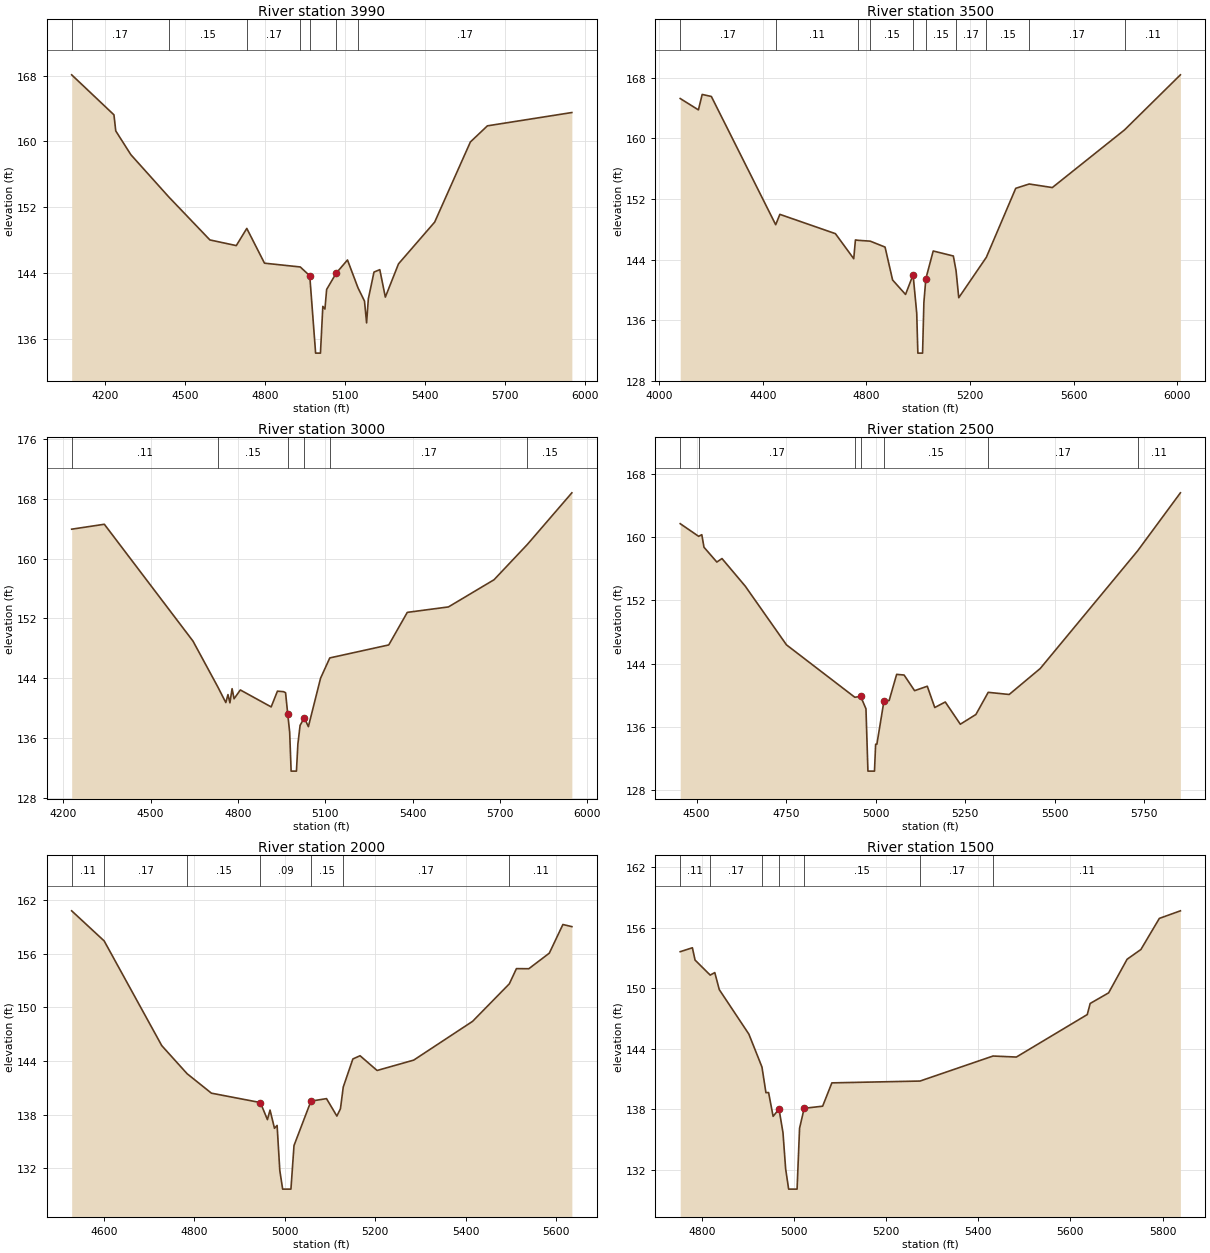
Type RM Length L Ch R = 1 ,3990    ,490,490,490
BEGIN DESCRIPTION:
WEST FORK OF CRYSTAL CREEK 8.0
END DESCRIPTION:
XS GIS Cut Line= 3
      3865575.92      10102357.2      3864939.02     10101682.74
      3864201.76     10101081.81
#Sta/Elev= 30
  4073.7   168.1  4232.5  163.23  4239.3  161.27    4296  158.38  4438.3  153.24
  4592.9     148    4692  147.31  4731.5   149.4    4798  145.17  4932.3  144.71
    4968  143.64    4990  134.22  5008.2  134.22  5017.1  139.91    5025  139.59
  5031.4  141.97  5067.4  143.96  5109.7  145.56  5149.3  142.16  5173.6  140.56
  5181.5   137.9    5188  140.82  5209.3  144.09  5231.1  144.38  5251.9  141.04
  5301.4  145.09  5437.2  150.17  5571.4  159.93  5635.3  161.89  5952.5  163.51
#Mann= 7 ,-1 , 0
  4073.7     .17       0  4438.3     .15       0  4731.5     .17       0
  4932.3     .15       0    4968     .09       0  5067.4     .15       0
  5149.3     .17       0
Bank Sta=4968,5067.4
XS Rating Curve= 0 ,0
Exp/Cntr=0.3,0.1

Type RM Length L Ch R = 1 ,3500    ,500,500,500
BEGIN DESCRIPTION:
WEST FORK OF CRYSTAL CREEK 7.0
END DESCRIPTION:
XS GIS Cut Line= 3
      3866049.72     10101957.73      3865313.64     10101406.68
      3864552.55     10100738.32
#Sta/Elev= 30
  4080.5  165.28  4150.8  163.78  4165.4  165.82  4200.8  165.55  4449.4  148.61
  4465.4  149.98  4680.1  147.43  4750.9  144.12  4757.4   146.6    4768  146.55
  4814.7  146.44  4871.8  145.66    4901  141.31    4951   139.4  4980.2     142
  4994.2  136.94  4998.6  131.65  5016.8  131.65  5021.9  138.35  5029.4  141.47
  5057.9  145.14  5135.7  144.48  5146.2  142.53  5156.6  138.97  5263.2  144.31
  5376.7  153.42  5428.6  153.99  5518.1  153.52  5797.2  161.14  6012.9  168.41
#Mann= 10 ,-1 , 0
  4080.5     .17       0  4449.4     .11       0    4768     .17       0
  4814.7     .15       0  4980.2     .09       0  5029.4     .15       0
  5146.2     .17       0  5263.2     .15       0  5428.6     .17       0
  5797.2     .11       0
Bank Sta=4980.2,5029.4
XS Rating Curve= 0 ,0
Exp/Cntr=0.3,0.1

Type RM Length L Ch R = 1 ,3000    ,500,500,500
BEGIN DESCRIPTION:
WEST FORK OF CRYSTAL CREEK 6.0
END DESCRIPTION:
XS GIS Cut Line= 3
        3866245.     10101662.57      3865681.04     10101136.84
      3864968.95     10100512.39
#Sta/Elev= 30
    4229  163.96  4341.2  164.62  4645.6  148.98  4730.4  142.88  4758.5  140.74
  4765.8  141.81  4772.6  140.71    4780   142.6  4786.8  141.25  4808.3  142.43
  4914.3  140.16  4935.8  142.27  4956.8   142.2  4963.7  142.06    4971  139.26
  4977.8  136.78  4982.8  131.56  5001.1  131.56    5006  135.18  5013.6  137.68
  5027.8  138.69  5042.1  137.52    5084  144.01  5115.6  146.72  5318.2  148.46
  5381.8  152.82  5523.2  153.55  5679.8  157.19  5794.3  161.92  5947.1  168.83
#Mann= 6 ,-1 , 0
    4229     .11       0  4730.4     .15       0    4971     .09       0
  5027.8     .15       0  5115.6     .17       0  5794.3     .15       0
Bank Sta=4971,5027.8
XS Rating Curve= 0 ,0
Exp/Cntr=0.3,0.1

Type RM Length L Ch R = 1 ,2500    ,500,500,500
BEGIN DESCRIPTION:
WEST FORK OF CRYSTAL CREEK 5.0
END DESCRIPTION:
XS GIS Cut Line= 3
       3866470.7     10101172.12      3866028.48     10100852.05
      3865342.54      10100347.7
#Sta/Elev= 30
  4454.1  161.68  4505.6  160.08  4514.4  160.29  4520.5   158.7  4556.4  156.83
  4570.8  157.27  4635.8  153.78    4751  146.36  4941.8  139.74  4958.3  139.84
    4973  138.27  4978.5   130.4  4996.8   130.4    5000   133.8  5003.5   133.8
  5023.2  139.25  5037.8  139.33  5058.7  142.63  5079.5  142.55  5108.8  140.57
  5144.3  141.13  5165.2  138.44  5194.5  139.14  5236.6  136.33  5280.1  137.56
  5314.5  140.36  5373.1  140.09  5459.8  143.37  5731.8  158.24  5851.4  165.58
#Mann= 7 ,-1 , 0
  4454.1     .11       0  4505.6     .17       0  4941.8     .15       0
  4958.3     .09       0  5023.2     .15       0  5314.5     .17       0
  5731.8     .11       0
Bank Sta=4958.3,5023.2
XS Rating Curve= 0 ,0
Exp/Cntr=0.3,0.1

Type RM Length L Ch R = 1 ,2000    ,500,500,500
BEGIN DESCRIPTION:
WEST FORK OF CRYSTAL CREEK 4.0
END DESCRIPTION:
XS GIS Cut Line= 3
      3866583.55     10100638.27      3866178.23     10100397.18
      3865624.34     10100087.05
#Sta/Elev= 30
  4528.4   160.8  4600.3  157.43  4727.7  145.71  4783.7  142.57  4837.5  140.39
  4945.8  139.34  4961.4  137.43  4967.2   138.5    4977  136.46  4982.8  136.78
  4988.8  131.73  4995.1  129.65  5013.4  129.65  5020.2  134.53  5057.7   139.5
  5092.1  139.78    5115  137.83  5122.9  138.64  5129.1  141.07  5150.4  144.22
  5166.3  144.58    5204  142.93    5285  144.09  5415.2  148.43  5496.5  152.63
  5512.2  154.33  5539.6  154.32  5584.9  156.06    5615  159.27  5634.8  159.03
#Mann= 7 ,-1 , 0
  4528.4     .11       0  4600.3     .17       0  4783.7     .15       0
  4945.8     .09       0  5057.7     .15       0  5129.1     .17       0
  5496.5     .11       0
Bank Sta=4945.8,5057.7
XS Rating Curve= 0 ,0
Exp/Cntr=0.3,0.1

Type RM Length L Ch R = 1 ,1500    ,564,564,564
BEGIN DESCRIPTION:
WEST FORK OF CRYSTAL CREEK 3.0
END DESCRIPTION:
XS GIS Cut Line= 3
      3866692.08     10100221.62      3866480.14     10100095.36
      3865642.23     10100056.69
#Sta/Elev= 30
  4753.3  153.62  4779.7  154.01  4785.5  152.79  4818.4   151.3  4828.3  151.55
  4838.1  149.86  4902.3  145.45  4930.7  142.19  4939.3  139.65  4945.1  139.66
  4954.9   137.3  4967.7  138.03  4976.3  135.69  4982.1  132.09  4988.6  130.09
  5006.9  130.09  5012.3  136.12  5022.3   138.1  5062.4  138.31  5082.4  140.62
  5273.7   140.8  5432.1  143.28  5482.8  143.18  5636.7  147.39    5643  148.49
    5683  149.54  5723.1  152.87  5753.1  153.84  5793.1  156.92  5838.8  157.67
#Mann= 7 ,-1 , 0
  4753.3     .11       0  4818.4     .17       0  4930.7     .15       0
  4967.7     .09       0  5022.3     .15       0  5273.7     .17       0
  5432.1     .11       0
Bank Sta=4967.7,5022.3
XS Rating Curve= 0 ,0
Exp/Cntr=0.3,0.1

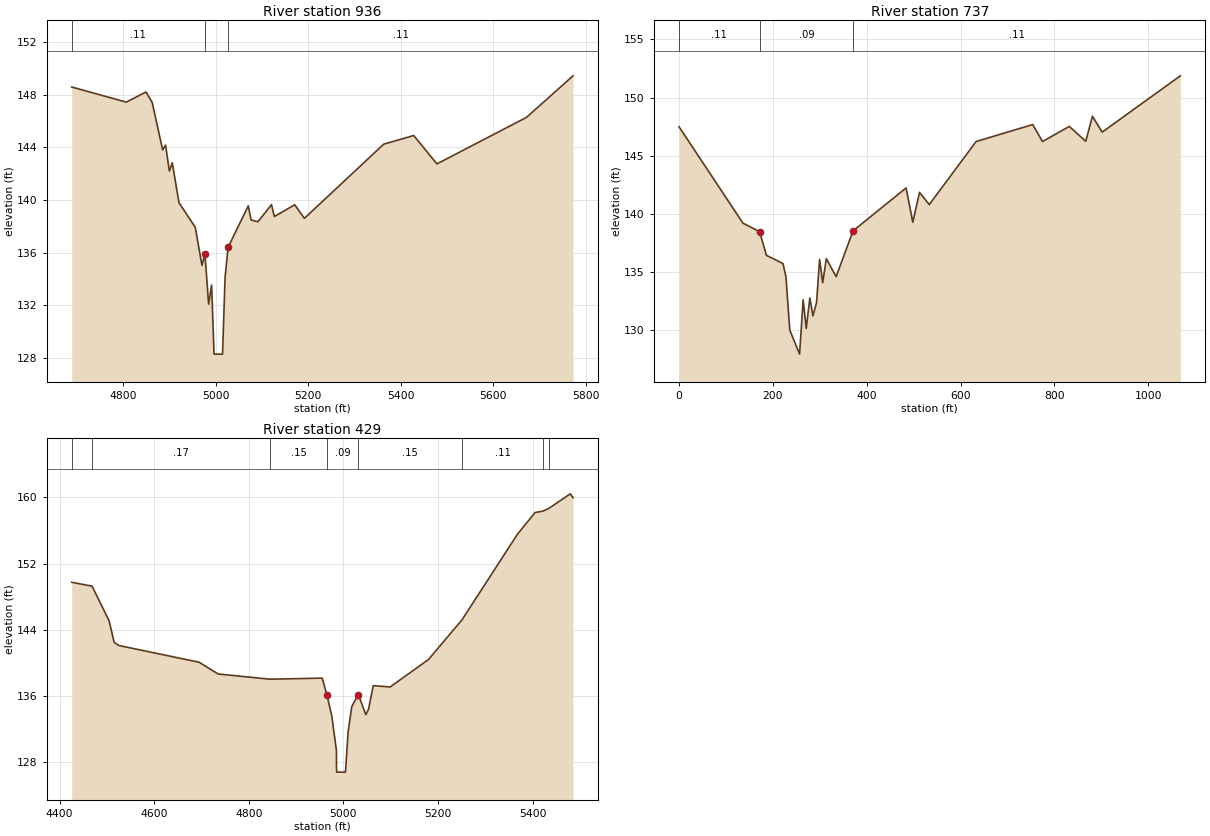
Type RM Length L Ch R = 1 ,936     ,199,199,199
BEGIN DESCRIPTION:
WEST FORK OF CRYSTAL CREEK 2.0
END DESCRIPTION:
XS GIS Cut Line= 3
      3866674.09      10099382.2      3866429.45     10099574.38
      3865806.67      10100030.6
#Sta/Elev= 30
  4688.9   148.6  4806.7  147.45  4849.4  148.22  4862.8  147.42  4885.3  143.82
  4891.7  144.18  4899.8  142.21  4906.1  142.84  4920.6   139.8  4955.8  137.93
  4970.3  135.03  4976.7   135.9  4984.7  132.08  4991.1  133.53  4996.4  128.28
  5014.7  128.28  5020.2  134.12  5026.8  136.41  5070.3  139.56  5076.5  138.48
  5091.2  138.35  5120.5  139.65  5126.7  138.75  5170.7  139.64  5191.6  138.61
  5362.9  144.25  5427.8  144.91  5477.9  142.75  5671.4  146.29    5772  149.45
#Mann= 3 , 0 , 0
  4688.9     .11       0  4976.7     .09       0  5026.8     .11       0
Bank Sta=4976.7,5026.8
XS Rating Curve= 0 ,0
Exp/Cntr=0.3,0.1

Type RM Length L Ch R = 1 ,737     ,309,309,309
XS GIS Cut Line= 3
      3866548.39     10099250.97       3866352.8     10099401.57
      3865730.87     10099938.35
#Sta/Elev= 30
       0  147.49   136.3   139.2   171.7  138.47   186.2  136.44   221.5  135.73
   227.9  134.58     236  130.01   256.9  127.94   264.5  132.61   271.1  130.15
   278.8  132.77   285.4  131.23     293  132.36   299.6  136.08   306.2  134.08
   313.9  136.15   334.8   134.6   370.9  138.54   483.9  142.23   498.2  139.28
   512.5  141.85   533.3   140.8   633.1  146.22   753.8  147.68   774.6  146.22
   831.7  147.52   866.8  146.24     881  148.39   901.9  147.03  1068.4  151.87
#Mann= 3 , 0 , 0
       0     .11       0   171.7     .09       0   370.9     .11       0
Bank Sta=171.7,370.9
XS Rating Curve= 0 ,0
Exp/Cntr=0.3,0.1

Type RM Length L Ch R = 1 ,429     ,0,0,0
BEGIN DESCRIPTION:
WEST FORK OF CRYSTAL CREEK 1.0
END DESCRIPTION:
XS GIS Cut Line= 3
      3866816.85     10099160.28      3866243.26     10099131.84
      3865823.91      10099376.7
#Sta/Elev= 30
  4425.7  149.73  4468.7  149.26  4504.8  145.07  4515.3  142.49  4524.8   142.1
    4695  140.07  4735.1  138.65  4845.2  138.02  4955.3  138.15  4965.4  136.07
  4975.4  133.62  4985.4  129.38  4985.5  127.29    4986  126.79  5004.4  126.79
  5010.2  131.72  5017.8  134.71  5031.7  136.17  5047.4  133.74  5053.2  134.38
  5063.1  137.24  5098.9  137.08    5180   140.4  5250.9   145.2  5368.2  155.55
  5405.4  158.16  5421.9  158.33    5434  158.65  5479.8  160.42  5485.6  159.95
#Mann= 8 ,-1 , 0
  4425.7     .11       0  4468.7     .17       0  4845.2     .15       0
  4965.4     .09       0  5031.7     .15       0  5250.9     .11       0
  5421.9     .17       0    5434     .11       0
Bank Sta=4965.4,5031.7
XS Rating Curve= 0 ,0
Exp/Cntr=0.3,0.1

Chan Stop Cuts=-1
Use User Specified Reach Order=0
Composite Channel Slope=5

--- WEST FORK OF CRYSTAL CREEK.g10 (geometry) ---

Geom Title=Existing Conditions
Program Version=4.10

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
River Reach=WEST FORK OF CRY,Reach-1

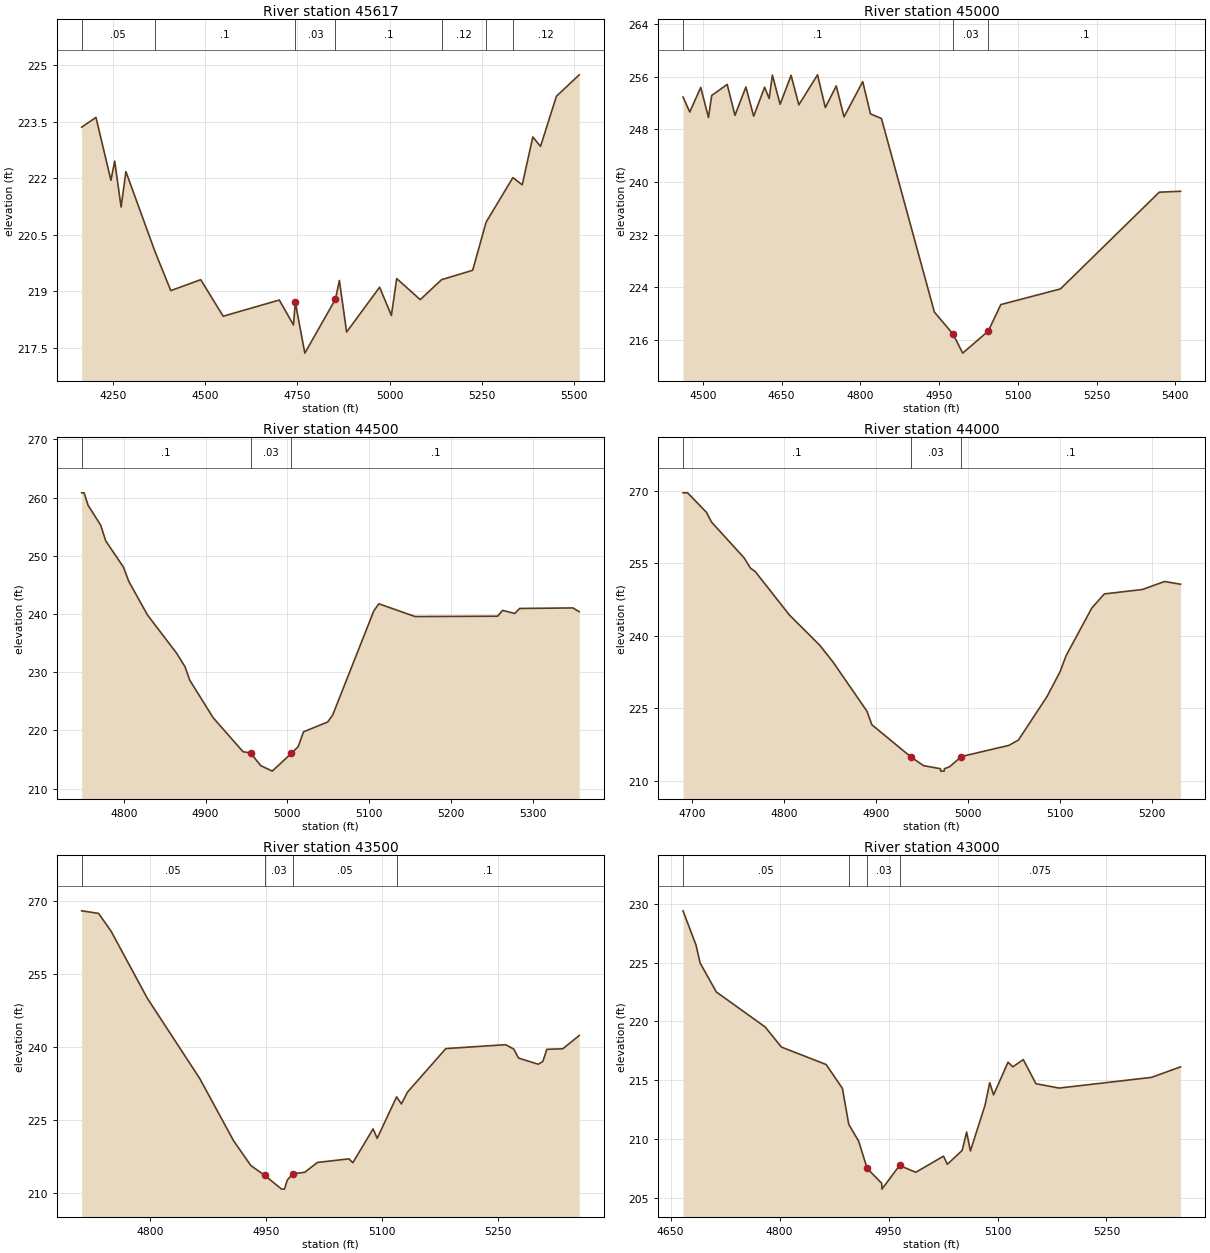
Type RM Length L Ch R = 1 ,45617   ,617,617,617
BEGIN DESCRIPTION:
WEST FORK OF CRYSTAL CREEK 91.0
END DESCRIPTION:
XS GIS Cut Line= 3
       3848616.1     10123214.71      3847792.98       10123072.
      3847393.13     10122748.56
#Sta/Elev= 30
  4164.6  223.36  4203.4  223.62    4244  221.95  4254.2  222.46  4271.6  221.24
  4284.6  222.18  4363.4  220.06  4406.4  219.02  4487.6  219.31  4548.5  218.34
  4700.7  218.77  4739.1  218.11  4744.2  218.71    4770  217.36    4853  218.79
  4863.7  219.29  4883.4  217.92  4972.9  219.11  5004.8  218.36  5019.2  219.34
  5083.1  218.78  5140.9  219.31  5225.3  219.56  5261.9  220.84  5334.4  222.02
  5359.8  221.83  5388.5   223.1  5409.4  222.85  5452.5  224.18  5514.3  224.75
#Mann= 7 ,-1 , 0
  4164.6     .05       0  4363.4      .1       0  4744.2     .03       0
    4853      .1       0  5140.9     .12       0  5261.9      .1       0
  5334.4     .12       0
Bank Sta=4744.2,4853
XS Rating Curve= 0 ,0
Exp/Cntr=0.3,0.1

Type RM Length L Ch R = 1 ,45000   ,500,500,500
BEGIN DESCRIPTION:
WEST FORK OF CRYSTAL CREEK 90.0
END DESCRIPTION:
XS GIS Cut Line= 3
      3848672.29     10123044.29      3848233.99      10122732.3
      3848100.67     10122344.69
#Sta/Elev= 30
    4462  252.92  4474.9  250.65  4495.8  254.39  4510.5  249.82  4516.7  253.16
  4546.2  254.84    4561  250.14  4581.8  254.45  4596.6  250.01  4617.5  254.42
  4626.1   252.7  4632.3  256.26    4647  251.82  4667.9  256.22  4682.7  251.74
  4718.3   256.3  4733.1  251.33    4754  254.61  4768.8  249.91  4804.4  255.27
  4819.2  250.36  4840.1  249.66  4940.9  220.24  4976.6  216.88  4994.9     214
  5043.6  217.35  5067.5  221.38  5181.1  223.76  5369.3  238.46  5409.9   238.6
#Mann= 3 , 0 , 0
    4462      .1       0  4976.6     .03       0  5043.6      .1       0
Bank Sta=4976.6,5043.6
XS Rating Curve= 0 ,0
Exp/Cntr=0.3,0.1

Type RM Length L Ch R = 1 ,44500   ,500,500,500
BEGIN DESCRIPTION:
WEST FORK OF CRYSTAL CREEK 89.0
END DESCRIPTION:
XS GIS Cut Line= 3
       3848698.1     10122420.72      3848478.68      10122297.8
       3848187.8     10122090.83
#Sta/Elev= 30
  4748.5  260.82  4751.5  260.82  4756.3   258.7  4771.7  255.28    4778  252.55
  4799.6  248.06  4806.1  245.62    4829  239.84  4864.7  233.26  4874.9  230.95
  4880.7  228.64  4909.3   222.2  4945.8  216.36  4955.1  216.13  4967.5  213.97
  4981.6  213.02  5005.1  216.09  5013.3  217.22  5019.8  219.77  5049.4  221.46
  5055.5  222.65  5105.9  240.57    5112  241.76  5156.3  239.57  5257.2  239.63
  5263.3  240.63  5278.1   240.1  5284.2  240.96  5349.4  241.05    5357   240.4
#Mann= 3 , 0 , 0
  4748.5      .1       0  4955.1     .03       0  5005.1      .1       0
Bank Sta=4955.1,5005.1
XS Rating Curve= 0 ,0
Exp/Cntr=0.3,0.1

Type RM Length L Ch R = 1 ,44000   ,500,500,500
BEGIN DESCRIPTION:
WEST FORK OF CRYSTAL CREEK 88.0
END DESCRIPTION:
XS GIS Cut Line= 3
      3849042.56     10121943.31      3848741.03     10121872.16
      3848517.85     10121811.07
#Sta/Elev= 30
  4690.2  269.56  4695.2  269.56  4715.6  265.56  4721.2  263.52  4756.7  256.11
  4763.5     254  4768.7   253.3  4805.9  244.31  4838.9  238.06  4853.3   234.6
  4890.3  224.41  4895.6  221.62    4938  214.97  4951.9  213.15  4970.3  212.52
  4970.6  212.02  4974.3  212.02  4974.5  212.52  4980.3  212.94    4993  215.04
  5044.8  217.35  5055.1  218.46  5086.2  227.45  5100.3  232.55    5107  235.92
  5134.8  245.72  5148.5  248.66  5189.9  249.57  5214.1  251.23  5231.4  250.66
#Mann= 3 , 0 , 0
  4690.2      .1       0    4938     .03       0    4993      .1       0
Bank Sta=4938,4993
XS Rating Curve= 0 ,0
Exp/Cntr=0.3,0.1

Type RM Length L Ch R = 1 ,43500   ,500,500,500
BEGIN DESCRIPTION:
WEST FORK OF CRYSTAL CREEK 87.0
END DESCRIPTION:
XS GIS Cut Line= 3
      3849267.85     10121561.07      3849003.39     10121446.52
      3848667.81     10121561.09
#Sta/Elev= 30
  4711.8  267.95  4733.6  267.43  4749.7   263.8  4796.7  249.97  4864.4  233.49
    4908  220.74  4930.4  215.62  4948.5  213.58  4970.1  210.78  4973.8  210.78
  4977.4  212.61  4984.2  213.91    5000  214.24  5016.4  216.26    5057     217
  5062.2  216.21  5088.3  223.15  5093.6  221.22  5118.7  229.73  5124.9  228.28
  5132.7   230.7  5182.3  239.65  5259.5  240.45    5270  239.56  5276.2   237.7
  5301.7  236.44  5307.6     237  5312.8   239.5  5333.4  239.61  5354.6  242.33
#Mann= 4 ,-1 , 0
  4711.8     .05       0  4948.5     .03       0  4984.2     .05       0
  5118.7      .1       0
Bank Sta=4948.5,4984.2
XS Rating Curve= 0 ,0
Exp/Cntr=0.3,0.1

Type RM Length L Ch R = 1 ,43000   ,500,500,500
BEGIN DESCRIPTION:
WEST FORK OF CRYSTAL CREEK 86.0
END DESCRIPTION:
XS GIS Cut Line= 3
      3849374.85     10121136.06      3849076.63     10120987.88
      3848742.18     10121097.63
#Sta/Elev= 30
    4667  229.39  4684.9  226.49  4690.5  224.97  4712.9   222.5  4780.1  219.53
  4802.5  217.82  4864.1  216.34  4886.5  214.31  4895.2  211.26  4908.9  209.82
  4920.5  207.52  4940.5  206.26  4940.9  205.76  4965.1  207.77  4987.5  207.19
  5025.7  208.56  5030.9  207.87  5051.3  209.04  5057.5  210.61  5062.7     209
  5082.9   212.9  5089.3   214.8  5094.6  213.76  5114.5  216.54  5121.1  216.14
  5135.5  216.76  5152.9  214.71  5184.8  214.34  5312.1  215.25    5352  216.14
#Mann= 4 ,-1 , 0
    4667     .05       0  4895.2    .075       0  4920.5     .03       0
  4965.1    .075       0
Bank Sta=4920.5,4965.1
XS Rating Curve= 0 ,0
Exp/Cntr=0.3,0.1

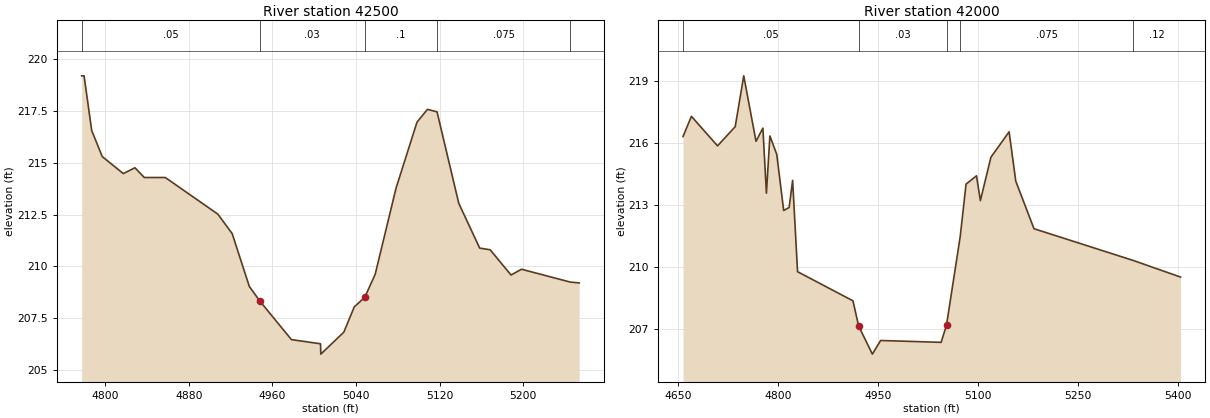
Type RM Length L Ch R = 1 ,42500   ,500,500,500
BEGIN DESCRIPTION:
WEST FORK OF CRYSTAL CREEK 85.0
END DESCRIPTION:
XS GIS Cut Line= 3
      3849487.92     10121120.63      3849511.22     10120899.46
      3849508.45     10120645.87
#Sta/Elev= 30
  4777.6   219.2  4779.9   219.2  4787.2  216.56  4797.3   215.3  4817.4  214.48
  4828.6  214.76  4837.5  214.29  4857.6  214.29  4907.9  212.52  4921.6  211.58
    4938  209.03  4948.1  208.32  4978.3  206.46  5006.1  206.26  5006.4  205.76
  5028.4  206.82  5038.4  208.04  5048.4   208.5  5058.4  209.61  5078.4  213.78
  5098.4  216.96  5108.4  217.58  5117.6  217.46  5138.4  213.04  5158.4  210.88
  5168.4   210.8  5188.4  209.58  5198.4  209.86    5245  209.24  5253.6   209.2
#Mann= 5 ,-1 , 0
  4777.6     .05       0  4948.1     .03       0  5048.4      .1       0
  5117.6    .075       0    5245     .12       0
Bank Sta=4948.1,5048.4
XS Rating Curve= 0 ,0
Exp/Cntr=0.3,0.1

Type RM Length L Ch R = 1 ,42000   ,500,500,500
BEGIN DESCRIPTION:
WEST FORK OF CRYSTAL CREEK 84.0
END DESCRIPTION:
XS GIS Cut Line= 3
      3850293.22     10120919.97       3849963.7     10120827.31
      3849613.82     10120625.52
#Sta/Elev= 30
  4657.7  216.32  4670.3   217.3  4709.5  215.87    4736   216.8  4748.8  219.26
  4767.2  216.09  4777.5  216.73  4782.8  213.58    4788  216.35  4798.3  215.46
  4808.7  212.74  4816.9  212.89  4822.1   214.2  4829.5  209.78  4912.6  208.37
  4921.1 207.152  4941.7  205.79  4954.1  206.45  5044.8  206.36  5052.9  207.19
  5073.5  211.49  5082.2  214.02  5097.9  214.42  5103.7  213.22  5119.5  215.32
  5146.8  216.55  5156.8  214.16  5184.1  211.86  5333.3  210.32  5403.9  209.52
#Mann= 5 ,-1 , 0
  4657.7     .05       0  4921.1     .03       0  5052.9     .05       0
  5073.5    .075       0  5333.3     .12       0
Bank Sta=4921.1,5052.9
XS Rating Curve= 0 ,0
Exp/Cntr=0.3,0.1