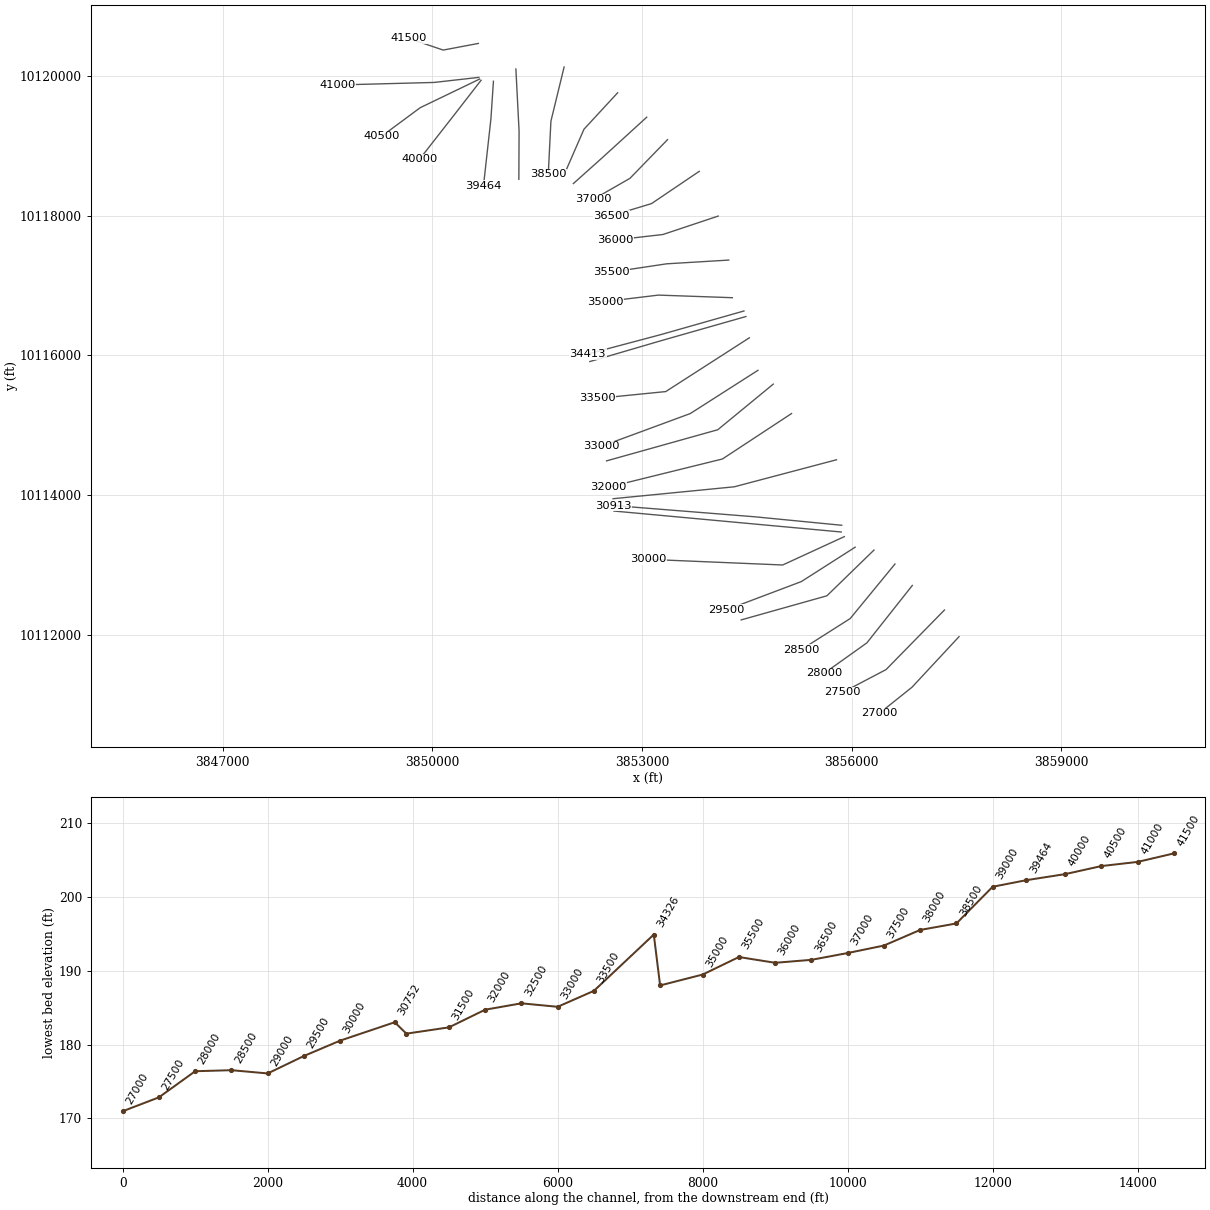
HEC-RAS study WEST FORK OF CRYSTAL CREEK.prj: WEST FORK OF CRYSTAL CREEK Base Level Engineering

--- WEST FORK OF CRYSTAL CREEK.g10 (geometry) --- (continued)

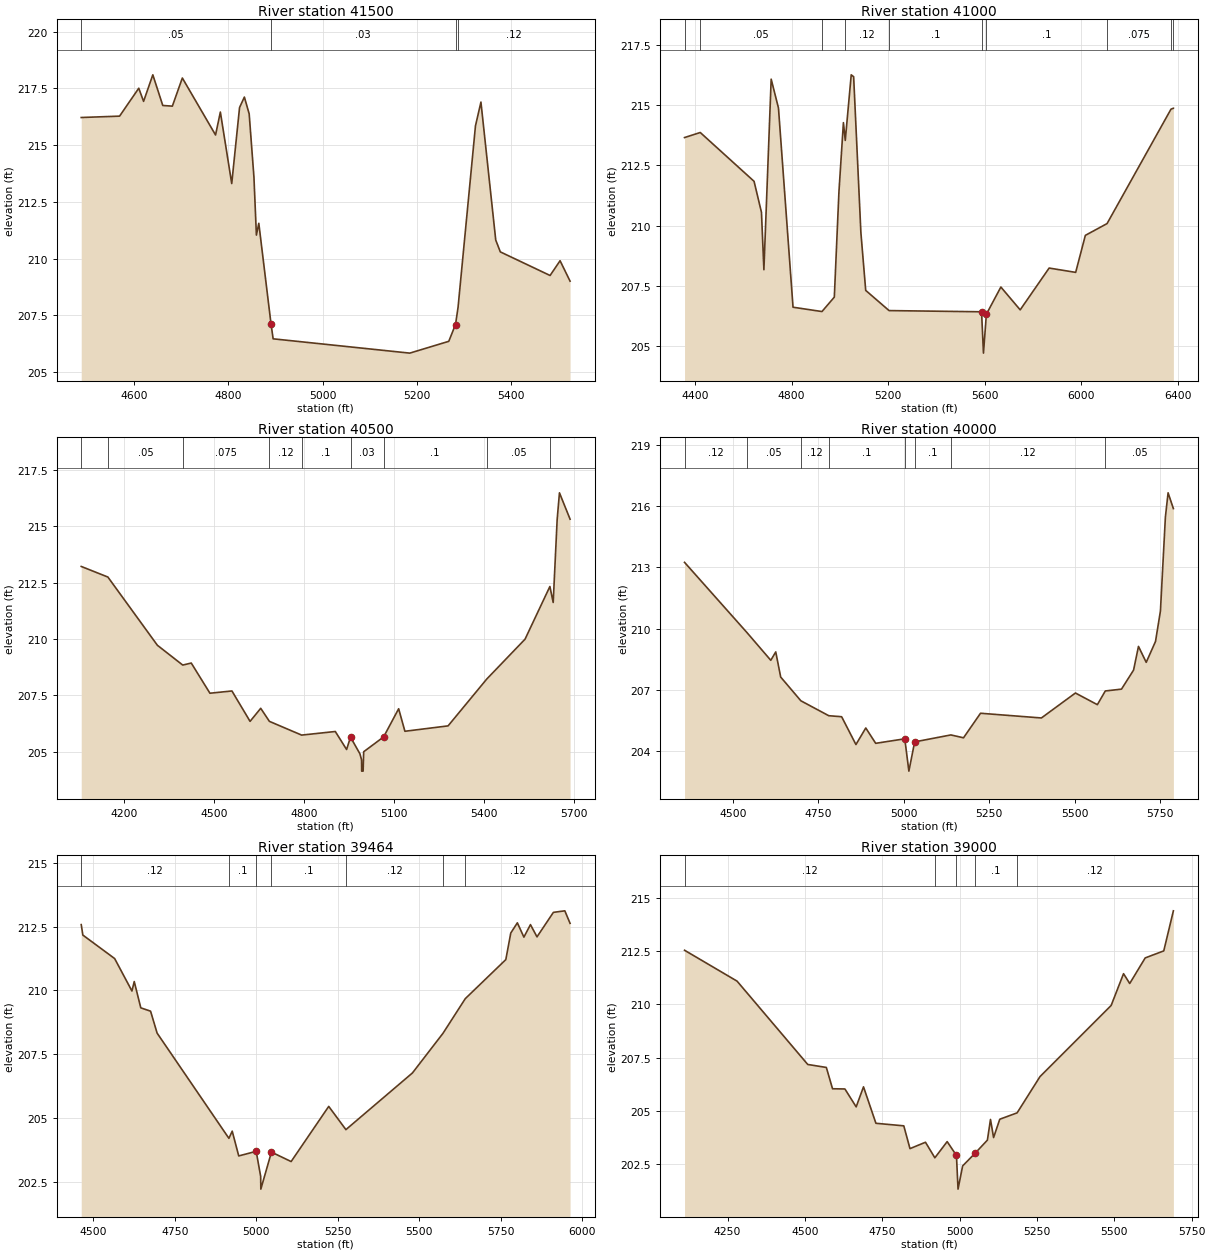
Type RM Length L Ch R = 1 ,41500   ,500,500,500
BEGIN DESCRIPTION:
WEST FORK OF CRYSTAL CREEK 83.0
END DESCRIPTION:
XS GIS Cut Line= 3
      3850657.72     10120465.09      3850154.53     10120369.96
      3849657.79     10120538.01
#Sta/Elev= 30
  4487.9  216.22  4569.2  216.28  4609.9  217.51  4620.1  216.93  4639.7   218.1
  4660.8  216.75  4681.1  216.72  4702.3  217.96  4772.7  215.45  4782.9  216.46
    4807  213.31  4823.6  216.66  4833.8  217.12    4844  216.38  4854.1  213.59
  4859.3  211.04  4864.4  211.56 4890.33 207.125  4894.8  206.47  5184.5  205.84
  5267.2  206.36  5281.5   207.1  5286.9  207.86  5323.8  215.85  5335.4   216.9
  5366.8  210.82  5376.5   210.3    5482  209.26  5503.2  209.91  5524.4  209.01
#Mann= 4 ,-1 , 0
  4487.9     .05       0 4890.33     .03       0  5281.5    .075       0
  5286.9     .12       0
Bank Sta=4890.33,5281.5
XS Rating Curve= 0 ,0
Exp/Cntr=0.3,0.1

Type RM Length L Ch R = 1 ,41000   ,500,500,500
BEGIN DESCRIPTION:
WEST FORK OF CRYSTAL CREEK 82.0
END DESCRIPTION:
XS GIS Cut Line= 3
      3850664.67     10119978.99      3850024.76     10119906.52
      3848643.04     10119870.14
#Sta/Elev= 30
    4356  213.66  4421.1  213.87  4644.1  211.84  4674.8  210.55  4684.9  208.16
  4715.1  216.09  4745.3  214.89  4805.7   206.6  4925.6  206.42  4976.8  207.02
  4995.9  211.39  5014.5  214.28  5022.2  213.54  5046.9  216.27  5056.9  216.19
  5086.9  209.71  5106.9   207.3  5203.8  206.46  5587.1  206.41    5595  204.69
  5607.1  206.31  5667.1  207.44  5747.2  206.49  5867.2  208.23  5977.2  208.05
  6017.3  209.59  6107.3  210.08  6372.2  214.84  6381.8  214.88  6382.2  214.88
#Mann= 10 ,-1 , 0
    4356     .12       0  4421.1     .05       0  4925.6    .075       0
  5022.2     .12       0  5203.8      .1       0  5587.1     .07       0
  5607.1      .1       0  6107.3    .075       0  6372.2      .1       0
  6381.8    .075       0
Bank Sta=5587.1,5607.1
XS Rating Curve= 0 ,0
Exp/Cntr=0.3,0.1

Type RM Length L Ch R = 1 ,40500   ,500,500,500
BEGIN DESCRIPTION:
WEST FORK OF CRYSTAL CREEK 81.0
END DESCRIPTION:
XS GIS Cut Line= 3
      3850675.14     10119954.69      3849825.29     10119544.87
      3849273.18     10119135.87
#Sta/Elev= 30
  4056.5  213.22  4145.4  212.75  4310.5  209.72  4395.1  208.84  4423.5  208.93
  4485.8  207.59  4559.2  207.69  4619.7  206.34  4655.2  206.92  4684.2  206.34
  4791.7  205.73    4904  205.89  4941.7  205.09  4954.7  205.64  4986.1   204.9
  4991.6  204.63    4992  204.13  4996.8  204.13  4998.6  204.99  5065.2  205.65
  5115.3   206.9  5136.2   205.9  5280.2  206.14  5409.2  208.22  5536.9  209.99
  5619.8  212.33  5630.8  211.62    5644   215.3  5651.7  216.49  5687.1  215.32
#Mann= 9 ,-1 , 0
  4056.5     .12       0  4145.4     .05       0  4395.1    .075       0
  4684.2     .12       0  4791.7      .1       0  4954.7     .03       0
  5065.2      .1       0  5409.2     .05       0  5619.8    .075       0
Bank Sta=4954.7,5065.2
XS Rating Curve= 0 ,0
Exp/Cntr=0.3,0.1

Type RM Length L Ch R = 1 ,40000   ,536,536,536
BEGIN DESCRIPTION:
WEST FORK OF CRYSTAL CREEK 80.0
END DESCRIPTION:
XS GIS Cut Line= 3
      3850695.96     10119937.34       3850303.1     10119430.46
      3849817.48     10118808.86
#Sta/Elev= 30
  4358.7  213.25  4541.1  209.82    4611  208.46  4625.5  208.87    4640  207.64
    4699  206.48  4780.6  205.75  4818.3   205.7  4860.1  204.34  4888.9  205.15
  4917.9   204.4    5003  204.62    5015  203.04  5031.9  204.47  5137.9  204.81
  5174.8  204.67  5224.6  205.87  5402.7  205.64  5502.2  206.86  5566.4  206.29
  5589.6  206.96    5637  207.05  5672.3  207.98  5686.7  209.14  5709.3  208.36
  5736.5  209.38  5750.9  210.87  5765.4  215.46  5773.3  216.65  5788.8  215.88
#Mann= 8 ,-1 , 0
  4358.7     .12       0  4541.1     .05       0    4699     .12       0
  4780.6      .1       0    5003     .07       0  5031.9      .1       0
  5137.9     .12       0  5589.6     .05       0
Bank Sta=5003,5031.9
XS Rating Curve= 0 ,0
Exp/Cntr=0.3,0.1

Type RM Length L Ch R = 1 ,39464   ,464,464,464
BEGIN DESCRIPTION:
WEST FORK OF CRYSTAL CREEK 79.0
END DESCRIPTION:
XS GIS Cut Line= 3
      3850873.03     10119923.44       3850837.4     10119387.73
      3850731.07     10118430.21
#Sta/Elev= 30
  4463.1  212.58  4468.1  212.17  4565.7  211.25  4618.7  209.98  4625.8  210.35
  4645.9  209.32  4675.9  209.19    4696  208.33  4916.3  204.21  4926.5  204.49
  4946.5  203.52    5000   203.7  5013.8  202.72  5014.3  202.22  5046.9  203.67
  5107.3   203.3  5222.7  205.46  5275.4  204.55  5479.6  206.77  5573.2  208.32
  5641.8  209.68  5766.2  211.21  5781.4  212.25  5801.6  212.65  5821.7  212.09
  5841.8  212.58  5861.9   212.1  5912.2  213.06  5947.3  213.12  5963.4  212.63
#Mann= 7 ,-1 , 0
  4463.1     .12       0  4916.3      .1       0    5000     .07       0
  5046.9      .1       0  5275.4     .12       0  5573.2      .1       0
  5641.8     .12       0
Bank Sta=5000,5046.9
XS Rating Curve= 0 ,0
Exp/Cntr=0.3,0.1

Type RM Length L Ch R = 1 ,39000   ,500,500,500
BEGIN DESCRIPTION:
WEST FORK OF CRYSTAL CREEK 78.0
END DESCRIPTION:
XS GIS Cut Line= 3
      3851194.29     10120098.72      3851239.95     10119210.99
      3851236.83       10118520.
#Sta/Elev= 30
  4111.1  212.54  4280.9  211.09  4509.3  207.18  4569.4  207.04  4589.4  206.04
  4629.4  206.03  4665.8  205.19  4689.5  206.13  4729.6  204.42  4819.7   204.3
  4839.7  203.23  4889.8  203.53  4920.1   202.8  4959.9  203.56  4989.9  202.91
    4995  201.33  5009.9  202.42  5049.9  203.01  5089.9  203.63  5099.9   204.6
  5109.9  203.75  5129.9  204.61    5186  204.91  5259.9  206.61  5489.9  209.95
  5529.9  211.44  5549.9  210.98  5599.9  212.18  5659.9  212.51    5691  214.39
#Mann= 5 ,-1 , 0
  4111.1     .12       0  4920.1      .1       0  4989.9     .07       0
  5049.9      .1       0    5186     .12       0
Bank Sta=4989.9,5049.9
XS Rating Curve= 0 ,0
Exp/Cntr=0.3,0.1

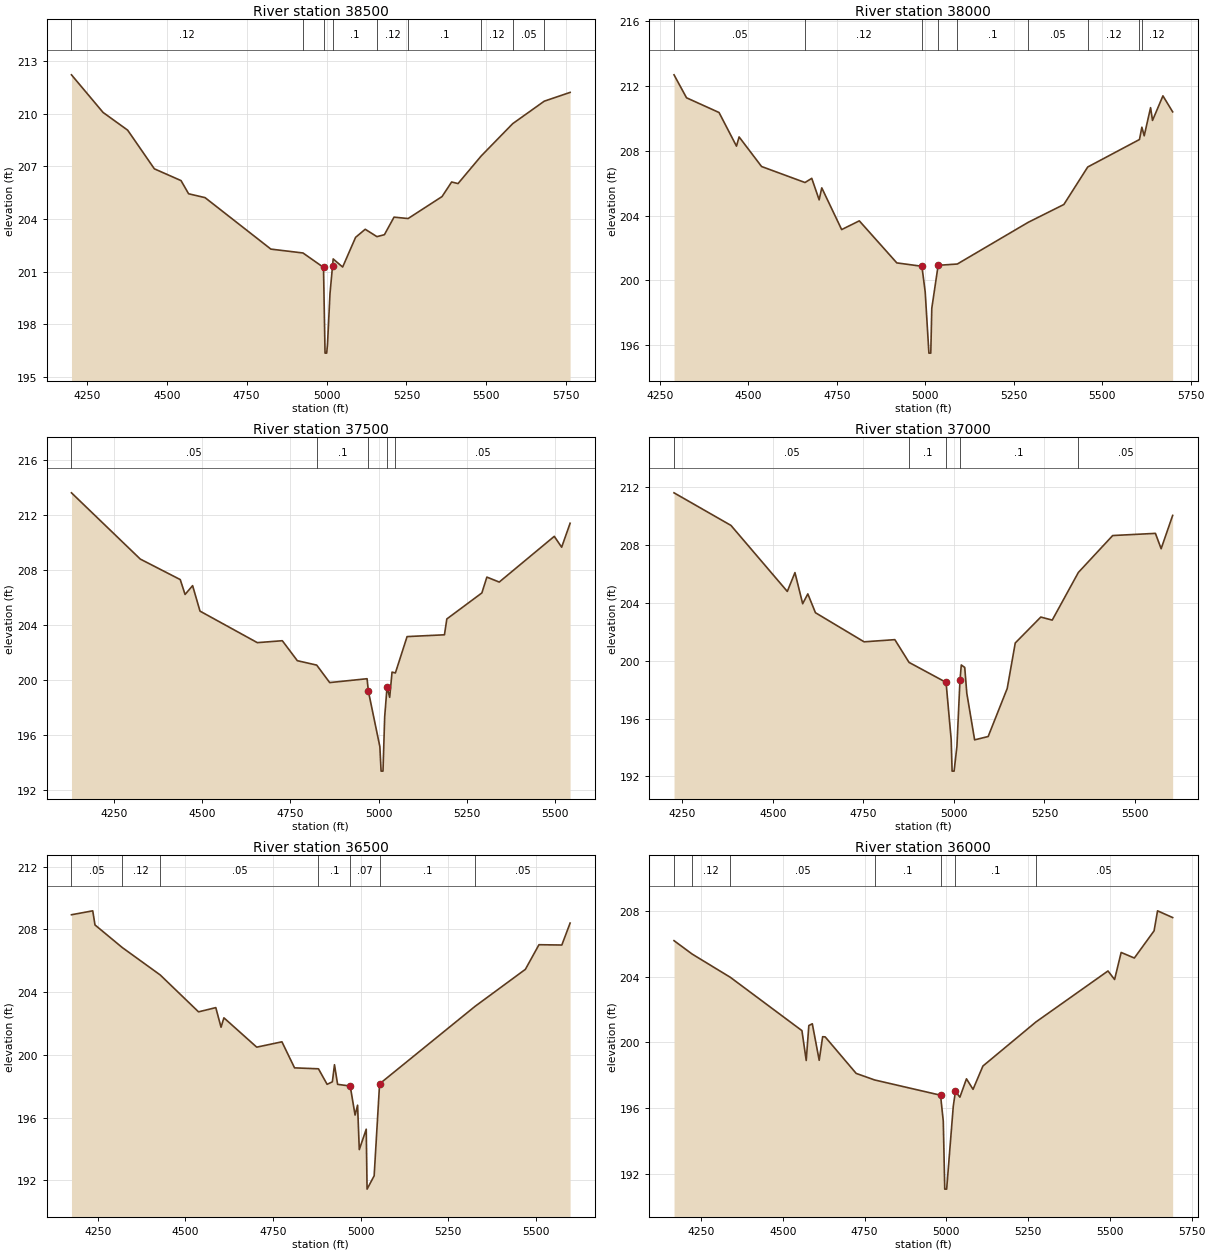
Type RM Length L Ch R = 1 ,38500   ,500,500,500
BEGIN DESCRIPTION:
WEST FORK OF CRYSTAL CREEK 77.0
END DESCRIPTION:
XS GIS Cut Line= 3
       3851884.4     10120127.11      3851695.59     10119351.77
      3851657.52     10118590.93
#Sta/Elev= 30
    4202  212.21  4300.8  210.07  4377.8  209.06  4461.3  206.86  4544.7  206.19
  4568.4  205.44  4619.9  205.22  4825.8  202.29  4926.2  202.07  4990.4  201.25
  4995.2  196.37  5000.3  196.37  5002.9  196.87  5010.7  199.76 5018.63 201.322
  5020.7  201.73  5050.3  201.27  5090.8  202.96  5120.9  203.42  5157.5     203
  5180.9  203.11    5211  204.11    5255  204.03  5361.2  205.28  5391.2  206.11
  5411.2  206.02  5483.6  207.59  5582.2  209.43  5680.9  210.71  5761.8  211.21
#Mann= 9 ,-1 , 0
    4202     .12       0  4926.2      .1       0  4990.4     .07       0
 5018.63      .1       0  5157.5     .12       0    5255      .1       0
  5483.6     .12       0  5582.2     .05       0  5680.9     .12       0
Bank Sta=4990.4,5018.63
XS Rating Curve= 0 ,0
Exp/Cntr=0.3,0.1

Type RM Length L Ch R = 1 ,38000   ,500,500,500
BEGIN DESCRIPTION:
WEST FORK OF CRYSTAL CREEK 76.0
END DESCRIPTION:
XS GIS Cut Line= 3
      3852650.15     10119758.42      3852168.66      10119236.9
      3851889.23     10118595.86
#Sta/Elev= 30
  4290.2   212.7  4325.5  211.28  4417.4  210.37  4466.7  208.29  4474.1  208.86
  4537.6  207.03  4660.4  206.04  4679.4   206.3  4700.3  204.97  4707.7  205.71
  4763.9  203.13  4813.8  203.67  4919.8  201.07  4990.7  200.86    5000  199.27
  5010.5  195.49  5015.8  195.49  5018.6  198.26  5036.6  200.92  5090.7     201
  5291.2  203.58  5391.8  204.68  5459.3     207  5605.5   208.7  5612.3  209.46
  5618.9  208.93  5636.9  210.67  5642.4  209.88  5671.8   211.4  5699.3  210.41
#Mann= 9 ,-1 , 0
  4290.2     .05       0  4660.4     .12       0  4990.7     .07       0
  5036.6     .12       0  5090.7      .1       0  5291.2     .05       0
  5459.3     .12       0  5605.5     .05       0  5612.3     .12       0
Bank Sta=4990.7,5036.6
XS Rating Curve= 0 ,0
Exp/Cntr=0.3,0.1

Type RM Length L Ch R = 1 ,37500   ,500,500,500
BEGIN DESCRIPTION:
WEST FORK OF CRYSTAL CREEK 75.0
END DESCRIPTION:
XS GIS Cut Line= 3
       3853066.1     10119408.63       3852422.1     10118821.16
      3852016.73     10118458.53
#Sta/Elev= 30
  4128.3  213.59  4323.6  208.78  4437.1  207.29  4450.8  206.21  4472.2  206.85
  4493.2     205    4656  202.71  4726.9  202.85  4769.5   201.4  4824.5  201.08
  4861.4  199.81  4967.5  200.09 4971.18 199.185  5003.8  195.16  5007.3  193.38
  5012.7  193.38  5017.5  197.32  5024.2  199.49  5031.7  198.74  5038.4  200.57
  5047.9  200.51  5081.1  203.15  5187.2  203.28  5193.9  204.43  5293.4  206.32
  5307.6  207.47  5342.7  207.11    5499  210.43  5519.9  209.64  5543.9  211.38
#Mann= 5 ,-1 , 0
  4128.3     .05       0  4824.5      .1       0 4971.18     .07       0
  5024.2      .1       0  5047.9     .05       0
Bank Sta=4971.18,5024.2
XS Rating Curve= 0 ,0
Exp/Cntr=0.3,0.1

Type RM Length L Ch R = 1 ,37000   ,500,500,500
BEGIN DESCRIPTION:
WEST FORK OF CRYSTAL CREEK 74.0
END DESCRIPTION:
XS GIS Cut Line= 3
       3853363.9     10119087.22      3852825.56     10118532.77
      3852301.57     10118232.35
#Sta/Elev= 30
  4227.2  211.59  4384.4  209.34    4540  204.78  4561.1  206.08  4582.4  203.93
  4596.6  204.61  4617.7  203.31    4752   201.3  4836.9  201.45  4876.1  199.88
  4978.3   198.5  4992.5  194.55    4995  192.37  5000.5  192.37  5008.3  194.08
 5016.75  198.64  5020.4   199.7  5029.9  199.53  5035.6  197.75  5057.2  194.53
  5094.6  194.76  5147.2  198.08  5169.4  201.22  5239.9  203.01  5271.5   202.8
  5343.6  206.09  5438.4  208.64  5556.4  208.79  5572.2  207.73    5604  210.03
#Mann= 5 ,-1 , 0
  4227.2     .05       0  4876.1      .1       0  4978.3     .07       0
 5016.75      .1       0  5343.6     .05       0
Bank Sta=4978.3,5016.75
XS Rating Curve= 0 ,0
Exp/Cntr=0.3,0.1

Type RM Length L Ch R = 1 ,36500   ,500,500,500
BEGIN DESCRIPTION:
WEST FORK OF CRYSTAL CREEK 73.0
END DESCRIPTION:
XS GIS Cut Line= 3
      3853818.11     10118633.85      3853134.72     10118171.68
      3852562.89     10117998.43
#Sta/Elev= 30
    4175  208.94  4235.7  209.19  4242.1  208.29  4319.9  206.85  4428.3   205.1
  4537.5  202.75  4586.7  203.02  4601.7  201.77  4609.9  202.37  4703.5   200.5
  4775.4  200.84  4811.4  199.18  4879.6  199.12  4904.3  198.13  4919.3  198.29
  4925.3  199.38  4934.2  198.13  4970.2  198.02  4984.1  196.17  4991.2   196.8
  4996.1  193.97  5015.9  195.27  5018.3  191.45  5038.5   192.3    5054  198.16
  5326.3   203.1  5469.9  205.46  5508.7  207.03  5573.9  207.01  5597.5  208.41
#Mann= 7 ,-1 , 0
    4175     .05       0  4319.9     .12       0  4428.3     .05       0
  4879.6      .1       0  4970.2     .07       0    5054      .1       0
  5326.3     .05       0
Bank Sta=4970.2,5054
XS Rating Curve= 0 ,0
Exp/Cntr=0.3,0.1

Type RM Length L Ch R = 1 ,36000   ,500,500,500
BEGIN DESCRIPTION:
WEST FORK OF CRYSTAL CREEK 72.0
END DESCRIPTION:
XS GIS Cut Line= 3
      3854088.96     10117993.23      3853298.74     10117729.41
      3852611.38     10117650.28
#Sta/Elev= 30
  4166.9  206.21  4222.5  205.39  4339.4  203.97  4558.1  200.72  4571.2   198.9
  4579.2  201.03  4589.8  201.14  4610.9  198.91  4621.4  200.35  4629.1  200.34
    4724  198.11  4780.5  197.71    4982  196.78  4990.4  195.19  4994.9  191.05
  5000.7  191.05    5021  196.12  5027.6  197.01  5041.2  196.66  5061.3  197.78
  5081.4  197.14  5111.6  198.56  5273.8  201.25  5494.1  204.36  5514.3  203.84
  5534.4  205.49  5574.7  205.15  5635.1  206.81  5645.7  208.03  5691.9  207.62
#Mann= 7 ,-1 , 0
  4166.9     .05       0  4222.5     .12       0  4339.4     .05       0
  4780.5      .1       0    4982     .07       0  5027.6      .1       0
  5273.8     .05       0
Bank Sta=4982,5027.6
XS Rating Curve= 0 ,0
Exp/Cntr=0.3,0.1

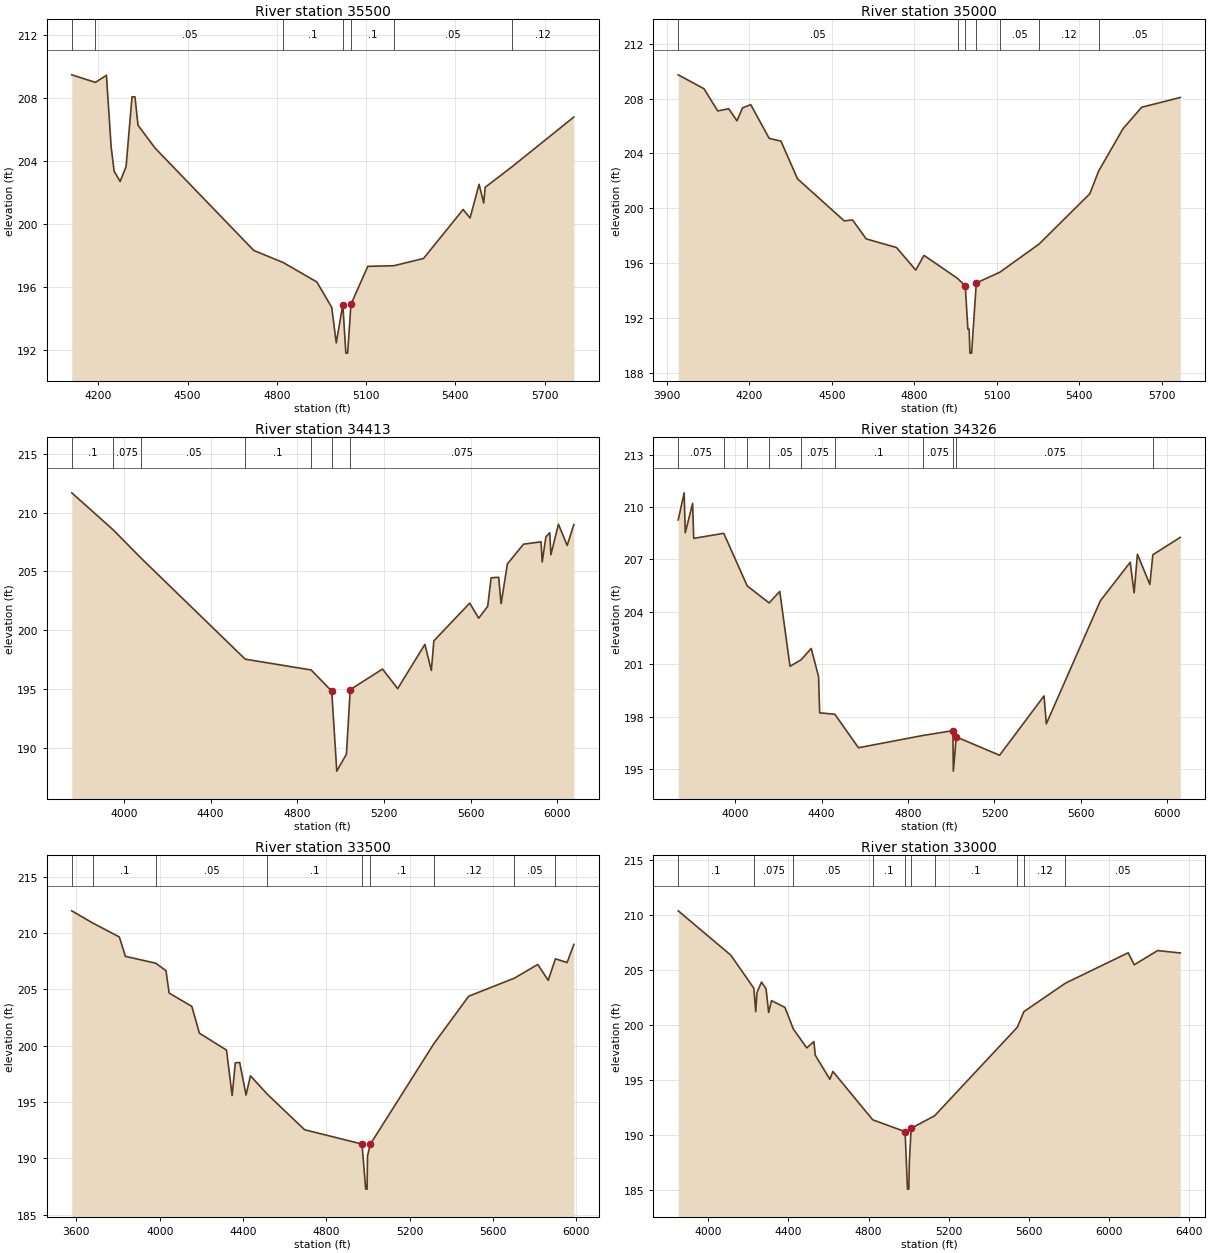
Type RM Length L Ch R = 1 ,35500   ,500,500,500
BEGIN DESCRIPTION:
WEST FORK OF CRYSTAL CREEK 71.0
END DESCRIPTION:
XS GIS Cut Line= 3
      3854240.01     10117363.02      3853352.42     10117309.61
      3852562.95     10117191.15
#Sta/Elev= 30
  4110.8   209.5  4190.3  209.02  4227.3  209.47  4243.2  204.91  4253.2  203.38
  4273.3  202.73  4293.3  203.67  4313.3  208.11  4323.3   208.1  4333.4   206.3
  4390.7  204.85  4722.5  198.35  4821.5  197.58  4934.4  196.35  4984.5  194.74
  4999.8  192.48  5021.8  194.91    5032  191.83    5038  191.83  5049.1 194.926
  5105.7  197.34  5193.5  197.38  5293.1  197.84  5426.2  200.95  5449.5  200.41
  5479.9  202.55  5495.3  201.36  5500.4  202.36  5590.3  203.66  5798.3  206.82
#Mann= 7 ,-1 , 0
  4110.8    .075       0  4190.3     .05       0  4821.5      .1       0
  5021.8     .07       0  5049.1      .1       0  5193.5     .05       0
  5590.3     .12       0
Bank Sta=5021.8,5049.1
XS Rating Curve= 0 ,0
Exp/Cntr=0.3,0.1

Type RM Length L Ch R = 1 ,35000   ,587,587,587
BEGIN DESCRIPTION:
WEST FORK OF CRYSTAL CREEK 70.0
END DESCRIPTION:
XS GIS Cut Line= 3
      3854291.43     10116824.34      3853233.69     10116861.61
      3852471.03      10116769.5
#Sta/Elev= 30
  3941.6  209.73  4035.2  208.72  4085.3   207.1  4125.3  207.26  4155.3  206.38
  4175.3  207.32  4205.3  207.56  4272.6   205.1  4315.4   204.9  4375.4  202.16
  4545.6  199.09  4575.6  199.16  4625.6  197.78  4735.7  197.15  4805.7  195.51
  4835.7  196.58    4958   194.9  4985.8  194.36  4995.4   191.2    5000   191.2
  5002.8  189.46  5008.9  189.46    5026  194.57  5112.2  195.36  5254.7  197.41
    5439  201.07  5470.8  202.71  5559.9  205.81  5627.7  207.37  5768.2  208.08
#Mann= 7 ,-1 , 0
  3941.6     .05       0    4958      .1       0  4985.8     .07       0
    5026      .1       0  5112.2     .05       0  5254.7     .12       0
  5470.8     .05       0
Bank Sta=4985.8,5026
XS Rating Curve= 0 ,0
Exp/Cntr=0.3,0.1

Type RM Length L Ch R = 1 ,34413   ,87,87,87
BEGIN DESCRIPTION:
WEST FORK OF CRYSTAL CREEK 69.0
END DESCRIPTION:
XS GIS Cut Line= 3
      3854457.38     10116634.22       3853264.2     10116294.84
      3852223.38     10116018.06
#Sta/Elev= 30
  3759.5  211.68  3951.3  208.52  4081.1  206.09  4560.2  197.52  4864.6   196.6
  4959.4   194.8  4982.7  187.99  5027.3  189.43 5044.86 194.928  5193.9  196.68
  5263.8  195.01  5389.5  198.78  5419.3  196.56  5430.8  199.08  5596.4  202.29
  5637.8  201.01  5679.2  202.01  5695.2  204.45  5730.1  204.49  5741.2  202.24
  5770.3  205.63  5844.7  207.31  5925.7  207.51  5930.9  205.79  5948.2  207.94
  5965.9  208.28    5971  206.41    6006  209.01  6046.2   207.2    6077  208.98
#Mann= 7 ,-1 , 0
  3759.5      .1       0  3951.3    .075       0  4081.1     .05       0
  4560.2      .1       0  4864.6    .075       0  4959.4     .07       0
 5044.86    .075       0
Bank Sta=4959.4,5044.86
XS Rating Curve= 0 ,0
Exp/Cntr=0.3,0.1

Type RM Length L Ch R = 1 ,34326   ,826,826,826
BEGIN DESCRIPTION:
WEST FORK OF CRYSTAL CREEK 68.0
END DESCRIPTION:
XS GIS Cut Line= 3
      3854485.48     10116554.66      3853270.47     10116208.34
      3852252.64     10115910.19
#Sta/Elev= 30
  3736.6  209.27    3764  210.82  3769.2  208.53  3803.1  210.21  3808.3  208.21
  3947.3   208.5  4055.7  205.49  4157.2  204.51  4206.5  205.17    4254  200.88
  4305.2  201.25  4352.2   201.9  4386.1  200.29  4391.3  198.21  4461.7  198.13
  4570.8  196.21  4867.6  196.91    5008  197.19    5010  194.87  5023.6  196.83
  5224.1  195.78  5429.8  199.18  5440.4  197.58  5690.5  204.63  5828.7  206.84
  5846.8  205.09  5862.1   207.3  5919.7  205.57  5933.4  207.27  6060.6  208.27
#Mann= 10 ,-1 , 0
  3736.6    .075       0  3947.3      .1       0  4055.7    .075       0
  4157.2     .05       0  4305.2    .075       0  4461.7      .1       0
  4867.6    .075       0    5008     .07       0  5023.6    .075       0
  5933.4      .1       0
Bank Sta=5008,5023.6
XS Rating Curve= 0 ,0
Exp/Cntr=0.3,0.1

Type RM Length L Ch R = 1 ,33500   ,500,500,500
BEGIN DESCRIPTION:
WEST FORK OF CRYSTAL CREEK 67.0
END DESCRIPTION:
XS GIS Cut Line= 3
      3854534.37     10116250.01      3853338.58      10115480.3
      3852355.58     10115381.97
#Sta/Elev= 30
  3577.9  211.96  3679.3  210.87  3806.3  209.64  3835.4  207.92  3981.3  207.31
  4030.1  206.65  4045.3  204.66  4154.2  203.48  4190.6   201.1  4320.6   199.6
  4347.7  195.57  4362.9  198.47    4384   198.5  4414.4  195.61  4435.5  197.32
  4516.8  195.68  4695.7  192.53    4971  191.26  4988.9  187.26  4995.4  187.26
  4997.5  190.21  5010.8  191.24  5315.3  200.15  5483.1  204.38  5701.9  205.98
  5814.8   207.2    5865  205.79  5899.4   207.7  5955.5  207.37  5987.9  208.98
#Mann= 9 ,-1 , 0
  3577.9    .075       0  3679.3      .1       0  3981.3     .05       0
  4516.8      .1       0    4971     .07       0  5010.8      .1       0
  5315.3     .12       0  5701.9     .05       0  5899.4      .1       0
Bank Sta=4971,5010.8
XS Rating Curve= 0 ,0
Exp/Cntr=0.3,0.1

Type RM Length L Ch R = 1 ,33000   ,500,500,500
BEGIN DESCRIPTION:
WEST FORK OF CRYSTAL CREEK 66.0
END DESCRIPTION:
XS GIS Cut Line= 3
      3854657.86      10115784.8      3853689.47     10115165.47
       3852418.3     10114696.27
#Sta/Elev= 30
  3850.5  210.38  4112.8  206.35  4227.6  203.35  4237.1  201.21    4243  202.95
    4266  203.91  4288.7  203.28  4301.6  201.15  4315.8  202.22  4382.6  201.61
  4424.8  199.64  4491.5  197.93  4527.1   198.5    4534  197.27  4606.7  195.08
  4621.9  195.79  4820.4   191.4  4982.2  190.32  4994.1   185.1  5000.7   185.1
  5003.5  187.64  5012.4  190.63  5129.3  191.76  5541.8   199.8  5574.6  201.22
  5782.1  203.81    6095  206.57  6125.4  205.48  6241.8  206.77    6355  206.55
#Mann= 10 ,-1 , 0
  3850.5      .1       0  4227.6    .075       0  4424.8     .05       0
  4820.4      .1       0  4982.2     .07       0  5012.4     .05       0
  5129.3      .1       0  5541.8     .05       0  5574.6     .12       0
  5782.1     .05       0
Bank Sta=4982.2,5012.4
XS Rating Curve= 0 ,0
Exp/Cntr=0.3,0.1

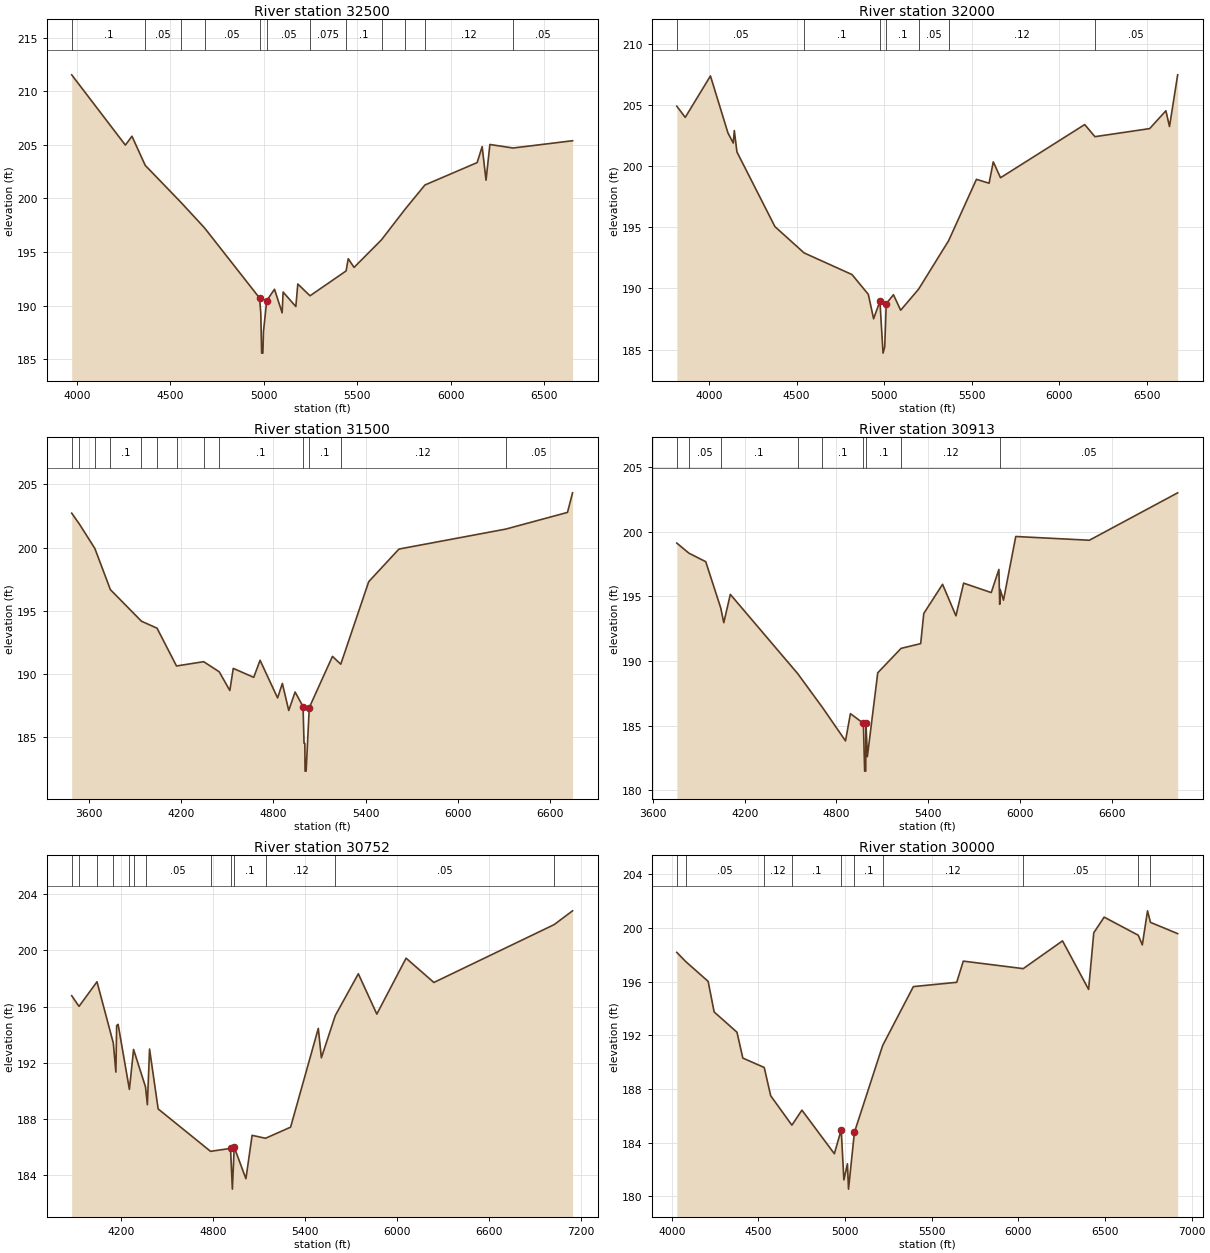
Type RM Length L Ch R = 1 ,32500   ,500,500,500
BEGIN DESCRIPTION:
WEST FORK OF CRYSTAL CREEK 65.0
END DESCRIPTION:
XS GIS Cut Line= 3
      3854876.64     10115586.91      3854082.81     10114933.75
      3852492.04     10114488.16
#Sta/Elev= 30
    3972  211.54  4259.2  204.98  4294.4  205.81  4365.5  203.09  4558.7   199.6
  4682.6  197.26  4977.3  190.71  4983.8   189.3  4988.3  185.57    4995  185.57
  4998.1  187.58  5015.5  190.47  5057.1  191.53    5098  189.33  5103.2  191.27
  5171.3  189.92  5181.8  192.02  5247.2  190.92  5440.3  193.24  5451.7  194.38
  5482.9  193.57  5629.9  196.15  5754.1  198.96  5862.1  201.26  6141.5  203.35
  6168.3  204.84    6189  201.71  6209.7  205.04  6333.3  204.71    6652  205.39
#Mann= 12 ,-1 , 0
    3972      .1       0  4365.5     .05       0  4558.7    .075       0
  4682.6     .05       0  4977.3     .07       0  5015.5     .05       0
  5247.2    .075       0  5440.3      .1       0  5629.9    .075       0
  5754.1     .05       0  5862.1     .12       0  6333.3     .05       0
Bank Sta=4977.3,5015.5
XS Rating Curve= 0 ,0
Exp/Cntr=0.3,0.1

Type RM Length L Ch R = 1 ,32000   ,500,500,500
BEGIN DESCRIPTION:
WEST FORK OF CRYSTAL CREEK 64.0
END DESCRIPTION:
XS GIS Cut Line= 3
      3855138.26     10115165.69      3854149.78     10114515.23
      3852522.66     10114112.98
#Sta/Elev= 30
  3816.7  204.91  3864.8     204  4008.7  207.39  4108.8  202.72  4138.9   201.9
  4144.9  202.92    4160  201.17  4376.9  195.06  4543.2  192.91  4816.7  191.14
    4910  189.52  4940.2  187.52  4976.3  188.96    4994  184.71  5003.6  185.21
  5012.3  188.75  5053.5  189.49  5094.7  188.22  5196.9  189.94  5368.5  193.91
  5527.3  198.93  5599.4  198.61  5623.4  200.36  5664.8  199.06  6145.4  203.41
  6203.8  202.42  6516.2  203.08  6608.9  204.54  6629.5  203.25  6676.1  207.48
#Mann= 7 ,-1 , 0
  3816.7     .05       0  4543.2      .1       0  4976.3     .07       0
  5012.3      .1       0  5196.9     .05       0  5368.5     .12       0
  6203.8     .05       0
Bank Sta=4976.3,5012.3
XS Rating Curve= 0 ,0
Exp/Cntr=0.3,0.1

Type RM Length L Ch R = 1 ,31500   ,587,587,587
BEGIN DESCRIPTION:
WEST FORK OF CRYSTAL CREEK 63.0
END DESCRIPTION:
XS GIS Cut Line= 3
      3855781.33     10114503.91      3854320.38     10114117.05
      3852584.97     10113946.27
#Sta/Elev= 30
  3488.7  202.73    3538  201.88  3639.1  199.94  3740.1  196.68  3942.2  194.18
  4043.3  193.63  4169.8  190.64  4346.4  190.98  4447.4  190.18  4516.4   188.7
  4538.7  190.45  4671.6  189.74    4713  191.09  4826.8  188.11  4857.8  189.26
  4899.2  187.12  4940.6  188.58  4992.3  187.43  4998.7  184.52  5003.8  184.52
  5005.3  182.32  5012.2  182.32  5032.7  187.35  5183.4   191.4  5237.4  190.78
    5419  197.31  5615.5  199.89  6309.6  201.47  6710.8  202.79  6743.8  204.34
#Mann= 13 ,-1 , 0
  3488.7    .075       0    3538      .1       0  3639.1    .075       0
  3740.1      .1       0  3942.2    .075       0  4043.3      .1       0
  4169.8    .075       0  4346.4     .05       0  4447.4      .1       0
  4992.3     .07       0  5032.7      .1       0  5237.4     .12       0
  6309.6     .05       0
Bank Sta=4992.3,5032.7
XS Rating Curve= 0 ,0
Exp/Cntr=0.3,0.1

Type RM Length L Ch R = 1 ,30913   ,161,161,161
BEGIN DESCRIPTION:
WEST FORK OF CRYSTAL CREEK 62.0
END DESCRIPTION:
XS GIS Cut Line= 3
      3855856.15     10113565.96      3854618.24     10113686.86
      3852592.09     10113848.75
#Sta/Elev= 30
  3756.2  199.12  3835.3  198.34  3945.4  197.68  4043.3  194.11  4063.4  192.96
  4106.2  195.15  4546.8  189.02  4708.8   186.4  4859.7  183.81  4891.9  185.92
 4976.67  185.17    4985  181.47  4992.2  181.47  4993.6   185.2  5002.7  182.59
  5070.6  189.08  5223.1  190.97  5351.5  191.34  5371.7  193.67  5494.6  195.93
  5582.2  193.49  5632.4  196.02    5813  195.29  5863.1  197.08  5868.5  194.38
  5871.8  195.53  5893.2   194.7  5973.5  199.63    6455  199.34  7032.6  203.01
#Mann= 9 ,-1 , 0
  3756.2    .075       0  3835.3     .05       0  4043.3      .1       0
  4546.8     .05       0  4708.8      .1       0 4976.67     .07       0
  4993.6      .1       0  5223.1     .12       0  5871.8     .05       0
Bank Sta=4976.67,4993.6
XS Rating Curve= 0 ,0
Exp/Cntr=0.3,0.1

Type RM Length L Ch R = 1 ,30752   ,752,752,752
BEGIN DESCRIPTION:
WEST FORK OF CRYSTAL CREEK 61.0
END DESCRIPTION:
XS GIS Cut Line= 3
       3855849.2     10113469.62      3854732.51     10113572.38
      3852596.91     10113769.67
#Sta/Elev= 30
  3878.6  196.78  3926.4  196.02  4043.5  197.77  4149.9  193.41  4166.7  191.34
  4171.7  194.65  4181.2  194.74  4254.8  190.11    4282  192.95  4359.9  190.29
    4372  189.02  4386.3  192.98  4442.3  188.72    4784   185.7  4914.3  185.91
  4926.4  183.01  4938.3     186  5014.7  183.75  5054.9  186.84  5142.6  186.63
    5306  187.42  5486.7  194.45  5506.8  192.36  5597.2  195.36  5747.8  198.34
  5868.3  195.47  6059.2  199.45  6240.4  197.72  7024.9  201.84  7144.7  202.82
#Mann= 13 ,-1 , 0
  3878.6    .075       0  3926.4     .05       0  4043.5      .1       0
  4149.9     .05       0  4254.8     .12       0    4282      .1       0
  4359.9     .05       0    4784      .1       0  4914.3     .07       0
  4938.3      .1       0  5142.6     .12       0  5597.2     .05       0
  7024.9    .075       0
Bank Sta=4914.3,4938.3
XS Rating Curve= 0 ,0
Exp/Cntr=0.3,0.1

Type RM Length L Ch R = 1 ,30000   ,500,500,500
BEGIN DESCRIPTION:
WEST FORK OF CRYSTAL CREEK 60.0
END DESCRIPTION:
XS GIS Cut Line= 3
      3855893.52     10113403.33      3855011.79     10112997.36
      3853094.07      10113077.8
#Sta/Elev= 30
  4029.3  198.18  4081.3  197.49  4210.1  196.02  4244.7  193.74  4376.4  192.23
  4410.3   190.3  4533.7   189.6  4571.1  187.49  4693.3   185.3  4751.1  186.42
  4938.3  183.17    4978  184.95  4993.3  181.22  5013.9  182.42  5020.1  180.53
    5054  184.76  5216.8  191.23  5394.3  195.63  5644.5  195.95  5682.3  197.53
  6028.2  196.97    6255  199.04  6405.5  195.42  6435.2  199.64  6495.2  200.81
  6692.1  199.46  6715.4  198.74  6745.5  201.28  6762.5  200.42  6919.4  199.58
#Mann= 10 ,-1 , 0
  4029.3    .075       0  4081.3     .05       0  4533.7     .12       0
  4693.3      .1       0    4978     .07       0    5054      .1       0
  5216.8     .12       0  6028.2     .05       0  6692.1     .12       0
  6762.5     .05       0
Bank Sta=4978,5054
XS Rating Curve= 0 ,0
Exp/Cntr=0.3,0.1

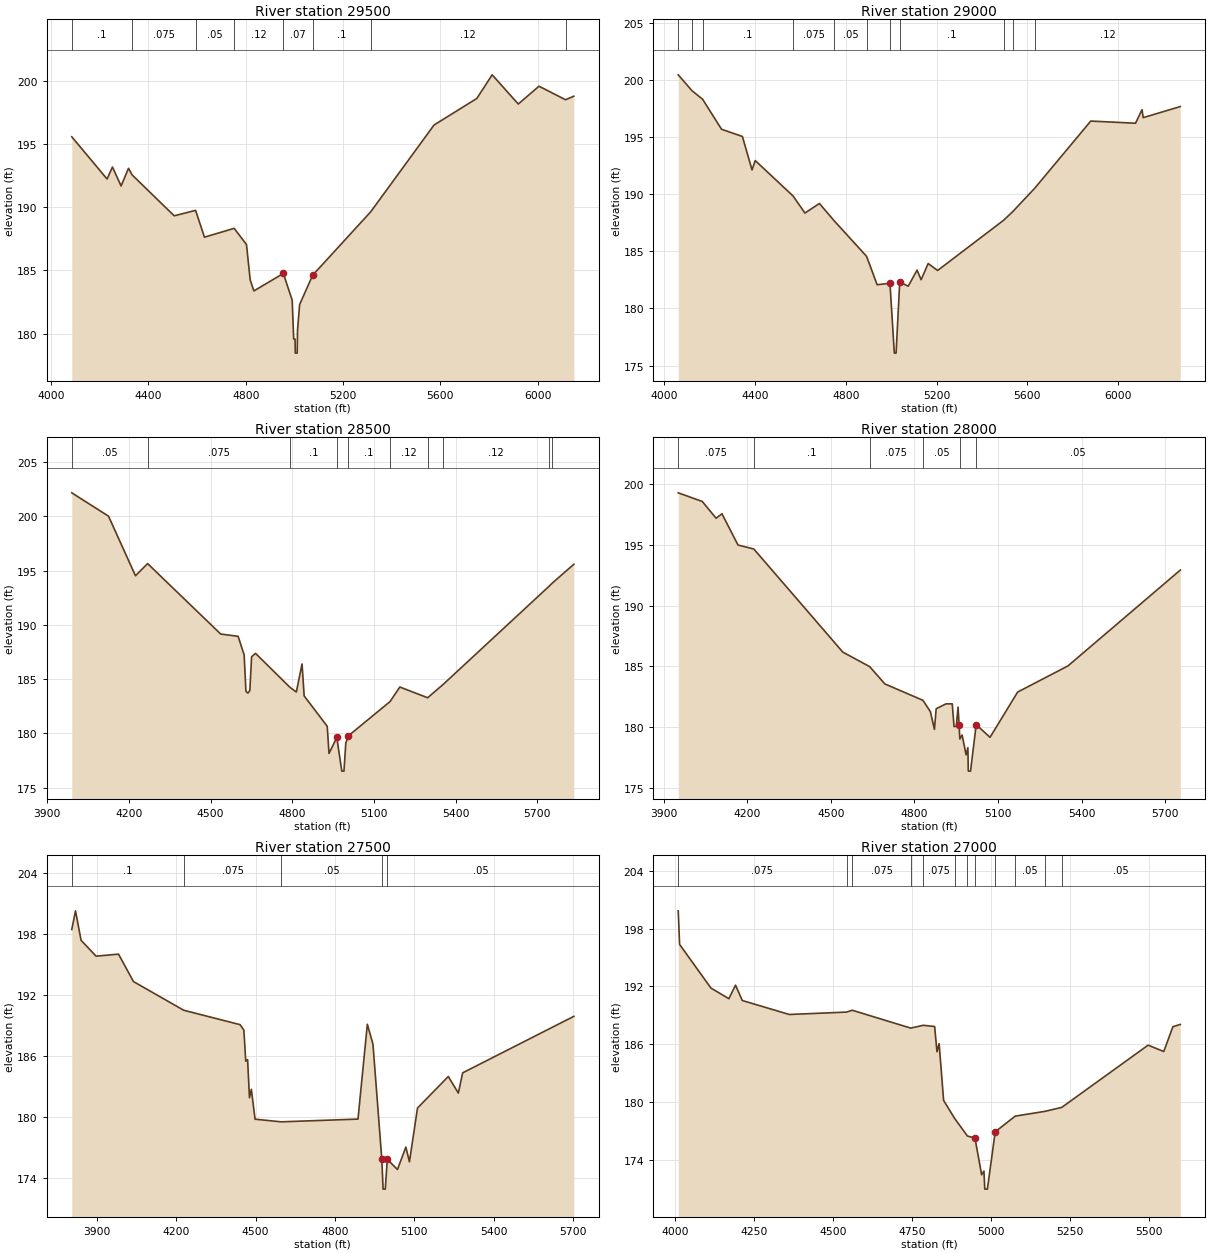
Type RM Length L Ch R = 1 ,29500   ,500,500,500
BEGIN DESCRIPTION:
WEST FORK OF CRYSTAL CREEK 59.0
END DESCRIPTION:
XS GIS Cut Line= 3
      3856048.63     10113252.01      3855277.97      10112759.5
      3854204.02     10112353.57
#Sta/Elev= 30
  4085.4  195.56  4230.5  192.22  4252.5  193.17  4288.1  191.67  4318.5  193.07
  4333.1  192.55  4506.3  189.31  4594.1  189.74  4630.6  187.62  4752.6  188.32
  4803.2  187.04  4818.4  184.24  4833.6  183.37  4954.6  184.75    4991  182.64
  4997.1  179.56  5002.7  179.56  5003.7  178.45  5011.4  178.45  5012.9  180.26
  5021.5  182.29    5075  184.61  5313.7  189.63  5573.7  196.49  5749.4  198.59
  5812.6  200.46  5919.8  198.15    6005  199.56    6114  198.49  6148.1  198.77
#Mann= 8 ,-1 , 0
  4085.4      .1       0  4333.1    .075       0  4594.1     .05       0
  4752.6     .12       0  4954.6     .07       0    5075      .1       0
  5313.7     .12       0    6114    .075       0
Bank Sta=4954.6,5075
XS Rating Curve= 0 ,0
Exp/Cntr=0.3,0.1

Type RM Length L Ch R = 1 ,29000   ,500,500,500
BEGIN DESCRIPTION:
WEST FORK OF CRYSTAL CREEK 58.0
END DESCRIPTION:
XS GIS Cut Line= 3
      3856317.88      10113211.1      3855644.48     10112556.27
      3854417.83     10112211.06
#Sta/Elev= 30
  4060.7  200.47  4121.7  199.07  4168.2  198.33  4251.7   195.7  4343.6  195.07
    4386  192.14  4400.2  192.96  4567.3  189.85  4619.3  188.36  4683.1   189.2
  4749.3  187.66  4891.1  184.57  4937.7  182.08  4994.2  182.21  5013.4  176.09
  5021.2  176.09 5037.24 182.331  5074.5  181.95  5113.7  183.36  5131.5  182.52
  5162.7  183.94  5204.3  183.33  5495.3  187.73  5535.2  188.48  5632.2  190.53
  5879.5  196.42  6076.9  196.23  6105.5  197.42  6110.7  196.72  6274.3  197.69
#Mann= 11 ,-1 , 0
  4060.7      .1       0  4121.7    .075       0  4168.2      .1       0
  4567.3    .075       0  4749.3     .05       0  4891.1      .1       0
  4994.2     .07       0 5037.24      .1       0  5495.3     .12       0
  5535.2      .1       0  5632.2     .12       0
Bank Sta=4994.2,5037.24
XS Rating Curve= 0 ,0
Exp/Cntr=0.3,0.1

Type RM Length L Ch R = 1 ,28500   ,500,500,500
BEGIN DESCRIPTION:
WEST FORK OF CRYSTAL CREEK 57.0
END DESCRIPTION:
XS GIS Cut Line= 3
      3856617.83     10113011.05      3855977.58     10112230.43
      3855273.97     10111783.22
#Sta/Elev= 30
  3990.4  202.17  4125.3  200.02  4224.3  194.53  4268.9  195.65  4537.2  189.16
  4601.1  188.95  4623.3  187.24  4629.8  183.88    4637  183.72  4644.1  183.94
  4650.6  187.06    4665  187.38    4792  184.24  4814.9  183.82  4835.8   186.4
  4843.6  183.46  4928.3  180.66  4934.8  178.16  4963.5  179.63  4981.8  176.53
  4989.7  176.53  4996.4   179.1 5005.07 179.764    5159  182.94  5194.9  184.28
  5296.9  183.29    5354  184.52  5743.9  193.59  5753.5  193.83  5833.7  195.59
#Mann= 10 ,-1 , 0
  3990.4     .05       0  4268.9    .075       0    4792      .1       0
  4963.5     .07       0 5005.07      .1       0    5159     .12       0
  5296.9      .1       0    5354     .12       0  5743.9     .05       0
  5753.5     .12       0
Bank Sta=4963.5,5005.07
XS Rating Curve= 0 ,0
Exp/Cntr=0.3,0.1

Type RM Length L Ch R = 1 ,28000   ,500,500,500
BEGIN DESCRIPTION:
WEST FORK OF CRYSTAL CREEK 56.0
END DESCRIPTION:
XS GIS Cut Line= 3
      3856866.02     10112704.24      3856216.03     10111882.04
      3855601.59     10111443.81
#Sta/Elev= 30
  3951.9  199.27  4038.2  198.56  4087.9  197.18  4108.9  197.55  4166.5  194.98
  4223.4  194.65  4543.1  186.17  4639.4  184.98  4693.8  183.56  4830.6  182.21
  4857.3  181.28  4871.8  179.82  4878.1  181.52  4913.4  181.92  4935.9  181.92
  4942.2  180.05  4950.2  180.08  4956.7  181.65 4960.26 180.193  4963.1  179.03
  4971.1  179.36  4985.6  177.73  4991.9  178.32  4993.4  176.39  5001.4  176.39
  5021.8  180.21  5071.5  179.17  5170.6  182.89  5351.3  185.04  5754.7  192.92
#Mann= 6 ,-1 , 0
  3951.9    .075       0  4223.4      .1       0  4639.4    .075       0
  4830.6     .05       0  4963.1     .07       0  5021.8     .05       0
Bank Sta=4960.26,5021.8
XS Rating Curve= 0 ,0
Exp/Cntr=0.3,0.1

Type RM Length L Ch R = 1 ,27500   ,500,500,500
BEGIN DESCRIPTION:
WEST FORK OF CRYSTAL CREEK 55.0
END DESCRIPTION:
XS GIS Cut Line= 3
       3857326.1     10112352.69      3856490.23     10111499.37
       3855867.8     10111172.15
#Sta/Elev= 30
  3805.5   198.4  3819.6  200.24  3840.7  197.34  3897.3  195.78  3982.2  195.98
  4038.8  193.28  4228.5  190.46  4441.8  189.04    4456  188.51  4463.1  185.45
  4470.1   185.6  4477.2  181.85  4484.2  182.68  4498.4  179.74  4597.1  179.48
  4887.3  179.75  4922.7  189.08  4943.9  187.13 4977.44 175.788  4982.2  172.86
  4990.4  172.86  4998.1  175.79  5036.6  174.79  5068.2     177  5081.8  175.55
  5112.3  180.84  5228.6  183.94  5266.6  182.31    5283   184.3  5703.2  189.86
#Mann= 5 ,-1 , 0
  3805.5      .1       0  4228.5    .075       0  4597.1     .05       0
 4977.44     .07       0  4998.1     .05       0
Bank Sta=4977.44,4998.1
XS Rating Curve= 0 ,0
Exp/Cntr=0.3,0.1

Type RM Length L Ch R = 1 ,27000   ,500,500,500
BEGIN DESCRIPTION:
WEST FORK OF CRYSTAL CREEK 54.0
END DESCRIPTION:
XS GIS Cut Line= 3
      3857534.43     10111970.74      3856860.38     10111245.79
      3856392.94     10110872.66
#Sta/Elev= 30
  4010.1  199.84  4014.4  196.36  4113.6  191.83  4170.3  190.73  4191.3  192.13
  4212.8  190.54  4361.4  189.09  4542.6  189.34  4560.6  189.53  4745.2  187.68
  4785.6  187.97  4821.1  187.84  4828.5  185.22  4835.3  186.07  4849.5  180.18
  4884.4  178.31  4924.8  176.49  4948.7  176.27  4969.7  172.47    4977  172.85
  4979.7  170.98  4987.9  170.98  5012.6  176.92    5076  178.55  5170.7  179.05
  5223.3  179.46  5496.2  185.91  5545.8  185.25  5574.6  187.82  5598.1  188.06
#Mann= 12 ,-1 , 0
  4010.1    .075       0  4542.6      .1       0  4560.6    .075       0
  4745.2     .05       0  4785.6    .075       0  4884.4     .12       0
  4924.8      .1       0  4948.7     .07       0  5012.6      .1       0
    5076     .05       0  5170.7      .1       0  5223.3     .05       0
Bank Sta=4948.7,5012.6
XS Rating Curve= 0 ,0
Exp/Cntr=0.3,0.1