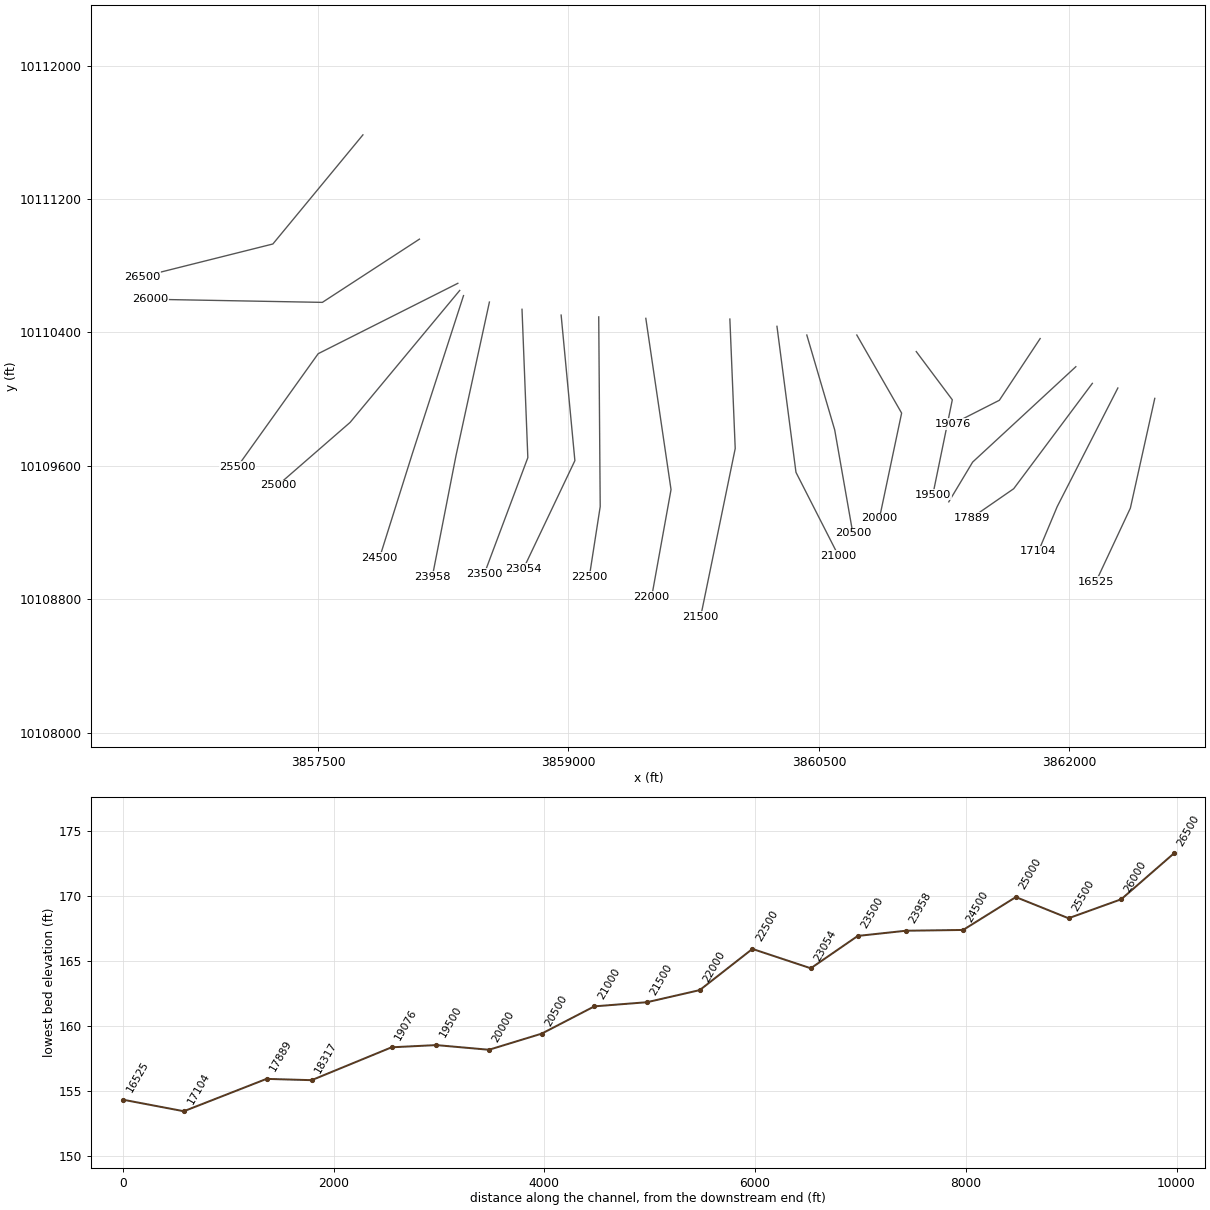
HEC-RAS study WEST FORK OF CRYSTAL CREEK.prj: WEST FORK OF CRYSTAL CREEK Base Level Engineering

--- WEST FORK OF CRYSTAL CREEK.g10 (geometry) --- (continued)

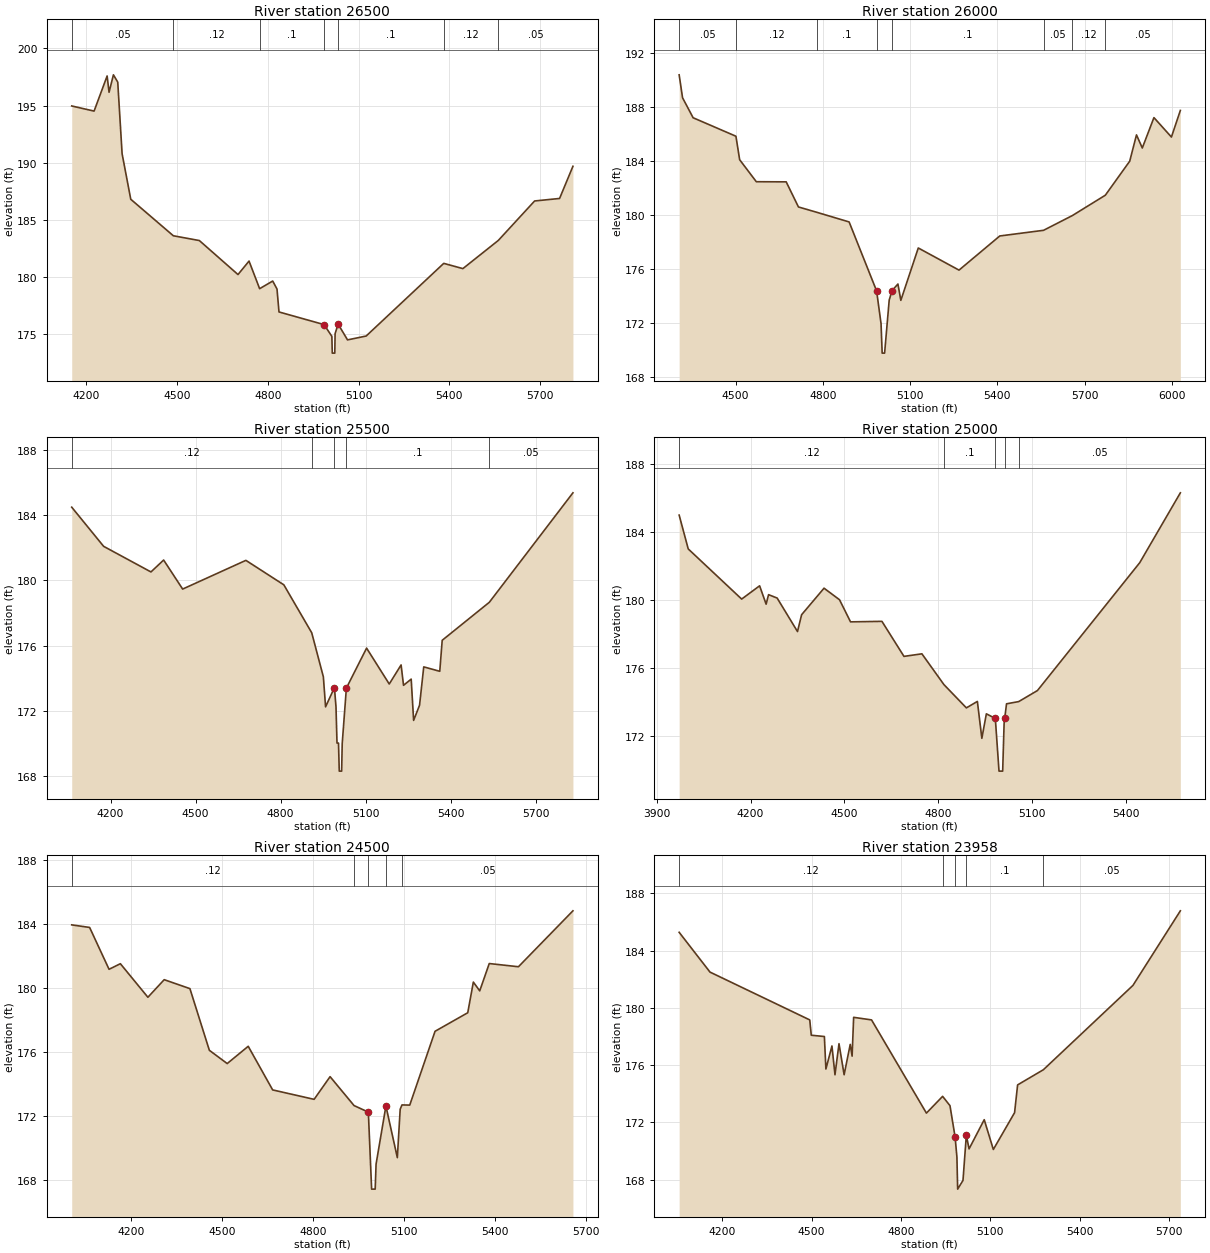
Type RM Length L Ch R = 1 ,26500   ,500,500,500
BEGIN DESCRIPTION:
WEST FORK OF CRYSTAL CREEK 53.0
END DESCRIPTION:
XS GIS Cut Line= 3
       3857768.8     10111584.45      3857229.38      10110930.4
      3856445.05     10110733.77
#Sta/Elev= 30
  4152.2  194.96  4226.1  194.51  4269.2  197.59  4275.6  196.16    4290  197.69
  4304.3  197.05  4318.7  190.77  4347.3  186.78    4488  183.58    4574  183.16
  4701.7  180.18  4738.2  181.36  4773.2  178.94  4816.4  179.61  4830.6  178.91
  4837.2   176.9  4986.2  175.79  5011.9  174.76  5013.3  173.29  5021.6  173.29
  5022.6  174.99  5032.5  175.84  5063.7  174.45  5125.3  174.79  5381.7  181.16
  5444.9   180.7    5562  183.17    5682  186.63  5764.5  186.85  5808.6  189.67
#Mann= 7 ,-1 , 0
  4152.2     .05       0    4488     .12       0  4773.2      .1       0
  4986.2     .07       0  5032.5      .1       0  5381.7     .12       0
    5562     .05       0
Bank Sta=4986.2,5032.5
XS Rating Curve= 0 ,0
Exp/Cntr=0.3,0.1

Type RM Length L Ch R = 1 ,26000   ,500,500,500
BEGIN DESCRIPTION:
WEST FORK OF CRYSTAL CREEK 52.0
END DESCRIPTION:
XS GIS Cut Line= 3
      3858107.34     10110959.45      3857525.84     10110580.46
      3856497.11     10110599.22
#Sta/Elev= 30
  4305.9  190.38  4317.6  188.68  4353.9   187.2  4501.1  185.83  4513.9  184.09
  4571.2  182.46  4673.9  182.45    4716  180.59  4781.4  180.18  4890.2  179.48
  4984.7  174.37    5000  171.94  5003.8  169.76  5012.2  169.76    5028  173.69
    5038   174.4    5058  174.88    5068  173.67    5128  177.55    5268  175.91
  5408.1  178.44  5558.7  178.86  5657.5  179.95    5771  181.46  5854.8  183.98
  5878.1  185.93  5898.1  184.96  5938.1  187.21  5998.2  185.77  6028.9  187.74
#Mann= 8 ,-1 , 0
  4305.9     .05       0  4501.1     .12       0  4781.4      .1       0
  4984.7     .07       0    5038      .1       0  5558.7     .05       0
  5657.5     .12       0    5771     .05       0
Bank Sta=4984.7,5038
XS Rating Curve= 0 ,0
Exp/Cntr=0.3,0.1

Type RM Length L Ch R = 1 ,25500   ,500,500,500
BEGIN DESCRIPTION:
WEST FORK OF CRYSTAL CREEK 51.0
END DESCRIPTION:
XS GIS Cut Line= 3
      3858337.38      10110694.7      3857500.89     10110272.93
      3857017.91     10109596.58
#Sta/Elev= 30
  4063.2  184.48  4175.7  182.08  4342.7  180.51  4387.4  181.24  4454.5  179.46
  4677.5  181.22  4811.4  179.72  4909.8  176.78  4950.8  174.08  4958.6  172.24
  4989.8  173.42  4995.4  172.23  4998.9  170.02  5004.2  170.02  5006.9   168.3
  5015.3   168.3  5017.3  169.99    5032  173.39  5103.3  175.84  5183.2  173.64
    5225  174.81  5233.6  173.56  5260.6  173.94  5269.2  171.41  5290.1  172.34
  5304.9  174.69  5361.4  174.42    5370  176.32  5536.2  178.65  5831.1  185.36
#Mann= 5 ,-1 , 0
  4063.2     .12       0  4909.8      .1       0  4989.8     .07       0
    5032      .1       0  5536.2     .05       0
Bank Sta=4989.8,5032
XS Rating Curve= 0 ,0
Exp/Cntr=0.3,0.1

Type RM Length L Ch R = 1 ,25000   ,500,500,500
BEGIN DESCRIPTION:
WEST FORK OF CRYSTAL CREEK 50.0
END DESCRIPTION:
XS GIS Cut Line= 3
      3858348.52     10110651.82      3857691.93     10109860.95
      3857260.15     10109485.18
#Sta/Elev= 30
  3972.1  184.99  4001.1     183  4171.7  180.05    4229  180.83  4249.8  179.75
  4257.6  180.31    4285  180.11    4350  178.14  4363.1  179.13  4434.7  180.69
  4484.2  180.01  4519.3  178.71  4619.6  178.74  4689.9  176.68  4747.2  176.83
  4817.5  175.02  4889.2  173.65  4924.3  174.03  4938.6  171.86    4953   173.3
  4981.6  173.03  4993.4  169.93  5005.1  169.93  5009.7  172.76 5011.84 173.074
  5017.4  173.89  5056.3  174.02  5116.1  174.67  5442.7  182.19  5572.4   186.3
#Mann= 5 ,-1 , 0
  3972.1     .12       0  4817.5      .1       0  4981.6     .07       0
 5011.84      .1       0  5056.3     .05       0
Bank Sta=4981.6,5011.84
XS Rating Curve= 0 ,0
Exp/Cntr=0.3,0.1

Type RM Length L Ch R = 1 ,24500   ,542,542,542
BEGIN DESCRIPTION:
WEST FORK OF CRYSTAL CREEK 49.0
END DESCRIPTION:
XS GIS Cut Line= 3
      3858371.41     10110620.99      3858065.01     10109674.35
      3857867.95     10109048.12
#Sta/Elev= 30
    4005  183.94    4064  183.78    4128  181.16  4165.3  181.51    4256  179.41
  4309.7  180.51  4394.5  179.95  4458.5  176.09  4517.3  175.26  4586.6  176.34
  4667.1  173.61  4803.7  173.02  4856.3  174.44  4935.3  172.63  4982.4  172.22
  4993.2   167.4  5004.9   167.4  5007.9  168.97  5040.3   172.6  5077.9  169.37
  5087.3   172.4  5093.2  172.67  5118.8  172.66  5202.2  177.28  5309.9  178.44
  5328.4  180.36  5349.4  179.81  5380.8  181.52    5477  181.32  5656.5  184.82
#Mann= 5 ,-1 , 0
    4005     .12       0  4935.3      .1       0  4982.4     .07       0
  5040.3      .1       0  5093.2     .05       0
Bank Sta=4982.4,5040.3
XS Rating Curve= 0 ,0
Exp/Cntr=0.3,0.1

Type RM Length L Ch R = 1 ,23958   ,458,458,458
BEGIN DESCRIPTION:
WEST FORK OF CRYSTAL CREEK 48.0
END DESCRIPTION:
XS GIS Cut Line= 3
      3858526.47     10110582.35      3858325.87      10109659.5
      3858184.17     10108934.82
#Sta/Elev= 30
  4055.6  185.28  4159.2   182.5  4494.1  179.16  4499.2  178.09  4543.2     178
  4548.3  175.73  4568.6  177.34  4578.8  175.33  4592.3   177.5  4609.5  175.33
    4630  177.45  4636.3  176.63  4641.5  179.34  4701.6  179.16  4885.8  172.65
  4940.2  173.82  4964.9  173.17  4982.1 170.984  4988.2  169.58  4990.7  167.34
  5008.6  167.95  5019.8   171.1    5029  170.15  5079.9  172.19  5110.5  170.11
  5181.8  172.68    5192  174.62  5278.5  175.68  5579.2  181.57  5738.4  186.78
#Mann= 5 ,-1 , 0
  4055.6     .12       0  4940.2      .1       0  4982.1     .07       0
  5019.8      .1       0  5278.5     .05       0
Bank Sta=4982.1,5019.8
XS Rating Curve= 0 ,0
Exp/Cntr=0.3,0.1

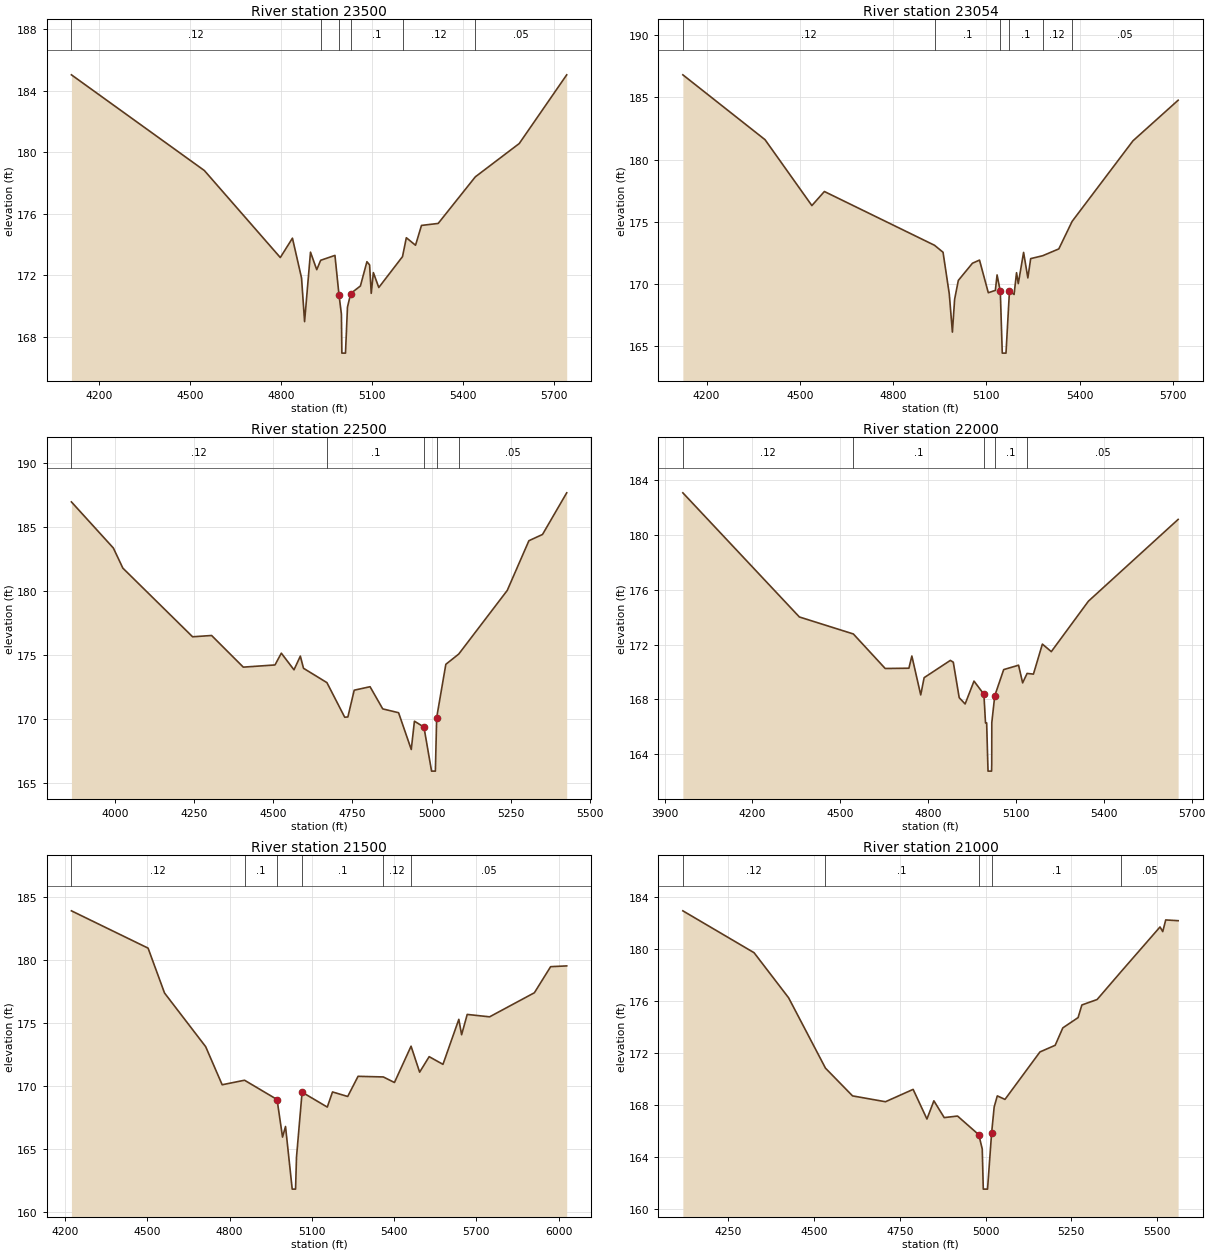
Type RM Length L Ch R = 1 ,23500   ,446,446,446
BEGIN DESCRIPTION:
WEST FORK OF CRYSTAL CREEK 47.0
END DESCRIPTION:
XS GIS Cut Line= 3
      3858721.78     10110539.01      3858756.68      10109649.8
      3858496.21     10108954.37
#Sta/Elev= 30
  4110.1  185.05  4548.4  178.82  4798.6  173.16  4838.6  174.42  4868.6  171.83
  4878.6  168.99  4898.1  173.51  4918.7  172.37  4931.6  172.98  4978.7   173.3
 4991.99 170.737    5000  169.48  5001.5  166.94  5013.4  166.94    5020  169.94
  5030.7  170.82  5062.6  171.31  5084.1  172.89  5092.9  172.68  5098.3  170.83
  5105.4  172.18  5123.2  171.21  5201.4  173.22    5214  174.45  5244.3  173.96
  5263.9  175.25    5319  175.38  5441.3  178.41  5586.2  180.58  5742.6  185.05
#Mann= 6 ,-1 , 0
  4110.1     .12       0  4931.6      .1       0 4991.99     .07       0
  5030.7      .1       0  5201.4     .12       0  5441.3     .05       0
Bank Sta=4991.99,5030.7
XS Rating Curve= 0 ,0
Exp/Cntr=0.3,0.1

Type RM Length L Ch R = 1 ,23054   ,554,554,554
BEGIN DESCRIPTION:
WEST FORK OF CRYSTAL CREEK 46.0
END DESCRIPTION:
XS GIS Cut Line= 3
      3858956.16     10110504.26       3859038.5     10109631.84
      3858730.65     10108984.51
#Sta/Elev= 30
  4123.7   186.8  4388.1  181.59  4538.7   176.3  4578.9  177.43  4933.3  173.11
  4960.6  172.55  4980.7   169.2  4990.7  166.14  4997.9  168.78  5009.8  170.29
  5055.2  171.67  5077.9  171.92  5106.2   169.3  5128.9  169.49  5134.4  170.73
  5144.8  169.41  5151.1  164.45  5163.1  164.45  5174.3  169.46  5189.1  169.16
    5197  170.91  5202.6  170.03  5219.7  172.54  5233.4  170.49  5242.5  172.04
  5280.9  172.27    5333  172.82  5375.8  175.03  5571.5   181.5  5716.8  184.76
#Mann= 6 ,-1 , 0
  4123.7     .12       0  4933.3      .1       0  5144.8     .07       0
  5174.3      .1       0  5280.9     .12       0  5375.8     .05       0
Bank Sta=5144.8,5174.3
XS Rating Curve= 0 ,0
Exp/Cntr=0.3,0.1

Type RM Length L Ch R = 1 ,22500   ,500,500,500
BEGIN DESCRIPTION:
WEST FORK OF CRYSTAL CREEK 45.0
END DESCRIPTION:
XS GIS Cut Line= 3
      3859181.31     10110493.38      3859190.22     10109356.62
      3859124.95     10108935.65
#Sta/Elev= 30
  3863.2  186.96  3995.5  183.36  4025.5  181.79  4245.5  176.43  4305.5  176.53
  4405.5  174.06  4505.5  174.23  4525.5  175.15  4565.5  173.85  4585.5  174.92
  4595.5  173.97  4669.4  172.85  4725.5  170.15  4735.5  170.17  4755.5  172.26
  4805.5  172.53  4845.5   170.8  4895.5   170.5  4935.5  167.63  4945.5  169.84
  4975.5  169.38  4999.6  165.94  5011.6  165.94  5015.7  170.12  5044.6  174.28
  5085.3  175.08  5238.4  180.05  5306.7  183.93  5349.7  184.42    5426  187.67
#Mann= 5 ,-1 , 0
  3863.2     .12       0  4669.4      .1       0  4975.5     .07       0
  5015.7      .1       0  5085.3     .05       0
Bank Sta=4975.5,5015.7
XS Rating Curve= 0 ,0
Exp/Cntr=0.3,0.1

Type RM Length L Ch R = 1 ,22000   ,500,500,500
BEGIN DESCRIPTION:
WEST FORK OF CRYSTAL CREEK 44.0
END DESCRIPTION:
XS GIS Cut Line= 3
      3859463.43     10110484.72      3859614.44     10109458.37
      3859498.36     10108814.86
#Sta/Elev= 30
  3962.6  183.08  4360.5  174.02  4544.8  172.78  4653.6  170.26  4734.5  170.28
  4744.6  171.17  4774.9  168.33  4786.5  169.59    4876  170.85  4886.1  170.72
  4906.3  168.13  4926.5  167.67  4956.8  169.34  4990.6  168.38  4996.1  166.29
    5000  166.29  5004.7  162.77  5016.8  162.77  5017.3  163.27  5017.6  166.31
  5027.7  168.27  5058.2  170.18    5109   170.5  5122.9  169.21  5138.1   169.9
  5159.8  169.85  5190.3  172.04  5220.8  171.49  5347.4  175.17  5653.9  181.14
#Mann= 5 ,-1 , 0
  3962.6     .12       0  4544.8      .1       0  4990.6     .07       0
  5027.7      .1       0  5138.1     .05       0
Bank Sta=4990.6,5027.7
XS Rating Curve= 0 ,0
Exp/Cntr=0.3,0.1

Type RM Length L Ch R = 1 ,21500   ,500,500,500
BEGIN DESCRIPTION:
WEST FORK OF CRYSTAL CREEK 43.0
END DESCRIPTION:
XS GIS Cut Line= 3
       3859966.9     10110480.39      3859998.94     10109704.35
      3859791.68     10108695.62
#Sta/Elev= 30
  4223.3  183.92  4502.9  180.96  4562.9   177.4    4713  173.14  4773.1  170.12
  4854.7  170.48  4973.3  168.95  4993.3  165.97  5004.2  166.81  5028.6  161.84
  5040.8  161.84  5044.2  164.36  5064.6  169.53  5156.5  168.35  5175.6  169.55
    5231  169.19  5268.8  170.79    5361  170.74  5401.5   170.3  5462.1  173.18
  5493.4  171.12  5528.1  172.35  5578.5  171.74  5636.3  175.31  5646.5  174.09
  5666.9   175.7  5748.6  175.51  5911.9  177.42  5971.2  179.49  6029.8  179.55
#Mann= 6 ,-1 , 0
  4223.3     .12       0  4854.7      .1       0  4973.3     .07       0
  5064.6      .1       0    5361     .12       0  5462.1     .05       0
Bank Sta=4973.3,5064.6
XS Rating Curve= 0 ,0
Exp/Cntr=0.3,0.1

Type RM Length L Ch R = 1 ,21000   ,500,500,500
BEGIN DESCRIPTION:
WEST FORK OF CRYSTAL CREEK 42.0
END DESCRIPTION:
XS GIS Cut Line= 3
      3860249.01     10110437.01      3860362.92     10109561.69
      3860617.86     10109061.06
#Sta/Elev= 30
  4117.3  182.92    4325   179.7  4425.8  176.23  4533.3  170.82  4612.2  168.69
  4708.2  168.24  4788.9  169.19  4829.2  166.91  4849.4  168.31  4879.6  167.02
  4918.4  167.14  4980.5   165.7  4990.5   164.6  4993.5  161.52  5005.9  161.52
 5017.84 165.852  5025.3  167.84  5034.4  168.69  5056.8  168.42  5158.8  172.07
  5203.2  172.58  5225.5  173.92    5270  174.71    5281  175.68  5325.5   176.1
    5395  178.23    5509  181.68  5516.9  181.32  5525.6  182.22  5561.8  182.16
#Mann= 5 ,-1 , 0
  4117.3     .12       0  4533.3      .1       0  4980.5     .07       0
 5017.84      .1       0    5395     .05       0
Bank Sta=4980.5,5017.84
XS Rating Curve= 0 ,0
Exp/Cntr=0.3,0.1

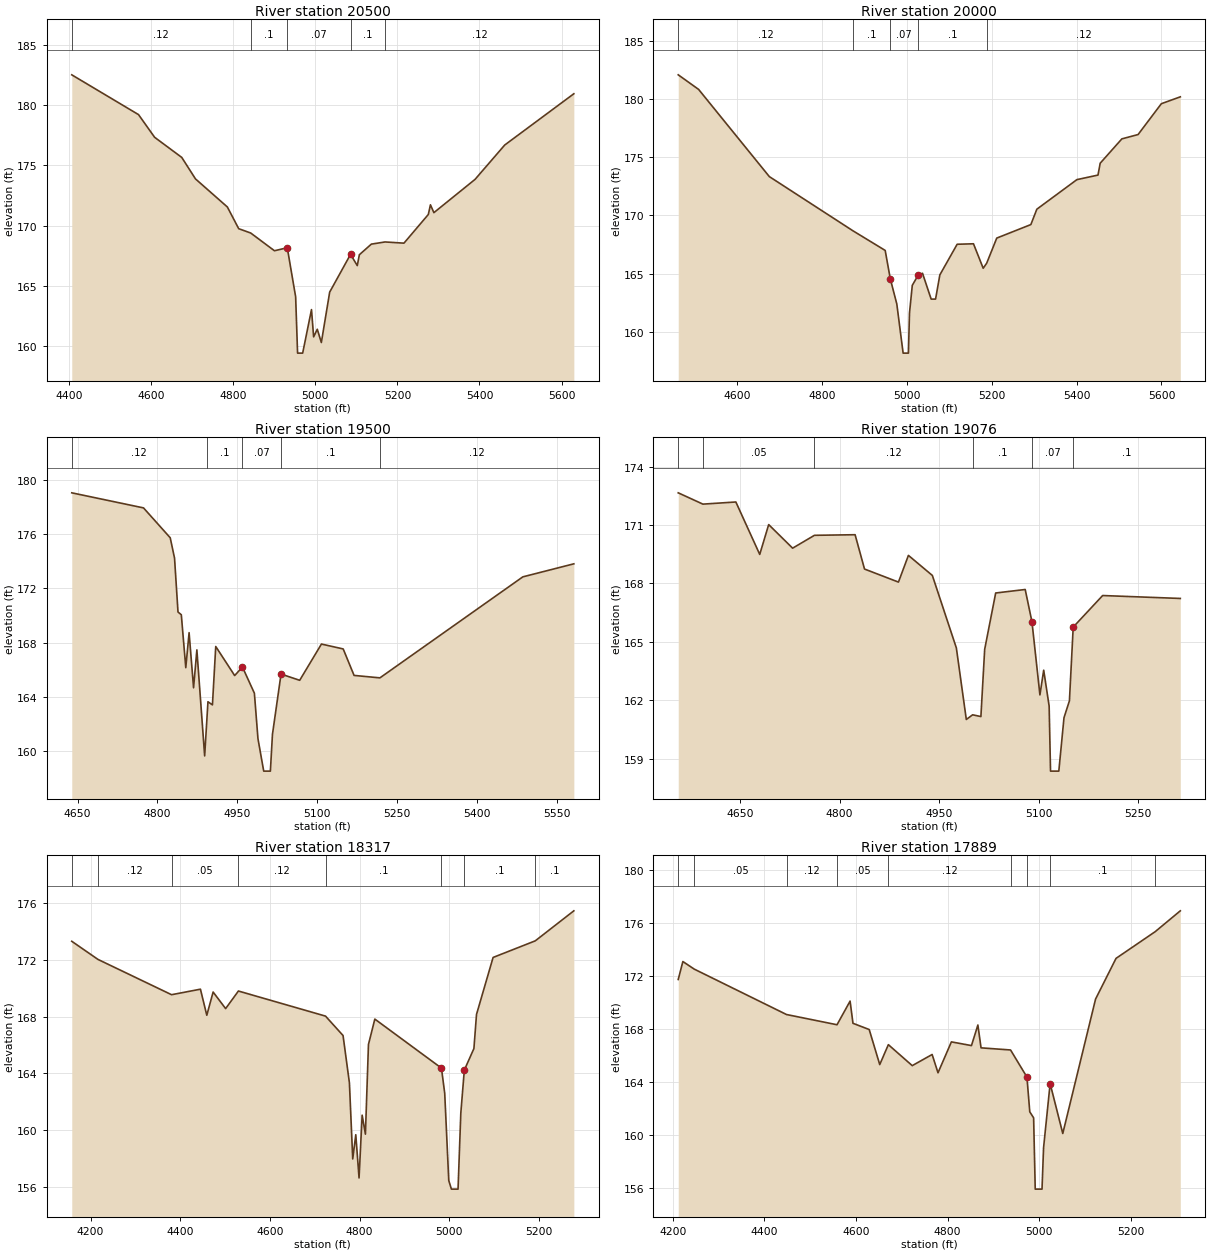
Type RM Length L Ch R = 1 ,20500   ,500,500,500
BEGIN DESCRIPTION:
WEST FORK OF CRYSTAL CREEK 41.0
END DESCRIPTION:
XS GIS Cut Line= 3
      3860427.83     10110384.72      3860594.98     10109815.66
      3860703.75     10109195.33
#Sta/Elev= 30
  4406.9   182.5  4569.5   179.2  4608.7  177.32  4674.8  175.65  4708.2  173.87
  4785.9  171.54  4813.5  169.74  4842.8  169.38  4900.6  167.91  4931.8  168.16
  4952.2  164.09  4956.9  159.42  4969.3  159.42  4990.8  163.03    4996  160.77
  5004.9   161.4  5014.8   160.3  5035.1  164.48  5085.9  167.61  5102.3  166.68
  5107.4  167.58  5136.6  168.46    5170  168.64    5216  168.54  5275.4  170.92
  5280.5  171.72  5288.9  171.07  5389.2  173.83  5461.5  176.68  5629.8  180.93
#Mann= 5 ,-1 , 0
  4406.9     .12       0  4842.8      .1       0  4931.8     .07       0
  5085.9      .1       0    5170     .12       0
Bank Sta=4931.8,5085.9
XS Rating Curve= 0 ,0
Exp/Cntr=0.3,0.1

Type RM Length L Ch R = 1 ,20000   ,500,500,500
BEGIN DESCRIPTION:
WEST FORK OF CRYSTAL CREEK 40.0
END DESCRIPTION:
XS GIS Cut Line= 3
       3860727.3     10110384.73      3860995.73     10109916.86
      3860862.83     10109286.21
#Sta/Elev= 30
  4460.6  182.08  4508.6  180.83  4675.4  173.34  4872.4  168.69  4948.6     167
  4960.6  164.57    4976   162.4  4990.9  158.18  5003.4  158.18  5005.9  161.62
  5012.5     164  5026.4  164.88  5036.6  165.04    5057  162.82  5067.4  162.82
  5077.5   164.9  5118.3  167.53  5156.8  167.57  5179.7  165.47  5187.9   165.9
  5211.7  168.06  5292.1  169.22  5306.2  170.54  5400.7  173.08  5450.4  173.47
  5455.6  174.49  5506.7  176.58  5544.9  176.95  5599.8   179.6  5644.5  180.19
#Mann= 5 ,-1 , 0
  4460.6     .12       0  4872.4      .1       0  4960.6     .07       0
  5026.4      .1       0  5187.9     .12       0
Bank Sta=4960.6,5026.4
XS Rating Curve= 0 ,0
Exp/Cntr=0.3,0.1

Type RM Length L Ch R = 1 ,19500   ,424,424,424
BEGIN DESCRIPTION:
WEST FORK OF CRYSTAL CREEK 39.0
END DESCRIPTION:
XS GIS Cut Line= 3
      3861083.43      10110285.5       3861299.4     10109996.47
      3861182.62     10109427.23
#Sta/Elev= 30
  4639.2  179.04  4773.8  177.93  4823.9  175.73    4832  174.23  4838.5  170.26
  4844.7  170.06  4853.1  166.16  4859.3  168.74  4867.7  164.68  4873.9  167.47
  4888.5  159.66  4892.8  162.43  4894.7  163.65  4903.1  163.42  4909.3  167.72
  4944.8  165.58  4959.4  166.21  4981.8  164.28  4988.5  160.93  4999.3  158.54
  5011.8  158.54  5015.7  161.25  5031.8  165.69  5066.8  165.23  5107.6   167.9
  5148.4  167.54  5168.8  165.59  5217.3  165.41  5485.4  172.85  5581.1  173.81
#Mann= 5 ,-1 , 0
  4639.2     .12       0  4892.8      .1       0  4959.4     .07       0
  5031.8      .1       0  5217.3     .12       0
Bank Sta=4959.4,5031.8
XS Rating Curve= 0 ,0
Exp/Cntr=0.3,0.1

Type RM Length L Ch R = 1 ,19076   ,759,759,759
BEGIN DESCRIPTION:
WEST FORK OF CRYSTAL CREEK 37.0
END DESCRIPTION:
XS GIS Cut Line= 3
       3861825.6     10110363.59      3861581.21     10109993.73
       3861301.5      10109851.5
#Sta/Elev= 30
  4556.7  172.65  4593.9  172.07  4643.6  172.18  4679.6  169.49  4693.1  171.02
  4729.2  169.81  4762.1  170.47  4823.4   170.5  4837.6  168.74  4888.8  168.07
  4903.8  169.44  4939.9  168.41  4976.1  164.69  4991.1  161.02  5000.6  161.26
  5013.1  161.17  5018.8  164.62  5035.4  167.51  5079.9  167.69  5090.1 166.032
  5102.1  162.28  5107.8  163.55    5116  161.71  5118.1  158.37  5130.6  158.37
  5138.4  161.11  5146.6  161.98  5152.3  165.76  5196.7  167.38  5313.8  167.23
#Mann= 6 ,-1 , 0
  4556.7     .12       0  4593.9     .05       0  4762.1     .12       0
  5000.6      .1       0  5090.1     .07       0  5152.3      .1       0
Bank Sta=5090.1,5152.3
XS Rating Curve= 0 ,0
Exp/Cntr=0.3,0.1

Type RM Length L Ch R = 1 ,18317   ,428,428,428
BEGIN DESCRIPTION:
WEST FORK OF CRYSTAL CREEK 38.0
END DESCRIPTION:
XS GIS Cut Line= 3
      3862039.33     10110194.89      3861421.18     10109623.18
      3861278.28     10109384.84
#Sta/Elev= 30
    4158  173.33  4216.5  172.05  4380.6  169.56    4445  169.95  4459.2  168.11
  4473.3  169.75  4501.2  168.58  4529.7  169.82    4724  168.05  4763.1  166.68
  4777.3  163.34  4784.7  157.97  4791.5  159.68  4798.8  156.63  4805.7  161.06
    4813  159.72  4819.8  166.05    4834  167.84  4982.6  164.38  4989.9   162.6
  4998.9  156.45  5004.8  155.84  5019.6  155.84  5025.8  161.21  5033.6  164.24
    5055  165.76  5060.8  168.17  5097.8  172.19  5191.8  173.36  5277.9  175.48
#Mann= 8 ,-1 , 0
    4158     .05       0  4216.5     .12       0  4380.6     .05       0
  4529.7     .12       0    4724      .1       0  4982.6     .07       0
  5033.6      .1       0  5191.8      .1       0
Bank Sta=4982.6,5033.6
XS Rating Curve= 0 ,0
Exp/Cntr=0.3,0.1

Type RM Length L Ch R = 1 ,17889   ,785,785,785
BEGIN DESCRIPTION:
WEST FORK OF CRYSTAL CREEK 36.0
END DESCRIPTION:
XS GIS Cut Line= 3
      3862138.24     10110095.02      3861667.17     10109463.57
       3861414.3     10109288.61
#Sta/Elev= 30
  4212.2  171.73  4222.3  173.08  4247.1  172.51  4448.4  169.09  4558.6  168.32
  4587.1   170.1  4593.4  168.43  4628.8  167.96  4651.8  165.32  4670.6  166.82
  4722.7  165.24  4766.1  166.08  4778.9   164.7  4808.1  167.03  4851.9  166.75
  4865.9   168.3  4872.8  166.58  4937.2  166.42  4972.9  164.38  4979.1  161.76
  4987.5  161.31    4991  155.94  5005.8  155.94  5009.2  159.06  5023.5  163.89
  5051.1  160.13  5122.7  170.26  5167.3  173.32  5252.7  175.33  5307.5   176.9
#Mann= 9 ,-1 , 0
  4212.2     .12       0  4247.1     .05       0  4448.4     .12       0
  4558.6     .05       0  4670.6     .12       0  4937.2      .1       0
  4972.9     .07       0  5023.5      .1       0  5252.7     .12       0
Bank Sta=4972.9,5023.5
XS Rating Curve= 0 ,0
Exp/Cntr=0.3,0.1

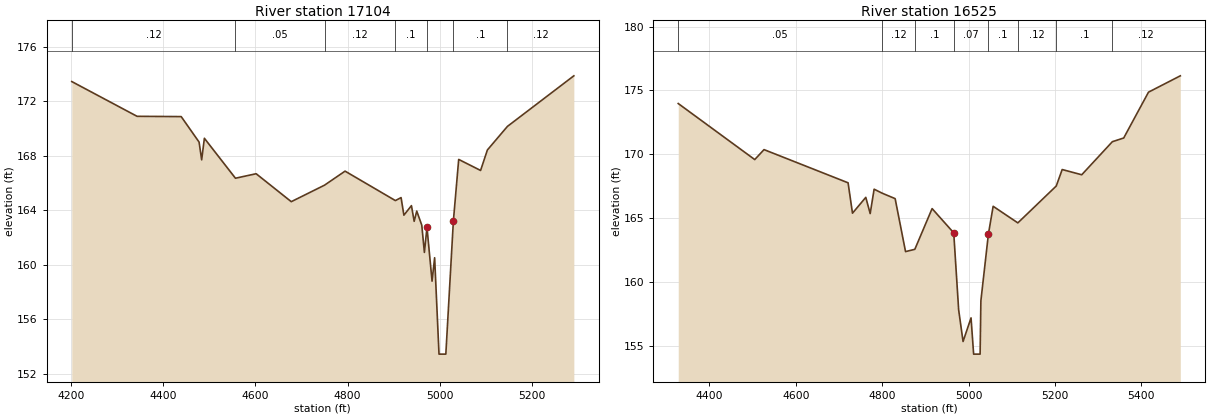
Type RM Length L Ch R = 1 ,17104   ,579,579,579
BEGIN DESCRIPTION:
WEST FORK OF CRYSTAL CREEK 34.0
END DESCRIPTION:
XS GIS Cut Line= 3
      3862291.01     10110067.22       3861927.7     10109356.38
      3861815.32     10109088.06
#Sta/Elev= 30
  4201.7  173.44  4343.4  170.89  4439.1  170.87  4477.9     169  4483.5   167.7
  4489.4  169.28  4556.8  166.35  4601.7  166.68  4677.9  164.63    4750  165.84
  4794.6  166.87  4903.8  164.71  4916.1  164.93  4922.2  163.64  4938.6  164.34
  4944.5  163.19  4950.1  163.94    4961  162.91  4966.7  160.91  4972.3  162.75
  4983.3   158.8  4988.9  160.52  4998.4  153.45  5013.2  153.45 5029.53 163.198
  5041.1  167.73  5088.6  166.92  5103.3  168.42  5146.8  170.15  5290.9  173.86
#Mann= 7 ,-1 , 0
  4201.7     .12       0  4556.8     .05       0    4750     .12       0
  4903.8      .1       0  4972.3     .07       0 5029.53      .1       0
  5146.8     .12       0
Bank Sta=4972.3,5029.53
XS Rating Curve= 0 ,0
Exp/Cntr=0.3,0.1

Type RM Length L Ch R = 1 ,16525   ,494,494,494
BEGIN DESCRIPTION:
WEST FORK OF CRYSTAL CREEK 33.0
END DESCRIPTION:
XS GIS Cut Line= 3
      3862512.18     10110005.08      3862365.96     10109347.24
      3862158.73     10108904.31
#Sta/Elev= 30
  4327.6  173.97  4504.8  169.58  4526.3  170.36    4721  167.76  4731.2  165.38
    4762  166.62  4772.2  165.35  4781.3  167.26  4800.4  166.94    4830  166.52
  4854.1  162.37  4875.6  162.55  4915.6  165.74  4965.7  163.84  4977.1  157.81
  4987.3  155.33  5005.8  157.18  5011.8  154.34  5026.8  154.34  5028.6  158.52
 5046.03 163.745    5057  165.92  5114.2  164.62  5203.2  167.51  5216.9   168.8
  5262.2  168.39  5333.1  170.98  5359.4  171.27  5416.8  174.86  5490.5  176.14
#Mann= 8 ,-1 , 0
  4327.6     .05       0  4800.4     .12       0  4875.6      .1       0
  4965.7     .07       0 5046.03      .1       0  5114.2     .12       0
  5203.2      .1       0  5333.1     .12       0
Bank Sta=4965.7,5046.03
XS Rating Curve= 0 ,0
Exp/Cntr=0.3,0.1