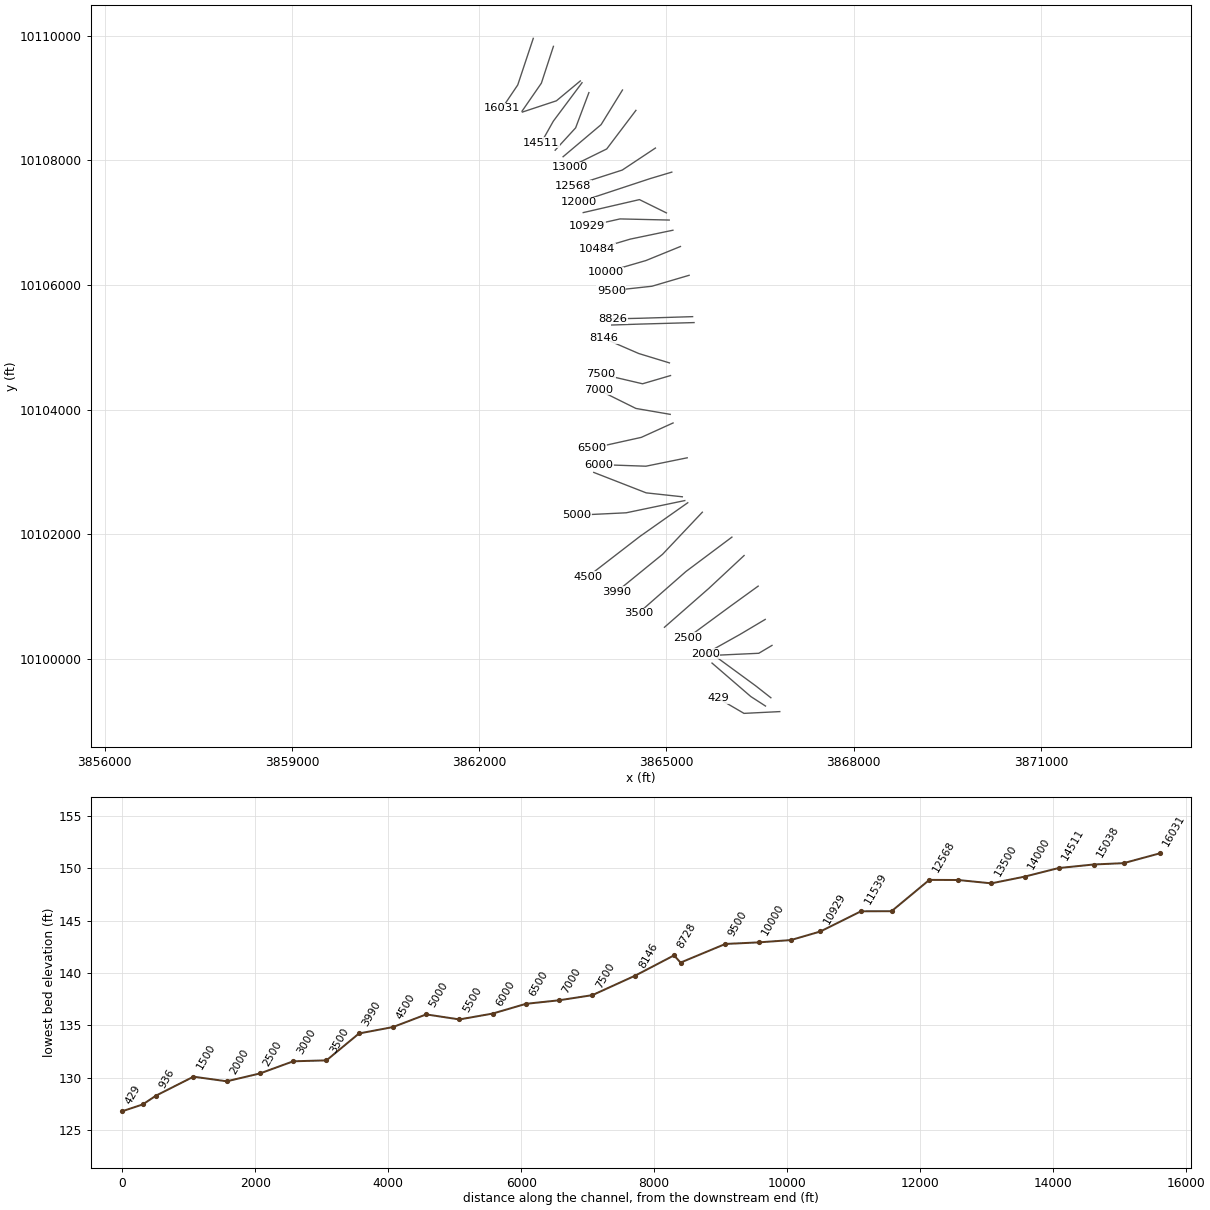
HEC-RAS study WEST FORK OF CRYSTAL CREEK.prj: WEST FORK OF CRYSTAL CREEK Base Level Engineering

--- WEST FORK OF CRYSTAL CREEK.g10 (geometry) --- (continued)

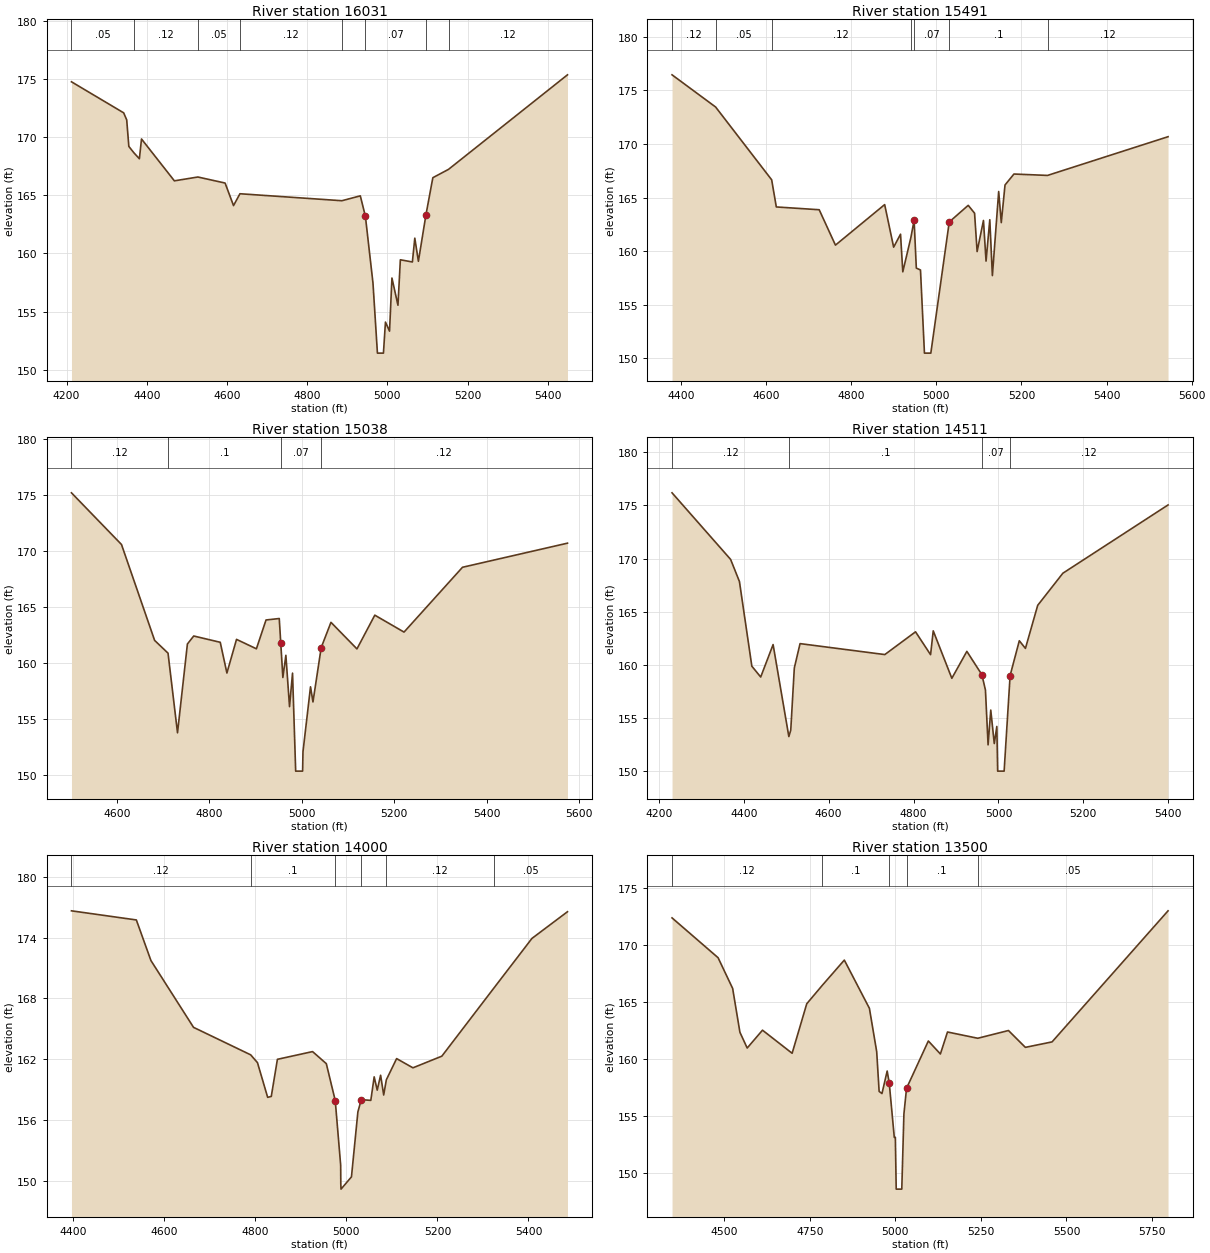
Type RM Length L Ch R = 1 ,16031   ,540,540,540
BEGIN DESCRIPTION:
WEST FORK OF CRYSTAL CREEK 32.0
END DESCRIPTION:
XS GIS Cut Line= 3
       3862867.1     10109954.62      3862618.27     10109207.15
      3862367.21     10108834.54
#Sta/Elev= 30
  4212.2  174.76  4342.4  172.09    4350  171.48  4355.3   169.2    4368  168.65
  4381.6  168.14  4386.9  169.84  4468.9  166.24  4527.5  166.57  4595.4  166.05
  4616.4  164.11  4632.4  165.13  4886.7  164.53  4932.6  164.95 4945.27 163.196
  4964.2  157.45  4975.3  151.42  4990.3  151.42  4995.3  154.09  5005.5  153.31
  5011.5  157.88  5026.5  155.54  5032.5  159.45  5062.5  159.26  5068.5  161.31
  5077.5  159.32 5096.21 163.297  5113.5  166.51  5152.7  167.23  5449.3  175.36
#Mann= 8 ,-1 , 0
  4212.2     .05       0    4368     .12       0  4527.5     .05       0
  4632.4     .12       0  4886.7      .1       0 4945.27     .07       0
 5096.21      .1       0  5152.7     .12       0
Bank Sta=4945.27,5096.21
XS Rating Curve= 0 ,0
Exp/Cntr=0.3,0.1

Type RM Length L Ch R = 1 ,15491   ,453,453,453
BEGIN DESCRIPTION:
WEST FORK OF CRYSTAL CREEK 31.0
END DESCRIPTION:
XS GIS Cut Line= 3
      3863190.01     10109826.12      3862996.77     10109235.53
      3862687.39     10108787.47
#Sta/Elev= 30
  4378.6  176.44    4481  173.44  4612.8  166.65  4623.7  164.12  4724.5  163.86
  4762.7  160.56  4878.4  164.34  4899.5  160.37  4915.7  161.58    4921  158.07
  4939.8  161.23  4947.6  162.87  4952.8  158.42  4962.6  158.24  4971.9  150.49
  4986.9  150.49  5030.2  162.72  5074.8  164.27  5089.7  163.54  5095.7  159.96
  5110.6  162.86  5116.7  159.07  5125.5  162.93  5131.6  157.72  5146.4  165.56
  5152.5  162.66  5161.3  166.17  5182.3  167.19  5261.2  167.06  5544.5  170.67
#Mann= 7 ,-1 , 0
  4378.6     .12       0    4481     .05       0  4612.8     .12       0
  4939.8      .1       0  4947.6     .07       0  5030.2      .1       0
  5261.2     .12       0
Bank Sta=4947.6,5030.2
XS Rating Curve= 0 ,0
Exp/Cntr=0.3,0.1

Type RM Length L Ch R = 1 ,15038   ,527,527,527
BEGIN DESCRIPTION:
WEST FORK OF CRYSTAL CREEK 30.0
END DESCRIPTION:
XS GIS Cut Line= 3
      3863620.61     10109271.48      3863237.74     10108953.02
      3862692.34     10108772.51
#Sta/Elev= 30
    4502  175.18  4610.2  170.57  4681.8  162.02  4710.8  160.88  4731.3  153.78
  4752.7   161.7  4766.4  162.41  4823.7  161.85  4838.1  159.11  4858.9  162.11
  4901.9  161.27  4922.7  163.84  4951.3  163.97 4954.59 161.751  4959.1  158.71
  4965.6  160.69  4973.5  156.11    4980   159.1  4986.8  150.36  5001.8  150.36
  5002.6  152.09  5018.9  157.88  5024.2  156.53    5042  161.38  5063.1  163.63
  5119.3  161.26  5157.9  164.27  5221.1  162.76  5347.5  168.54  5574.5  170.69
#Mann= 4 ,-1 , 0
    4502     .12       0  4710.8      .1       0 4954.59     .07       0
    5042     .12       0
Bank Sta=4954.59,5042
XS Rating Curve= 0 ,0
Exp/Cntr=0.3,0.1

Type RM Length L Ch R = 1 ,14511   ,511,511,511
BEGIN DESCRIPTION:
WEST FORK OF CRYSTAL CREEK 29.0
END DESCRIPTION:
XS GIS Cut Line= 3
      3863648.32     10109242.76      3863188.29     10108626.54
      3862992.48      10108278.2
#Sta/Elev= 30
    4231  176.19    4369  169.93  4389.8  167.85    4419  159.89  4439.9  158.87
  4469.1  161.92  4506.2  153.27  4510.7  153.87  4519.1  159.72  4532.6  162.01
  4732.3  160.98  4804.7  163.12  4840.1  160.97  4846.4  163.21  4890.2  158.75
  4925.6  161.28    4961  159.09  4969.4  157.64  4975.6  152.49  4981.9  155.76
  4990.2  152.61  4996.2  154.22  4998.2  150.02  5013.4  150.02  5027.5  159.01
  5049.2  162.28  5063.6  161.56  5092.5  165.61  5151.8  168.63  5399.6  175.05
#Mann= 4 ,-1 , 0
    4231     .12       0  4506.2      .1       0    4961     .07       0
  5027.5     .12       0
Bank Sta=4961,5027.5
XS Rating Curve= 0 ,0
Exp/Cntr=0.3,0.1

Type RM Length L Ch R = 1 ,14000   ,500,500,500
BEGIN DESCRIPTION:
WEST FORK OF CRYSTAL CREEK 28.0
END DESCRIPTION:
XS GIS Cut Line= 3
      3863758.13     10109084.43      3863545.71     10108519.33
      3863217.87      10108161.1
#Sta/Elev= 30
  4396.3  176.64  4538.8  175.74  4570.8  171.74  4664.4  165.15  4789.9  162.44
  4804.8  161.67  4827.2  158.25  4835.1  158.34  4848.6     162  4925.8  162.76
    4956  161.57  4975.6  157.93  4987.5  151.56  4987.8   149.7  4988.3   149.2
  5011.2  150.41  5025.3  156.81  5032.7  158.02  5053.7  157.95  5061.1  160.27
  5067.8  158.96  5075.2  160.43    5082  158.48  5087.8  159.98  5110.4  162.07
  5146.2  161.16  5209.7  162.31  5324.6  169.06  5407.6  173.92  5485.6  176.55
#Mann= 6 ,-1 , 0
  4396.3     .12       0  4789.9      .1       0  4975.6     .07       0
  5032.7      .1       0  5087.8     .12       0  5324.6     .05       0
Bank Sta=4975.6,5032.7
XS Rating Curve= 0 ,0
Exp/Cntr=0.3,0.1

Type RM Length L Ch R = 1 ,13500   ,500,500,500
BEGIN DESCRIPTION:
WEST FORK OF CRYSTAL CREEK 27.0
END DESCRIPTION:
XS GIS Cut Line= 3
      3864296.29     10109126.02      3863953.58     10108570.77
      3863344.89     10108056.58
#Sta/Elev= 30
  4347.5   172.4    4482   168.9  4524.6   166.2  4545.8  162.35  4567.1  160.96
  4611.8  162.53  4698.4   160.5  4741.1  164.85  4786.5  166.47  4850.9  168.69
  4924.2  164.45  4945.5  160.64  4952.6  157.15  4960.9  156.96  4976.1  158.94
  4982.2  157.87  4996.9  153.11    5000  153.11  5002.5  148.56  5018.8  148.56
    5025  155.16  5032.7  157.42  5096.4  161.58  5131.6  160.44  5152.4  162.37
  5240.8  161.82  5330.5   162.5  5379.9  161.02  5457.9   161.5  5796.8  173.02
#Mann= 5 ,-1 , 0
  4347.5     .12       0  4786.5      .1       0  4982.2     .07       0
  5032.7      .1       0  5240.8     .05       0
Bank Sta=4982.2,5032.7
XS Rating Curve= 0 ,0
Exp/Cntr=0.3,0.1

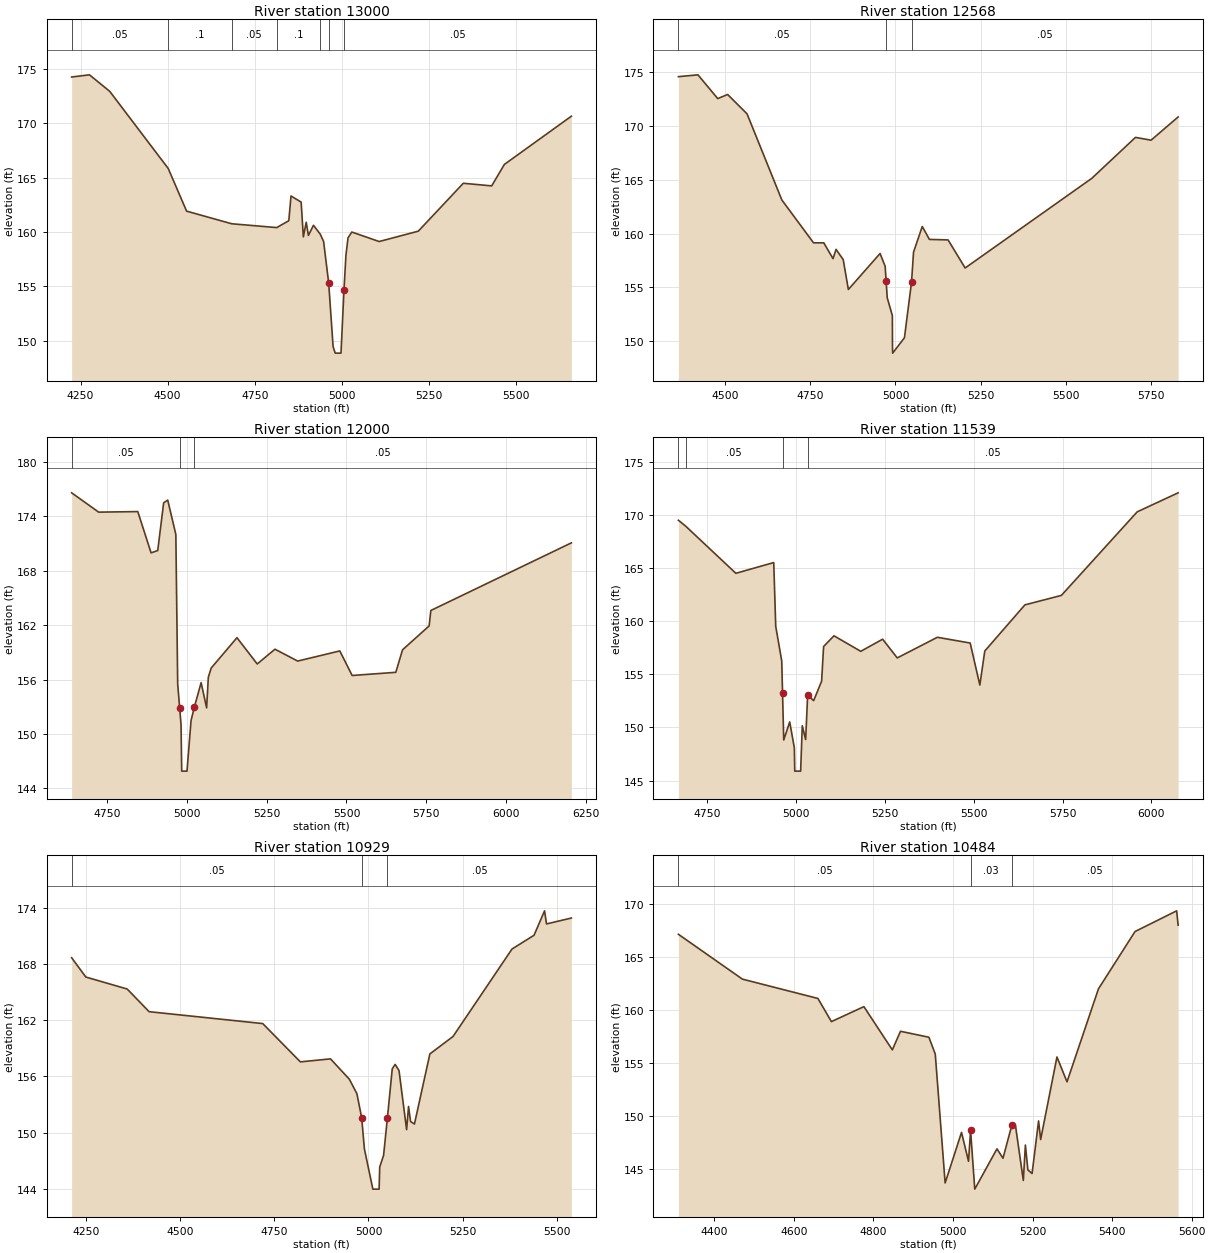
Type RM Length L Ch R = 1 ,13000   ,432,432,432
BEGIN DESCRIPTION:
WEST FORK OF CRYSTAL CREEK 26.0
END DESCRIPTION:
XS GIS Cut Line= 3
      3864511.62      10108799.7      3864043.78     10108181.09
      3863452.67       10107890.
#Sta/Elev= 30
  4224.4  174.24  4275.6  174.44  4333.8  172.92  4501.6  165.84  4554.4  161.92
  4684.1  160.76  4813.1  160.41  4847.8  161.04  4854.1  163.31  4883.2  162.75
  4889.5  159.56  4897.8   160.9    4904  159.69  4918.6  160.62    4938  159.81
  4947.7  159.13  4962.3  155.31  4974.9  149.48  4981.1  148.88  4997.6  148.88
  5006.2  154.71  5011.8  157.88  5017.8  159.47  5028.7     160  5107.2  159.13
  5219.5  160.08  5348.7  164.48  5430.2  164.24  5466.6  166.21  5658.9  170.64
#Mann= 7 ,-1 , 0
  4224.4     .05       0  4501.6      .1       0  4684.1     .05       0
  4813.1      .1       0    4938     .05       0  4962.3     .07       0
  5006.2     .05       0
Bank Sta=4962.3,5006.2
XS Rating Curve= 0 ,0
Exp/Cntr=0.3,0.1

Type RM Length L Ch R = 1 ,12568   ,568,568,568
BEGIN DESCRIPTION:
WEST FORK OF CRYSTAL CREEK 25.0
END DESCRIPTION:
XS GIS Cut Line= 3
       3864824.1     10108195.51      3864292.72     10107842.58
      3863502.06     10107588.14
#Sta/Elev= 30
  4362.1  174.61  4419.5  174.78  4477.6  172.57  4506.7  172.95  4563.8  171.15
    4666  163.14  4759.2  159.15  4789.3  159.15  4816.4  157.68  4825.4  158.54
  4846.4  157.59  4861.5  154.81  4954.7  158.16  4969.7  156.96 4972.56 155.573
  4975.7  154.05  4990.8  152.38  4991.2  149.39  4991.7  148.89  5026.3  150.32
  5047.1  155.48  5053.1  158.29  5078.7  160.67  5099.7  159.47  5154.6  159.42
  5204.7  156.81  5576.9  165.15  5705.2  168.96    5751   168.7  5830.6  170.86
#Mann= 3 , 0 , 0
  4362.1     .05       0 4972.56     .07       0  5047.1     .05       0
Bank Sta=4972.56,5047.1
XS Rating Curve= 0 ,0
Exp/Cntr=0.3,0.1

Type RM Length L Ch R = 1 ,12000   ,461,461,461
BEGIN DESCRIPTION:
WEST FORK OF CRYSTAL CREEK 24.0
END DESCRIPTION:
XS GIS Cut Line= 3
      3865086.61     10107809.63      3864739.61     10107705.81
      3863594.92     10107327.44
#Sta/Elev= 30
  4637.8   176.6  4722.6  174.47  4845.3  174.53    4887  169.98  4907.9  170.23
  4926.4  175.49  4939.2   175.8  4964.7  172.01  4970.5  155.53  4976.7 152.879
    4981  151.04  4983.1   145.9  4999.7   145.9  5012.4  151.48  5022.9  152.98
    5044  155.66  5061.3  152.88  5066.6  156.25  5075.6  157.27  5156.5  160.62
    5220  157.72  5275.7  159.35  5346.9  158.04  5479.1  159.16  5517.9  156.45
  5654.8   156.8  5675.9  159.28  5759.4  161.92  5764.7  163.62  6205.6  171.08
#Mann= 3 , 0 , 0
  4637.8     .05       0  4976.7     .07       0  5022.9     .05       0
Bank Sta=4976.7,5022.9
XS Rating Curve= 0 ,0
Exp/Cntr=0.3,0.1

Type RM Length L Ch R = 1 ,11539   ,610,610,610
BEGIN DESCRIPTION:
WEST FORK OF CRYSTAL CREEK 23.0
END DESCRIPTION:
XS GIS Cut Line= 3
      3865000.33     10107155.84      3864568.48     10107368.98
      3863667.82     10107160.77
#Sta/Elev= 30
  4669.3  169.49  4690.2  168.92  4830.9   164.5  4937.5  165.51  4943.1  159.51
    4960  156.25 4962.26 153.252  4965.6  148.82  4982.4  150.52  4995.5  148.08
  4996.6  145.89  5013.2  145.89  5017.8  150.16  5027.3  148.86  5032.9  153.03
  5049.8  152.52  5072.2  154.35  5077.8  157.61    5107  158.62  5182.3  157.16
  5243.9   158.3    5285  156.54  5397.9  158.48  5490.2  157.94  5517.4  153.99
  5531.3  157.19  5644.2  161.53  5746.8  162.42  5960.1  170.28  6075.3  172.07
#Mann= 4 ,-1 , 0
  4669.3     .12       0  4690.2     .05       0 4962.26     .07       0
  5032.9     .05       0
Bank Sta=4962.26,5032.9
XS Rating Curve= 0 ,0
Exp/Cntr=0.3,0.1

Type RM Length L Ch R = 1 ,10929   ,445,445,445
BEGIN DESCRIPTION:
WEST FORK OF CRYSTAL CREEK 22.0
END DESCRIPTION:
XS GIS Cut Line= 3
      3865045.44     10107041.28      3864256.95     10107059.39
      3863731.12     10106940.95
#Sta/Elev= 30
  4211.3  168.67  4248.9  166.61  4358.9  165.33  4417.1  162.91    4719  161.64
    4819  157.55  4899.1  157.87  4949.1   155.7  4969.1  154.16 4981.81 151.606
  4989.1  148.26  5011.6  143.96  5028.2  143.96  5029.8  146.32  5040.1  147.57
  5050.3  151.59  5063.1   156.8  5070.8  157.28  5081.1  156.62  5101.3  150.31
  5106.4  152.79  5111.8  151.18  5122.1  150.91  5163.1   158.4  5224.6  160.26
  5381.3   169.6  5439.8  171.07  5467.8  173.68    5473  172.28    5539  172.91
#Mann= 3 , 0 , 0
  4211.3     .05       0 4981.81     .07       0  5050.3     .05       0
Bank Sta=4981.81,5050.3
XS Rating Curve= 0 ,0
Exp/Cntr=0.3,0.1

Type RM Length L Ch R = 1 ,10484   ,484,484,484
BEGIN DESCRIPTION:
WEST FORK OF CRYSTAL CREEK 21.0
END DESCRIPTION:
XS GIS Cut Line= 3
      3865104.45     10106878.08      3864420.98     10106735.56
      3863885.83     10106576.03
#Sta/Elev= 30
  4309.5  167.13  4470.4  162.91  4660.3  161.09  4694.2  158.91  4775.9  160.32
  4847.4  156.25  4867.9     158  4939.4  157.44  4955.4  155.85  4980.2  143.72
  5021.4  148.48    5039  145.76  5044.2  148.66  5054.7  143.14  5110.5  146.93
  5125.7  146.05 5147.85  149.15    5157  149.15  5176.8  143.96    5182  147.29
  5188.3  144.95  5198.8  144.61  5215.2  149.56  5220.4  147.81  5261.4  155.58
  5286.7  153.24  5365.7  161.99  5457.7  167.39  5562.4  169.34  5566.1  167.99
#Mann= 3 , 0 , 0
  4309.5     .05       0  5044.2     .03       0 5147.85     .05       0
Bank Sta=5044.2,5147.85
XS Rating Curve= 0 ,0
Exp/Cntr=0.3,0.1

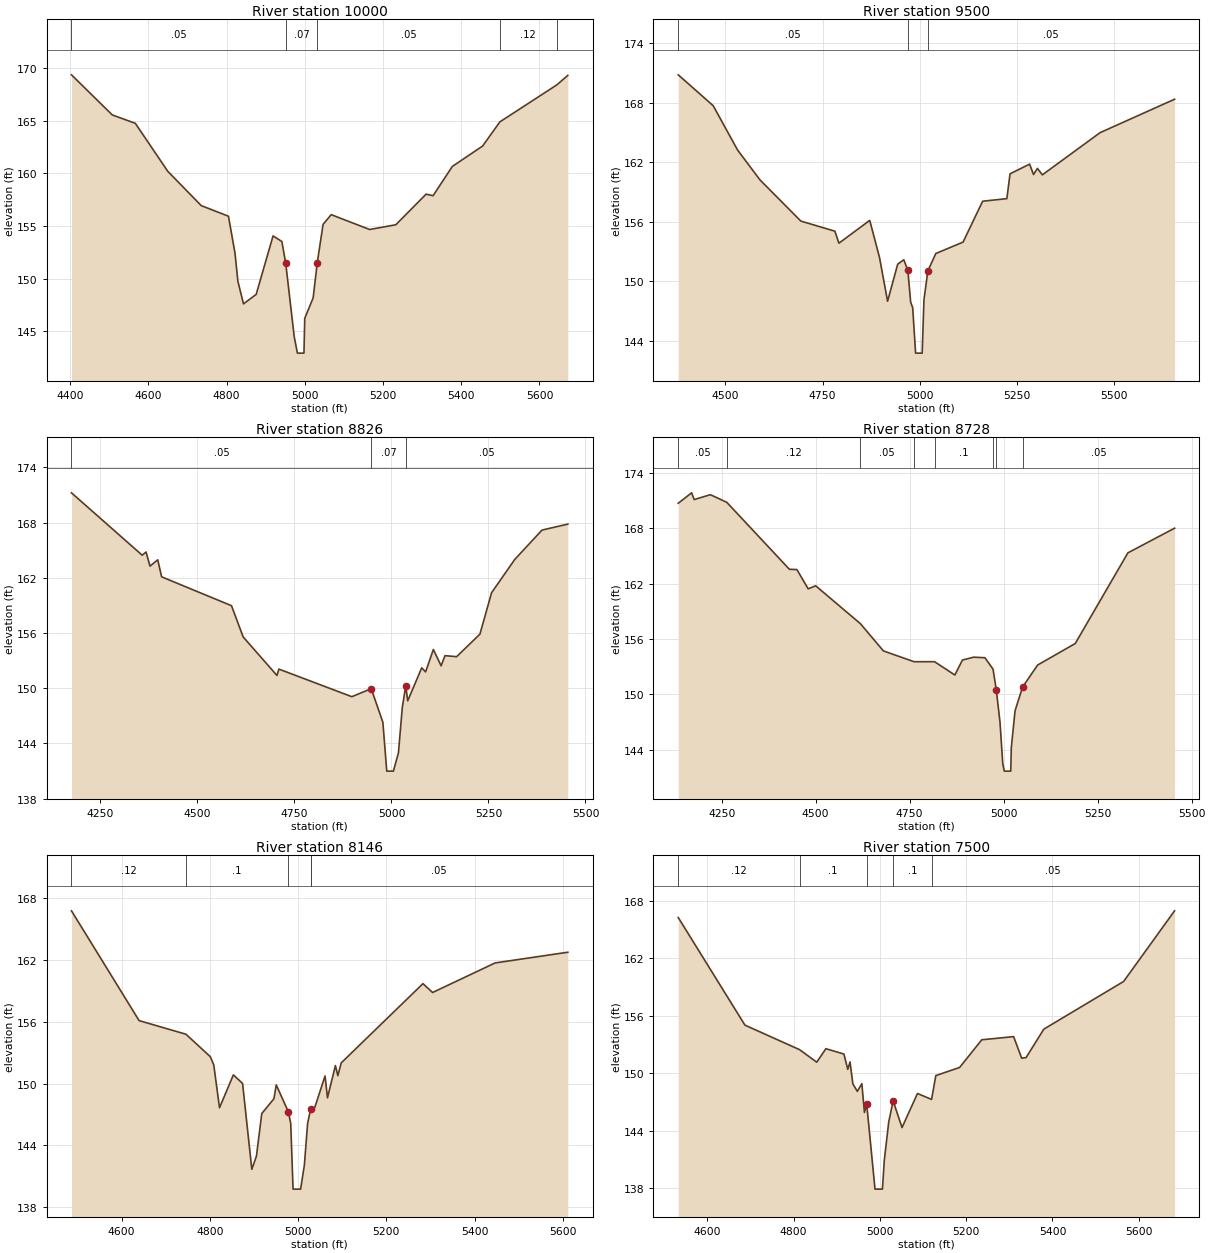
Type RM Length L Ch R = 1 ,10000   ,500,500,500
BEGIN DESCRIPTION:
WEST FORK OF CRYSTAL CREEK 20.0
END DESCRIPTION:
XS GIS Cut Line= 3
      3865225.09     10106617.21      3864672.84     10106392.28
      3864027.22     10106204.04
#Sta/Elev= 30
  4403.7  169.37    4508  165.56  4566.9  164.76  4649.9   160.2  4735.4  156.94
    4805  155.93  4821.8   152.4  4829.1  149.75  4843.4   147.6  4875.8   148.5
    4919  154.06  4941.5  153.53  4951.4  151.46    4973  144.51  4981.2  142.92
    4998  142.92    5000  146.23  5021.5  148.17 5031.81 151.461  5046.9  155.16
  5067.7  156.08  5165.9  154.67  5232.8  155.12  5310.2  158.03  5328.1  157.88
  5377.2  160.66  5454.6   162.6  5498.9   164.9  5644.3  168.41  5672.5  169.32
#Mann= 5 ,-1 , 0
  4403.7     .05       0  4951.4     .07       0 5031.81     .05       0
  5498.9     .12       0  5644.3     .05       0
Bank Sta=4951.4,5031.81
XS Rating Curve= 0 ,0
Exp/Cntr=0.3,0.1

Type RM Length L Ch R = 1 ,9500    ,674,674,674
BEGIN DESCRIPTION:
WEST FORK OF CRYSTAL CREEK 19.0
END DESCRIPTION:
XS GIS Cut Line= 3
      3865364.01     10106155.42       3864768.4     10105980.01
      3864117.48     10105908.89
#Sta/Elev= 30
  4379.1  170.82  4468.9  167.71  4531.5  163.25    4589  160.24  4694.2  156.08
  4781.7  155.06  4792.1  153.85  4871.3  156.15  4896.3  152.43  4917.2     148
  4943.2  151.74  4958.9  152.18  4969.3   151.1  4976.5   147.9  4981.7  147.35
  4989.2  142.77  5006.1  142.77  5010.6  148.13  5020.7  151.06  5041.1  152.81
  5111.2  153.96  5161.5  158.08  5223.7  158.34  5231.9  160.84  5282.2  161.82
  5292.3  160.77  5302.3  161.39    5315  160.74  5463.3  164.99  5654.8  168.36
#Mann= 3 , 0 , 0
  4379.1     .05       0  4969.3     .07       0  5020.7     .05       0
Bank Sta=4969.3,5020.7
XS Rating Curve= 0 ,0
Exp/Cntr=0.3,0.1

Type RM Length L Ch R = 1 ,8826    ,98,98,98
BEGIN DESCRIPTION:
WEST FORK OF CRYSTAL CREEK 18.0
END DESCRIPTION:
XS GIS Cut Line= 3
      3865420.01     10105492.55       3864595.8     10105466.99
      3864141.42     10105456.83
#Sta/Elev= 30
  4175.4  171.24  4357.6  164.46  4367.6  164.81  4377.7  163.27  4397.7  163.96
  4407.7  162.11  4587.8  158.97  4617.8  155.58  4704.9  151.39  4709.9  152.08
  4897.9  149.08  4947.9  149.95  4977.9   146.3  4987.9  140.99    5005  140.99
    5018  142.98    5028  147.92  5036.9  150.27  5041.9  148.63    5078  152.22
    5088  151.77    5108  154.21    5128  152.44    5138  153.54    5168  153.43
    5228  155.88    5258  160.38    5318  164.01    5388  167.19  5454.5  167.84
#Mann= 3 , 0 , 0
  4175.4     .05       0  4947.9     .07       0  5036.9     .05       0
Bank Sta=4947.9,5036.9
XS Rating Curve= 0 ,0
Exp/Cntr=0.3,0.1

Type RM Length L Ch R = 1 ,8728    ,582,582,582
BEGIN DESCRIPTION:
WEST FORK OF CRYSTAL CREEK 17.0
END DESCRIPTION:
XS GIS Cut Line= 3
      3865443.35     10105397.31      3864578.18     10105373.21
      3864123.83     10105358.24
#Sta/Elev= 30
  4134.5  170.69    4170  171.82    4177  171.09    4220  171.62  4263.7  170.79
  4430.1  163.54  4450.1  163.51  4480.1  161.42  4500.1  161.75    4619  157.65
  4680.2   154.7  4761.6  153.53  4816.2  153.53  4870.3  152.09  4890.3  153.71
  4920.3  154.02  4950.3  153.96  4971.8  152.72  4980.3  150.52  4990.3  146.98
  4997.7  142.46  5001.8  141.68  5018.9  141.68  5020.3   144.2  5030.3  148.21
  5050.4  150.79  5090.4  153.17  5190.4   155.5  5330.5  165.32  5454.6  167.99
#Mann= 8 ,-1 , 0
  4134.5     .05       0  4263.7     .12       0    4619     .05       0
  4761.6     .12       0  4816.2      .1       0  4971.8     .05       0
  4980.3     .07       0  5050.4     .05       0
Bank Sta=4980.3,5050.4
XS Rating Curve= 0 ,0
Exp/Cntr=0.3,0.1

Type RM Length L Ch R = 1 ,8146    ,646,646,646
BEGIN DESCRIPTION:
WEST FORK OF CRYSTAL CREEK 16.0
END DESCRIPTION:
XS GIS Cut Line= 3
      3865048.72     10104751.03      3864557.64     10104901.11
      3863996.67     10105144.25
#Sta/Elev= 30
  4486.5  166.77  4639.8  156.11  4745.9  154.79  4801.1  152.61    4809  151.81
    4822  147.65  4853.4  150.84  4874.3  150.01  4895.2  141.68  4905.7  142.95
  4917.8  147.09  4945.4  148.53  4950.6  149.87  4978.2  147.24  4983.4  146.14
  4988.7  139.75  5005.8  139.75  5014.3  142.07  5021.6   146.1  5028.6  147.55
  5037.8  147.66  5061.2  150.74  5066.7  148.62  5084.7  151.74  5090.2  150.77
  5097.9  152.01  5283.1   159.7  5304.9  158.84  5446.6  161.71  5611.4  162.75
#Mann= 5 ,-1 , 0
  4486.5     .12       0  4745.9      .1       0  4978.2     .07       0
  5028.6      .1       0  5028.6     .05       0
Bank Sta=4978.2,5028.6
XS Rating Curve= 0 ,0
Exp/Cntr=0.3,0.1

Type RM Length L Ch R = 1 ,7500    ,500,500,500
BEGIN DESCRIPTION:
WEST FORK OF CRYSTAL CREEK 15.0
END DESCRIPTION:
XS GIS Cut Line= 3
      3865066.14      10104547.9      3864617.88     10104416.23
      3863952.83     10104571.77
#Sta/Elev= 30
  4532.8  166.25  4687.4  155.01  4813.9  152.45  4853.8  151.14    4875  152.55
  4916.7  151.99  4925.7  150.39  4930.9  151.17  4937.5  148.87  4947.9  148.09
  4958.3   148.9  4964.3  145.89  4969.5  146.79  4988.8  137.88    5006  137.88
  5010.3  140.88  5020.6  144.89  5030.8   147.1  5051.4  144.31  5087.2  147.87
  5119.9  147.25  5129.7  149.74  5184.9  150.59  5236.2  153.48    5310  153.81
  5328.7  151.56  5338.9  151.62    5380  154.59  5564.9  159.57    5683  166.95
#Mann= 5 ,-1 , 0
  4532.8     .12       0  4813.9      .1       0  4969.5     .07       0
  5030.8      .1       0  5119.9     .05       0
Bank Sta=4969.5,5030.8
XS Rating Curve= 0 ,0
Exp/Cntr=0.3,0.1

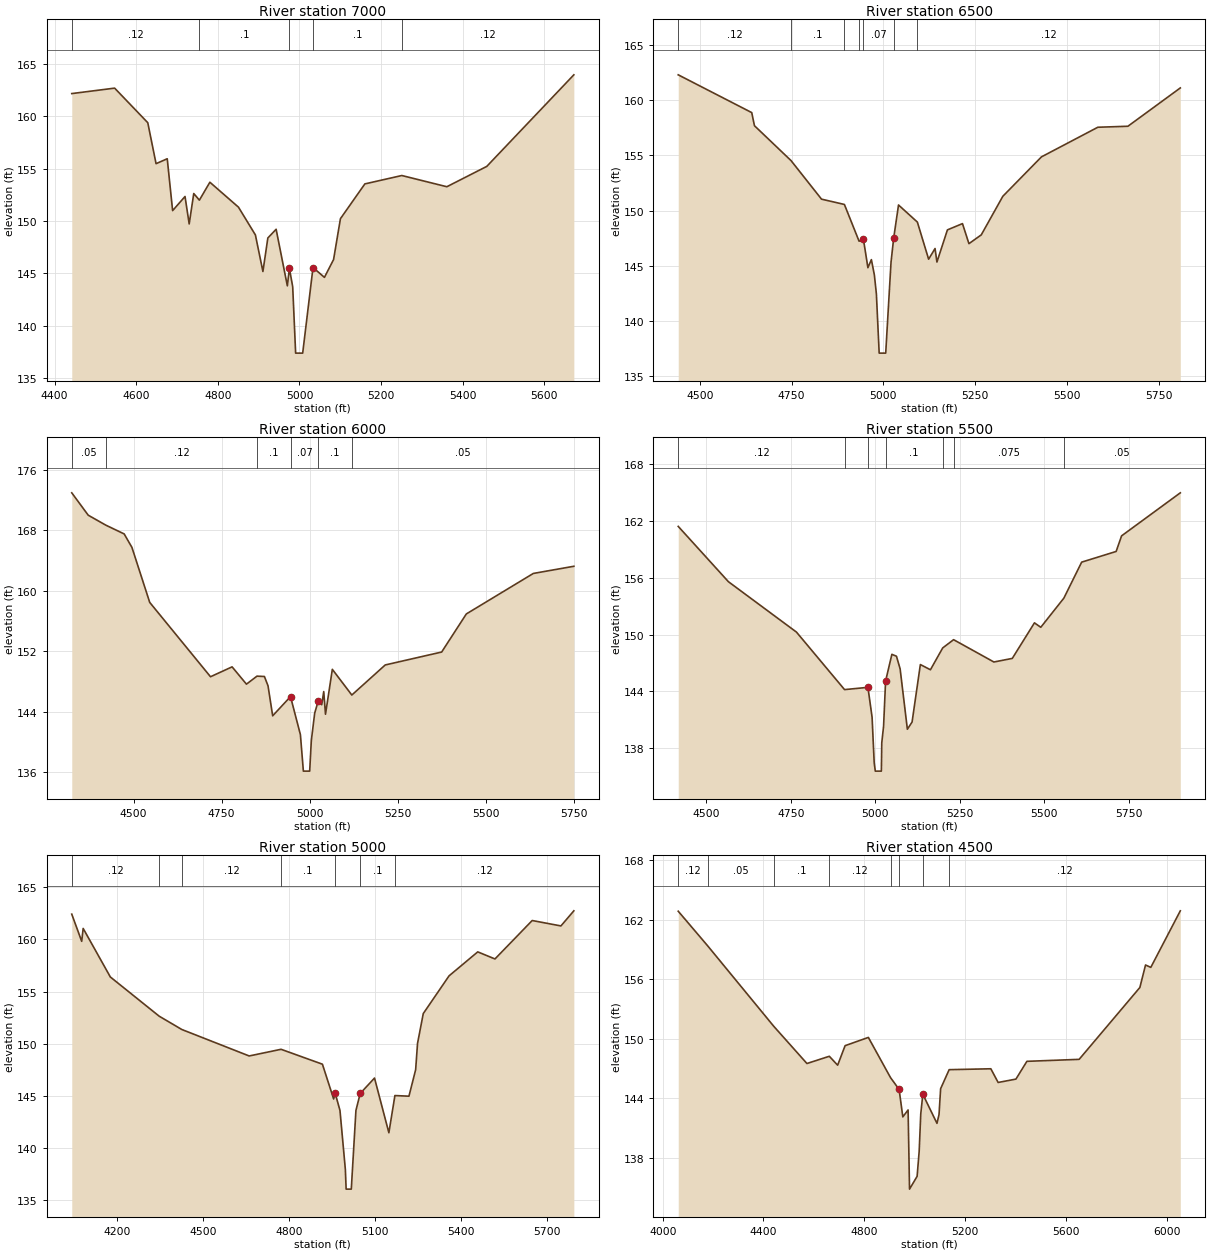
Type RM Length L Ch R = 1 ,7000    ,500,500,500
BEGIN DESCRIPTION:
WEST FORK OF CRYSTAL CREEK 14.0
END DESCRIPTION:
XS GIS Cut Line= 3
      3865061.45     10103925.99      3864511.45     10104020.76
        3863909.      10104319.6
#Sta/Elev= 30
  4441.9  162.16    4547  162.68  4628.2  159.38  4648.5  155.47  4675.9  155.94
  4689.1  150.99  4719.5  152.34  4729.7  149.72  4740.9  152.62  4754.7  151.99
  4780.4   153.7  4850.5  151.32    4892  148.67  4910.4  145.18  4922.5  148.38
  4942.8  149.21  4970.3  143.81  4975.3  145.48  4983.4  143.73  4990.6  137.39
  5007.9  137.39  5033.2  145.56  5061.2  144.62  5083.6  146.32  5100.4  150.22
  5160.3  153.54  5250.9  154.34  5361.2  153.27  5459.1  155.21  5672.5  163.95
#Mann= 5 ,-1 , 0
  4441.9     .12       0  4754.7      .1       0  4975.3     .07       0
  5033.2      .1       0  5250.9     .12       0
Bank Sta=4975.3,5033.2
XS Rating Curve= 0 ,0
Exp/Cntr=0.3,0.1

Type RM Length L Ch R = 1 ,6500    ,500,500,500
BEGIN DESCRIPTION:
WEST FORK OF CRYSTAL CREEK 13.0
END DESCRIPTION:
XS GIS Cut Line= 3
       3865106.9     10103788.05      3864598.11     10103556.97
      3863808.58     10103381.95
#Sta/Elev= 30
  4441.2  162.32  4641.4  158.89  4648.8   157.7  4748.5  154.53  4831.5  151.03
  4893.8  150.55  4933.8  147.21  4945.4  147.43  4957.8  144.81  4967.3  145.54
  4975.4  144.15  4980.9  142.43  4988.5  137.05  5006.3  137.05  5020.8  145.31
  5028.1 147.514  5041.2   150.5  5092.5  148.95  5123.2  145.58  5140.7  146.55
  5145.8  145.32  5174.4  148.24  5215.4  148.81    5233  146.99  5266.6  147.79
  5325.3  151.29  5430.5  154.87  5584.1  157.56    5666  157.65  5808.7  161.13
#Mann= 7 ,-1 , 0
  4441.2     .12       0  4748.5      .1       0  4893.8     .12       0
  4933.8      .1       0  4945.4     .07       0  5028.1      .1       0
  5092.5     .12       0
Bank Sta=4945.4,5028.1
XS Rating Curve= 0 ,0
Exp/Cntr=0.3,0.1

Type RM Length L Ch R = 1 ,6000    ,500,500,500
BEGIN DESCRIPTION:
WEST FORK OF CRYSTAL CREEK 12.0
END DESCRIPTION:
XS GIS Cut Line= 3
      3865333.59     10103229.42      3864671.87     10103094.65
      3863922.93      10103120.9
#Sta/Elev= 30
  4324.7  172.95  4371.4  169.99  4421.4  168.67  4473.4  167.51  4495.4  165.73
  4545.9  158.45  4718.4  148.61  4779.6  149.92  4820.4  147.63  4850.3  148.69
  4871.4  148.64  4881.6  147.41  4894.8  143.44  4945.4  145.98  4973.5  140.95
  4981.9  136.12  4999.8  136.12  5004.5  140.17    5014  143.79    5024  145.39
    5034  144.91  5039.7  146.65  5044.7  143.65  5064.1  149.59  5119.4  146.19
  5214.2  150.17  5374.3  151.88  5444.3  156.92  5634.4  162.28  5749.4  163.23
#Mann= 6 ,-1 , 0
  4324.7     .05       0  4421.4     .12       0  4850.3      .1       0
  4945.4     .07       0    5024      .1       0  5119.4     .05       0
Bank Sta=4945.4,5024
XS Rating Curve= 0 ,0
Exp/Cntr=0.3,0.1

Type RM Length L Ch R = 1 ,5500    ,500,500,500
BEGIN DESCRIPTION:
WEST FORK OF CRYSTAL CREEK 11.0
END DESCRIPTION:
XS GIS Cut Line= 3
      3865255.39     10102604.41       3864676.2     10102667.39
      3863836.14     10102995.04
#Sta/Elev= 30
  4417.4  161.44  4565.8  155.59    4767  150.26  4909.1  144.18  4978.2  144.42
  4990.5  141.26  4996.7  136.46    5000  135.56  5017.9  135.56  5019.1  138.55
  5024.5  140.32  5030.4  145.08    5049  147.91  5062.6  147.71  5073.4  146.37
  5094.8  139.99  5108.7  140.75  5133.2  146.83    5163  146.28  5199.3  148.59
  5231.5  149.46  5350.6   147.1    5405  147.48  5470.5  151.24  5489.2  150.77
  5557.4  153.85  5610.1  157.66    5712  158.79  5728.1  160.44  5901.7  164.99
#Mann= 7 ,-1 , 0
  4417.4     .12       0  4909.1      .1       0  4978.2     .07       0
  5030.4      .1       0  5199.3     .05       0  5231.5    .075       0
  5557.4     .05       0
Bank Sta=4978.2,5030.4
XS Rating Curve= 0 ,0
Exp/Cntr=0.3,0.1

Type RM Length L Ch R = 1 ,5000    ,500,500,500
BEGIN DESCRIPTION:
WEST FORK OF CRYSTAL CREEK 10.0
END DESCRIPTION:
XS GIS Cut Line= 3
      3865294.51     10102543.65      3864356.06      10102347.7
      3863562.78     10102309.28
#Sta/Elev= 30
  4041.3  162.43    4076  159.82  4081.1  161.06    4176   156.4  4346.4  152.64
  4425.5  151.36  4660.7  148.82    4772  149.46  4916.4  148.03  4955.6  144.69
  4960.7  145.27  4977.7  143.59  4996.5  137.92  4999.2  136.04  5017.2  136.04
  5033.4  143.59  5048.3  145.22  5098.3   146.7  5148.4  141.45  5169.5  145.02
  5218.5  144.96  5241.9   147.5  5248.5  150.03  5268.5  152.89  5358.6  156.51
  5458.7  158.81  5518.8  158.13  5648.8  161.82  5749.1   161.3  5794.2  162.75
#Mann= 7 ,-1 , 0
  4041.3     .12       0  4346.4     .05       0  4425.5     .12       0
    4772      .1       0  4960.7     .07       0  5048.3      .1       0
  5169.5     .12       0
Bank Sta=4960.7,5048.3
XS Rating Curve= 0 ,0
Exp/Cntr=0.3,0.1

Type RM Length L Ch R = 1 ,4500    ,510,510,510
BEGIN DESCRIPTION:
WEST FORK OF CRYSTAL CREEK 9.0
END DESCRIPTION:
XS GIS Cut Line= 3
      3865342.24     10102508.94      3864575.08      10101968.5
      3863740.68     10101324.05
#Sta/Elev= 30
  4061.6  162.84  4178.8  159.34  4440.5  151.25  4572.4  147.49  4661.2  148.22
  4694.3  147.32  4723.9  149.29  4816.2  150.12  4904.4  146.06  4938.2  144.88
    4953  142.11  4973.9  142.81  4979.6  134.83  5009.7  136.12  5017.9  138.65
  5024.2  142.42  5032.4  144.39  5088.5  141.46  5096.7  142.35    5103  144.95
  5136.9  146.87  5302.3  146.96  5331.3  145.58  5401.9  145.92  5445.4  147.71
  5652.8  147.91  5893.7  155.15  5916.3  157.42  5937.2  157.18  6054.3  162.88
#Mann= 8 ,-1 , 0
  4061.6     .12       0  4178.8     .05       0  4440.5      .1       0
  4661.2     .12       0  4904.4      .1       0  4938.2     .07       0
  5032.4      .1       0  5136.9     .12       0
Bank Sta=4938.2,5032.4
XS Rating Curve= 0 ,0
Exp/Cntr=0.3,0.1

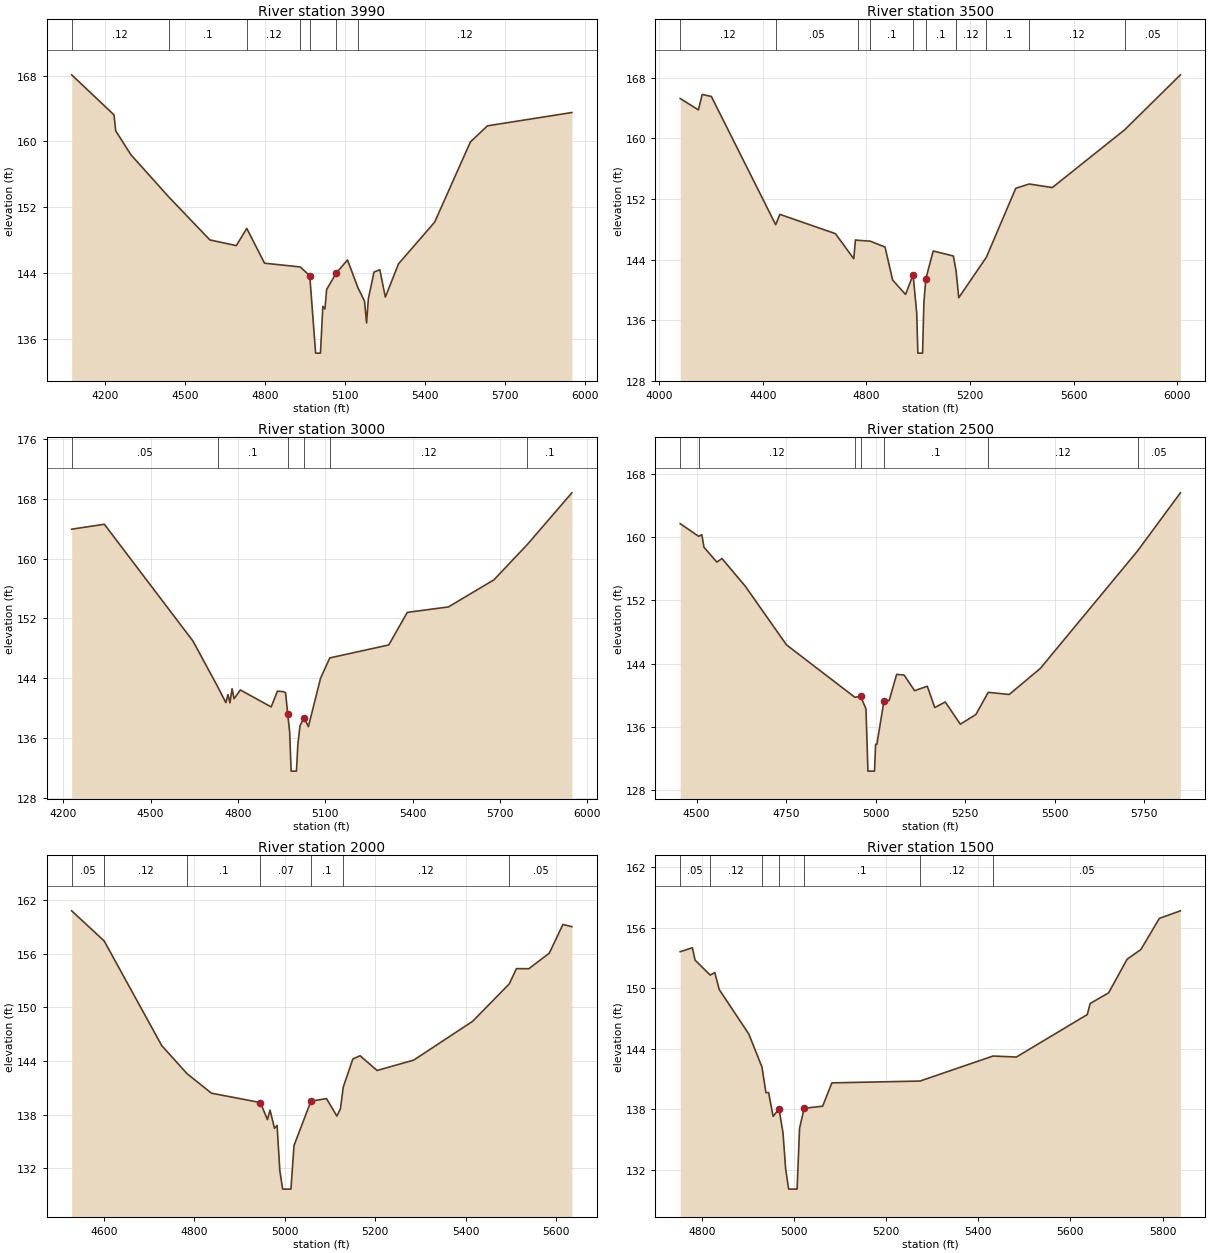
Type RM Length L Ch R = 1 ,3990    ,490,490,490
BEGIN DESCRIPTION:
WEST FORK OF CRYSTAL CREEK 8.0
END DESCRIPTION:
XS GIS Cut Line= 3
      3865575.92      10102357.2      3864939.02     10101682.74
      3864201.76     10101081.81
#Sta/Elev= 30
  4073.7   168.1  4232.5  163.23  4239.3  161.27    4296  158.38  4438.3  153.24
  4592.9     148    4692  147.31  4731.5   149.4    4798  145.17  4932.3  144.71
    4968  143.64    4990  134.22  5008.2  134.22  5017.1  139.91    5025  139.59
  5031.4  141.97  5067.4  143.96  5109.7  145.56  5149.3  142.16  5173.6  140.56
  5181.5   137.9    5188  140.82  5209.3  144.09  5231.1  144.38  5251.9  141.04
  5301.4  145.09  5437.2  150.17  5571.4  159.93  5635.3  161.89  5952.5  163.51
#Mann= 7 ,-1 , 0
  4073.7     .12       0  4438.3      .1       0  4731.5     .12       0
  4932.3      .1       0    4968     .07       0  5067.4      .1       0
  5149.3     .12       0
Bank Sta=4968,5067.4
XS Rating Curve= 0 ,0
Exp/Cntr=0.3,0.1

Type RM Length L Ch R = 1 ,3500    ,500,500,500
BEGIN DESCRIPTION:
WEST FORK OF CRYSTAL CREEK 7.0
END DESCRIPTION:
XS GIS Cut Line= 3
      3866049.72     10101957.73      3865313.64     10101406.68
      3864552.55     10100738.32
#Sta/Elev= 30
  4080.5  165.28  4150.8  163.78  4165.4  165.82  4200.8  165.55  4449.4  148.61
  4465.4  149.98  4680.1  147.43  4750.9  144.12  4757.4   146.6    4768  146.55
  4814.7  146.44  4871.8  145.66    4901  141.31    4951   139.4  4980.2     142
  4994.2  136.94  4998.6  131.65  5016.8  131.65  5021.9  138.35  5029.4  141.47
  5057.9  145.14  5135.7  144.48  5146.2  142.53  5156.6  138.97  5263.2  144.31
  5376.7  153.42  5428.6  153.99  5518.1  153.52  5797.2  161.14  6012.9  168.41
#Mann= 10 ,-1 , 0
  4080.5     .12       0  4449.4     .05       0    4768     .12       0
  4814.7      .1       0  4980.2     .07       0  5029.4      .1       0
  5146.2     .12       0  5263.2      .1       0  5428.6     .12       0
  5797.2     .05       0
Bank Sta=4980.2,5029.4
XS Rating Curve= 0 ,0
Exp/Cntr=0.3,0.1

Type RM Length L Ch R = 1 ,3000    ,500,500,500
BEGIN DESCRIPTION:
WEST FORK OF CRYSTAL CREEK 6.0
END DESCRIPTION:
XS GIS Cut Line= 3
        3866245.     10101662.57      3865681.04     10101136.84
      3864968.95     10100512.39
#Sta/Elev= 30
    4229  163.96  4341.2  164.62  4645.6  148.98  4730.4  142.88  4758.5  140.74
  4765.8  141.81  4772.6  140.71    4780   142.6  4786.8  141.25  4808.3  142.43
  4914.3  140.16  4935.8  142.27  4956.8   142.2  4963.7  142.06    4971  139.26
  4977.8  136.78  4982.8  131.56  5001.1  131.56    5006  135.18  5013.6  137.68
  5027.8  138.69  5042.1  137.52    5084  144.01  5115.6  146.72  5318.2  148.46
  5381.8  152.82  5523.2  153.55  5679.8  157.19  5794.3  161.92  5947.1  168.83
#Mann= 6 ,-1 , 0
    4229     .05       0  4730.4      .1       0    4971     .07       0
  5027.8      .1       0  5115.6     .12       0  5794.3      .1       0
Bank Sta=4971,5027.8
XS Rating Curve= 0 ,0
Exp/Cntr=0.3,0.1

Type RM Length L Ch R = 1 ,2500    ,500,500,500
BEGIN DESCRIPTION:
WEST FORK OF CRYSTAL CREEK 5.0
END DESCRIPTION:
XS GIS Cut Line= 3
       3866470.7     10101172.12      3866028.48     10100852.05
      3865342.54      10100347.7
#Sta/Elev= 30
  4454.1  161.68  4505.6  160.08  4514.4  160.29  4520.5   158.7  4556.4  156.83
  4570.8  157.27  4635.8  153.78    4751  146.36  4941.8  139.74  4958.3  139.84
    4973  138.27  4978.5   130.4  4996.8   130.4    5000   133.8  5003.5   133.8
  5023.2  139.25  5037.8  139.33  5058.7  142.63  5079.5  142.55  5108.8  140.57
  5144.3  141.13  5165.2  138.44  5194.5  139.14  5236.6  136.33  5280.1  137.56
  5314.5  140.36  5373.1  140.09  5459.8  143.37  5731.8  158.24  5851.4  165.58
#Mann= 7 ,-1 , 0
  4454.1     .05       0  4505.6     .12       0  4941.8      .1       0
  4958.3     .07       0  5023.2      .1       0  5314.5     .12       0
  5731.8     .05       0
Bank Sta=4958.3,5023.2
XS Rating Curve= 0 ,0
Exp/Cntr=0.3,0.1

Type RM Length L Ch R = 1 ,2000    ,500,500,500
BEGIN DESCRIPTION:
WEST FORK OF CRYSTAL CREEK 4.0
END DESCRIPTION:
XS GIS Cut Line= 3
      3866583.55     10100638.27      3866178.23     10100397.18
      3865624.34     10100087.05
#Sta/Elev= 30
  4528.4   160.8  4600.3  157.43  4727.7  145.71  4783.7  142.57  4837.5  140.39
  4945.8  139.34  4961.4  137.43  4967.2   138.5    4977  136.46  4982.8  136.78
  4988.8  131.73  4995.1  129.65  5013.4  129.65  5020.2  134.53  5057.7   139.5
  5092.1  139.78    5115  137.83  5122.9  138.64  5129.1  141.07  5150.4  144.22
  5166.3  144.58    5204  142.93    5285  144.09  5415.2  148.43  5496.5  152.63
  5512.2  154.33  5539.6  154.32  5584.9  156.06    5615  159.27  5634.8  159.03
#Mann= 7 ,-1 , 0
  4528.4     .05       0  4600.3     .12       0  4783.7      .1       0
  4945.8     .07       0  5057.7      .1       0  5129.1     .12       0
  5496.5     .05       0
Bank Sta=4945.8,5057.7
XS Rating Curve= 0 ,0
Exp/Cntr=0.3,0.1

Type RM Length L Ch R = 1 ,1500    ,564,564,564
BEGIN DESCRIPTION:
WEST FORK OF CRYSTAL CREEK 3.0
END DESCRIPTION:
XS GIS Cut Line= 3
      3866692.08     10100221.62      3866480.14     10100095.36
      3865642.23     10100056.69
#Sta/Elev= 30
  4753.3  153.62  4779.7  154.01  4785.5  152.79  4818.4   151.3  4828.3  151.55
  4838.1  149.86  4902.3  145.45  4930.7  142.19  4939.3  139.65  4945.1  139.66
  4954.9   137.3  4967.7  138.03  4976.3  135.69  4982.1  132.09  4988.6  130.09
  5006.9  130.09  5012.3  136.12  5022.3   138.1  5062.4  138.31  5082.4  140.62
  5273.7   140.8  5432.1  143.28  5482.8  143.18  5636.7  147.39    5643  148.49
    5683  149.54  5723.1  152.87  5753.1  153.84  5793.1  156.92  5838.8  157.67
#Mann= 7 ,-1 , 0
  4753.3     .05       0  4818.4     .12       0  4930.7      .1       0
  4967.7     .07       0  5022.3      .1       0  5273.7     .12       0
  5432.1     .05       0
Bank Sta=4967.7,5022.3
XS Rating Curve= 0 ,0
Exp/Cntr=0.3,0.1

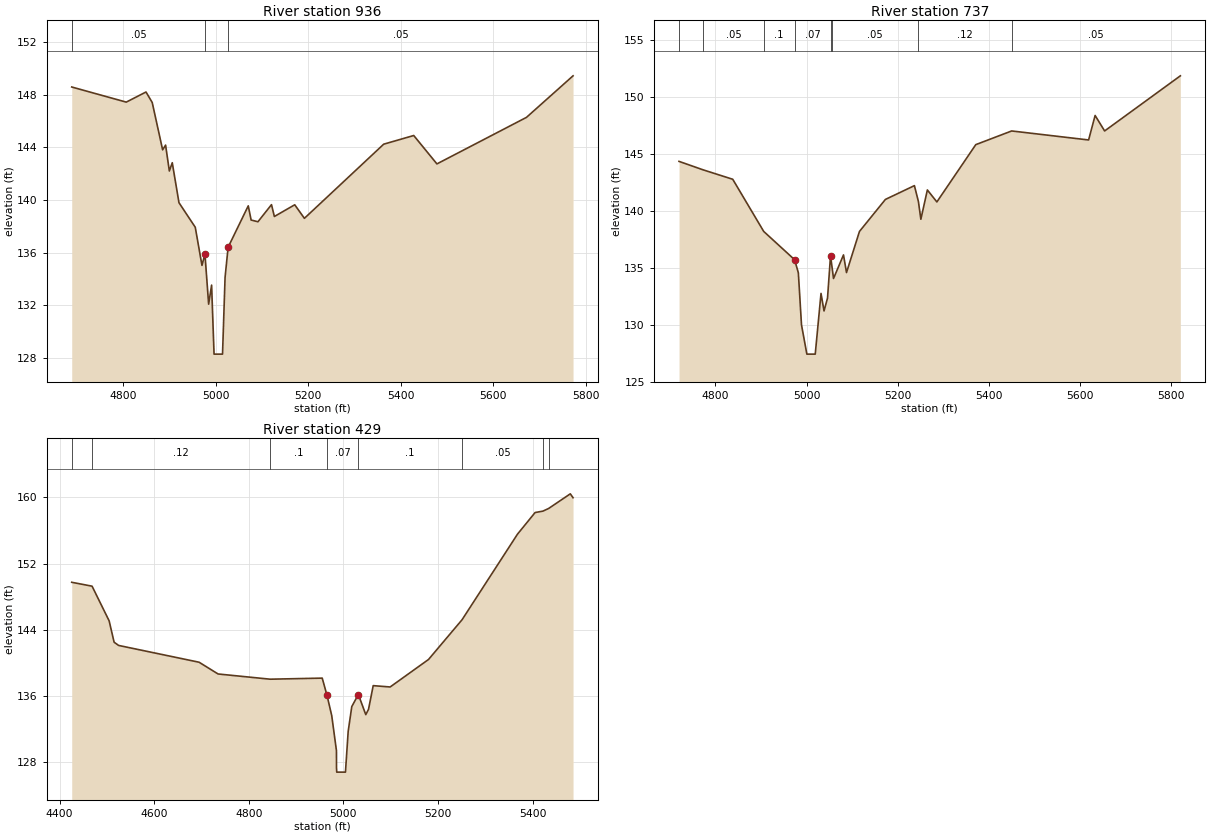
Type RM Length L Ch R = 1 ,936     ,199,199,199
BEGIN DESCRIPTION:
WEST FORK OF CRYSTAL CREEK 2.0
END DESCRIPTION:
XS GIS Cut Line= 3
      3866674.09      10099382.2      3866429.45     10099574.38
      3865806.67      10100030.6
#Sta/Elev= 30
  4688.9   148.6  4806.7  147.45  4849.4  148.22  4862.8  147.42  4885.3  143.82
  4891.7  144.18  4899.8  142.21  4906.1  142.84  4920.6   139.8  4955.8  137.93
  4970.3  135.03  4976.7   135.9  4984.7  132.08  4991.1  133.53  4996.4  128.28
  5014.7  128.28  5020.2  134.12  5026.8  136.41  5070.3  139.56  5076.5  138.48
  5091.2  138.35  5120.5  139.65  5126.7  138.75  5170.7  139.64  5191.6  138.61
  5362.9  144.25  5427.8  144.91  5477.9  142.75  5671.4  146.29    5772  149.45
#Mann= 3 , 0 , 0
  4688.9     .05       0  4976.7     .07       0  5026.8     .05       0
Bank Sta=4976.7,5026.8
XS Rating Curve= 0 ,0
Exp/Cntr=0.3,0.1

Type RM Length L Ch R = 1 ,737     ,308,308,308
BEGIN DESCRIPTION:
Mapping XS 79246175
END DESCRIPTION:
XS GIS Cut Line= 3
      3866587.92     10099249.35       3866352.8     10099401.57
       3865730.9     10099938.32
#Sta/Elev= 30
  4719.9  144.36  4772.6  143.62  4837.9  142.79    4906  138.21  4973.8  135.73
  4982.1  134.58    4989  130.01  5000.8  127.44  5019.2  127.44  5031.9  132.77
  5038.5  131.23  5046.2  132.36  5052.8  136.08  5055.4  135.29  5059.4  134.08
  5081.3  136.15  5087.9   134.6  5116.4  138.21  5173.4  141.02  5237.1  142.23
  5245.9  140.84  5251.3  139.28  5265.6  141.85  5286.5   140.8    5372  145.83
  5450.8  147.03  5619.9  146.24  5634.2  148.39  5655.1  147.03  5821.5  151.87
#Mann= 8 ,-1 , 0
  4719.9     .12       0  4772.6     .05       0    4906      .1       0
  4973.8     .07       0  5052.8      .1       0  5055.4     .05       0
  5245.9     .12       0  5450.8     .05       0
Bank Sta=4973.8,5052.8
XS Rating Curve= 0 ,0
Exp/Cntr=0.3,0.1

Type RM Length L Ch R = 1 ,429     ,0,0,0
BEGIN DESCRIPTION:
WEST FORK OF CRYSTAL CREEK 1.0
END DESCRIPTION:
XS GIS Cut Line= 3
      3866816.85     10099160.28      3866243.26     10099131.84
      3865823.91      10099376.7
#Sta/Elev= 30
  4425.7  149.73  4468.7  149.26  4504.8  145.07  4515.3  142.49  4524.8   142.1
    4695  140.07  4735.1  138.65  4845.2  138.02  4955.3  138.15  4965.4  136.07
  4975.4  133.62  4985.4  129.38  4985.5  127.29    4986  126.79  5004.4  126.79
  5010.2  131.72  5017.8  134.71  5031.7  136.17  5047.4  133.74  5053.2  134.38
  5063.1  137.24  5098.9  137.08    5180   140.4  5250.9   145.2  5368.2  155.55
  5405.4  158.16  5421.9  158.33    5434  158.65  5479.8  160.42  5485.6  159.95
#Mann= 8 ,-1 , 0
  4425.7     .05       0  4468.7     .12       0  4845.2      .1       0
  4965.4     .07       0  5031.7      .1       0  5250.9     .05       0
  5421.9     .12       0    5434     .05       0
Bank Sta=4965.4,5031.7
XS Rating Curve= 0 ,0
Exp/Cntr=0.3,0.1