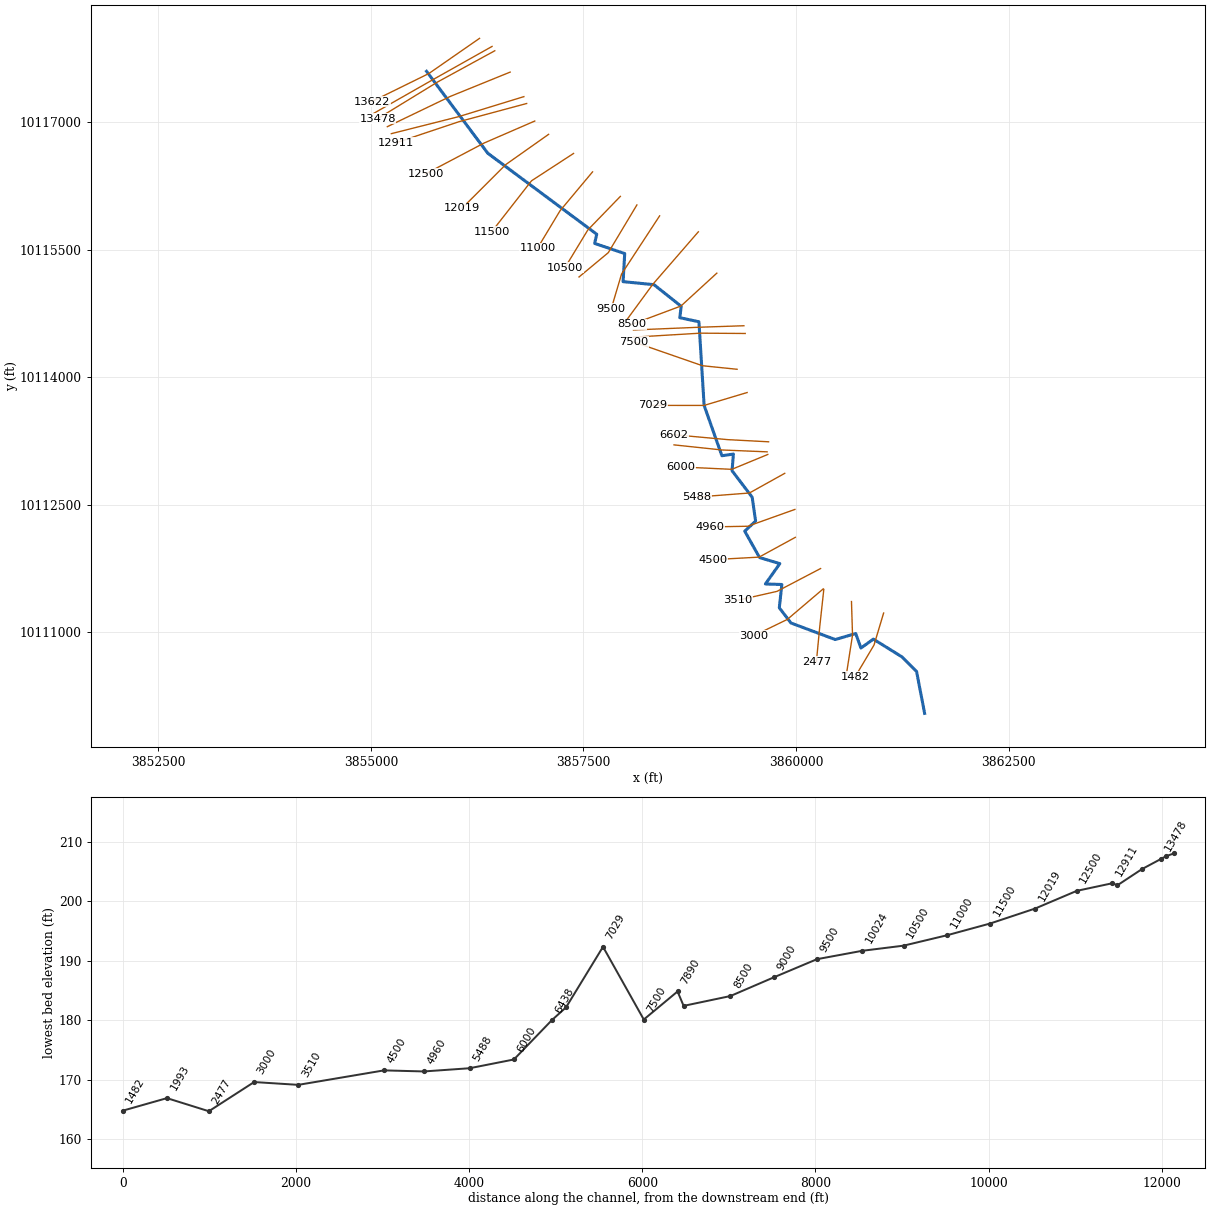
--- WF OF CRYSTAL CREEK TRIB NO 1.prj (project) ---

Proj Title=WF OF CRYSTAL CREEK TRIB NO 1 Base Level Engineering
Current Plan=p01
Default Exp/Contr=0.3,0.1
English Units
Geom File=g01
Flow File=f01
Plan File=p01
Y Axis Title=Elevation
X Axis Title(PF)=Main Channel Distance
X Axis Title(XS)=Station
BEGIN DESCRIPTION:
WF OF CRYSTAL CREEK TRIB NO 1
END DESCRIPTION:
DSS Export Rating Curves= 0
DSS Export Rating Curve Sorted= 0
DSS Export Volume Flow Curves= 0
DXF OffsetX= 0
DXF OffsetY= 0
DXF ScaleX= 1
DXF ScaleY= 10

--- WF OF CRYSTAL CREEK TRIB NO 1.p01 (plan) ---

Plan Title=Multiple Run
Short Identifier=Multiple
Geom File=g01
Flow File=f01
Subcritical Flow
K Sum by GR= 0
Std Step Tol= 0.01
Critical Tol= 0.01
Num of Std Step Trials= 20
Max Error Tol= 0.3
Flow Tol Ratio= 0.001
Split Flow NTrial= 30
Split Flow Tol= 0.02
Split Flow Ratio= 0.02
Log Output Level= 0
Friction Slope Method= 1
Unsteady Friction Slope Method= 2
Unsteady Bridges Friction Slope Method= 1
Parabolic Critical Depth
Global Vel Dist=  1 , 1 , 1
Global Log Level= 0
CheckData=True
Encroach Param= -1, 0, 0, 0
BEGIN DESCRIPTION:
Multiple Run
END DESCRIPTION:

--- WF OF CRYSTAL CREEK TRIB NO 1.f01 (steady flow) ---

Flow Title=Multiple
Program Version=4.10
Number of Profiles= 7
Profile Names=10-year,25-year,50-year,1pct_min,100-year,1pct_plu,500-year
River Rch & RM=WF OF CRYSTAL CR,Reach-1         ,13622
     421     537     693     295     891    2691    1515
River Rch & RM=WF OF CRYSTAL CR,Reach-1         ,5488
     508     653     852     365    1101    3325    1901
Boundary for River Rch & Prof#=WF OF CRYSTAL CR,Reach-1         , 1
Up Type= 0
Dn Type= 3
Dn Slope=0.005
Boundary for River Rch & Prof#=WF OF CRYSTAL CR,Reach-1         , 2
Up Type= 0
Dn Type= 3
Dn Slope=0.005
Boundary for River Rch & Prof#=WF OF CRYSTAL CR,Reach-1         , 3
Up Type= 0
Dn Type= 3
Dn Slope=0.005
Boundary for River Rch & Prof#=WF OF CRYSTAL CR,Reach-1         , 4
Up Type= 0
Dn Type= 3
Dn Slope=0.005
Boundary for River Rch & Prof#=WF OF CRYSTAL CR,Reach-1         , 5
Up Type= 0
Dn Type= 3
Dn Slope=0.005
Boundary for River Rch & Prof#=WF OF CRYSTAL CR,Reach-1         , 6
Up Type= 0
Dn Type= 3
Dn Slope=0.005
Boundary for River Rch & Prof#=WF OF CRYSTAL CR,Reach-1         , 7
Up Type= 0
Dn Type= 3
Dn Slope=0.005
DSS Import GetInterval= 0
DSS Import GetPeak= 0
DSS Import FillOption= 0

--- WF OF CRYSTAL CREEK TRIB NO 1.g01 (geometry) ---

Geom Title=Existing Conditions
Program Version=4.10

River Reach=WF OF CRYSTAL CR,Reach-1
Reach XY= 30
      3855653.58     10117599.35      3856373.76      10116635.5
      3857655.95     10115682.35      3857630.73     10115574.53
       3857984.9     10115455.24      3857965.59      10115124.6
      3858328.64     10115089.36      3858649.54     10114834.51
      3858632.61     10114700.92      3858857.86     10114652.76
      3858918.97     10113668.73      3859128.09     10113076.73
       3859263.6     10113096.44      3859247.38     10112900.79
      3859484.48     10112588.57      3859524.68     10112307.99
      3859396.83     10112189.75      3859571.06     10111879.07
      3859809.39     10111807.76      3859639.86     10111568.25
      3859833.09     10111562.52       3859803.4     10111288.04
       3859941.1     10111109.03       3860461.7     10110914.73
      3860701.91     10110985.38      3860763.81     10110815.12
       3860909.9      10110919.4      3861247.04     10110710.35
      3861417.99     10110538.86        3861513.      10110046.2

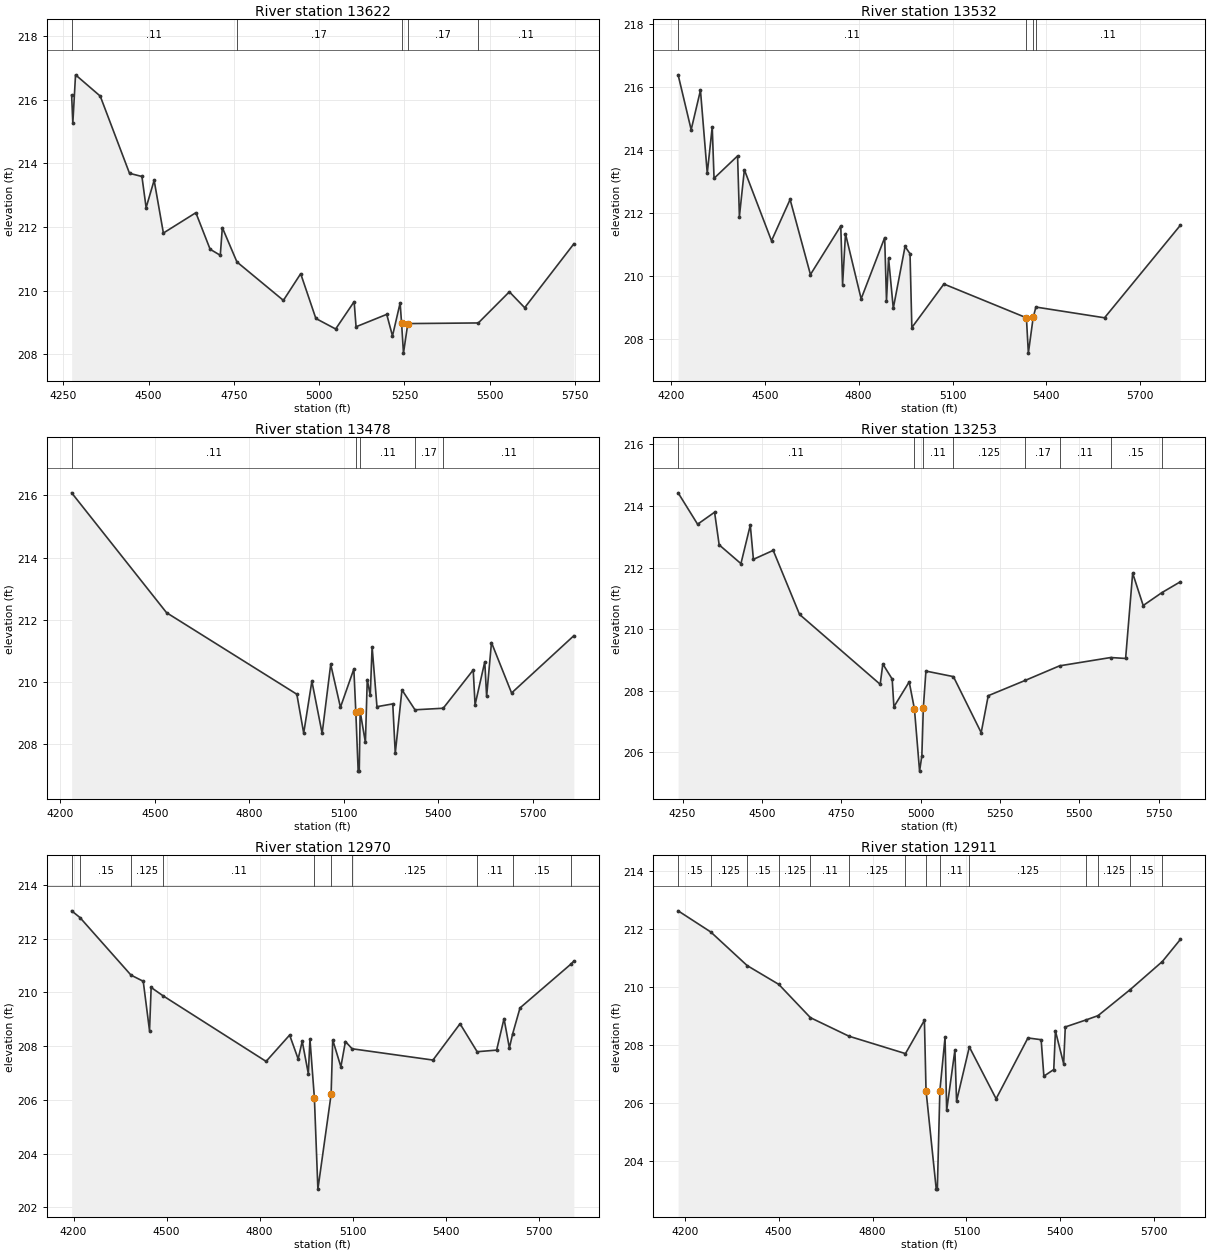
Type RM Length L Ch R = 1 ,13622   ,90,90,90
BEGIN DESCRIPTION:
WF OF CRYSTAL CREEK TRIB NO 1 26.0
END DESCRIPTION:
XS GIS Cut Line= 3
       3856277.2     10117986.96      3855681.25     10117573.21
       3855011.4     10117243.49
#Sta/Elev= 30
  4274.5  216.15  4277.9  215.26  4285.9  216.79  4358.3  216.12  4444.1  213.69
  4480.5  213.59  4492.8  212.61  4516.3  213.47  4543.4  211.81  4638.6  212.45
  4680.4   211.3  4710.2  211.11  4716.2  211.98    4759   210.9  4895.2  209.69
  4945.9  210.53  4990.4  209.12  5048.4  208.79  5102.6  209.65  5108.2  208.86
  5198.1  209.25    5215  208.57  5237.4  209.61 5241.71208.9635  5247.2  208.03
  5259.9  208.96  5466.6  208.98  5557.6  209.96  5602.5  209.46  5746.6  211.47
#Mann= 5 ,-1 , 0
  4274.5     .11       0    4759     .17       0 5241.71     .09       0
  5259.9     .17       0  5466.6     .11       0
Bank Sta=5241.71,5259.9
XS Rating Curve= 0 ,0
Exp/Cntr=0.3,0.1

Type RM Length L Ch R = 1 ,13532   ,54,54,54
BEGIN DESCRIPTION:
Mapping XS 5284a2b1
END DESCRIPTION:
XS GIS Cut Line= 3
      3856424.17     10117891.57      3855746.84     10117511.27
      3855027.42     10117101.77
#Sta/Elev= 30
  4223.2  216.38  4264.9  214.64  4294.6  215.89  4316.3  213.26  4332.2  214.73
    4338   213.1  4413.2  213.81    4419  211.89  4434.9  213.37  4521.6  211.12
    4581  212.43    4646  210.05  4742.9  211.59  4748.7  209.73    4758  211.34
    4808  209.28  4883.2  211.22    4889  209.22  4895.6  210.57  4910.7  208.98
  4948.3  210.94  4964.2  210.71    4970  208.37  5072.4  209.75  5336.1  208.68
  5342.3  207.56  5357.7  208.69  5366.4  209.02  5585.7  208.68  5827.8  211.61
#Mann= 4 ,-1 , 0
  4223.2     .11       0  5336.1     .09       0  5357.7     .17       0
  5366.4     .11       0
Bank Sta=5336.1,5357.7
XS Rating Curve= 0 ,0
Exp/Cntr=0.3,0.1

Type RM Length L Ch R = 1 ,13478   ,225,225,225
BEGIN DESCRIPTION:
Mapping XS 2794839d
END DESCRIPTION:
XS GIS Cut Line= 3
      3856456.74      10117840.8      3855785.65     10117474.61
      3855077.32     10117041.01
#Sta/Elev= 30
  4235.5  216.08  4536.9  212.23  4950.7  209.61  4972.5  208.36  4998.5  210.03
  5031.1  208.35  5058.3  210.57  5089.2  209.19  5131.8  210.42  5138.1  209.03
  5145.5  207.14    5149  207.14 5151.83209.0561  5168.5  208.06  5174.4  210.08
  5183.9  209.57  5189.8  211.13  5205.2  209.21  5255.4   209.3  5263.3  207.71
  5284.6  209.75    5326  209.11  5415.6  209.16  5510.9  210.39  5516.8  209.27
  5547.6  210.65  5553.5  209.54  5568.9  211.27  5632.8  209.65  5830.5  211.49
#Mann= 5 ,-1 , 0
  4235.5     .11       0  5138.1     .09       0 5151.83     .11       0
    5326     .17       0  5415.6     .11       0
Bank Sta=5138.1,5151.83
XS Rating Curve= 0 ,0
Exp/Cntr=0.3,0.1

Type RM Length L Ch R = 1 ,13253   ,283,283,283
BEGIN DESCRIPTION:
Mapping XS 660a28fa
END DESCRIPTION:
XS GIS Cut Line= 3
       3856637.6     10117590.03      3855929.74     10117302.31
      3855192.55     10116947.79
#Sta/Elev= 30
  4235.9  214.43  4297.3  213.41  4350.8   213.8  4365.2  212.74  4433.8  212.13
  4463.3  213.38  4473.1  212.27  4535.5  212.56  4618.5  210.48  4872.5  208.21
  4880.8  208.87  4910.3  208.38  4915.7  207.48  4963.9  208.29  4980.4  207.41
  4996.6  205.39  5003.8  205.89 5008.44207.4496  5016.6  208.64  5103.2  208.46
  5190.7  206.64  5212.9  207.84  5330.1  208.34  5437.6  208.81  5598.6  209.08
  5645.7  209.05  5667.9  211.82  5701.1  210.77  5760.2  211.19    5818  211.54
#Mann= 8 ,-1 , 0
  4235.9     .11       0  4980.4     .09       0 5008.44     .11       0
  5103.2    .125       0  5330.1     .17       0  5437.6     .11       0
  5598.6     .15       0  5760.2     .11       0
Bank Sta=4980.4,5008.44
XS Rating Curve= 0 ,0
Exp/Cntr=0.3,0.1

Type RM Length L Ch R = 1 ,12970   ,59,59,59
BEGIN DESCRIPTION:
WF OF CRYSTAL CREEK TRIB NO 1 25.0
END DESCRIPTION:
XS GIS Cut Line= 3
      3856798.52     10117301.07      3856027.97     10117064.67
       3855239.6     10116865.64
#Sta/Elev= 30
    4194  213.03  4220.8  212.78  4385.3  210.64  4424.8  210.41  4445.1  208.57
  4450.3  210.18  4487.4  209.88  4820.9  207.43  4896.8  208.41  4924.3  207.52
  4937.4  208.18  4957.1  206.97  4962.3  208.26  4976.6206.0755  4987.9  202.68
  5030.5   206.2  5035.7  208.23    5062  207.23  5076.7  208.17  5098.2   207.9
  5358.9  207.48  5446.2  208.83  5501.4  207.79  5564.2  207.85    5588  209.02
  5605.3  207.93  5615.7  208.45  5639.6  209.42  5803.8  211.05  5813.1  211.16
#Mann= 10 ,-1 , 0
    4194    .125       0  4220.8     .15       0  4385.3    .125       0
  4487.4     .11       0  4976.6     .09       0  5030.5     .11       0
  5098.2    .125       0  5501.4     .11       0  5615.7     .15       0
  5803.8     .11       0
Bank Sta=4976.6,5030.5
XS Rating Curve= 0 ,0
Exp/Cntr=0.3,0.1

Type RM Length L Ch R = 1 ,12911   ,411,411,411
BEGIN DESCRIPTION:
Mapping XS 51618a81
END DESCRIPTION:
XS GIS Cut Line= 3
      3856831.53     10117220.35      3856038.73     10117007.38
      3855296.43     10116758.86
#Sta/Elev= 30
  4179.1  212.63  4283.3   211.9  4399.5  210.74  4500.6  210.09  4601.7  208.94
  4724.9   208.3  4905.1   207.7  4965.6  208.85  4970.8  206.42  5003.4  203.02
  5006.9  203.02 5014.99206.4185  5031.5  208.26  5036.7  205.74    5063  207.82
  5068.3  206.06  5109.1  207.93  5194.6  206.14  5296.2  208.24  5338.4  208.18
  5347.1  206.92  5378.7  207.15    5384  208.48  5410.3  207.35  5415.5  208.62
  5481.1  208.86    5520  209.01  5622.8  209.91  5725.5  210.88  5782.8  211.64
#Mann= 14 ,-1 , 0
  4179.1     .15       0  4283.3    .125       0  4399.5     .15       0
  4500.6    .125       0  4601.7     .11       0  4724.9    .125       0
  4905.1     .11       0  4970.8     .09       0 5014.99     .11       0
  5109.1    .125       0  5481.1     .11       0    5520    .125       0
  5622.8     .15       0  5725.5    .125       0
Bank Sta=4970.8,5014.99
XS Rating Curve= 0 ,0
Exp/Cntr=0.3,0.1

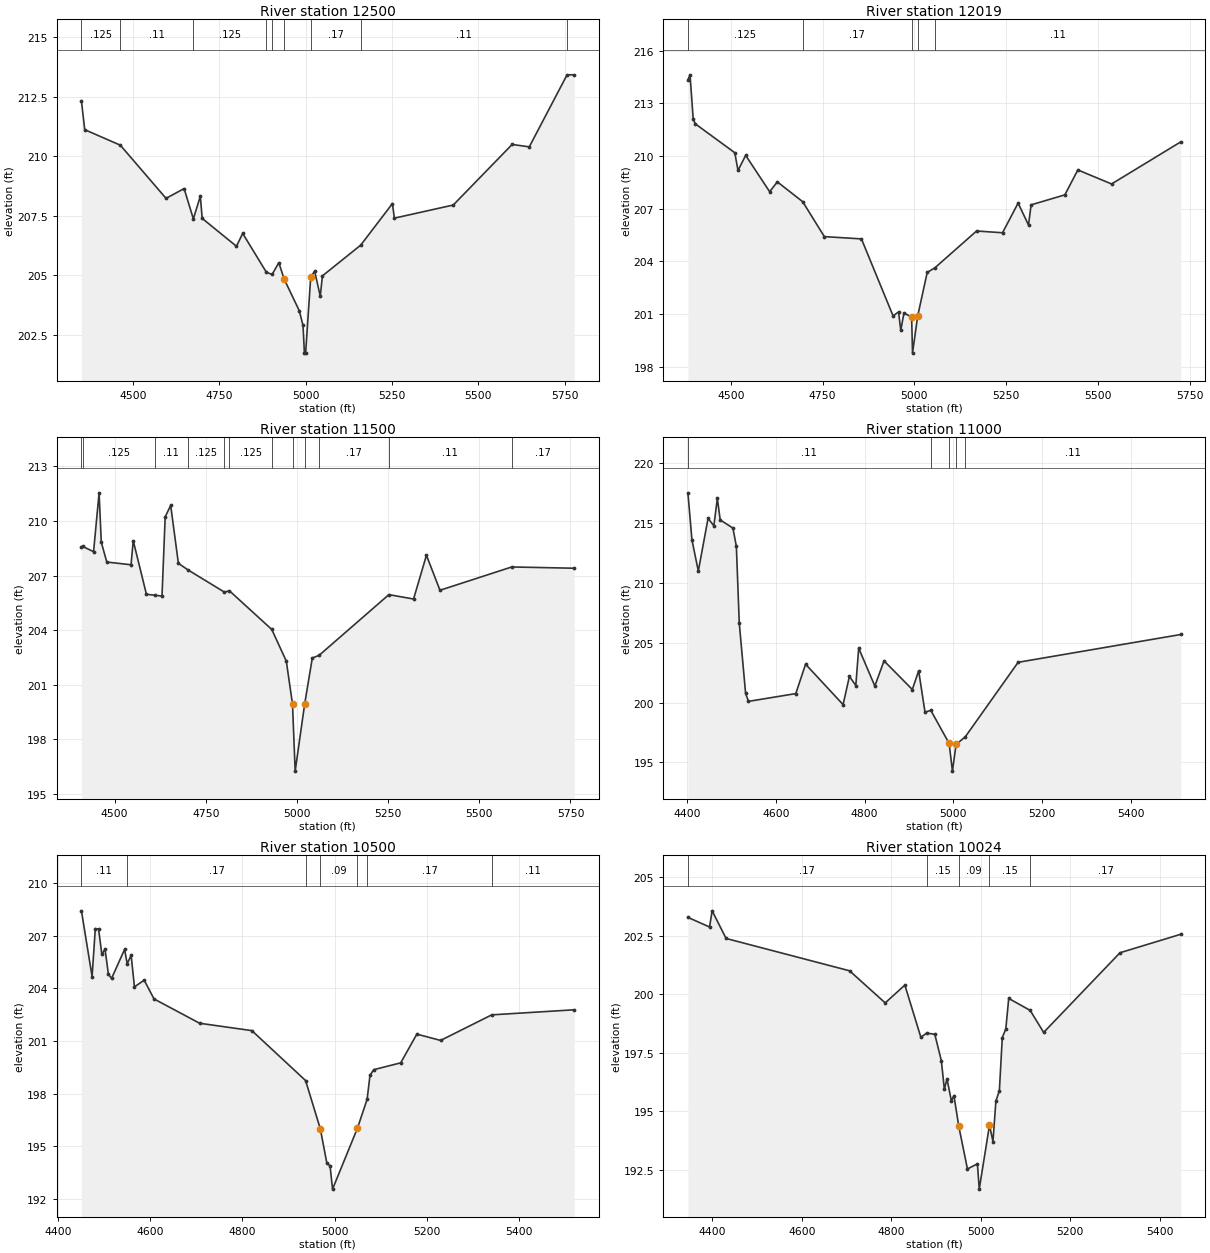
Type RM Length L Ch R = 1 ,12500   ,481,481,481
BEGIN DESCRIPTION:
WF OF CRYSTAL CREEK TRIB NO 1 24.0
END DESCRIPTION:
XS GIS Cut Line= 3
      3856926.67     10117014.07      3856330.69     10116755.39
      3855642.37     10116392.77
#Sta/Elev= 30
  4350.3  212.31  4359.9  211.11  4462.9  210.46  4595.4  208.23  4647.7  208.64
  4674.5  207.37  4694.7  208.32  4700.1  207.39  4799.4  206.22  4817.4  206.76
  4886.1  205.13  4902.6  205.04  4922.1  205.53  4937.7  204.84  4981.3  203.52
  4992.2   202.9  4996.2  201.74  4999.7  201.74  5014.4  204.92  5025.8  205.18
  5042.1  204.13  5048.4  204.98  5159.4  206.27  5251.1  208.01  5256.8   207.4
  5427.3  207.95  5597.9  210.49  5647.6  210.39    5757  213.41    5778  213.41
#Mann= 9 ,-1 , 0
  4350.3    .125       0  4462.9     .11       0  4674.5    .125       0
  4886.1     .11       0  4902.6     .17       0  4937.7     .09       0
  5014.4     .17       0  5159.4     .11       0    5757     .15       0
Bank Sta=4937.7,5014.4
XS Rating Curve= 0 ,0
Exp/Cntr=0.3,0.1

Type RM Length L Ch R = 1 ,12019   ,519,519,519
BEGIN DESCRIPTION:
WF OF CRYSTAL CREEK TRIB NO 1 23.0
END DESCRIPTION:
XS GIS Cut Line= 3
       3857089.9     10116857.84      3856586.12     10116502.31
      3856072.65     10115989.91
#Sta/Elev= 30
  4383.4  214.34  4389.2  214.63  4397.9  212.09    4404  211.83  4511.1  210.19
  4519.8  209.18  4540.7  210.04    4606  207.97  4626.9  208.53    4696   207.4
  4754.9  205.41  4855.9  205.28  4942.1  200.89  4956.9  201.12    4963  200.07
  4971.7  201.06  4992.6  200.82    4995  198.77 5009.11 200.888    5035  203.37
  5055.8  203.63  5169.4  205.73  5240.1  205.63  5282.5  207.32  5310.8  206.07
  5317.9  207.22  5409.8  207.79  5445.1  209.21    5537  208.41  5725.4  210.81
#Mann= 5 ,-1 , 0
  4383.4    .125       0    4696     .17       0  4992.6     .09       0
 5009.11     .17       0  5055.8     .11       0
Bank Sta=4992.6,5009.11
XS Rating Curve= 0 ,0
Exp/Cntr=0.3,0.1

Type RM Length L Ch R = 1 ,11500   ,500,500,500
BEGIN DESCRIPTION:
WF OF CRYSTAL CREEK TRIB NO 1 22.0
END DESCRIPTION:
XS GIS Cut Line= 3
      3857383.02     10116632.77       3856887.9     10116310.62
      3856419.76     10115711.16
#Sta/Elev= 30
  4409.3  208.56  4412.4   208.6  4442.6  208.31  4457.7  211.54  4463.7  208.83
  4478.8  207.74  4545.3  207.59  4551.3  208.91  4587.5  205.97  4609.7  205.92
  4630.2  205.87  4638.9  210.22    4654  210.85  4675.1  207.67  4701.3  207.31
  4801.2  206.09  4815.1  206.16  4931.1  204.04    4971   202.3    4988199.9378
  4995.3  196.26  5021.5  199.97  5042.3  202.47  5061.1  202.62  5252.2  205.95
  5319.9  205.71  5355.2  208.11  5392.3  206.19  5589.1  207.47  5760.6   207.4
#Mann= 12 ,-1 , 0
  4409.3     .11       0  4412.4    .125       0  4609.7     .11       0
  4701.3    .125       0  4801.2     .11       0  4815.1    .125       0
  4931.1     .11       0    4988     .09       0  5021.5     .11       0
  5061.1     .17       0  5252.2     .11       0  5589.1     .17       0
Bank Sta=4988,5021.5
XS Rating Curve= 0 ,0
Exp/Cntr=0.3,0.1

Type RM Length L Ch R = 1 ,11000   ,500,500,500
BEGIN DESCRIPTION:
WF OF CRYSTAL CREEK TRIB NO 1 21.0
END DESCRIPTION:
XS GIS Cut Line= 3
      3857606.26     10116416.01      3857222.51     10115956.35
      3856957.95     10115516.71
#Sta/Elev= 30
  4401.2   217.5  4410.3  213.58  4424.7  210.97  4446.7  215.37  4459.8  214.75
  4467.6  217.03  4474.1  215.24  4502.7  214.56  4510.5  213.04  4517.1  206.62
  4531.4  200.76  4537.9   200.1  4644.6  200.75  4666.7   203.2  4751.3  199.83
  4765.6  202.19    4780  201.42  4786.5  204.54  4822.9  201.38  4843.7  203.48
  4907.5  201.09  4921.8  202.65  4936.1   199.2  4949.2  199.35 4990.53196.5918
    4998  194.28  5006.2  196.51  5026.9  197.14  5146.2  203.36  5513.1  205.68
#Mann= 5 ,-1 , 0
  4401.2     .11       0  4949.2    .125       0 4990.53     .09       0
  5006.2    .125       0  5026.9     .11       0
Bank Sta=4990.53,5006.2
XS Rating Curve= 0 ,0
Exp/Cntr=0.3,0.1

Type RM Length L Ch R = 1 ,10500   ,476,476,476
BEGIN DESCRIPTION:
WF OF CRYSTAL CREEK TRIB NO 1 20.0
END DESCRIPTION:
XS GIS Cut Line= 3
      3857933.65     10116127.81      3857551.35     10115733.38
      3857281.84     10115289.14
#Sta/Elev= 30
  4450.7  208.43  4473.8  204.68  4480.8  207.41  4487.9  207.39  4494.9  205.95
  4501.9  206.24  4509.1  204.82    4516  204.57  4544.3  206.23  4549.9  205.41
  4558.5  205.89  4565.7  204.09  4586.8  204.47  4608.1   203.4  4707.1  202.01
  4820.3  201.59  4936.8  198.74  4968.8  195.98  4982.9  194.03  4989.9  193.87
  4995.3  192.54  5049.3  196.02  5070.3  197.67  5076.5  199.04  5084.6  199.36
  5143.1  199.75  5178.1  201.39  5229.6  201.03  5340.5  202.49  5519.6  202.78
#Mann= 7 ,-1 , 0
  4450.7     .11       0  4549.9     .17       0  4936.8     .15       0
  4968.8     .09       0  5049.3     .15       0  5070.3     .17       0
  5340.5     .11       0
Bank Sta=4968.8,5049.3
XS Rating Curve= 0 ,0
Exp/Cntr=0.3,0.1

Type RM Length L Ch R = 1 ,10024   ,524,524,524
BEGIN DESCRIPTION:
WF OF CRYSTAL CREEK TRIB NO 1 19.0
END DESCRIPTION:
XS GIS Cut Line= 3
      3858128.06     10116027.07      3857791.43     10115465.43
      3857447.52     10115179.88
#Sta/Elev= 30
  4345.2  203.28  4393.6  202.87  4399.4  203.56  4430.6  202.38  4706.6     201
  4786.3  199.63  4830.2  200.39    4866  198.16  4878.8  198.34  4897.1  198.29
  4911.8  197.16  4918.5  195.94  4924.4  196.39  4934.1  195.45  4939.9  195.67
 4950.74194.3648  4970.1  192.54  4992.4  192.76  4996.5  191.68  5019.4  194.41
  5027.2  193.71  5033.7  195.44  5041.5  195.88    5048  198.15  5055.9  198.52
  5062.4  199.82  5110.3  199.31  5140.5  198.37  5311.1  201.77    5447  202.56
#Mann= 5 ,-1 , 0
  4345.2     .17       0  4878.8     .15       0 4950.74     .09       0
  5019.4     .15       0  5110.3     .17       0
Bank Sta=4950.74,5019.4
XS Rating Curve= 0 ,0
Exp/Cntr=0.3,0.1

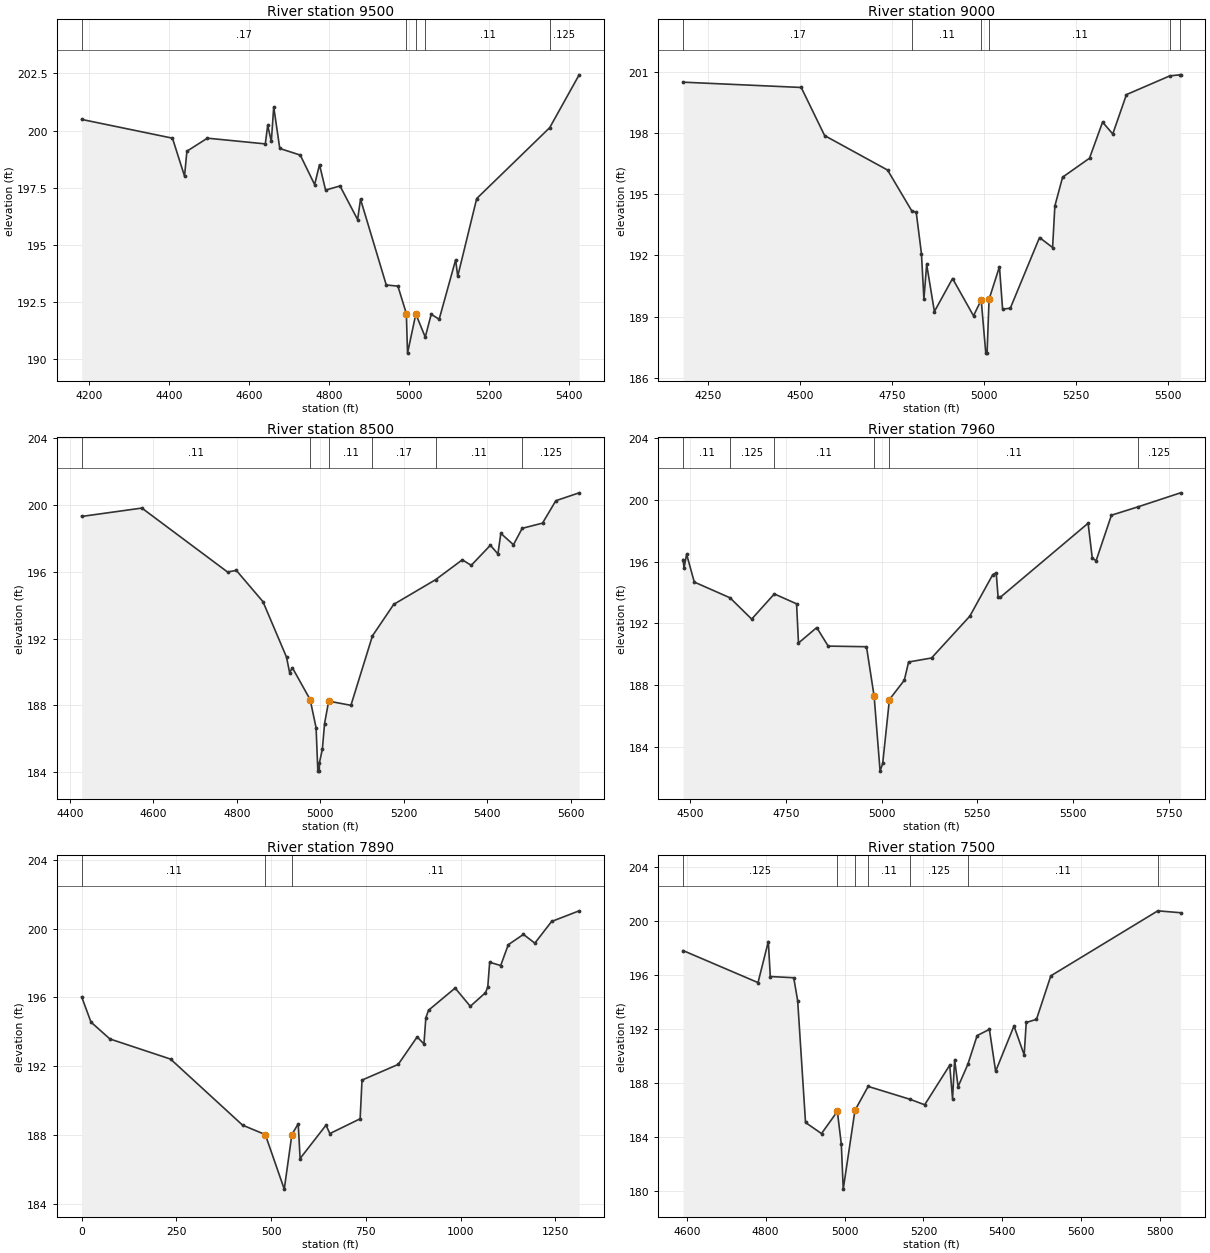
Type RM Length L Ch R = 1 ,9500    ,500,500,500
BEGIN DESCRIPTION:
WF OF CRYSTAL CREEK TRIB NO 1 18.0
END DESCRIPTION:
XS GIS Cut Line= 3
      3858395.46     10115898.67      3857947.66     10115214.13
      3857826.18      10114805.5
#Sta/Elev= 30
    4182  200.49  4409.1  199.67  4439.3  198.01  4445.2   199.1  4496.5  199.67
  4641.3  199.42  4647.3  200.23  4656.4  199.53  4662.4  201.04  4677.5  199.22
  4728.8  198.93  4764.7  197.64  4776.9  198.51  4792.1   197.4  4828.2  197.58
  4872.2  196.11  4879.5     197  4943.9  193.25    4973   193.2  4994.1     192
  4997.1  190.27  5017.8  191.98  5041.4  190.97  5056.3  191.97  5076.2  191.75
  5117.4  194.35  5122.6  193.63  5170.1  197.03  5352.7  200.13  5426.3  202.44
#Mann= 5 ,-1 , 0
    4182     .17       0  4994.1     .09       0  5017.8     .17       0
  5041.4     .11       0  5352.7    .125       0
Bank Sta=4994.1,5017.8
XS Rating Curve= 0 ,0
Exp/Cntr=0.3,0.1

Type RM Length L Ch R = 1 ,9000    ,500,500,500
BEGIN DESCRIPTION:
WF OF CRYSTAL CREEK TRIB NO 1 17.0
END DESCRIPTION:
XS GIS Cut Line= 3
      3858851.07     10115711.17      3858315.03     10115093.15
       3857999.6     10114662.51
#Sta/Elev= 30
  4181.9   200.5    4503  200.24  4566.6  197.88  4737.6  196.19  4803.3  194.19
  4815.5  194.12  4829.7  192.09  4836.4  189.86  4843.9  191.56  4864.9  189.25
  4914.2  190.87  4971.2  189.04  4992.1  189.82  5004.5  187.21    5008  187.21
  5013.5189.8544  5041.7  191.45  5050.2  189.37  5071.1  189.41  5150.6  192.88
  5186.1  192.39  5192.3  194.43  5213.3  195.84  5286.4  196.77  5321.9  198.54
  5349.6  197.96  5386.8  199.89  5504.8  200.81    5532  200.86  5533.8  200.86
#Mann= 6 ,-1 , 0
  4181.9     .17       0  4803.3     .11       0  4992.1     .09       0
  5013.5     .11       0  5504.8    .125       0    5532     .11       0
Bank Sta=4992.1,5013.5
XS Rating Curve= 0 ,0
Exp/Cntr=0.3,0.1

Type RM Length L Ch R = 1 ,8500    ,540,540,540
BEGIN DESCRIPTION:
WF OF CRYSTAL CREEK TRIB NO 1 16.0
END DESCRIPTION:
XS GIS Cut Line= 3
      3859068.19     10115224.59      3858646.45     10114838.02
      3858065.62     10114620.87
#Sta/Elev= 30
  4427.9  199.29  4572.2  199.79  4777.6  195.97  4798.5  196.07  4862.4   194.2
  4918.8  190.89  4926.2  189.97    4933  190.25  4975.5  188.35  4989.7  186.67
  4993.9  184.08  4997.4  184.08  4997.7  184.58  5004.7  185.38    5010  186.92
  5019.9  188.26  5073.2  188.01  5124.8  192.16  5175.8  194.04  5275.9  195.51
  5340.1   196.7  5361.5  196.37  5407.4  197.57  5425.5  197.05  5432.4  198.28
  5462.7   197.6  5483.6  198.58  5532.3  198.89  5564.3  200.23  5620.1   200.7
#Mann= 6 ,-1 , 0
  4427.9     .11       0  4975.5     .09       0  5019.9     .11       0
  5124.8     .17       0  5275.9     .11       0  5483.6    .125       0
Bank Sta=4975.5,5019.9
XS Rating Curve= 0 ,0
Exp/Cntr=0.3,0.1

Type RM Length L Ch R = 1 ,7960    ,70,70,70
BEGIN DESCRIPTION:
WF OF CRYSTAL CREEK TRIB NO 1 15.0
END DESCRIPTION:
XS GIS Cut Line= 3
      3859387.15     10114606.09      3858868.04     10114588.69
      3858087.32     10114556.18
#Sta/Elev= 30
  4480.6  196.13  4483.1  195.59  4489.9  196.48  4509.9  194.68  4603.3  193.66
    4660  192.28  4719.2  193.91  4777.4  193.27  4782.4  190.73  4830.1  191.73
  4860.1  190.53  4960.2  190.49  4980.2  187.28  4995.8  182.43  5002.6  182.93
  5020.2  187.07  5059.1  188.32  5070.3   189.5  5130.3  189.76  5230.4  192.47
  5290.4  195.16  5299.4  195.28  5304.4  193.68  5310.5   193.7  5539.7  198.49
  5550.7  196.21  5560.7  196.07  5600.7  199.01  5671.1  199.56  5781.4  200.46
#Mann= 6 ,-1 , 0
  4480.6     .11       0  4603.3    .125       0  4719.2     .11       0
  4980.2     .09       0  5020.2     .11       0  5671.1    .125       0
Bank Sta=4980.2,5020.2
XS Rating Curve= 0 ,0
Exp/Cntr=0.3,0.1

Type RM Length L Ch R = 1 ,7890    ,390,390,390
XS GIS Cut Line= 3
      3859402.47      10114515.1      3858874.21     10114518.76
      3858089.45     10114471.55
#Sta/Elev= 30
       0  196.03    24.6  194.56    74.6  193.58   234.6  192.41   424.6  188.57
   484.6  188.02   534.6  184.85   554.7  188.02   571.4  188.65   576.4  186.63
   644.8  188.57   654.9  188.08   734.8  188.94   739.8  191.19   835.2   192.1
   885.3   193.7   903.2  193.29   908.2  194.81   915.3  195.25   985.5  196.54
  1025.5  195.48  1065.6  196.27  1071.6   196.6  1076.6  198.04  1105.7  197.85
  1125.7  199.06  1165.8  199.66  1195.8  199.15    1240  200.41  1312.7  201.03
#Mann= 3 , 0 , 0
       0     .11       0   484.6     .09       0   554.7     .11       0
Bank Sta=484.6,554.7
XS Rating Curve= 0 ,0
Exp/Cntr=0.3,0.1

Type RM Length L Ch R = 1 ,7500    ,471,471,471
BEGIN DESCRIPTION:
WF OF CRYSTAL CREEK TRIB NO 1 14.0
END DESCRIPTION:
XS GIS Cut Line= 3
      3859306.88     10114093.94      3858899.61     10114135.68
      3858095.08     10114414.87
#Sta/Elev= 30
  4590.6  197.79  4780.6  195.42  4806.7  198.46  4811.7  195.87  4871.1  195.78
  4881.1  194.08    4901  185.07  4941.5  184.25  4981.7  185.89  4991.7  183.48
  4996.6  180.14 5026.35185.9691  5059.7  187.74  5166.6  186.78    5203  186.38
  5266.5  189.31  5273.7  186.83    5279  189.72  5287.7  187.72  5312.4  189.37
    5336   191.5  5367.1  191.96  5382.9  188.86  5429.4  192.21  5455.2  190.07
  5460.5  192.47  5486.4   192.7  5522.8  195.92    5794  200.73  5851.6  200.59
#Mann= 7 ,-1 , 0
  4590.6    .125       0  4981.7     .09       0 5026.35    .125       0
  5059.7     .11       0  5166.6    .125       0  5312.4     .11       0
    5794    .125       0
Bank Sta=4981.7,5026.35
XS Rating Curve= 0 ,0
Exp/Cntr=0.3,0.1

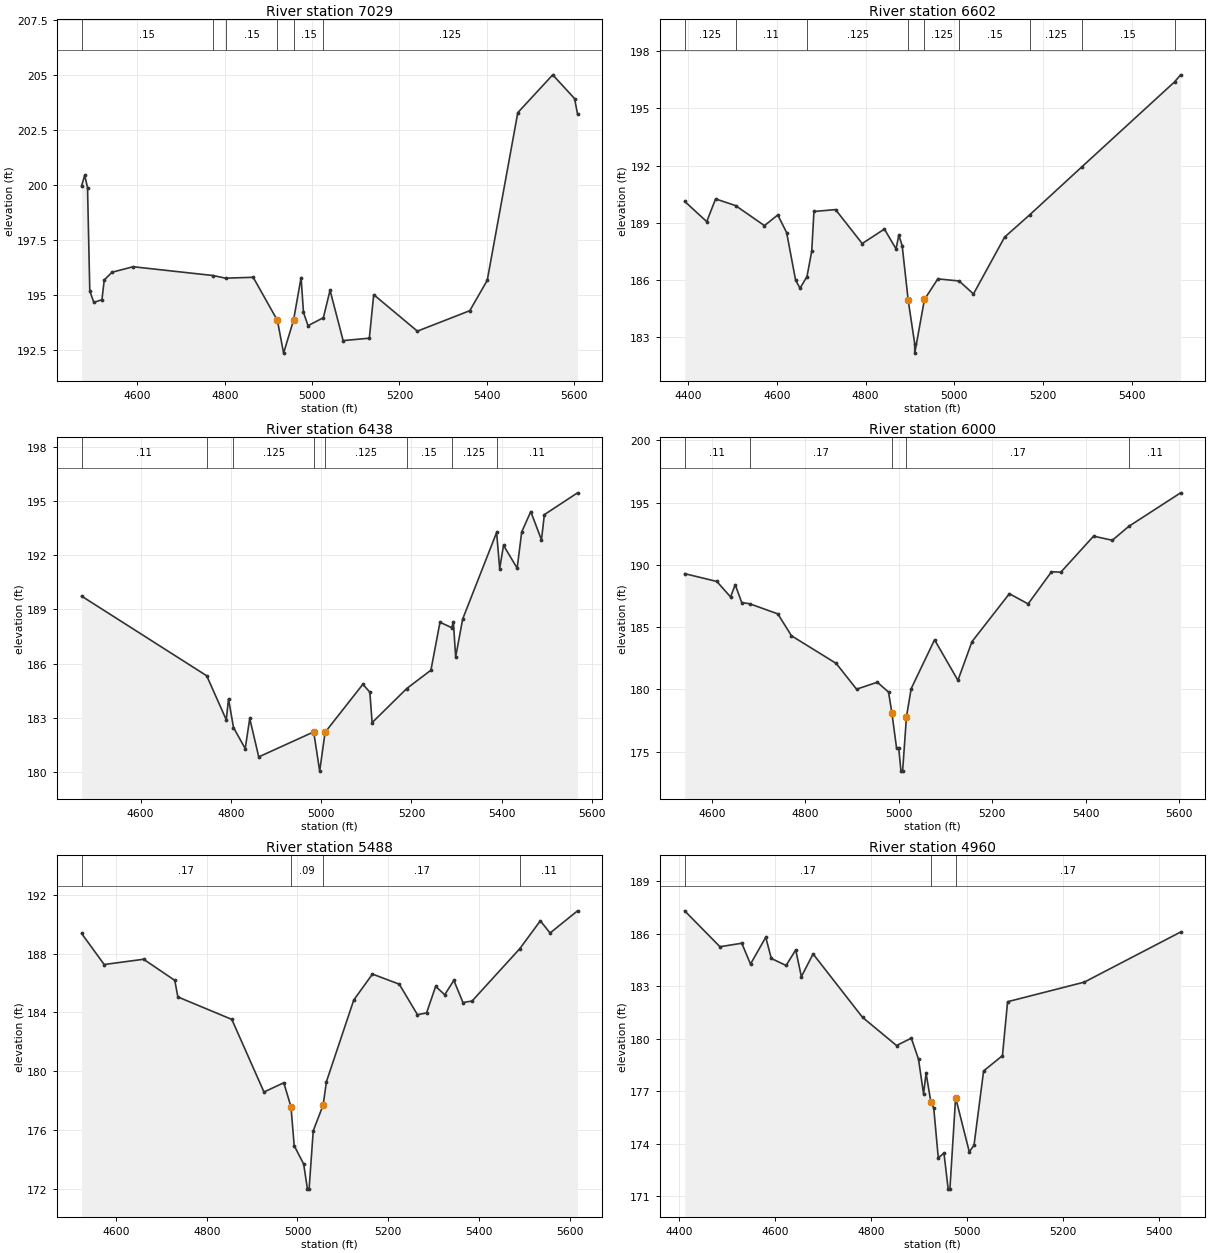
Type RM Length L Ch R = 1 ,7029    ,427,427,427
BEGIN DESCRIPTION:
WF OF CRYSTAL CREEK TRIB NO 1 13.0
END DESCRIPTION:
XS GIS Cut Line= 3
      3859424.63     10113820.34      3858918.97     10113668.73
      3858311.07     10113669.02
#Sta/Elev= 30
  4472.1  199.96  4479.2  200.44  4485.7  199.88  4490.9  195.18  4500.1  194.66
  4518.7  194.78    4524  195.68  4541.8  196.03  4590.1  196.28  4773.2  195.88
  4801.9  195.76  4865.1   195.8  4920.6193.8371  4934.7  192.35  4957.5193.8471
  4974.8  195.79  4980.3   194.2  4990.7   193.6  5025.8  193.96  5041.1  195.21
  5071.1  192.92  5131.1  193.03  5141.1  195.01  5241.1  193.35  5361.1  194.28
  5401.1  195.66  5471.1  203.29  5551.1  205.01  5601.1  203.93  5607.9  203.23
#Mann= 6 ,-1 , 0
  4472.1     .15       0  4773.2    .125       0  4801.9     .15       0
  4920.6     .09       0  4957.5     .15       0  5025.8    .125       0
Bank Sta=4920.6,4957.5
XS Rating Curve= 0 ,0
Exp/Cntr=0.3,0.1

Type RM Length L Ch R = 1 ,6602    ,164,164,164
BEGIN DESCRIPTION:
WF OF CRYSTAL CREEK TRIB NO 1 12.0
END DESCRIPTION:
XS GIS Cut Line= 3
      3859677.47     10113240.91      3859198.09      10113266.2
      3858562.78     10113324.22
#Sta/Elev= 30
    4392  190.13  4441.7  189.07  4461.7  190.26  4506.7  189.91  4571.9  188.86
  4601.9  189.42  4621.9  188.49    4642  186.01    4652  185.58  4667.7  186.19
  4678.4  187.52  4683.4   189.6  4732.1   189.7  4792.2  187.92  4842.2  188.68
  4868.5  187.64  4874.7  188.36  4882.3  187.81 4895.87 184.949  4910.5  182.68
  4910.7  182.18  4932.5  184.99  4962.7  186.07  5010.7  185.96    5043  185.28
  5113.3  188.26    5170  189.43  5287.4  191.94  5496.3  196.39    5510  196.76
#Mann= 9 ,-1 , 0
    4392    .125       0  4506.7     .11       0  4667.7    .125       0
 4895.87     .09       0  4932.5    .125       0  5010.7     .15       0
    5170    .125       0  5287.4     .15       0  5496.3    .125       0
Bank Sta=4895.87,4932.5
XS Rating Curve= 0 ,0
Exp/Cntr=0.3,0.1

Type RM Length L Ch R = 1 ,6438    ,438,438,438
BEGIN DESCRIPTION:
Mapping XS 547465b3
END DESCRIPTION:
XS GIS Cut Line= 3
      3859660.17      10113122.7      3859129.72     10113144.63
       3858564.8     10113204.66
#Sta/Elev= 30
  4469.1  189.74  4746.4  185.32  4789.7  182.88  4794.7  184.04  4805.7  182.45
  4831.7  181.28  4841.7  182.95  4861.7  180.82 4983.48182.2068  4996.7  180.03
 5008.76182.1853  5092.4  184.85  5107.9  184.41  5112.9  182.72  5189.5  184.61
  5243.2  185.63  5263.3  188.29  5289.2  187.99    5293  188.31    5298  186.36
  5313.6  188.47  5388.8  193.27  5395.6  191.26  5404.1  192.56  5434.3  191.29
  5444.4   193.3  5464.5  194.43  5488.2  192.86  5494.6  194.26  5568.1  195.47
#Mann= 8 ,-1 , 0
  4469.1     .11       0  4746.4     .17       0  4805.7    .125       0
 4983.48     .09       0 5008.76    .125       0  5189.5     .15       0
  5289.2    .125       0  5388.8     .11       0
Bank Sta=4983.48,5008.76
XS Rating Curve= 0 ,0
Exp/Cntr=0.3,0.1

Type RM Length L Ch R = 1 ,6000    ,512,512,512
BEGIN DESCRIPTION:
WF OF CRYSTAL CREEK TRIB NO 1 11.0
END DESCRIPTION:
XS GIS Cut Line= 3
      3859667.89     10113091.77      3859244.34     10112916.97
       3858641.8     10112945.28
#Sta/Elev= 30
  4541.8  189.29  4610.7  188.66    4640  187.42    4650   188.4  4663.9  186.97
  4680.9  186.87  4741.1  186.06  4770.4   184.3  4866.1  182.08  4909.7  180.01
  4954.1  180.57  4978.1  179.78  4985.4  178.07  4995.4  175.25    5000  175.25
  5004.7  173.43  5008.2  173.43  5016.5   177.8  5026.5  180.05  5076.6  183.98
  5126.6  180.72  5156.7  183.83  5236.7  187.68  5276.8  186.86  5326.8  189.44
  5346.9  189.41  5416.9   192.3    5457  191.97  5492.4  193.09  5603.2  195.78
#Mann= 5 ,-1 , 0
  4541.8     .11       0  4680.9     .17       0  4985.4     .09       0
  5016.5     .17       0  5492.4     .11       0
Bank Sta=4985.4,5016.5
XS Rating Curve= 0 ,0
Exp/Cntr=0.3,0.1

Type RM Length L Ch R = 1 ,5488    ,528,528,528
BEGIN DESCRIPTION:
WF OF CRYSTAL CREEK TRIB NO 1 10.0
END DESCRIPTION:
XS GIS Cut Line= 3
       3859867.3      10112869.8      3859451.54     10112638.43
      3858836.06     10112591.16
#Sta/Elev= 30
  4524.2  189.39    4574  187.27  4660.9  187.63  4729.6  186.19  4736.4  185.06
  4855.3  183.53  4926.2  178.58  4969.9  179.21  4985.7  177.57  4992.8  174.92
  5013.7  173.67    5022  171.96  5025.6  171.96  5034.8  175.94 5056.61177.6935
  5063.9  179.29  5124.1  184.85  5165.3  186.62  5224.4  185.93  5264.5  183.85
  5284.5  183.97  5304.6  185.78  5324.6  185.21  5344.7  186.19  5364.8  184.68
  5384.8  184.78  5490.3  188.36  5535.3  190.25  5556.8  189.42  5617.3  190.93
#Mann= 4 ,-1 , 0
  4524.2     .17       0  4985.7     .09       0 5056.61     .17       0
  5490.3     .11       0
Bank Sta=4985.7,5056.61
XS Rating Curve= 0 ,0
Exp/Cntr=0.3,0.1

Type RM Length L Ch R = 1 ,4960    ,460,460,460
BEGIN DESCRIPTION:
WF OF CRYSTAL CREEK TRIB NO 1 9.0
END DESCRIPTION:
XS GIS Cut Line= 3
      3859987.13     10112445.34      3859432.79     10112247.45
      3858987.06      10112239.6
#Sta/Elev= 30
  4411.4  187.31    4485  185.26  4530.5  185.46  4548.7  184.27  4580.5   185.8
  4592.1  184.59    4623  184.19    4643  185.08  4654.8  183.55  4679.2  184.85
  4782.3  181.23  4853.3  179.62  4884.1  180.04  4899.1  178.84  4909.6  176.86
  4914.9  178.04 4924.77176.4159  4930.9  176.04  4940.4   173.2  4952.2  173.48
    4961  171.42  4964.6  171.42  4976.5  176.65    5005  173.55  5014.9  173.93
  5034.9  178.17  5074.2  179.04  5084.9  182.12    5245  183.24  5445.8   186.1
#Mann= 3 , 0 , 0
  4411.4     .17       0 4924.77     .09       0  4976.5     .17       0
Bank Sta=4924.77,4976.5
XS Rating Curve= 0 ,0
Exp/Cntr=0.3,0.1

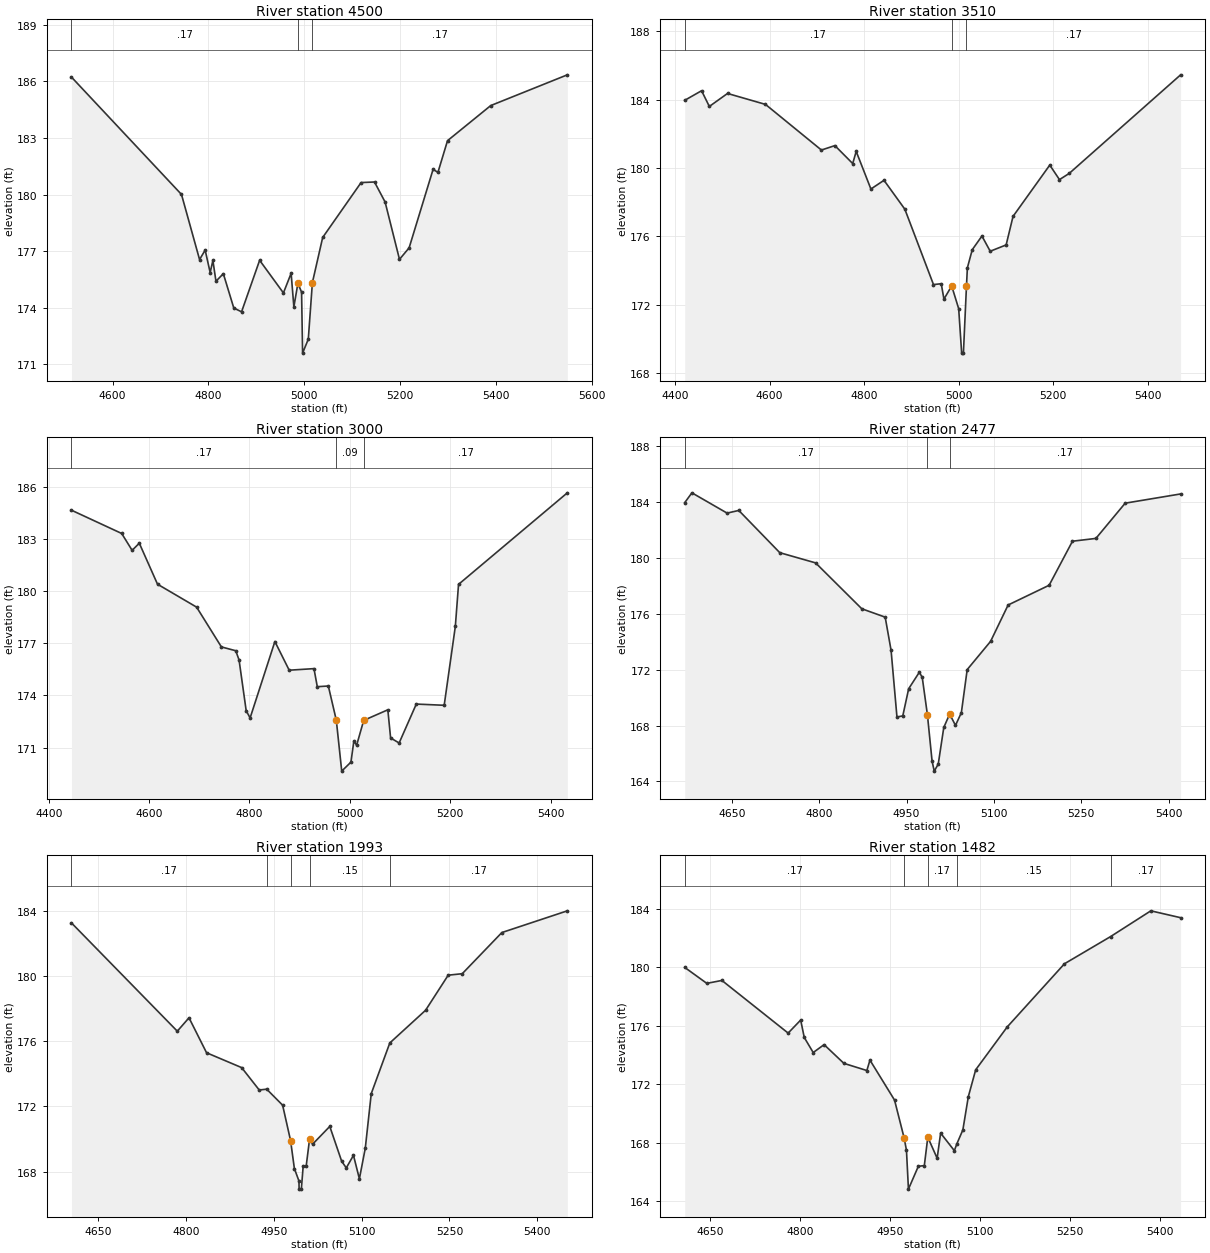
Type RM Length L Ch R = 1 ,4500    ,990,990,990
BEGIN DESCRIPTION:
WF OF CRYSTAL CREEK TRIB NO 1 8.0
END DESCRIPTION:
XS GIS Cut Line= 3
       3859992.3      10112117.2      3859565.99     10111884.26
      3859018.32     10111854.18
#Sta/Elev= 30
  4514.2  186.23  4743.7  180.01  4781.4  176.56  4793.1  177.06  4803.5  175.87
  4809.2  176.51  4815.6  175.41    4831  175.81  4852.8  173.99    4869  173.79
  4906.7  176.52  4956.3  174.79  4972.4  175.83  4978.1  174.05  4986.5   175.3
  4994.2  174.83  4996.3   171.6  5008.2  172.34 5016.74175.3376  5038.2  177.73
  5118.3  180.64  5146.3  180.67  5168.4  179.61  5198.4  176.57  5218.5  177.18
  5268.5  181.34  5278.6  181.18  5298.6  182.86  5388.7  184.72  5548.5  186.35
#Mann= 3 , 0 , 0
  4514.2     .17       0  4986.5     .09       0 5016.74     .17       0
Bank Sta=4986.5,5016.74
XS Rating Curve= 0 ,0
Exp/Cntr=0.3,0.1

Type RM Length L Ch R = 1 ,3510    ,510,510,510
BEGIN DESCRIPTION:
WF OF CRYSTAL CREEK TRIB NO 1 7.0
END DESCRIPTION:
XS GIS Cut Line= 3
       3860289.2     10111750.03      3859775.79     10111481.27
      3859317.88     10111377.63
#Sta/Elev= 30
  4420.5  183.96  4456.1  184.52  4472.5   183.6    4511  184.36  4591.3  183.72
  4709.6  181.05  4738.1  181.31  4775.8  180.26  4783.2  180.97  4814.3  178.77
    4842  179.28  4886.1  177.59  4946.7  173.18  4963.1  173.23  4968.8  172.33
  4985.2   173.1    5000  171.77  5006.3  169.17    5010  169.17  5016.5173.1069
  5018.4  174.16  5028.7  175.22  5049.2  176.02  5066.7  175.13  5100.4   175.5
    5115  177.17  5192.7  180.17  5213.2  179.32  5233.7  179.68  5469.5  185.45
#Mann= 3 , 0 , 0
  4420.5     .17       0  4985.2     .09       0  5016.5     .17       0
Bank Sta=4985.2,5016.5
XS Rating Curve= 0 ,0
Exp/Cntr=0.3,0.1

Type RM Length L Ch R = 1 ,3000    ,523,523,523
BEGIN DESCRIPTION:
WF OF CRYSTAL CREEK TRIB NO 1 6.0
END DESCRIPTION:
XS GIS Cut Line= 3
      3860319.59     10111510.45      3859897.05     10111151.07
      3859507.05     10110961.81
#Sta/Elev= 30
  4445.3  184.66  4545.4  183.32  4566.2  182.35  4580.5  182.76  4616.8   180.4
  4694.7  179.08  4744.1  176.79  4772.7  176.57  4779.3  176.04  4793.5  173.12
  4801.3   172.7  4850.7   177.1  4879.2  175.45  4928.6  175.54  4935.2   174.5
  4957.2  174.54  4973.1172.5714  4983.9  169.64  5002.3  170.16  5008.1  171.38
  5013.6  171.13 5027.72172.5611  5075.8  173.17  5081.3  171.55  5098.3  171.26
  5132.5   173.5  5188.1  173.43  5210.3  177.97  5216.7  180.39  5433.5  185.66
#Mann= 3 , 0 , 0
  4445.3     .17       0  4973.1     .09       0 5027.72     .17       0
Bank Sta=4973.1,5027.72
XS Rating Curve= 0 ,0
Exp/Cntr=0.3,0.1

Type RM Length L Ch R = 1 ,2477    ,484,484,484
BEGIN DESCRIPTION:
WF OF CRYSTAL CREEK TRIB NO 1 5.0
END DESCRIPTION:
XS GIS Cut Line= 3
      3860326.71      10111503.3      3860280.16     10111074.92
      3860239.71     10110656.27
#Sta/Elev= 30
  4569.1  183.94  4581.4  184.64  4641.8  183.19  4661.9  183.38  4732.3  180.36
  4793.8  179.63  4873.1  176.35  4913.3  175.75  4923.4  173.38  4933.5  168.61
  4943.5  168.69  4953.6  170.63  4971.9  171.81  4976.9  171.45 4985.75168.7846
  4993.8  165.46  4997.5  164.74  5004.4  165.24  5013.9  167.86    5024  168.82
    5034  168.01  5044.1  168.92  5054.1     172  5094.3  174.02  5124.4  176.62
  5194.8  178.03  5234.9  181.18  5275.1  181.38  5325.4   183.9  5420.6  184.56
#Mann= 3 , 0 , 0
  4569.1     .17       0 4985.75     .09       0    5024     .17       0
Bank Sta=4985.75,5024
XS Rating Curve= 0 ,0
Exp/Cntr=0.3,0.1

Type RM Length L Ch R = 1 ,1993    ,511,511,511
BEGIN DESCRIPTION:
WF OF CRYSTAL CREEK TRIB NO 1 4.0
END DESCRIPTION:
XS GIS Cut Line= 3
      3860652.38     10111361.85      3860664.68     10110965.94
      3860594.86     10110519.97
#Sta/Elev= 30
  4603.9  183.24  4784.8  176.61  4804.8  177.43  4834.8  175.29  4894.8  174.38
  4924.8  173.01  4937.6  173.06  4964.8  172.08 4978.38169.9148  4984.9   168.2
  4992.7  167.44    4993  166.94  4996.8  166.94  4999.9  168.33    5005  168.33
  5010.9  170.01    5016  169.69  5045.4  170.78  5065.7  168.65  5073.6  168.24
  5085.9  169.01    5096  167.57  5106.1  169.45  5116.3  172.79    5148  175.89
  5209.1  177.89  5247.8  180.04  5271.8  180.13  5339.5  182.65  5451.4  183.98
#Mann= 5 ,-1 , 0
  4603.9     .17       0  4937.6     .15       0 4978.38     .09       0
  5010.9     .15       0    5148     .17       0
Bank Sta=4978.38,5010.9
XS Rating Curve= 0 ,0
Exp/Cntr=0.3,0.1

Type RM Length L Ch R = 1 ,1482    ,482,482,482
BEGIN DESCRIPTION:
WF OF CRYSTAL CREEK TRIB NO 1 3.0
END DESCRIPTION:
XS GIS Cut Line= 3
       3861030.4     10111226.34      3860917.46     10110850.02
      3860695.56     10110476.57
#Sta/Elev= 30
  4607.1  179.99  4643.9   178.9  4669.1   179.1  4779.6   175.5  4800.5  176.39
  4806.5   175.2  4821.4  174.17  4839.6  174.71  4872.6  173.43  4910.9  172.94
  4916.1  173.65  4957.1  170.92 4973.01168.3475    4977  167.49  4980.3  164.83
  4996.8  166.39  5006.8  166.44  5012.6  168.38  5028.2  166.94    5034  168.66
  5056.9  167.46  5061.2  167.94  5071.1  168.88  5080.2  171.15  5092.5  172.99
  5145.1  175.92  5240.6  180.24  5317.6   182.1  5384.7  183.86  5434.4  183.39
#Mann= 5 ,-1 , 0
  4607.1     .17       0 4973.01     .09       0  5012.6     .17       0
  5061.2     .15       0  5317.6     .17       0
Bank Sta=4973.01,5012.6
XS Rating Curve= 0 ,0
Exp/Cntr=0.3,0.1