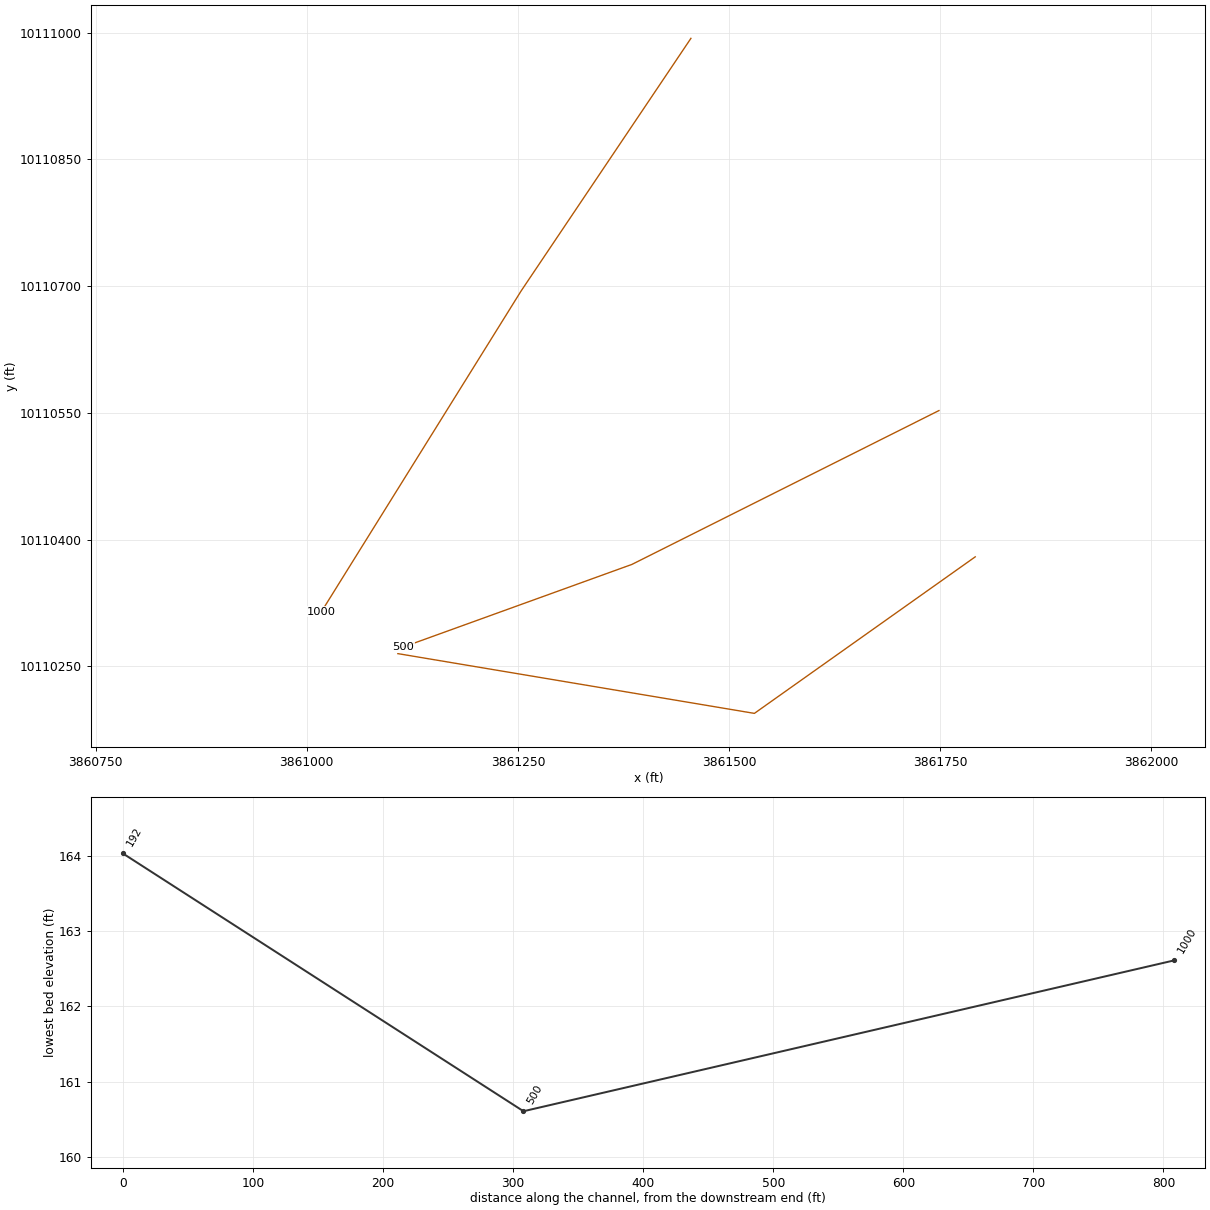
HEC-RAS study WF OF CRYSTAL CREEK TRIB NO 1.prj: WF OF CRYSTAL CREEK TRIB NO 1 Base Level Engineering

--- WF OF CRYSTAL CREEK TRIB NO 1.g01 (geometry) --- (continued)

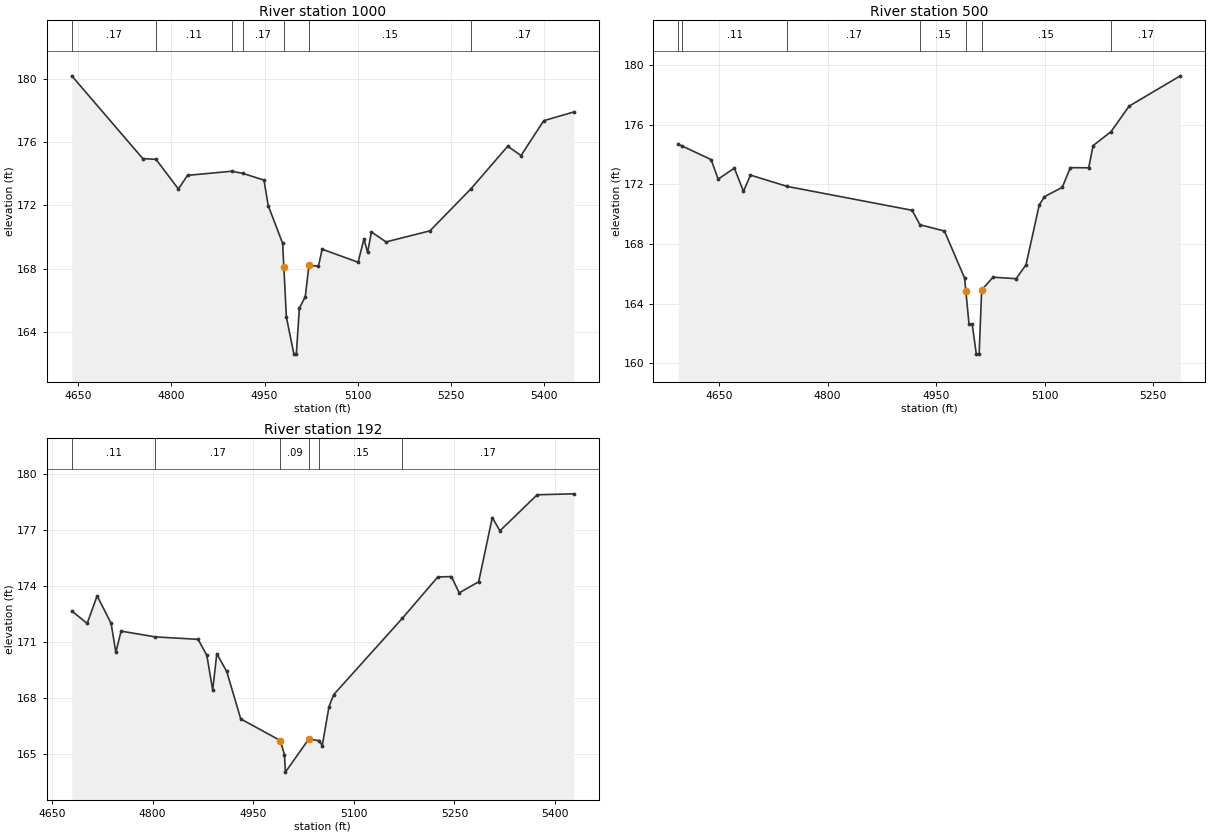
Type RM Length L Ch R = 1 ,1000    ,500,500,500
BEGIN DESCRIPTION:
WF OF CRYSTAL CREEK TRIB NO 1 2.0
END DESCRIPTION:
XS GIS Cut Line= 3
      3861454.87     10110993.36      3861253.92     10110694.43
      3861017.45     10110314.62
#Sta/Elev= 30
  4639.8  180.17    4754  174.95  4775.3   174.9  4811.3  173.03    4826  173.89
  4896.9  174.15  4914.6  174.02    4949  173.59  4955.8  171.98    4979   169.6
  4980.9168.1276    4985  164.95  4997.1  162.61    5001  162.61  5005.9  165.51
  5015.4  166.23  5021.3  168.22  5036.6  168.15  5042.5  169.23  5100.4  168.41
  5109.8  169.88  5115.7  169.03  5121.8  170.32  5145.3  169.69    5216  170.39
  5282.3  173.06  5341.1  175.73  5362.4  175.14    5399  177.34  5447.4  177.89
#Mann= 7 ,-1 , 0
  4639.8     .17       0  4775.3     .11       0  4896.9     .15       0
  4914.6     .17       0  4980.9     .09       0  5021.3     .15       0
  5282.3     .17       0
Bank Sta=4980.9,5021.3
XS Rating Curve= 0 ,0
Exp/Cntr=0.3,0.1

Type RM Length L Ch R = 1 ,500     ,308,308,308
BEGIN DESCRIPTION:
Mapping XS 294d502d
END DESCRIPTION:
XS GIS Cut Line= 3
      3861748.49     10110552.67      3861385.07     10110370.56
       3861114.4     10110272.74
#Sta/Elev= 30
  4593.5   174.7  4598.5  174.58    4639  173.66  4648.7  172.35  4671.1  173.09
  4683.7  171.53  4693.4  172.62  4744.3  171.86  4916.9  170.26  4927.8  169.29
  4961.6  168.87  4989.5  165.71 4991.21164.8466  4995.6  162.63    5000  162.63
  5005.7  160.61  5009.6  160.61  5013.1  164.92  5028.9  165.77  5060.8  165.67
  5074.4   166.6  5092.7  170.61  5099.8  171.17  5124.6   171.8  5135.7  173.12
  5161.1  173.11  5167.2   174.6  5191.9  175.53  5217.1  177.25  5287.8  179.28
#Mann= 7 ,-1 , 0
  4593.5     .17       0  4598.5     .11       0  4744.3     .17       0
  4927.8     .15       0 4991.21     .09       0  5013.1     .15       0
  5191.9     .17       0
Bank Sta=4991.21,5013.1
XS Rating Curve= 0 ,0
Exp/Cntr=0.3,0.1

Type RM Length L Ch R = 1 ,192     ,0,0,0
BEGIN DESCRIPTION:
WF OF CRYSTAL CREEK TRIB NO 1 1.0
END DESCRIPTION:
XS GIS Cut Line= 3
      3861791.48     10110379.51        3861530.     10110194.18
      3861107.88     10110264.92
#Sta/Elev= 30
  4679.5  172.66  4702.5  171.99  4717.3  173.47  4738.2  171.99  4745.2  170.44
    4753  171.58    4804  171.27  4867.8  171.14  4880.9  170.28  4889.6  168.42
  4895.7  170.37  4910.5  169.42  4931.4  166.88  4990.4  165.72  4996.6  164.96
    4998  164.03  5032.6  165.79  5048.1  165.72  5052.9  165.45    5063  167.54
    5070  168.18  5172.4  172.27  5225.2  174.48  5245.5   174.5  5257.1  173.63
  5286.1  174.22  5306.4  177.66  5317.8  176.95  5373.4  178.88    5428  178.93
#Mann= 6 ,-1 , 0
  4679.5     .11       0    4804     .17       0  4990.4     .09       0
  5032.6     .17       0  5048.1     .15       0  5172.4     .17       0
Bank Sta=4990.4,5032.6
XS Rating Curve= 0 ,0
Exp/Cntr=0.3,0.1

Chan Stop Cuts=-1
Use User Specified Reach Order=0
Composite Channel Slope=5

--- WF OF CRYSTAL CREEK TRIB NO 1.g10 (geometry) ---

Geom Title=Existing Conditions
Program Version=4.10

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
River Reach=WF OF CRYSTAL CR,Reach-1

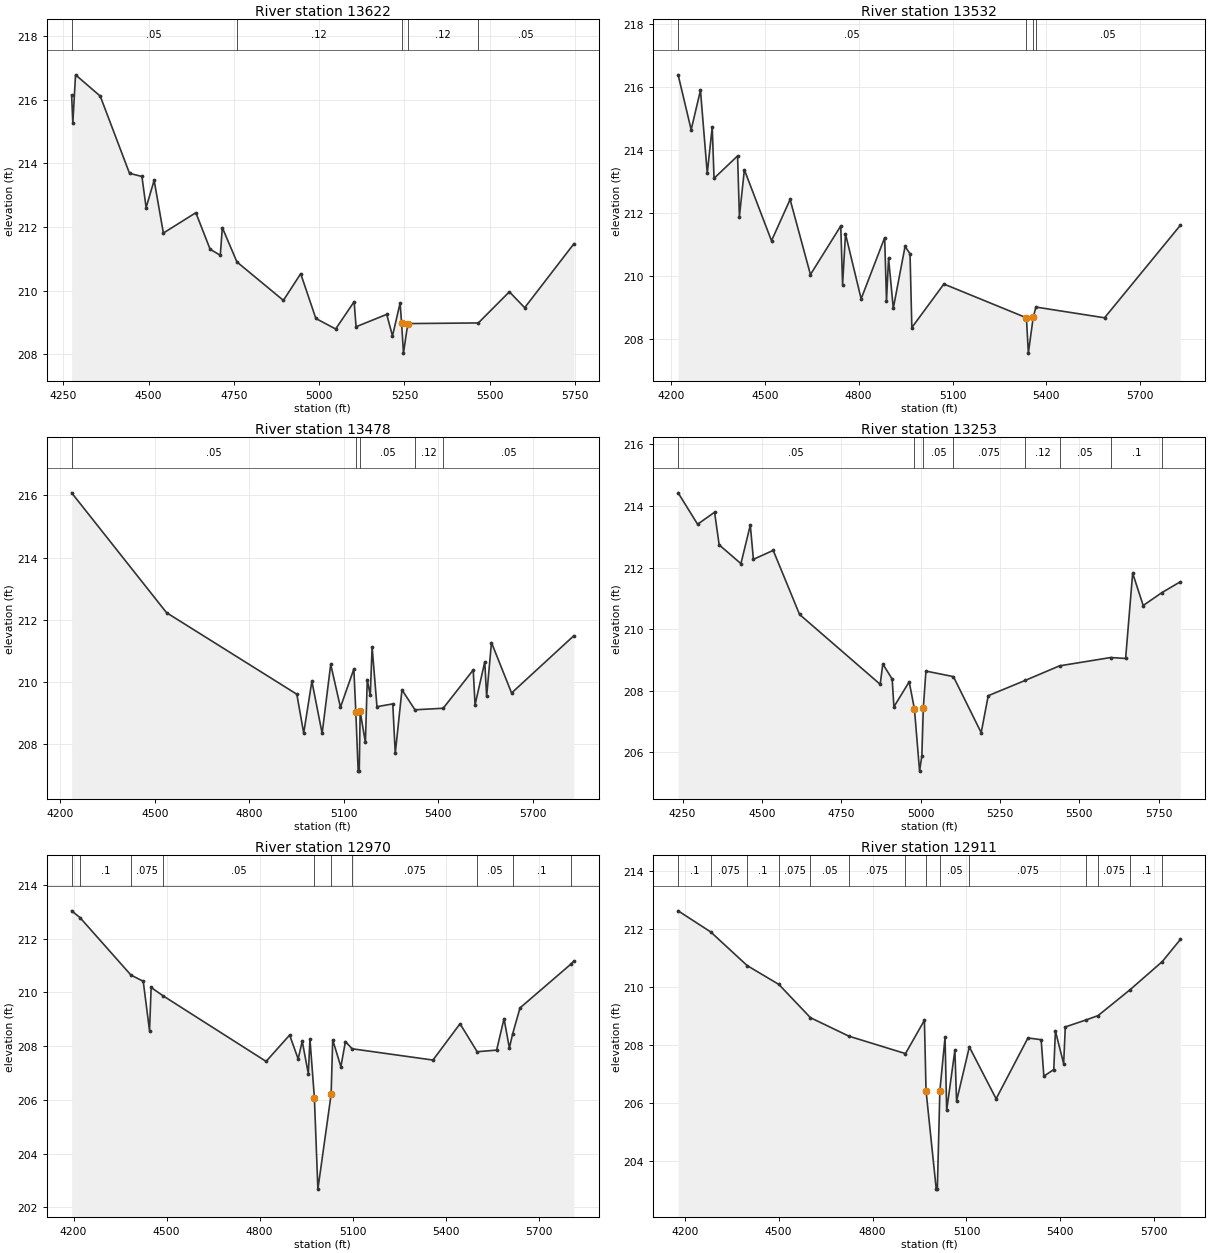
Type RM Length L Ch R = 1 ,13622   ,90,90,90
BEGIN DESCRIPTION:
WF OF CRYSTAL CREEK TRIB NO 1 26.0
END DESCRIPTION:
XS GIS Cut Line= 3
       3856277.2     10117986.96      3855681.25     10117573.21
       3855011.4     10117243.49
#Sta/Elev= 30
  4274.5  216.15  4277.9  215.26  4285.9  216.79  4358.3  216.12  4444.1  213.69
  4480.5  213.59  4492.8  212.61  4516.3  213.47  4543.4  211.81  4638.6  212.45
  4680.4   211.3  4710.2  211.11  4716.2  211.98    4759   210.9  4895.2  209.69
  4945.9  210.53  4990.4  209.12  5048.4  208.79  5102.6  209.65  5108.2  208.86
  5198.1  209.25    5215  208.57  5237.4  209.61 5241.71 208.964  5247.2  208.03
  5259.9  208.96  5466.6  208.98  5557.6  209.96  5602.5  209.46  5746.6  211.47
#Mann= 5 ,-1 , 0
  4274.5     .05       0    4759     .12       0 5241.71     .07       0
  5259.9     .12       0  5466.6     .05       0
Bank Sta=5241.71,5259.9
XS Rating Curve= 0 ,0
Exp/Cntr=0.3,0.1

Type RM Length L Ch R = 1 ,13532   ,54,54,54
BEGIN DESCRIPTION:
Mapping XS 5284a2b1
END DESCRIPTION:
XS GIS Cut Line= 3
      3856424.17     10117891.57      3855746.84     10117511.27
      3855027.42     10117101.77
#Sta/Elev= 30
  4223.2  216.38  4264.9  214.64  4294.6  215.89  4316.3  213.26  4332.2  214.73
    4338   213.1  4413.2  213.81    4419  211.89  4434.9  213.37  4521.6  211.12
    4581  212.43    4646  210.05  4742.9  211.59  4748.7  209.73    4758  211.34
    4808  209.28  4883.2  211.22    4889  209.22  4895.6  210.57  4910.7  208.98
  4948.3  210.94  4964.2  210.71    4970  208.37  5072.4  209.75  5336.1  208.68
  5342.3  207.56  5357.7  208.69  5366.4  209.02  5585.7  208.68  5827.8  211.61
#Mann= 4 ,-1 , 0
  4223.2     .05       0  5336.1     .07       0  5357.7     .12       0
  5366.4     .05       0
Bank Sta=5336.1,5357.7
XS Rating Curve= 0 ,0
Exp/Cntr=0.3,0.1

Type RM Length L Ch R = 1 ,13478   ,225,225,225
BEGIN DESCRIPTION:
Mapping XS 2794839d
END DESCRIPTION:
XS GIS Cut Line= 3
      3856456.74      10117840.8      3855785.65     10117474.61
      3855077.32     10117041.01
#Sta/Elev= 30
  4235.5  216.08  4536.9  212.23  4950.7  209.61  4972.5  208.36  4998.5  210.03
  5031.1  208.35  5058.3  210.57  5089.2  209.19  5131.8  210.42  5138.1  209.03
  5145.5  207.14    5149  207.14 5151.83 209.056  5168.5  208.06  5174.4  210.08
  5183.9  209.57  5189.8  211.13  5205.2  209.21  5255.4   209.3  5263.3  207.71
  5284.6  209.75    5326  209.11  5415.6  209.16  5510.9  210.39  5516.8  209.27
  5547.6  210.65  5553.5  209.54  5568.9  211.27  5632.8  209.65  5830.5  211.49
#Mann= 5 ,-1 , 0
  4235.5     .05       0  5138.1     .07       0 5151.83     .05       0
    5326     .12       0  5415.6     .05       0
Bank Sta=5138.1,5151.83
XS Rating Curve= 0 ,0
Exp/Cntr=0.3,0.1

Type RM Length L Ch R = 1 ,13253   ,283,283,283
BEGIN DESCRIPTION:
Mapping XS 660a28fa
END DESCRIPTION:
XS GIS Cut Line= 3
       3856637.6     10117590.03      3855929.74     10117302.31
      3855192.55     10116947.79
#Sta/Elev= 30
  4235.9  214.43  4297.3  213.41  4350.8   213.8  4365.2  212.74  4433.8  212.13
  4463.3  213.38  4473.1  212.27  4535.5  212.56  4618.5  210.48  4872.5  208.21
  4880.8  208.87  4910.3  208.38  4915.7  207.48  4963.9  208.29  4980.4  207.41
  4996.6  205.39  5003.8  205.89 5008.44  207.45  5016.6  208.64  5103.2  208.46
  5190.7  206.64  5212.9  207.84  5330.1  208.34  5437.6  208.81  5598.6  209.08
  5645.7  209.05  5667.9  211.82  5701.1  210.77  5760.2  211.19    5818  211.54
#Mann= 8 ,-1 , 0
  4235.9     .05       0  4980.4     .07       0 5008.44     .05       0
  5103.2    .075       0  5330.1     .12       0  5437.6     .05       0
  5598.6      .1       0  5760.2     .05       0
Bank Sta=4980.4,5008.44
XS Rating Curve= 0 ,0
Exp/Cntr=0.3,0.1

Type RM Length L Ch R = 1 ,12970   ,59,59,59
BEGIN DESCRIPTION:
WF OF CRYSTAL CREEK TRIB NO 1 25.0
END DESCRIPTION:
XS GIS Cut Line= 3
      3856798.52     10117301.07      3856027.97     10117064.67
       3855239.6     10116865.64
#Sta/Elev= 30
    4194  213.03  4220.8  212.78  4385.3  210.64  4424.8  210.41  4445.1  208.57
  4450.3  210.18  4487.4  209.88  4820.9  207.43  4896.8  208.41  4924.3  207.52
  4937.4  208.18  4957.1  206.97  4962.3  208.26  4976.6 206.076  4987.9  202.68
  5030.5   206.2  5035.7  208.23    5062  207.23  5076.7  208.17  5098.2   207.9
  5358.9  207.48  5446.2  208.83  5501.4  207.79  5564.2  207.85    5588  209.02
  5605.3  207.93  5615.7  208.45  5639.6  209.42  5803.8  211.05  5813.1  211.16
#Mann= 10 ,-1 , 0
    4194    .075       0  4220.8      .1       0  4385.3    .075       0
  4487.4     .05       0  4976.6     .07       0  5030.5     .05       0
  5098.2    .075       0  5501.4     .05       0  5615.7      .1       0
  5803.8     .05       0
Bank Sta=4976.6,5030.5
XS Rating Curve= 0 ,0
Exp/Cntr=0.3,0.1

Type RM Length L Ch R = 1 ,12911   ,411,411,411
BEGIN DESCRIPTION:
Mapping XS 51618a81
END DESCRIPTION:
XS GIS Cut Line= 3
      3856831.53     10117220.35      3856038.73     10117007.38
      3855296.43     10116758.86
#Sta/Elev= 30
  4179.1  212.63  4283.3   211.9  4399.5  210.74  4500.6  210.09  4601.7  208.94
  4724.9   208.3  4905.1   207.7  4965.6  208.85  4970.8  206.42  5003.4  203.02
  5006.9  203.02 5014.99 206.419  5031.5  208.26  5036.7  205.74    5063  207.82
  5068.3  206.06  5109.1  207.93  5194.6  206.14  5296.2  208.24  5338.4  208.18
  5347.1  206.92  5378.7  207.15    5384  208.48  5410.3  207.35  5415.5  208.62
  5481.1  208.86    5520  209.01  5622.8  209.91  5725.5  210.88  5782.8  211.64
#Mann= 14 ,-1 , 0
  4179.1      .1       0  4283.3    .075       0  4399.5      .1       0
  4500.6    .075       0  4601.7     .05       0  4724.9    .075       0
  4905.1     .05       0  4970.8     .07       0 5014.99     .05       0
  5109.1    .075       0  5481.1     .05       0    5520    .075       0
  5622.8      .1       0  5725.5    .075       0
Bank Sta=4970.8,5014.99
XS Rating Curve= 0 ,0
Exp/Cntr=0.3,0.1

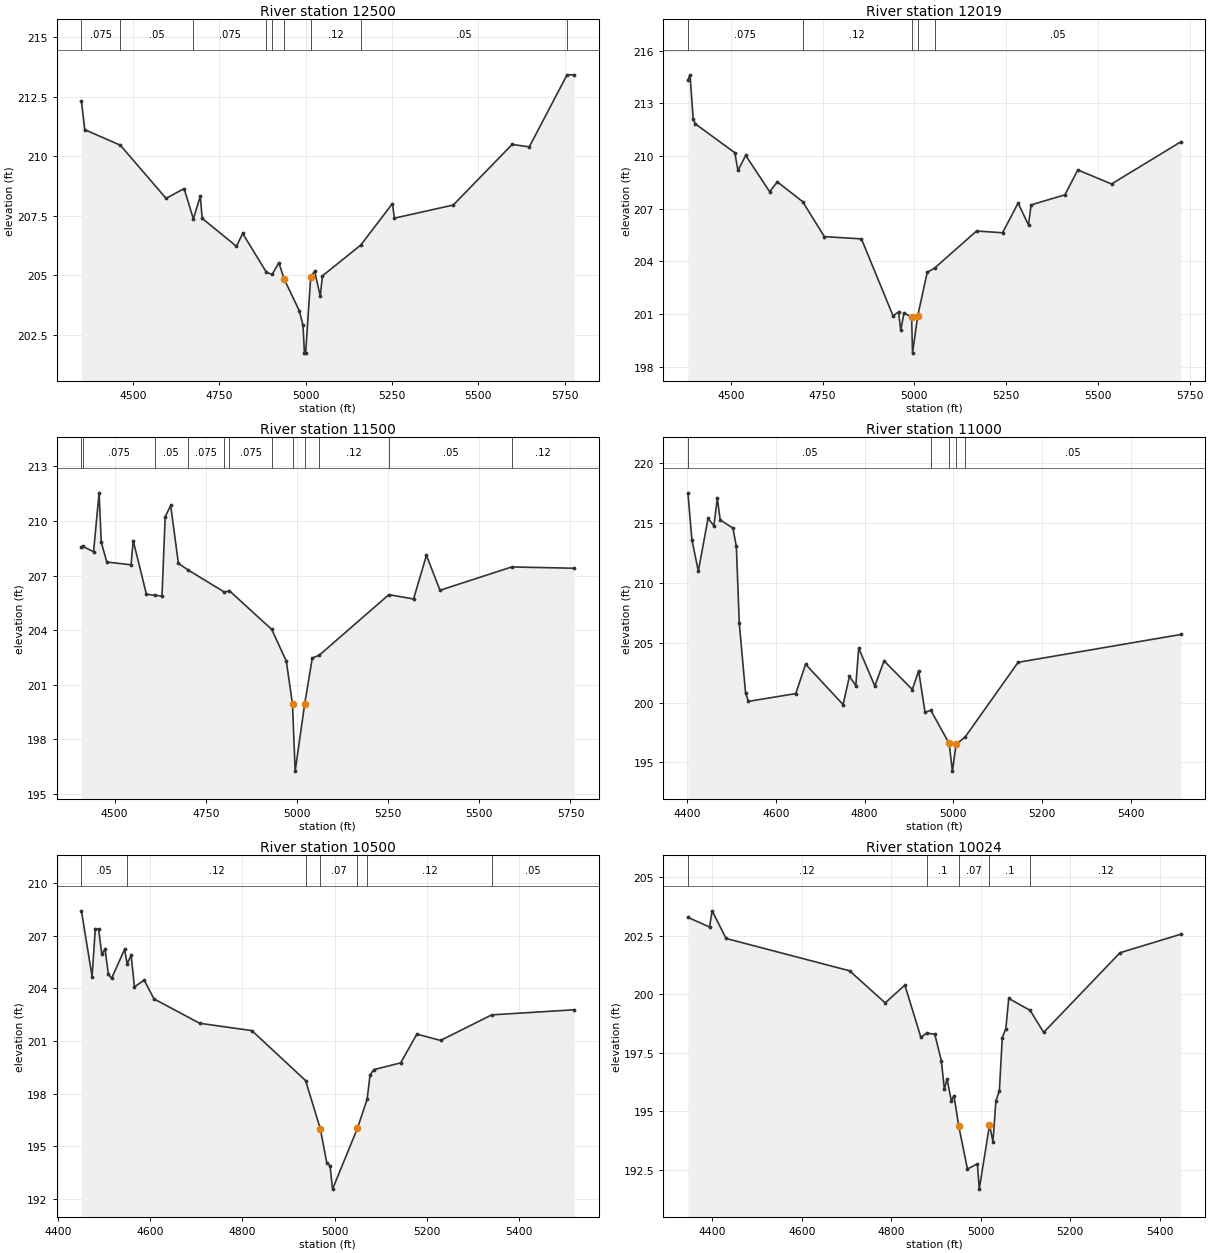
Type RM Length L Ch R = 1 ,12500   ,481,481,481
BEGIN DESCRIPTION:
WF OF CRYSTAL CREEK TRIB NO 1 24.0
END DESCRIPTION:
XS GIS Cut Line= 3
      3856926.67     10117014.07      3856330.69     10116755.39
      3855642.37     10116392.77
#Sta/Elev= 30
  4350.3  212.31  4359.9  211.11  4462.9  210.46  4595.4  208.23  4647.7  208.64
  4674.5  207.37  4694.7  208.32  4700.1  207.39  4799.4  206.22  4817.4  206.76
  4886.1  205.13  4902.6  205.04  4922.1  205.53  4937.7  204.84  4981.3  203.52
  4992.2   202.9  4996.2  201.74  4999.7  201.74  5014.4  204.92  5025.8  205.18
  5042.1  204.13  5048.4  204.98  5159.4  206.27  5251.1  208.01  5256.8   207.4
  5427.3  207.95  5597.9  210.49  5647.6  210.39    5757  213.41    5778  213.41
#Mann= 9 ,-1 , 0
  4350.3    .075       0  4462.9     .05       0  4674.5    .075       0
  4886.1     .05       0  4902.6     .12       0  4937.7     .07       0
  5014.4     .12       0  5159.4     .05       0    5757      .1       0
Bank Sta=4937.7,5014.4
XS Rating Curve= 0 ,0
Exp/Cntr=0.3,0.1

Type RM Length L Ch R = 1 ,12019   ,519,519,519
BEGIN DESCRIPTION:
WF OF CRYSTAL CREEK TRIB NO 1 23.0
END DESCRIPTION:
XS GIS Cut Line= 3
       3857089.9     10116857.84      3856586.12     10116502.31
      3856072.65     10115989.91
#Sta/Elev= 30
  4383.4  214.34  4389.2  214.63  4397.9  212.09    4404  211.83  4511.1  210.19
  4519.8  209.18  4540.7  210.04    4606  207.97  4626.9  208.53    4696   207.4
  4754.9  205.41  4855.9  205.28  4942.1  200.89  4956.9  201.12    4963  200.07
  4971.7  201.06  4992.6  200.82    4995  198.77 5009.11 200.888    5035  203.37
  5055.8  203.63  5169.4  205.73  5240.1  205.63  5282.5  207.32  5310.8  206.07
  5317.9  207.22  5409.8  207.79  5445.1  209.21    5537  208.41  5725.4  210.81
#Mann= 5 ,-1 , 0
  4383.4    .075       0    4696     .12       0  4992.6     .07       0
 5009.11     .12       0  5055.8     .05       0
Bank Sta=4992.6,5009.11
XS Rating Curve= 0 ,0
Exp/Cntr=0.3,0.1

Type RM Length L Ch R = 1 ,11500   ,500,500,500
BEGIN DESCRIPTION:
WF OF CRYSTAL CREEK TRIB NO 1 22.0
END DESCRIPTION:
XS GIS Cut Line= 3
      3857383.02     10116632.77       3856887.9     10116310.62
      3856419.76     10115711.16
#Sta/Elev= 30
  4409.3  208.56  4412.4   208.6  4442.6  208.31  4457.7  211.54  4463.7  208.83
  4478.8  207.74  4545.3  207.59  4551.3  208.91  4587.5  205.97  4609.7  205.92
  4630.2  205.87  4638.9  210.22    4654  210.85  4675.1  207.67  4701.3  207.31
  4801.2  206.09  4815.1  206.16  4931.1  204.04    4971   202.3    4988 199.938
  4995.3  196.26  5021.5  199.97  5042.3  202.47  5061.1  202.62  5252.2  205.95
  5319.9  205.71  5355.2  208.11  5392.3  206.19  5589.1  207.47  5760.6   207.4
#Mann= 12 ,-1 , 0
  4409.3     .05       0  4412.4    .075       0  4609.7     .05       0
  4701.3    .075       0  4801.2     .05       0  4815.1    .075       0
  4931.1     .05       0    4988     .07       0  5021.5     .05       0
  5061.1     .12       0  5252.2     .05       0  5589.1     .12       0
Bank Sta=4988,5021.5
XS Rating Curve= 0 ,0
Exp/Cntr=0.3,0.1

Type RM Length L Ch R = 1 ,11000   ,500,500,500
BEGIN DESCRIPTION:
WF OF CRYSTAL CREEK TRIB NO 1 21.0
END DESCRIPTION:
XS GIS Cut Line= 3
      3857606.26     10116416.01      3857222.51     10115956.35
      3856957.95     10115516.71
#Sta/Elev= 30
  4401.2   217.5  4410.3  213.58  4424.7  210.97  4446.7  215.37  4459.8  214.75
  4467.6  217.03  4474.1  215.24  4502.7  214.56  4510.5  213.04  4517.1  206.62
  4531.4  200.76  4537.9   200.1  4644.6  200.75  4666.7   203.2  4751.3  199.83
  4765.6  202.19    4780  201.42  4786.5  204.54  4822.9  201.38  4843.7  203.48
  4907.5  201.09  4921.8  202.65  4936.1   199.2  4949.2  199.35 4990.53 196.592
    4998  194.28  5006.2  196.51  5026.9  197.14  5146.2  203.36  5513.1  205.68
#Mann= 5 ,-1 , 0
  4401.2     .05       0  4949.2    .075       0 4990.53     .07       0
  5006.2    .075       0  5026.9     .05       0
Bank Sta=4990.53,5006.2
XS Rating Curve= 0 ,0
Exp/Cntr=0.3,0.1

Type RM Length L Ch R = 1 ,10500   ,476,476,476
BEGIN DESCRIPTION:
WF OF CRYSTAL CREEK TRIB NO 1 20.0
END DESCRIPTION:
XS GIS Cut Line= 3
      3857933.65     10116127.81      3857551.35     10115733.38
      3857281.84     10115289.14
#Sta/Elev= 30
  4450.7  208.43  4473.8  204.68  4480.8  207.41  4487.9  207.39  4494.9  205.95
  4501.9  206.24  4509.1  204.82    4516  204.57  4544.3  206.23  4549.9  205.41
  4558.5  205.89  4565.7  204.09  4586.8  204.47  4608.1   203.4  4707.1  202.01
  4820.3  201.59  4936.8  198.74  4968.8  195.98  4982.9  194.03  4989.9  193.87
  4995.3  192.54  5049.3  196.02  5070.3  197.67  5076.5  199.04  5084.6  199.36
  5143.1  199.75  5178.1  201.39  5229.6  201.03  5340.5  202.49  5519.6  202.78
#Mann= 7 ,-1 , 0
  4450.7     .05       0  4549.9     .12       0  4936.8      .1       0
  4968.8     .07       0  5049.3      .1       0  5070.3     .12       0
  5340.5     .05       0
Bank Sta=4968.8,5049.3
XS Rating Curve= 0 ,0
Exp/Cntr=0.3,0.1

Type RM Length L Ch R = 1 ,10024   ,524,524,524
BEGIN DESCRIPTION:
WF OF CRYSTAL CREEK TRIB NO 1 19.0
END DESCRIPTION:
XS GIS Cut Line= 3
      3858128.06     10116027.07      3857791.43     10115465.43
      3857447.52     10115179.88
#Sta/Elev= 30
  4345.2  203.28  4393.6  202.87  4399.4  203.56  4430.6  202.38  4706.6     201
  4786.3  199.63  4830.2  200.39    4866  198.16  4878.8  198.34  4897.1  198.29
  4911.8  197.16  4918.5  195.94  4924.4  196.39  4934.1  195.45  4939.9  195.67
 4950.74 194.365  4970.1  192.54  4992.4  192.76  4996.5  191.68  5019.4  194.41
  5027.2  193.71  5033.7  195.44  5041.5  195.88    5048  198.15  5055.9  198.52
  5062.4  199.82  5110.3  199.31  5140.5  198.37  5311.1  201.77    5447  202.56
#Mann= 5 ,-1 , 0
  4345.2     .12       0  4878.8      .1       0 4950.74     .07       0
  5019.4      .1       0  5110.3     .12       0
Bank Sta=4950.74,5019.4
XS Rating Curve= 0 ,0
Exp/Cntr=0.3,0.1

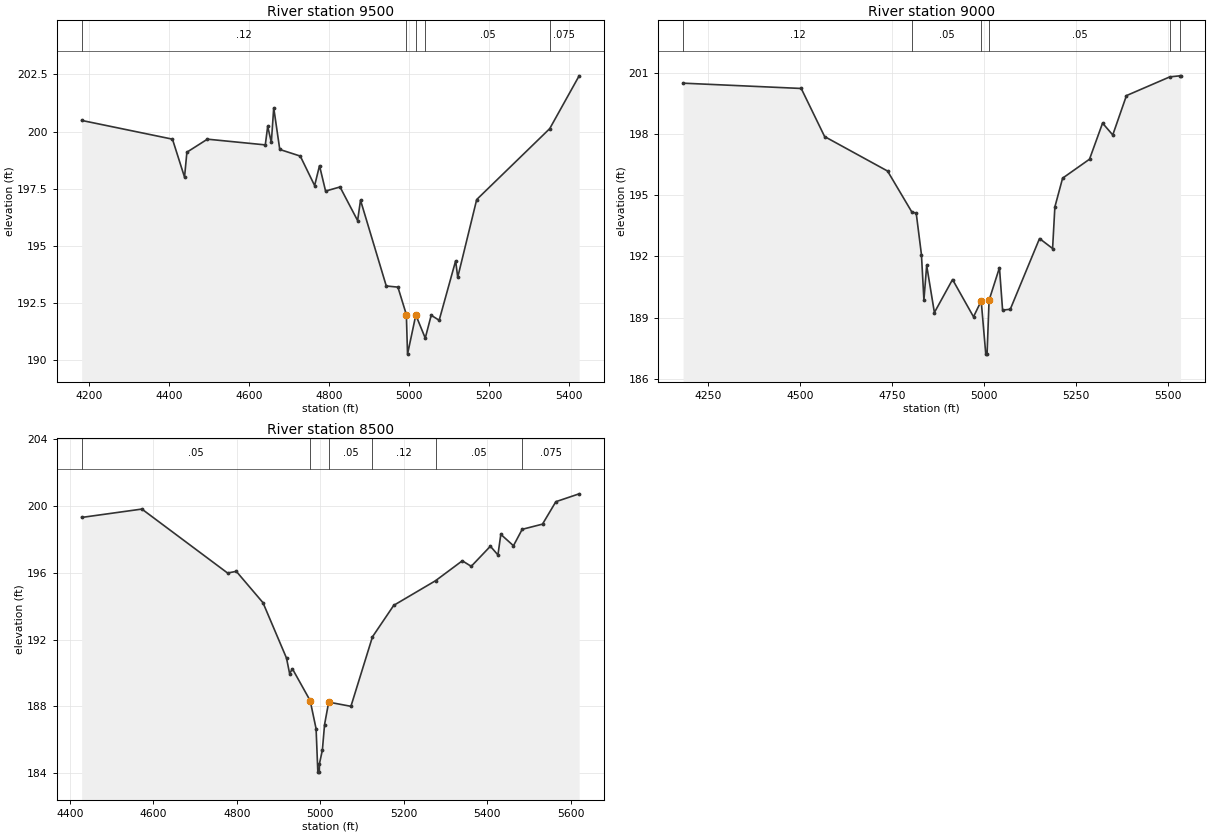
Type RM Length L Ch R = 1 ,9500    ,500,500,500
BEGIN DESCRIPTION:
WF OF CRYSTAL CREEK TRIB NO 1 18.0
END DESCRIPTION:
XS GIS Cut Line= 3
      3858395.46     10115898.67      3857947.66     10115214.13
      3857826.18      10114805.5
#Sta/Elev= 30
    4182  200.49  4409.1  199.67  4439.3  198.01  4445.2   199.1  4496.5  199.67
  4641.3  199.42  4647.3  200.23  4656.4  199.53  4662.4  201.04  4677.5  199.22
  4728.8  198.93  4764.7  197.64  4776.9  198.51  4792.1   197.4  4828.2  197.58
  4872.2  196.11  4879.5     197  4943.9  193.25    4973   193.2  4994.1     192
  4997.1  190.27  5017.8  191.98  5041.4  190.97  5056.3  191.97  5076.2  191.75
  5117.4  194.35  5122.6  193.63  5170.1  197.03  5352.7  200.13  5426.3  202.44
#Mann= 5 ,-1 , 0
    4182     .12       0  4994.1     .07       0  5017.8     .12       0
  5041.4     .05       0  5352.7    .075       0
Bank Sta=4994.1,5017.8
XS Rating Curve= 0 ,0
Exp/Cntr=0.3,0.1

Type RM Length L Ch R = 1 ,9000    ,500,500,500
BEGIN DESCRIPTION:
WF OF CRYSTAL CREEK TRIB NO 1 17.0
END DESCRIPTION:
XS GIS Cut Line= 3
      3858851.07     10115711.17      3858315.03     10115093.15
       3857999.6     10114662.51
#Sta/Elev= 30
  4181.9   200.5    4503  200.24  4566.6  197.88  4737.6  196.19  4803.3  194.19
  4815.5  194.12  4829.7  192.09  4836.4  189.86  4843.9  191.56  4864.9  189.25
  4914.2  190.87  4971.2  189.04  4992.1  189.82  5004.5  187.21    5008  187.21
  5013.5 189.854  5041.7  191.45  5050.2  189.37  5071.1  189.41  5150.6  192.88
  5186.1  192.39  5192.3  194.43  5213.3  195.84  5286.4  196.77  5321.9  198.54
  5349.6  197.96  5386.8  199.89  5504.8  200.81    5532  200.86  5533.8  200.86
#Mann= 6 ,-1 , 0
  4181.9     .12       0  4803.3     .05       0  4992.1     .07       0
  5013.5     .05       0  5504.8    .075       0    5532     .05       0
Bank Sta=4992.1,5013.5
XS Rating Curve= 0 ,0
Exp/Cntr=0.3,0.1

Type RM Length L Ch R = 1 ,8500    ,540,540,540
BEGIN DESCRIPTION:
WF OF CRYSTAL CREEK TRIB NO 1 16.0
END DESCRIPTION:
XS GIS Cut Line= 3
      3859068.19     10115224.59      3858646.45     10114838.02
      3858065.62     10114620.87
#Sta/Elev= 30
  4427.9  199.29  4572.2  199.79  4777.6  195.97  4798.5  196.07  4862.4   194.2
  4918.8  190.89  4926.2  189.97    4933  190.25  4975.5  188.35  4989.7  186.67
  4993.9  184.08  4997.4  184.08  4997.7  184.58  5004.7  185.38    5010  186.92
  5019.9  188.26  5073.2  188.01  5124.8  192.16  5175.8  194.04  5275.9  195.51
  5340.1   196.7  5361.5  196.37  5407.4  197.57  5425.5  197.05  5432.4  198.28
  5462.7   197.6  5483.6  198.58  5532.3  198.89  5564.3  200.23  5620.1   200.7
#Mann= 6 ,-1 , 0
  4427.9     .05       0  4975.5     .07       0  5019.9     .05       0
  5124.8     .12       0  5275.9     .05       0  5483.6    .075       0
Bank Sta=4975.5,5019.9
XS Rating Curve= 0 ,0
Exp/Cntr=0.3,0.1