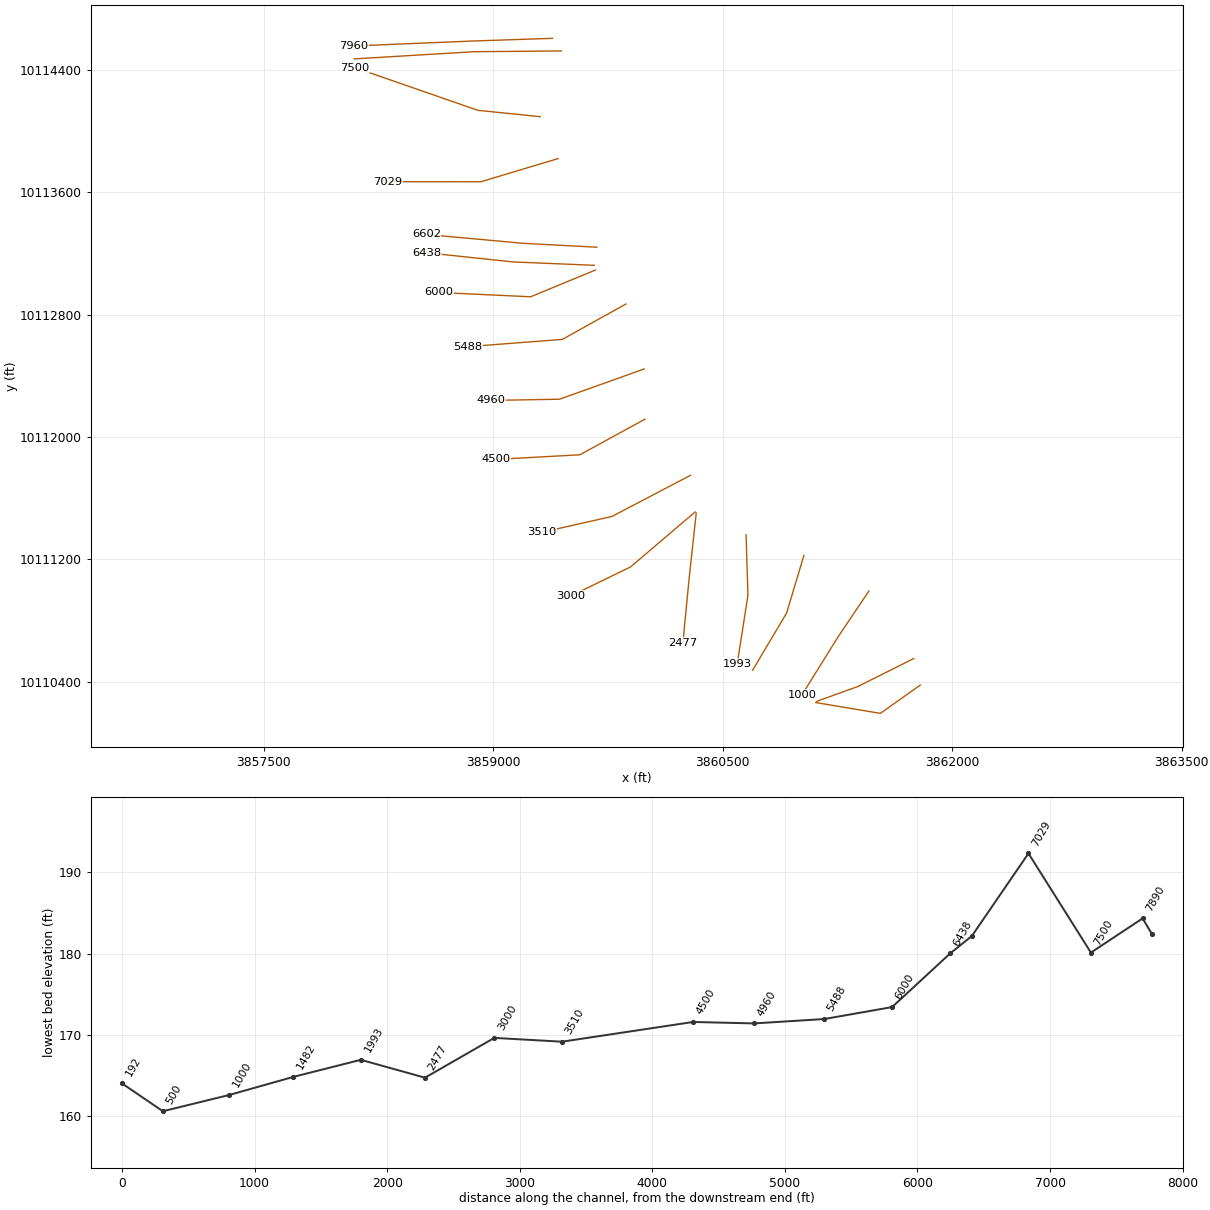
HEC-RAS study WF OF CRYSTAL CREEK TRIB NO 1.prj: WF OF CRYSTAL CREEK TRIB NO 1 Base Level Engineering

--- WF OF CRYSTAL CREEK TRIB NO 1.g10 (geometry) --- (continued)

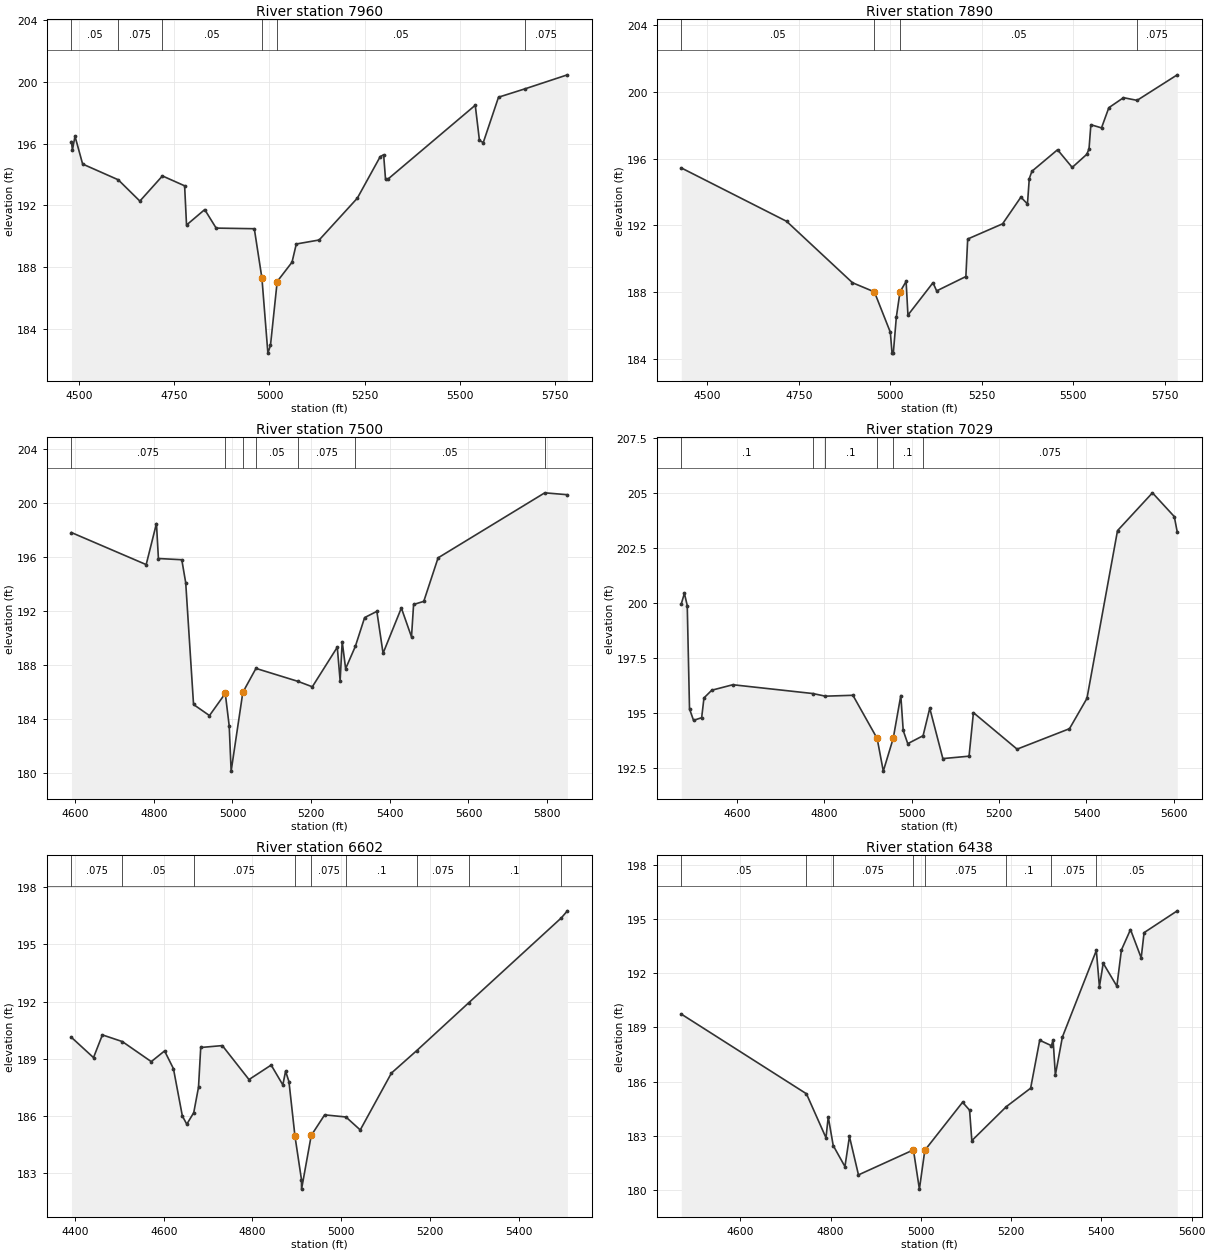
Type RM Length L Ch R = 1 ,7960    ,70,70,70
BEGIN DESCRIPTION:
WF OF CRYSTAL CREEK TRIB NO 1 15.0
END DESCRIPTION:
XS GIS Cut Line= 3
      3859387.15     10114606.09      3858868.04     10114588.69
      3858087.32     10114556.18
#Sta/Elev= 30
  4480.6  196.13  4483.1  195.59  4489.9  196.48  4509.9  194.68  4603.3  193.66
    4660  192.28  4719.2  193.91  4777.4  193.27  4782.4  190.73  4830.1  191.73
  4860.1  190.53  4960.2  190.49  4980.2  187.28  4995.8  182.43  5002.6  182.93
  5020.2  187.07  5059.1  188.32  5070.3   189.5  5130.3  189.76  5230.4  192.47
  5290.4  195.16  5299.4  195.28  5304.4  193.68  5310.5   193.7  5539.7  198.49
  5550.7  196.21  5560.7  196.07  5600.7  199.01  5671.1  199.56  5781.4  200.46
#Mann= 6 ,-1 , 0
  4480.6     .05       0  4603.3    .075       0  4719.2     .05       0
  4980.2     .07       0  5020.2     .05       0  5671.1    .075       0
Bank Sta=4980.2,5020.2
XS Rating Curve= 0 ,0
Exp/Cntr=0.3,0.1

Type RM Length L Ch R = 1 ,7890    ,390,390,390
BEGIN DESCRIPTION:
Mapping XS dfd34819
END DESCRIPTION:
XS GIS Cut Line= 3
      3859445.79     10114523.63      3858874.21     10114518.76
      3858091.13     10114471.65
#Sta/Elev= 30
  4428.4  195.45  4716.3  192.25  4896.4  188.57  4956.4  188.02    5000   185.6
  5004.6  184.35  5008.1  184.35  5016.4  186.51  5026.4  188.02  5043.1  188.65
  5048.1  186.63  5116.6  188.57  5126.6  188.08  5206.5  188.94  5211.5  191.19
  5306.9   192.1    5357   193.7  5374.9  193.29  5379.9  194.81  5387.1  195.25
  5457.2  196.54  5497.3  195.48  5537.3  196.27  5543.3   196.6  5548.3  198.04
  5577.4  197.85  5597.4  199.06  5637.5  199.66  5674.7   199.5  5784.5  201.03
#Mann= 4 ,-1 , 0
  4428.4     .05       0  4956.4     .07       0  5026.4     .05       0
  5674.7    .075       0
Bank Sta=4956.4,5026.4
XS Rating Curve= 0 ,0
Exp/Cntr=0.3,0.1

Type RM Length L Ch R = 1 ,7500    ,471,471,471
BEGIN DESCRIPTION:
WF OF CRYSTAL CREEK TRIB NO 1 14.0
END DESCRIPTION:
XS GIS Cut Line= 3
      3859306.88     10114093.94      3858899.61     10114135.68
      3858095.08     10114414.87
#Sta/Elev= 30
  4590.6  197.79  4780.6  195.42  4806.7  198.46  4811.7  195.87  4871.1  195.78
  4881.1  194.08    4901  185.07  4941.5  184.25  4981.7  185.89  4991.7  183.48
  4996.6  180.14 5026.35 185.969  5059.7  187.74  5166.6  186.78    5203  186.38
  5266.5  189.31  5273.7  186.83    5279  189.72  5287.7  187.72  5312.4  189.37
    5336   191.5  5367.1  191.96  5382.9  188.86  5429.4  192.21  5455.2  190.07
  5460.5  192.47  5486.4   192.7  5522.8  195.92    5794  200.73  5851.6  200.59
#Mann= 7 ,-1 , 0
  4590.6    .075       0  4981.7     .07       0 5026.35    .075       0
  5059.7     .05       0  5166.6    .075       0  5312.4     .05       0
    5794    .075       0
Bank Sta=4981.7,5026.35
XS Rating Curve= 0 ,0
Exp/Cntr=0.3,0.1

Type RM Length L Ch R = 1 ,7029    ,427,427,427
BEGIN DESCRIPTION:
WF OF CRYSTAL CREEK TRIB NO 1 13.0
END DESCRIPTION:
XS GIS Cut Line= 3
      3859424.63     10113820.34      3858918.97     10113668.73
      3858311.07     10113669.02
#Sta/Elev= 30
  4472.1  199.96  4479.2  200.44  4485.7  199.88  4490.9  195.18  4500.1  194.66
  4518.7  194.78    4524  195.68  4541.8  196.03  4590.1  196.28  4773.2  195.88
  4801.9  195.76  4865.1   195.8  4920.6 193.837  4934.7  192.35  4957.5 193.847
  4974.8  195.79  4980.3   194.2  4990.7   193.6  5025.8  193.96  5041.1  195.21
  5071.1  192.92  5131.1  193.03  5141.1  195.01  5241.1  193.35  5361.1  194.28
  5401.1  195.66  5471.1  203.29  5551.1  205.01  5601.1  203.93  5607.9  203.23
#Mann= 6 ,-1 , 0
  4472.1      .1       0  4773.2    .075       0  4801.9      .1       0
  4920.6     .07       0  4957.5      .1       0  5025.8    .075       0
Bank Sta=4920.6,4957.5
XS Rating Curve= 0 ,0
Exp/Cntr=0.3,0.1

Type RM Length L Ch R = 1 ,6602    ,164,164,164
BEGIN DESCRIPTION:
WF OF CRYSTAL CREEK TRIB NO 1 12.0
END DESCRIPTION:
XS GIS Cut Line= 3
      3859677.47     10113240.91      3859198.09      10113266.2
      3858562.78     10113324.22
#Sta/Elev= 30
    4392  190.13  4441.7  189.07  4461.7  190.26  4506.7  189.91  4571.9  188.86
  4601.9  189.42  4621.9  188.49    4642  186.01    4652  185.58  4667.7  186.19
  4678.4  187.52  4683.4   189.6  4732.1   189.7  4792.2  187.92  4842.2  188.68
  4868.5  187.64  4874.7  188.36  4882.3  187.81 4895.87 184.949  4910.5  182.68
  4910.7  182.18  4932.5  184.99  4962.7  186.07  5010.7  185.96    5043  185.28
  5113.3  188.26    5170  189.43  5287.4  191.94  5496.3  196.39    5510  196.76
#Mann= 9 ,-1 , 0
    4392    .075       0  4506.7     .05       0  4667.7    .075       0
 4895.87     .07       0  4932.5    .075       0  5010.7      .1       0
    5170    .075       0  5287.4      .1       0  5496.3    .075       0
Bank Sta=4895.87,4932.5
XS Rating Curve= 0 ,0
Exp/Cntr=0.3,0.1

Type RM Length L Ch R = 1 ,6438    ,438,438,438
BEGIN DESCRIPTION:
Mapping XS 547465b3
END DESCRIPTION:
XS GIS Cut Line= 3
      3859660.17      10113122.7      3859129.72     10113144.63
       3858564.8     10113204.66
#Sta/Elev= 30
  4469.1  189.74  4746.4  185.32  4789.7  182.88  4794.7  184.04  4805.7  182.45
  4831.7  181.28  4841.7  182.95  4861.7  180.82 4983.48 182.207  4996.7  180.03
 5008.76 182.185  5092.4  184.85  5107.9  184.41  5112.9  182.72  5189.5  184.61
  5243.2  185.63  5263.3  188.29  5289.2  187.99    5293  188.31    5298  186.36
  5313.6  188.47  5388.8  193.27  5395.6  191.26  5404.1  192.56  5434.3  191.29
  5444.4   193.3  5464.5  194.43  5488.2  192.86  5494.6  194.26  5568.1  195.47
#Mann= 8 ,-1 , 0
  4469.1     .05       0  4746.4     .12       0  4805.7    .075       0
 4983.48     .07       0 5008.76    .075       0  5189.5      .1       0
  5289.2    .075       0  5388.8     .05       0
Bank Sta=4983.48,5008.76
XS Rating Curve= 0 ,0
Exp/Cntr=0.3,0.1

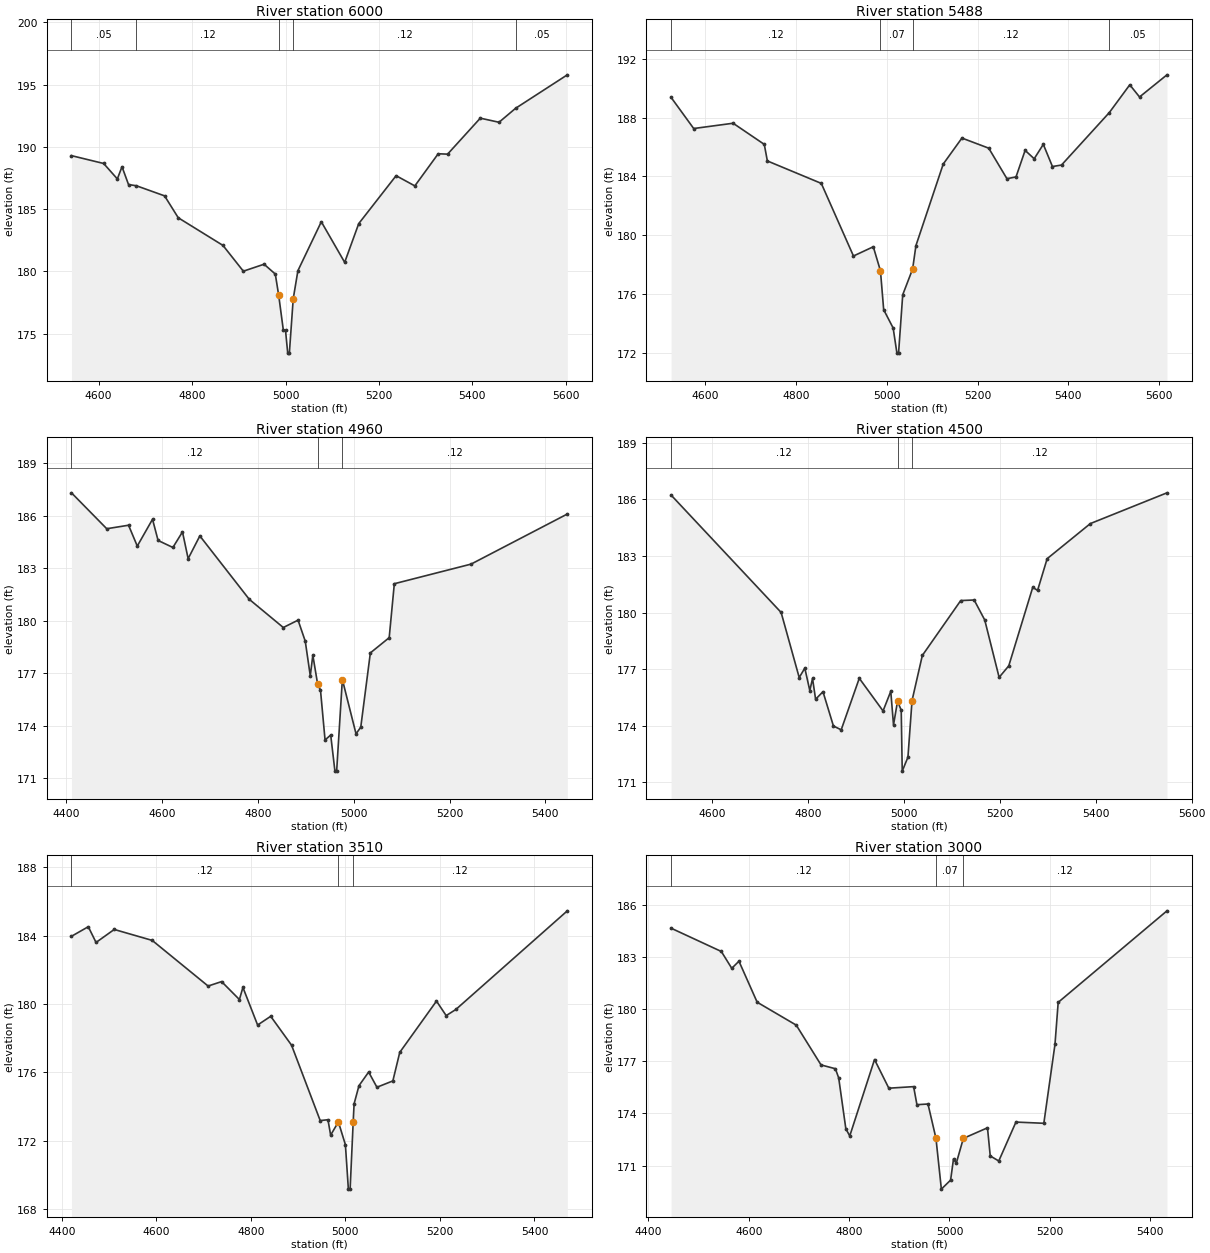
Type RM Length L Ch R = 1 ,6000    ,512,512,512
BEGIN DESCRIPTION:
WF OF CRYSTAL CREEK TRIB NO 1 11.0
END DESCRIPTION:
XS GIS Cut Line= 3
      3859667.89     10113091.77      3859244.34     10112916.97
       3858641.8     10112945.28
#Sta/Elev= 30
  4541.8  189.29  4610.7  188.66    4640  187.42    4650   188.4  4663.9  186.97
  4680.9  186.87  4741.1  186.06  4770.4   184.3  4866.1  182.08  4909.7  180.01
  4954.1  180.57  4978.1  179.78  4985.4  178.07  4995.4  175.25    5000  175.25
  5004.7  173.43  5008.2  173.43  5016.5   177.8  5026.5  180.05  5076.6  183.98
  5126.6  180.72  5156.7  183.83  5236.7  187.68  5276.8  186.86  5326.8  189.44
  5346.9  189.41  5416.9   192.3    5457  191.97  5492.4  193.09  5603.2  195.78
#Mann= 5 ,-1 , 0
  4541.8     .05       0  4680.9     .12       0  4985.4     .07       0
  5016.5     .12       0  5492.4     .05       0
Bank Sta=4985.4,5016.5
XS Rating Curve= 0 ,0
Exp/Cntr=0.3,0.1

Type RM Length L Ch R = 1 ,5488    ,528,528,528
BEGIN DESCRIPTION:
WF OF CRYSTAL CREEK TRIB NO 1 10.0
END DESCRIPTION:
XS GIS Cut Line= 3
       3859867.3      10112869.8      3859451.54     10112638.43
      3858836.06     10112591.16
#Sta/Elev= 30
  4524.2  189.39    4574  187.27  4660.9  187.63  4729.6  186.19  4736.4  185.06
  4855.3  183.53  4926.2  178.58  4969.9  179.21  4985.7  177.57  4992.8  174.92
  5013.7  173.67    5022  171.96  5025.6  171.96  5034.8  175.94 5056.61 177.694
  5063.9  179.29  5124.1  184.85  5165.3  186.62  5224.4  185.93  5264.5  183.85
  5284.5  183.97  5304.6  185.78  5324.6  185.21  5344.7  186.19  5364.8  184.68
  5384.8  184.78  5490.3  188.36  5535.3  190.25  5556.8  189.42  5617.3  190.93
#Mann= 4 ,-1 , 0
  4524.2     .12       0  4985.7     .07       0 5056.61     .12       0
  5490.3     .05       0
Bank Sta=4985.7,5056.61
XS Rating Curve= 0 ,0
Exp/Cntr=0.3,0.1

Type RM Length L Ch R = 1 ,4960    ,460,460,460
BEGIN DESCRIPTION:
WF OF CRYSTAL CREEK TRIB NO 1 9.0
END DESCRIPTION:
XS GIS Cut Line= 3
      3859987.13     10112445.34      3859432.79     10112247.45
      3858987.06      10112239.6
#Sta/Elev= 30
  4411.4  187.31    4485  185.26  4530.5  185.46  4548.7  184.27  4580.5   185.8
  4592.1  184.59    4623  184.19    4643  185.08  4654.8  183.55  4679.2  184.85
  4782.3  181.23  4853.3  179.62  4884.1  180.04  4899.1  178.84  4909.6  176.86
  4914.9  178.04 4924.77 176.416  4930.9  176.04  4940.4   173.2  4952.2  173.48
    4961  171.42  4964.6  171.42  4976.5  176.65    5005  173.55  5014.9  173.93
  5034.9  178.17  5074.2  179.04  5084.9  182.12    5245  183.24  5445.8   186.1
#Mann= 3 , 0 , 0
  4411.4     .12       0 4924.77     .07       0  4976.5     .12       0
Bank Sta=4924.77,4976.5
XS Rating Curve= 0 ,0
Exp/Cntr=0.3,0.1

Type RM Length L Ch R = 1 ,4500    ,990,990,990
BEGIN DESCRIPTION:
WF OF CRYSTAL CREEK TRIB NO 1 8.0
END DESCRIPTION:
XS GIS Cut Line= 3
       3859992.3      10112117.2      3859565.99     10111884.26
      3859018.32     10111854.18
#Sta/Elev= 30
  4514.2  186.23  4743.7  180.01  4781.4  176.56  4793.1  177.06  4803.5  175.87
  4809.2  176.51  4815.6  175.41    4831  175.81  4852.8  173.99    4869  173.79
  4906.7  176.52  4956.3  174.79  4972.4  175.83  4978.1  174.05  4986.5   175.3
  4994.2  174.83  4996.3   171.6  5008.2  172.34 5016.74 175.338  5038.2  177.73
  5118.3  180.64  5146.3  180.67  5168.4  179.61  5198.4  176.57  5218.5  177.18
  5268.5  181.34  5278.6  181.18  5298.6  182.86  5388.7  184.72  5548.5  186.35
#Mann= 3 , 0 , 0
  4514.2     .12       0  4986.5     .07       0 5016.74     .12       0
Bank Sta=4986.5,5016.74
XS Rating Curve= 0 ,0
Exp/Cntr=0.3,0.1

Type RM Length L Ch R = 1 ,3510    ,510,510,510
BEGIN DESCRIPTION:
WF OF CRYSTAL CREEK TRIB NO 1 7.0
END DESCRIPTION:
XS GIS Cut Line= 3
       3860289.2     10111750.03      3859775.79     10111481.27
      3859317.88     10111377.63
#Sta/Elev= 30
  4420.5  183.96  4456.1  184.52  4472.5   183.6    4511  184.36  4591.3  183.72
  4709.6  181.05  4738.1  181.31  4775.8  180.26  4783.2  180.97  4814.3  178.77
    4842  179.28  4886.1  177.59  4946.7  173.18  4963.1  173.23  4968.8  172.33
  4985.2   173.1    5000  171.77  5006.3  169.17    5010  169.17  5016.5 173.107
  5018.4  174.16  5028.7  175.22  5049.2  176.02  5066.7  175.13  5100.4   175.5
    5115  177.17  5192.7  180.17  5213.2  179.32  5233.7  179.68  5469.5  185.45
#Mann= 3 , 0 , 0
  4420.5     .12       0  4985.2     .07       0  5016.5     .12       0
Bank Sta=4985.2,5016.5
XS Rating Curve= 0 ,0
Exp/Cntr=0.3,0.1

Type RM Length L Ch R = 1 ,3000    ,523,523,523
BEGIN DESCRIPTION:
WF OF CRYSTAL CREEK TRIB NO 1 6.0
END DESCRIPTION:
XS GIS Cut Line= 3
      3860319.59     10111510.45      3859897.05     10111151.07
      3859507.05     10110961.81
#Sta/Elev= 30
  4445.3  184.66  4545.4  183.32  4566.2  182.35  4580.5  182.76  4616.8   180.4
  4694.7  179.08  4744.1  176.79  4772.7  176.57  4779.3  176.04  4793.5  173.12
  4801.3   172.7  4850.7   177.1  4879.2  175.45  4928.6  175.54  4935.2   174.5
  4957.2  174.54  4973.1 172.571  4983.9  169.64  5002.3  170.16  5008.1  171.38
  5013.6  171.13 5027.72 172.561  5075.8  173.17  5081.3  171.55  5098.3  171.26
  5132.5   173.5  5188.1  173.43  5210.3  177.97  5216.7  180.39  5433.5  185.66
#Mann= 3 , 0 , 0
  4445.3     .12       0  4973.1     .07       0 5027.72     .12       0
Bank Sta=4973.1,5027.72
XS Rating Curve= 0 ,0
Exp/Cntr=0.3,0.1

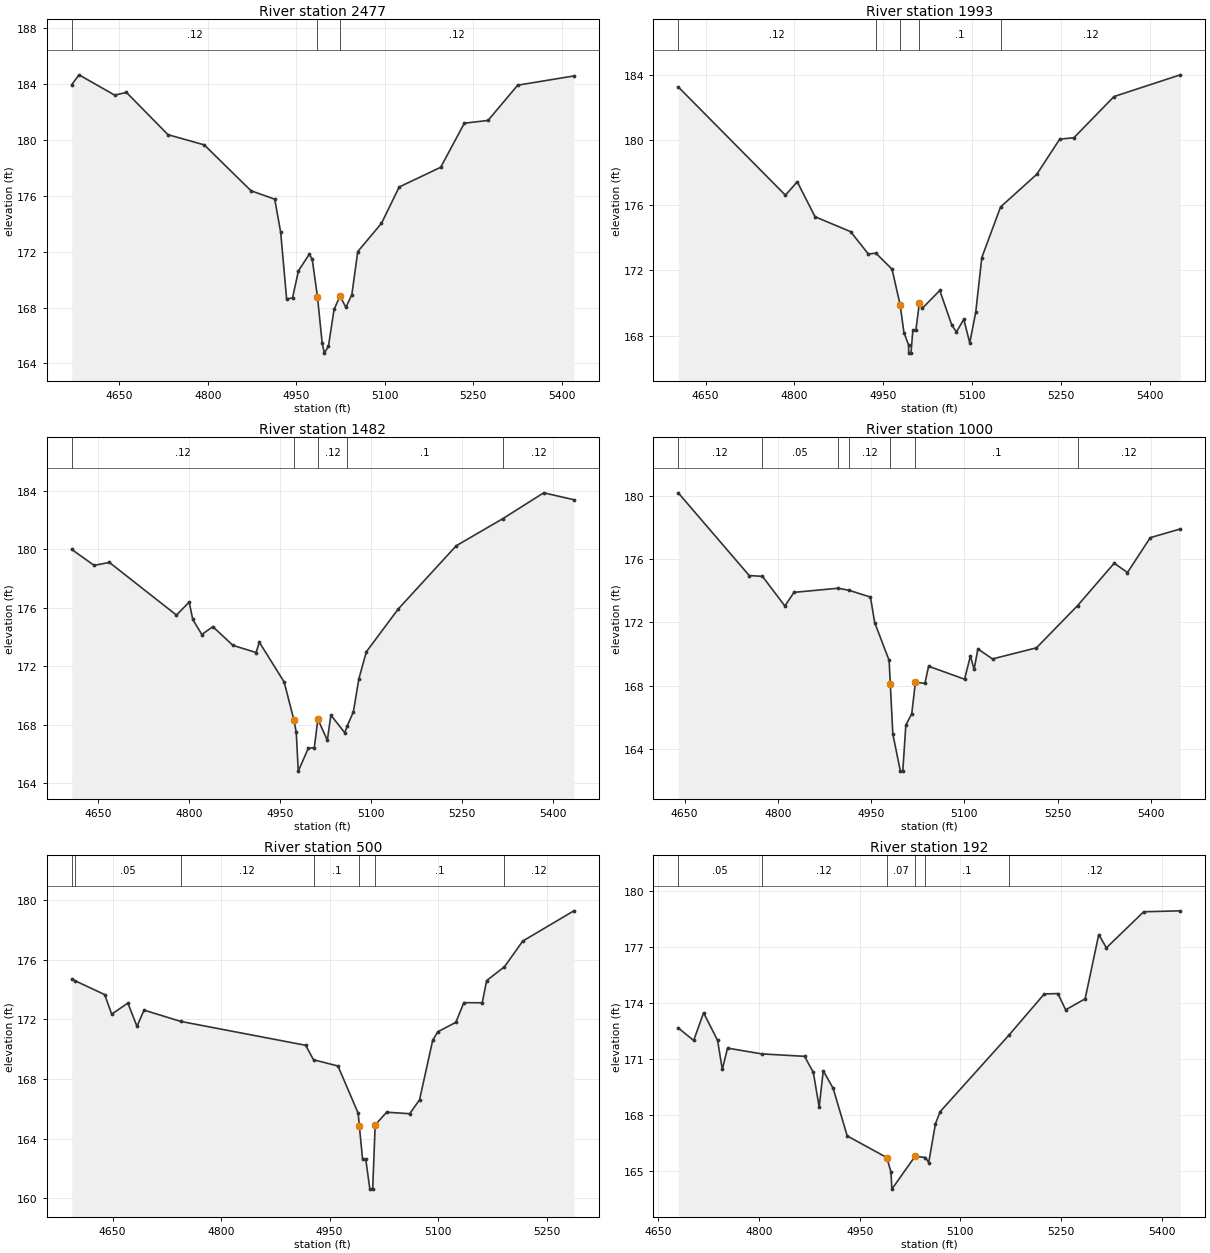
Type RM Length L Ch R = 1 ,2477    ,484,484,484
BEGIN DESCRIPTION:
WF OF CRYSTAL CREEK TRIB NO 1 5.0
END DESCRIPTION:
XS GIS Cut Line= 3
      3860326.71      10111503.3      3860280.16     10111074.92
      3860239.71     10110656.27
#Sta/Elev= 30
  4569.1  183.94  4581.4  184.64  4641.8  183.19  4661.9  183.38  4732.3  180.36
  4793.8  179.63  4873.1  176.35  4913.3  175.75  4923.4  173.38  4933.5  168.61
  4943.5  168.69  4953.6  170.63  4971.9  171.81  4976.9  171.45 4985.75 168.785
  4993.8  165.46  4997.5  164.74  5004.4  165.24  5013.9  167.86    5024  168.82
    5034  168.01  5044.1  168.92  5054.1     172  5094.3  174.02  5124.4  176.62
  5194.8  178.03  5234.9  181.18  5275.1  181.38  5325.4   183.9  5420.6  184.56
#Mann= 3 , 0 , 0
  4569.1     .12       0 4985.75     .07       0    5024     .12       0
Bank Sta=4985.75,5024
XS Rating Curve= 0 ,0
Exp/Cntr=0.3,0.1

Type RM Length L Ch R = 1 ,1993    ,511,511,511
BEGIN DESCRIPTION:
WF OF CRYSTAL CREEK TRIB NO 1 4.0
END DESCRIPTION:
XS GIS Cut Line= 3
      3860652.38     10111361.85      3860664.68     10110965.94
      3860594.86     10110519.97
#Sta/Elev= 30
  4603.9  183.24  4784.8  176.61  4804.8  177.43  4834.8  175.29  4894.8  174.38
  4924.8  173.01  4937.6  173.06  4964.8  172.08 4978.38 169.915  4984.9   168.2
  4992.7  167.44    4993  166.94  4996.8  166.94  4999.9  168.33    5005  168.33
  5010.9  170.01    5016  169.69  5045.4  170.78  5065.7  168.65  5073.6  168.24
  5085.9  169.01    5096  167.57  5106.1  169.45  5116.3  172.79    5148  175.89
  5209.1  177.89  5247.8  180.04  5271.8  180.13  5339.5  182.65  5451.4  183.98
#Mann= 5 ,-1 , 0
  4603.9     .12       0  4937.6      .1       0 4978.38     .07       0
  5010.9      .1       0    5148     .12       0
Bank Sta=4978.38,5010.9
XS Rating Curve= 0 ,0
Exp/Cntr=0.3,0.1

Type RM Length L Ch R = 1 ,1482    ,482,482,482
BEGIN DESCRIPTION:
WF OF CRYSTAL CREEK TRIB NO 1 3.0
END DESCRIPTION:
XS GIS Cut Line= 3
       3861030.4     10111226.34      3860917.46     10110850.02
      3860695.56     10110476.57
#Sta/Elev= 30
  4607.1  179.99  4643.9   178.9  4669.1   179.1  4779.6   175.5  4800.5  176.39
  4806.5   175.2  4821.4  174.17  4839.6  174.71  4872.6  173.43  4910.9  172.94
  4916.1  173.65  4957.1  170.92 4973.01 168.348    4977  167.49  4980.3  164.83
  4996.8  166.39  5006.8  166.44  5012.6  168.38  5028.2  166.94    5034  168.66
  5056.9  167.46  5061.2  167.94  5071.1  168.88  5080.2  171.15  5092.5  172.99
  5145.1  175.92  5240.6  180.24  5317.6   182.1  5384.7  183.86  5434.4  183.39
#Mann= 5 ,-1 , 0
  4607.1     .12       0 4973.01     .07       0  5012.6     .12       0
  5061.2      .1       0  5317.6     .12       0
Bank Sta=4973.01,5012.6
XS Rating Curve= 0 ,0
Exp/Cntr=0.3,0.1

Type RM Length L Ch R = 1 ,1000    ,500,500,500
BEGIN DESCRIPTION:
WF OF CRYSTAL CREEK TRIB NO 1 2.0
END DESCRIPTION:
XS GIS Cut Line= 3
      3861454.87     10110993.36      3861253.92     10110694.43
      3861017.45     10110314.62
#Sta/Elev= 30
  4639.8  180.17    4754  174.95  4775.3   174.9  4811.3  173.03    4826  173.89
  4896.9  174.15  4914.6  174.02    4949  173.59  4955.8  171.98    4979   169.6
  4980.9 168.128    4985  164.95  4997.1  162.61    5001  162.61  5005.9  165.51
  5015.4  166.23  5021.3  168.22  5036.6  168.15  5042.5  169.23  5100.4  168.41
  5109.8  169.88  5115.7  169.03  5121.8  170.32  5145.3  169.69    5216  170.39
  5282.3  173.06  5341.1  175.73  5362.4  175.14    5399  177.34  5447.4  177.89
#Mann= 7 ,-1 , 0
  4639.8     .12       0  4775.3     .05       0  4896.9      .1       0
  4914.6     .12       0  4980.9     .07       0  5021.3      .1       0
  5282.3     .12       0
Bank Sta=4980.9,5021.3
XS Rating Curve= 0 ,0
Exp/Cntr=0.3,0.1

Type RM Length L Ch R = 1 ,500     ,308,308,308
BEGIN DESCRIPTION:
Mapping XS 294d502d
END DESCRIPTION:
XS GIS Cut Line= 3
      3861748.49     10110552.67      3861385.07     10110370.56
       3861114.4     10110272.74
#Sta/Elev= 30
  4593.5   174.7  4598.5  174.58    4639  173.66  4648.7  172.35  4671.1  173.09
  4683.7  171.53  4693.4  172.62  4744.3  171.86  4916.9  170.26  4927.8  169.29
  4961.6  168.87  4989.5  165.71 4991.21 164.847  4995.6  162.63    5000  162.63
  5005.7  160.61  5009.6  160.61  5013.1  164.92  5028.9  165.77  5060.8  165.67
  5074.4   166.6  5092.7  170.61  5099.8  171.17  5124.6   171.8  5135.7  173.12
  5161.1  173.11  5167.2   174.6  5191.9  175.53  5217.1  177.25  5287.8  179.28
#Mann= 7 ,-1 , 0
  4593.5     .12       0  4598.5     .05       0  4744.3     .12       0
  4927.8      .1       0 4991.21     .07       0  5013.1      .1       0
  5191.9     .12       0
Bank Sta=4991.21,5013.1
XS Rating Curve= 0 ,0
Exp/Cntr=0.3,0.1

Type RM Length L Ch R = 1 ,192     ,0,0,0
BEGIN DESCRIPTION:
WF OF CRYSTAL CREEK TRIB NO 1 1.0
END DESCRIPTION:
XS GIS Cut Line= 3
      3861791.48     10110379.51        3861530.     10110194.18
      3861107.88     10110264.92
#Sta/Elev= 30
  4679.5  172.66  4702.5  171.99  4717.3  173.47  4738.2  171.99  4745.2  170.44
    4753  171.58    4804  171.27  4867.8  171.14  4880.9  170.28  4889.6  168.42
  4895.7  170.37  4910.5  169.42  4931.4  166.88  4990.4  165.72  4996.6  164.96
    4998  164.03  5032.6  165.79  5048.1  165.72  5052.9  165.45    5063  167.54
    5070  168.18  5172.4  172.27  5225.2  174.48  5245.5   174.5  5257.1  173.63
  5286.1  174.22  5306.4  177.66  5317.8  176.95  5373.4  178.88    5428  178.93
#Mann= 6 ,-1 , 0
  4679.5     .05       0    4804     .12       0  4990.4     .07       0
  5032.6     .12       0  5048.1      .1       0  5172.4     .12       0
Bank Sta=4990.4,5032.6
XS Rating Curve= 0 ,0
Exp/Cntr=0.3,0.1