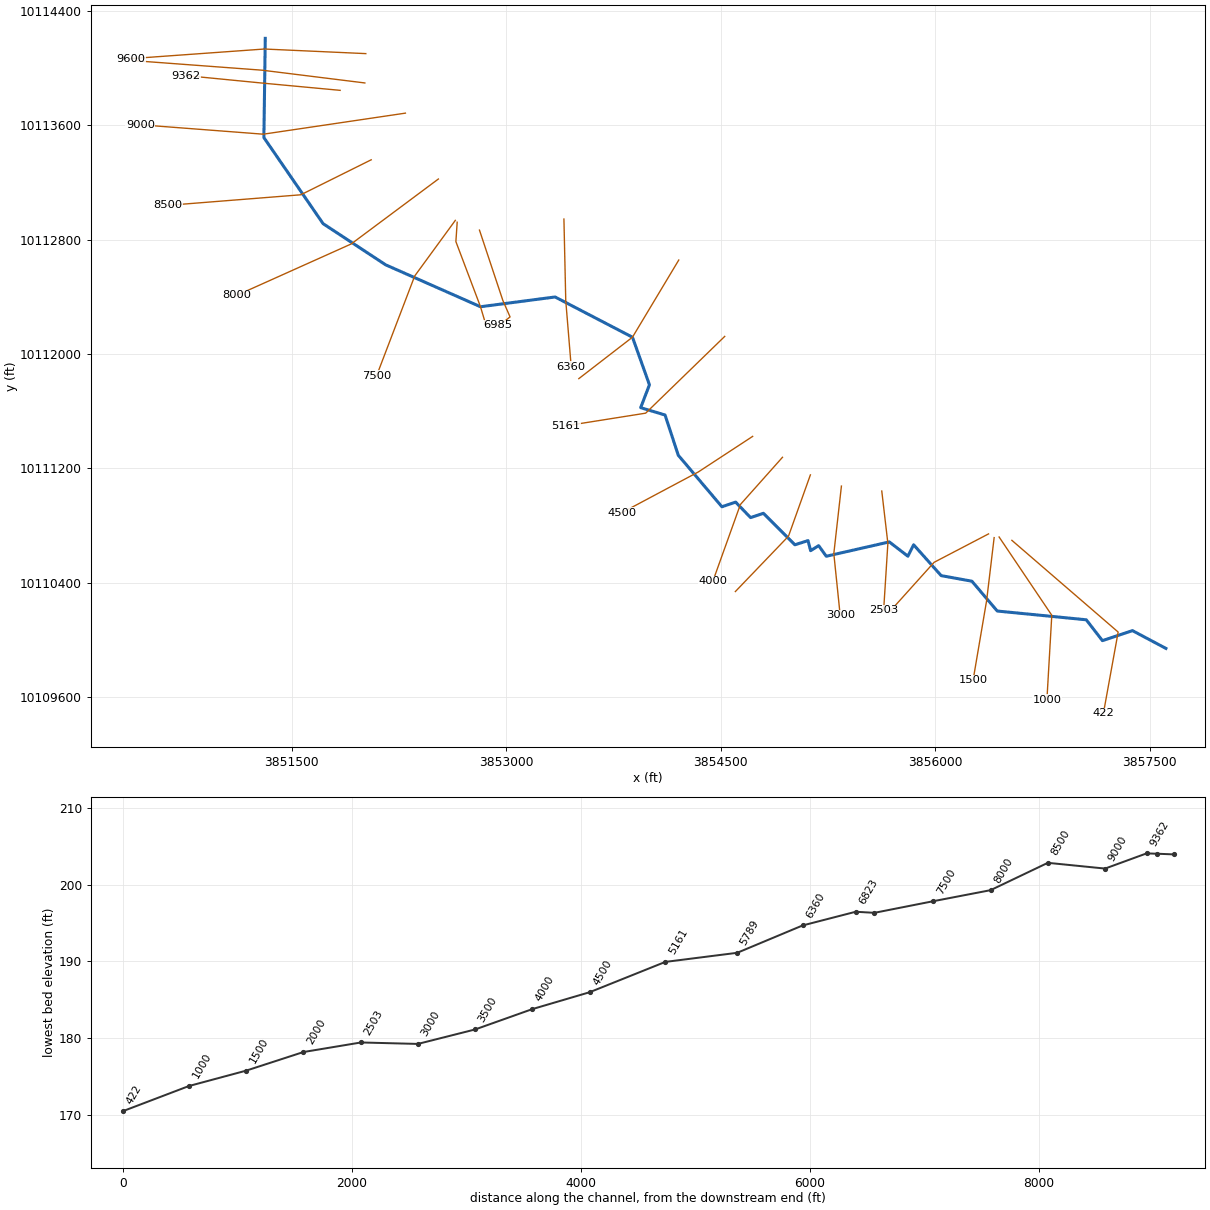
--- WF OF CRYSTAL CREEK TRIB NO 2.prj (project) ---

Proj Title=WF OF CRYSTAL CREEK TRIB NO 2 Base Level Engineering
Current Plan=p01
Default Exp/Contr=0.3,0.1
English Units
Geom File=g01
Flow File=f01
Plan File=p01
Y Axis Title=Elevation
X Axis Title(PF)=Main Channel Distance
X Axis Title(XS)=Station
BEGIN DESCRIPTION:
WF OF CRYSTAL CREEK TRIB NO 2
END DESCRIPTION:
DSS Export Rating Curves= 0
DSS Export Rating Curve Sorted= 0
DSS Export Volume Flow Curves= 0
DXF OffsetX= 0
DXF OffsetY= 0
DXF ScaleX= 1
DXF ScaleY= 10

--- WF OF CRYSTAL CREEK TRIB NO 2.p01 (plan) ---

Plan Title=Multiple Run
Short Identifier=Multiple
Geom File=g01
Flow File=f01
Subcritical Flow
K Sum by GR= 0
Std Step Tol= 0.01
Critical Tol= 0.01
Num of Std Step Trials= 20
Max Error Tol= 0.3
Flow Tol Ratio= 0.001
Split Flow NTrial= 30
Split Flow Tol= 0.02
Split Flow Ratio= 0.02
Log Output Level= 0
Friction Slope Method= 1
Unsteady Friction Slope Method= 2
Unsteady Bridges Friction Slope Method= 1
Parabolic Critical Depth
Global Vel Dist=  1 , 1 , 1
Global Log Level= 0
CheckData=True
Encroach Param= -1, 0, 0, 0
BEGIN DESCRIPTION:
Multiple Run
END DESCRIPTION:

--- WF OF CRYSTAL CREEK TRIB NO 2.f01 (steady flow) ---

Flow Title=Multiple
Program Version=4.10
Number of Profiles= 7
Profile Names=10-year,25-year,50-year,1pct_min,100-year,1pct_plu,500-year
River Rch & RM=WF OF CRYSTAL CR,Reach-1         ,9600
     362     454     581     244     737    2226    1228
River Rch & RM=WF OF CRYSTAL CR,Reach-1         ,6985
     691     913    1211     528    1594    4814    2850
Boundary for River Rch & Prof#=WF OF CRYSTAL CR,Reach-1         , 1
Up Type= 0
Dn Type= 3
Dn Slope=0.005
Boundary for River Rch & Prof#=WF OF CRYSTAL CR,Reach-1         , 2
Up Type= 0
Dn Type= 3
Dn Slope=0.005
Boundary for River Rch & Prof#=WF OF CRYSTAL CR,Reach-1         , 3
Up Type= 0
Dn Type= 3
Dn Slope=0.005
Boundary for River Rch & Prof#=WF OF CRYSTAL CR,Reach-1         , 4
Up Type= 0
Dn Type= 3
Dn Slope=0.005
Boundary for River Rch & Prof#=WF OF CRYSTAL CR,Reach-1         , 5
Up Type= 0
Dn Type= 3
Dn Slope=0.005
Boundary for River Rch & Prof#=WF OF CRYSTAL CR,Reach-1         , 6
Up Type= 0
Dn Type= 3
Dn Slope=0.005
Boundary for River Rch & Prof#=WF OF CRYSTAL CR,Reach-1         , 7
Up Type= 0
Dn Type= 3
Dn Slope=0.005
DSS Import GetInterval= 0
DSS Import GetPeak= 0
DSS Import FillOption= 0

--- WF OF CRYSTAL CREEK TRIB NO 2.g01 (geometry) ---

Geom Title=Existing Conditions
Program Version=4.10

River Reach=WF OF CRYSTAL CR,Reach-1
Reach XY= 30
      3851315.31     10114206.35      3851305.63     10113512.78
      3851719.51     10112911.16      3852157.01      10112623.4
      3852820.03     10112330.46      3853341.67      10112398.7
      3853882.51     10112117.51      3854001.26     10111784.83
      3853939.96     10111625.14      3854110.48     10111573.69
      3854202.78     10111292.65      3854507.93     10110932.46
      3854603.85     10110965.12      3854708.24     10110856.86
      3854798.24     10110886.86      3855018.24     10110666.86
      3855109.91     10110696.02      3855128.14      10110625.7
      3855184.13     10110660.86      3855237.51     10110586.64
      3855678.24     10110686.86      3855808.24     10110586.86
      3855848.24     10110666.86       3856040.9     10110451.22
      3856255.74     10110412.16      3856432.83     10110203.83
      3857055.22     10110142.63      3857168.24     10109996.86
      3857378.24     10110066.86      3857612.33      10109942.5

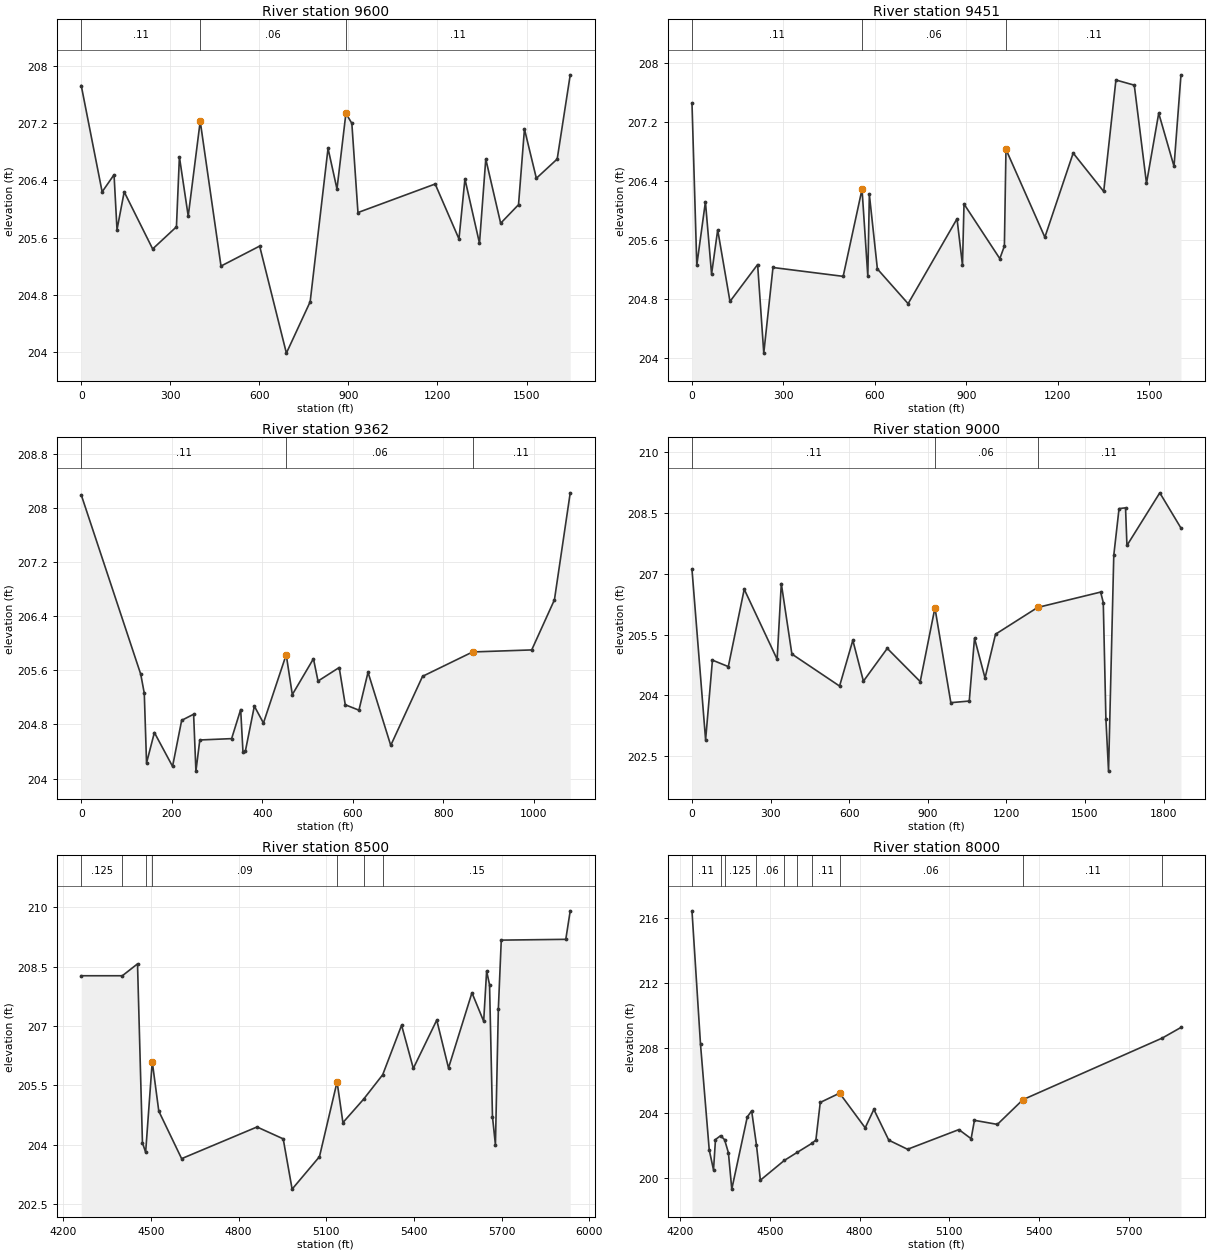
Type RM Length L Ch R = 1 ,9600    ,149,149,149
XS GIS Cut Line= 3
      3852018.21     10114099.56      3851308.58     10114131.69
      3850374.06      10114064.4
#Sta/Elev= 30
       0  207.73    70.4  206.24   110.5  206.48   120.5  205.71   144.7  206.24
   240.6  205.44   320.7  205.75   330.7  206.73   360.4   205.9   400.8  207.23
   470.8   205.2     601  205.48   691.1  203.98   771.2   204.7   831.4  206.85
   861.5  206.28   891.6  207.34   911.6   207.2   932.2  205.95  1192.3  206.35
  1272.5  205.58  1292.6  206.42  1341.6  205.52  1362.8   206.7  1412.9   205.8
  1473.1  206.06  1493.1  207.12  1533.2  206.43  1603.4   206.7  1647.3  207.88
#Mann= 3 , 0 , 0
       0     .11       0   400.8     .06       0   891.6     .11       0
Bank Sta=400.8,891.6
XS Rating Curve= 0 ,0
Exp/Cntr=0.3,0.1

Type RM Length L Ch R = 1 ,9451    ,90,90,90
XS GIS Cut Line= 3
      3852011.64     10113894.51      3851292.66     10113983.77
      3850415.07     10114048.99
#Sta/Elev= 30
       0  207.46    15.8  205.26    44.1  206.12    64.3  205.14    84.4  205.74
   124.7  204.77   215.4  205.27   235.6  204.07   265.8  205.23   496.1  205.11
     558  206.29     577  205.11     582  206.22   608.4  205.21   709.2  204.74
   869.7  205.89   887.6  205.26   892.6  206.09  1010.1  205.35  1025.1  205.52
  1030.3  206.83  1157.9  205.64  1250.8  206.78    1351  206.26  1391.1  207.77
  1451.3   207.7  1491.4  206.37  1531.5  207.32  1581.7   206.6  1604.5  207.84
#Mann= 3 , 0 , 0
       0     .11       0     558     .06       0  1030.3     .11       0
Bank Sta=558,1030.3
XS Rating Curve= 0 ,0
Exp/Cntr=0.3,0.1

Type RM Length L Ch R = 1 ,9362    ,362,362,362
XS GIS Cut Line= 3
      3851838.74     10113842.85      3851287.22     10113894.35
      3850763.18     10113945.62
#Sta/Elev= 30
       0  208.19   131.5  205.54   139.3  205.26   144.3  204.23   161.6  204.68
   201.8  204.18   221.9  204.86   248.3  204.95   253.4  204.11     262  204.57
   332.3  204.59   352.3  205.02   357.4  204.39   362.5   204.4   382.5  205.07
   402.6  204.82   452.9  205.83   466.4  205.24   513.1  205.77   523.2  205.44
     570  205.64   583.4  205.09   613.6  205.01   633.7  205.57   683.9  204.49
   754.2  205.51   864.8  205.87   995.4   205.9  1045.6  206.64  1080.5  208.22
#Mann= 3 , 0 , 0
       0     .11       0   452.9     .06       0   864.8     .11       0
Bank Sta=452.9,864.8
XS Rating Curve= 0 ,0
Exp/Cntr=0.3,0.1

Type RM Length L Ch R = 1 ,9000    ,500,500,500
XS GIS Cut Line= 3
      3852295.09     10113683.56      3851301.26     10113536.43
      3850441.56      10113602.3
#Sta/Elev= 30
       0  207.11      52   202.9    78.1  204.87   138.7  204.71   199.4  206.62
     325  204.89   340.9  206.76   381.3  205.02   563.3  204.23   613.9  205.36
   654.3  204.35   745.3  205.16   871.1  204.34   927.2  206.16   987.9  203.82
  1058.2  203.86  1078.3  205.41  1118.4  204.43  1158.5  205.51    1319  206.17
  1559.7  206.55  1569.7  206.29  1579.7  203.42  1589.8  202.13  1609.8  207.46
  1629.9  208.61  1654.7  208.63    1660   207.7  1785.4     209  1866.2  208.13
#Mann= 3 , 0 , 0
       0     .11       0   927.2     .06       0    1319     .11       0
Bank Sta=927.2,1319
XS Rating Curve= 0 ,0
Exp/Cntr=0.3,0.1

Type RM Length L Ch R = 1 ,8500    ,500,500,500
BEGIN DESCRIPTION:
WF OF CRYSTAL CREEK TRIB NO 2 17.0
END DESCRIPTION:
XS GIS Cut Line= 3
      3852056.06     10113357.54      3851563.98     10113112.97
      3850632.72     10113038.95
#Sta/Elev= 30
  4261.4  208.27    4402  208.27  4453.9  208.57  4470.8  204.05  4481.7  203.81
  4504.3   206.1  4526.7  204.85  4604.8  203.65  4862.7  204.45  4952.3  204.15
  4982.8  202.88  5076.4   203.7  5136.6  205.59  5156.6  204.56  5227.1  205.15
  5292.7  205.77  5357.3  207.02  5397.4  205.93  5477.6  207.15  5517.8  205.94
    5598  207.84  5638.1  207.12  5648.2  208.39  5658.2  208.04  5668.2  204.71
  5678.3     204  5688.3  207.43  5698.3  209.17    5919  209.19  5934.2  209.91
#Mann= 7 ,-1 , 0
  4261.4    .125       0    4402     .15       0  4481.7     .11       0
  4504.3     .09       0  5136.6     .17       0  5227.1     .11       0
  5292.7     .15       0
Bank Sta=4504.3,5136.6
XS Rating Curve= 0 ,0
Exp/Cntr=0.3,0.1

Type RM Length L Ch R = 1 ,8000    ,500,500,500
BEGIN DESCRIPTION:
WF OF CRYSTAL CREEK TRIB NO 2 16.0
END DESCRIPTION:
XS GIS Cut Line= 3
      3852525.56     10113223.21      3851915.77      10112769.1
      3851117.82     10112411.06
#Sta/Elev= 30
  4239.7  216.42  4268.2  208.22  4297.4  201.72  4311.7  200.49  4318.3  202.36
  4335.4202.5955  4348.6202.3516  4361.5  201.55  4372.8  199.31  4424.6  203.75
  4439.2  204.12  4455.2202.0359  4468.4  199.86  4548.4201.0744  4591.6201.5701
  4641.4202.1338    4654  202.33  4668.6  204.64  4733.3  205.21  4818.8  203.08
  4847.8  204.21  4897.7  202.32  4960.5  201.76  5132.1  202.97    5173  202.41
  5184.1  203.54  5260.8  203.29  5346.2  204.81  5812.3   208.6  5874.6  209.25
#Mann= 10 ,-1 , 0
  4239.7     .11       0  4335.4     .11       0  4348.6    .125       0
  4455.2     .06       0  4548.4     .11       0  4591.6    .125       0
  4641.4     .11       0  4733.3     .06       0  5346.2     .11       0
  5812.3    .125       0
Bank Sta=4733.3,5346.2
XS Rating Curve= 0 ,0
Exp/Cntr=0.3,0.1

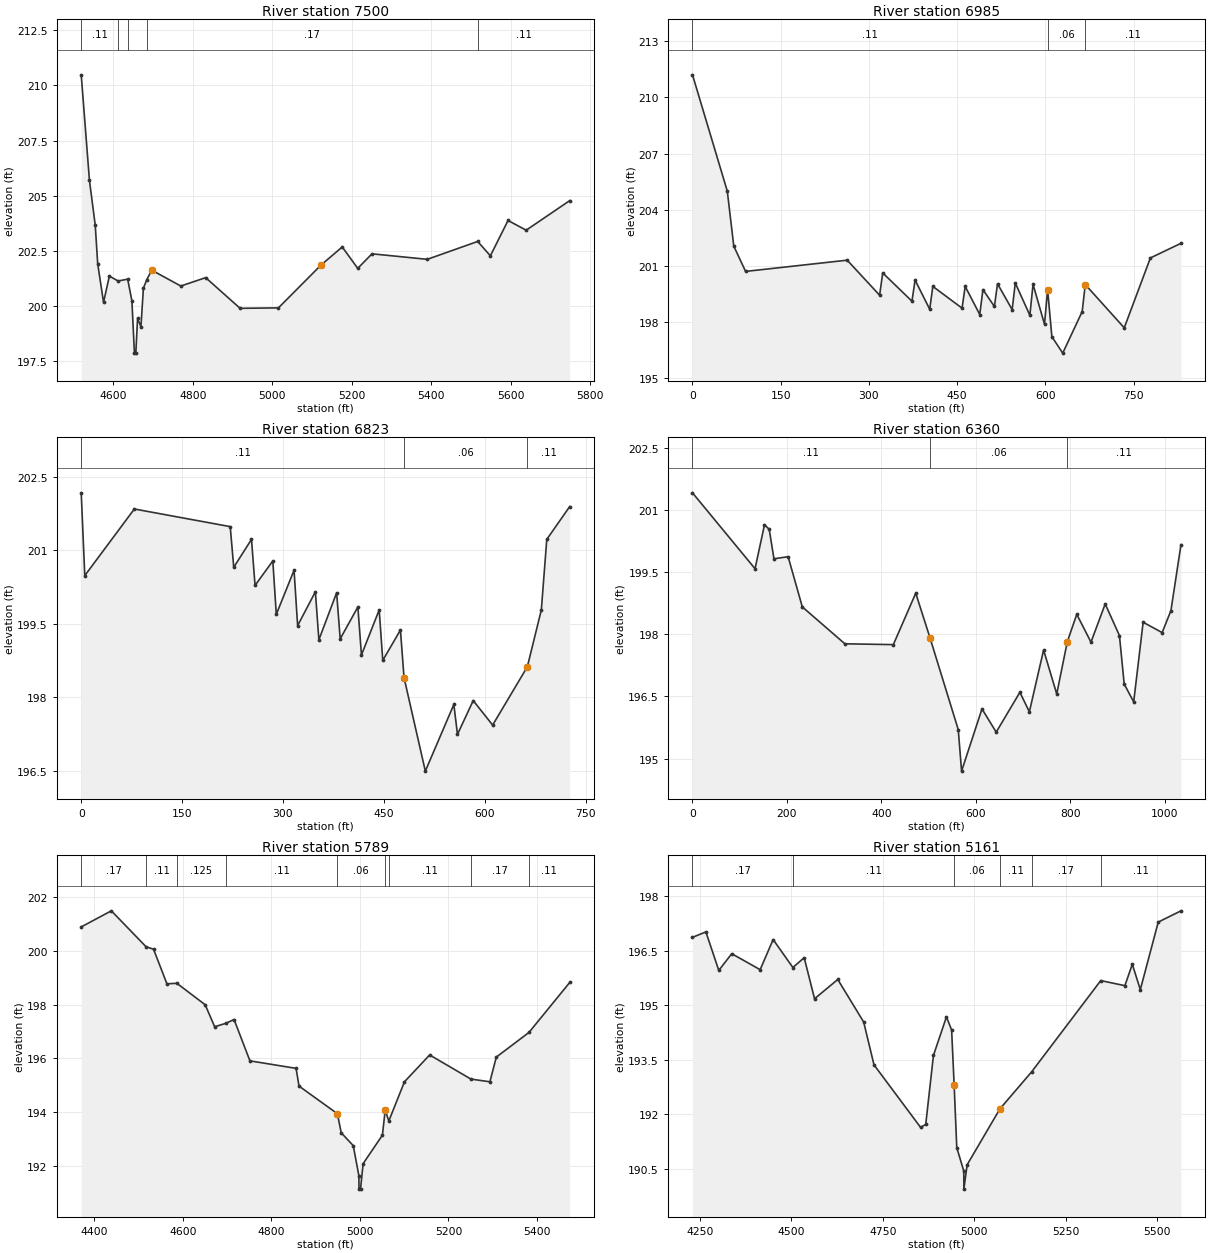
Type RM Length L Ch R = 1 ,7500    ,515,515,515
BEGIN DESCRIPTION:
WF OF CRYSTAL CREEK TRIB NO 2 15.0
END DESCRIPTION:
XS GIS Cut Line= 3
      3852644.05     10112934.13      3852360.18     10112545.57
      3852092.85     10111846.01
#Sta/Elev= 30
  4518.8  210.48  4539.5   205.7  4554.1  203.67  4560.3  201.92    4575  200.17
  4589.7  201.36  4611.7201.1386  4635.8201.2208  4646.4  200.24  4652.8  197.87
  4656.3  197.87  4660.7  199.44  4669.2  199.07  4675.4  200.81    4684201.2006
  4696.3  201.63  4769.6  200.91  4832.2  201.29  4918.9   199.9  5015.4  199.92
  5122.6  201.86  5176.1  202.68  5215.1  201.71    5251  202.37  5390.2  202.12
  5517.2  202.93  5549.1  202.28  5593.6  203.88  5639.3  203.44  5748.9  204.78
#Mann= 5 ,-1 , 0
  4518.8     .11       0  4611.7     .11       0  4635.8     .09       0
    4684     .17       0  5517.2     .11       0
Bank Sta=4696.3,5122.6
XS Rating Curve= 0 ,0
Exp/Cntr=0.3,0.1

Type RM Length L Ch R = 1 ,6985    ,163,163,163
XS GIS Cut Line= 5
       3852657.1     10112921.14      3852647.98     10112785.72
      3852820.03     10112330.46      3852855.45     10112212.05
      3852939.33     10112200.37
#Sta/Elev= 30
       0   211.2    59.2  204.99    70.2  202.06    90.3  200.71   263.1  201.31
   318.2  199.44   323.5  200.63   373.2  199.12   378.5  200.25   403.4  198.69
   408.7  199.91   458.4  198.75   463.7  199.91   488.5  198.41   493.9  199.74
   513.4  198.84   518.7  200.05   543.6  198.67   548.9  200.09   573.7  198.37
   579.1  200.02   598.6  197.89   603.9  199.74   611.1  197.23   629.6  196.35
   662.7  198.57   667.9  200.01   734.2   197.7   778.7  201.43   830.7  202.21
#Mann= 3 , 0 , 0
       0     .11       0   603.9     .06       0   667.9     .11       0
Bank Sta=603.9,667.9
XS Rating Curve= 0 ,0
Exp/Cntr=0.3,0.1

Type RM Length L Ch R = 1 ,6823    ,464,464,464
XS GIS Cut Line= 4
      3852812.83     10112866.06      3852976.28     10112374.73
       3853026.8     10112259.46       3852960.5     10112207.55
#Sta/Elev= 30
       0  202.17     5.3  200.48      79  201.84   221.6  201.48   226.8  200.65
   253.2  201.22   258.5  200.28   284.9  200.78   290.1  199.69   316.5  200.59
   321.8  199.46   348.2  200.15   353.4  199.17   379.8  200.13   385.1  199.19
   411.4  199.84   416.7  198.86   443.1  199.78   448.4  198.75   474.7  199.37
     480   198.4   511.7  196.49   554.1  197.85   559.5  197.24   582.9  197.93
   611.8  197.43   663.4  198.62   684.2  199.78   692.3  201.22   726.4  201.89
#Mann= 3 , 0 , 0
       0     .11       0     480     .06       0   663.4     .11       0
Bank Sta=480,663.4
XS Rating Curve= 0 ,0
Exp/Cntr=0.3,0.1

Type RM Length L Ch R = 1 ,6360    ,571,571,571
XS GIS Cut Line= 3
      3853403.36     10112943.45      3853416.19     10112372.19
       3853454.3     10111911.26
#Sta/Elev= 30
       0  201.41   132.4  199.58   152.4  200.64   162.4  200.53   172.4  199.82
   202.4  199.87   232.4  198.66   322.5  197.77   425.1  197.75   472.5  198.99
   502.5  197.92   562.5   195.7   569.5   194.7   612.7   196.2   642.8  195.64
   692.9   196.6     713  196.13   743.1  197.62   770.9  196.56   793.3  197.82
   813.3  198.48   843.4  197.81   873.5  198.73   903.6  197.97   913.7   196.8
   933.8  196.37   953.8  198.29     994  198.04  1012.6  198.57  1033.9  200.16
#Mann= 3 , 0 , 0
       0     .11       0   502.5     .06       0   793.3     .11       0
Bank Sta=502.5,793.3
XS Rating Curve= 0 ,0
Exp/Cntr=0.3,0.1

Type RM Length L Ch R = 1 ,5789    ,628,628,628
BEGIN DESCRIPTION:
WF OF CRYSTAL CREEK TRIB NO 2 11.0
END DESCRIPTION:
XS GIS Cut Line= 3
      3854206.32       10112657.      3853882.51     10112117.51
      3853507.56     10111828.02
#Sta/Elev= 30
  4370.8   200.9  4438.8   201.5  4517.3  200.16  4534.1  200.07  4564.3  198.78
  4586.7   198.8  4650.7     198  4672.1  197.18  4697.6  197.31  4715.9  197.45
  4751.7  195.91  4855.9  195.63  4862.5  194.97  4949.2  193.94  4957.8  193.23
    4985  192.75  4997.7  191.63  4997.9  191.13  5001.4  191.13  5007.3  192.08
  5050.8  193.14  5057.1  194.07  5065.3  193.67  5100.6  195.13  5157.5  196.13
  5250.7  195.23  5293.5  195.13    5308  196.05  5381.8  196.97  5473.7  198.83
#Mann= 9 ,-1 , 0
  4370.8     .17       0  4517.3     .11       0  4586.7    .125       0
  4697.6     .11       0  4949.2     .06       0  5057.1     .08       0
  5065.3     .11       0  5250.7     .17       0  5381.8     .11       0
Bank Sta=4949.2,5057.1
XS Rating Curve= 0 ,0
Exp/Cntr=0.3,0.1

Type RM Length L Ch R = 1 ,5161    ,661,661,661
BEGIN DESCRIPTION:
WF OF CRYSTAL CREEK TRIB NO 2 10.0
END DESCRIPTION:
XS GIS Cut Line= 3
      3854527.49     10112123.13       3853974.8     10111586.71
      3853416.38     10111498.13
#Sta/Elev= 30
  4229.8  196.87  4266.4  197.02  4301.7  195.96  4337.1  196.42  4414.8  195.98
  4450.3  196.81  4504.2  196.04  4535.2  196.31  4563.5  195.18    4627  195.71
  4697.8  194.54  4726.1  193.36  4853.4  191.64  4867.5  191.72  4888.6  193.62
  4924.1  194.68  4938.3  194.32  4945.2   192.8  4952.4  191.08  4971.5  190.44
  4971.8  189.94  4980.7  190.61  5070.4  192.15  5157.2  193.17    5346  195.68
    5412  195.54  5432.3  196.13  5454.2  195.43  5503.2  197.29  5565.4   197.6
#Mann= 6 ,-1 , 0
  4229.8     .17       0  4504.2     .11       0  4945.2     .06       0
  5070.4     .11       0  5157.2     .17       0    5346     .11       0
Bank Sta=4945.2,5070.4
XS Rating Curve= 0 ,0
Exp/Cntr=0.3,0.1

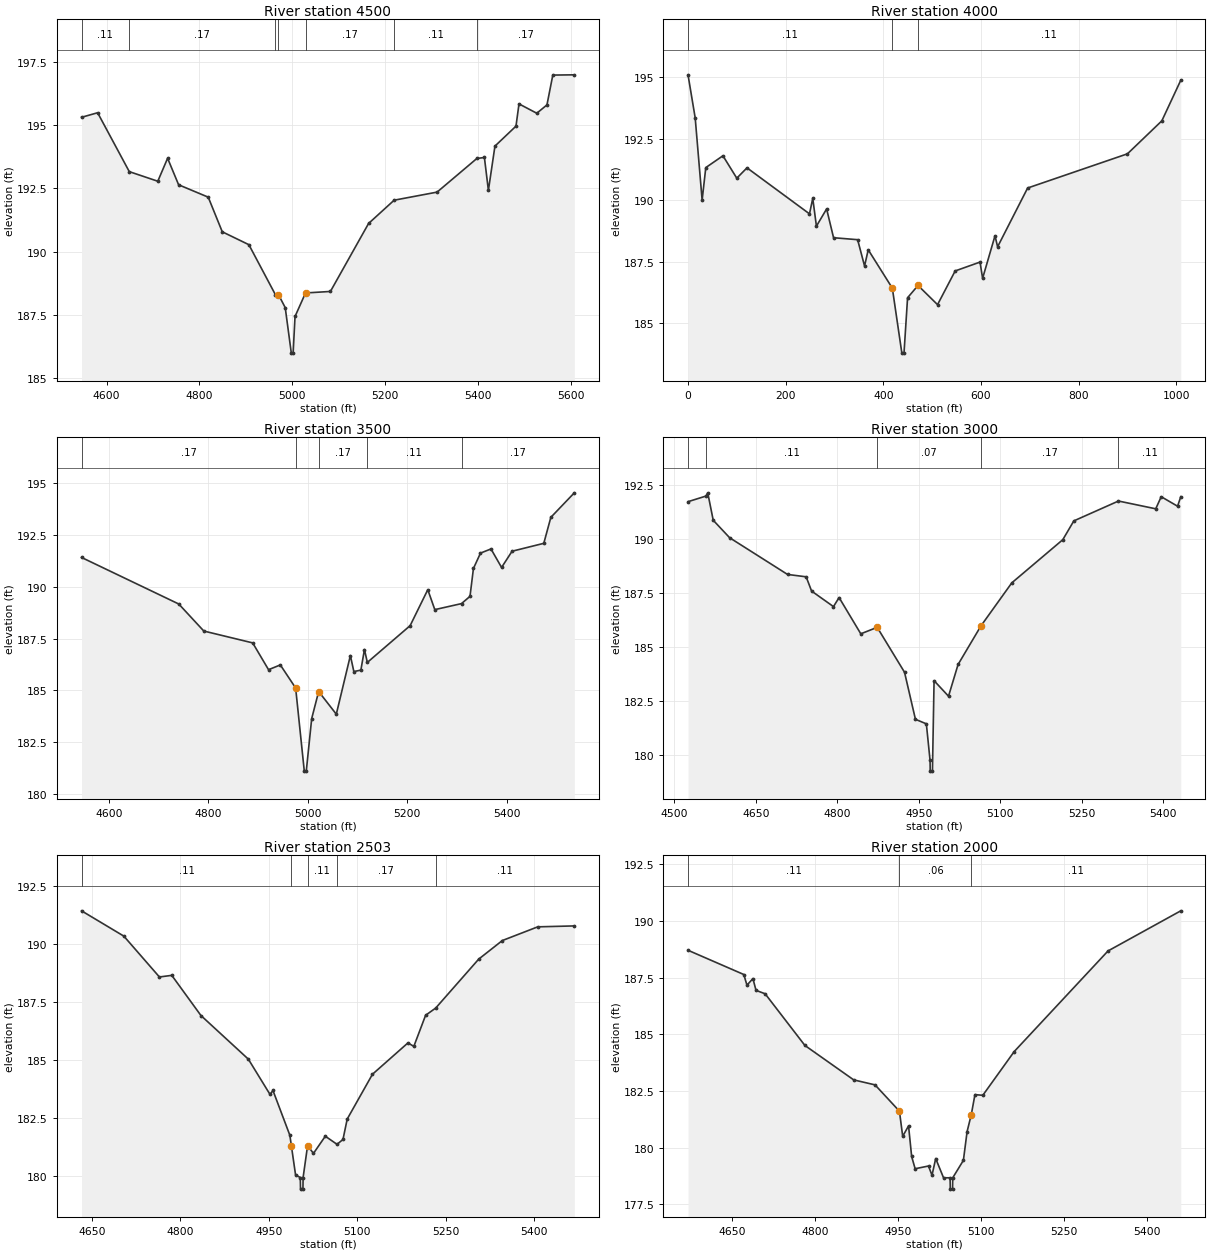
Type RM Length L Ch R = 1 ,4500    ,500,500,500
BEGIN DESCRIPTION:
WF OF CRYSTAL CREEK TRIB NO 2 9.0
END DESCRIPTION:
XS GIS Cut Line= 3
      3854722.78     10111424.33      3854342.96     10111175.82
      3853806.98     10110890.48
#Sta/Elev= 30
  4546.1  195.31  4580.7  195.49  4648.9  193.16  4710.3  192.78  4731.4  193.69
  4755.1  192.64  4818.9  192.15  4849.1  190.78  4906.4  190.27  4963.6  188.29
  4970.2  188.29  4984.7  187.78  4997.8  185.98  5001.7  185.98  5005.8  187.43
  5028.4  188.36    5082  188.42  5164.2  191.11  5219.2  192.03  5311.7  192.35
  5397.3  193.68  5413.6  193.72  5422.2  192.42  5436.3  194.17  5481.6  194.96
  5488.1  195.84  5526.4  195.47  5548.3   195.8  5560.9  196.98  5607.2  196.99
#Mann= 7 ,-1 , 0
  4546.1     .11       0  4648.9     .17       0  4963.6     .12       0
  4970.2     .09       0  5028.4     .17       0  5219.2     .11       0
  5397.3     .17       0
Bank Sta=4970.2,5028.4
XS Rating Curve= 0 ,0
Exp/Cntr=0.3,0.1

Type RM Length L Ch R = 1 ,4000    ,500,500,500
XS GIS Cut Line= 3
      3854931.43     10111278.34      3854637.02     10110948.08
      3854445.03     10110413.06
#Sta/Elev= 30
       0  195.09    14.7  193.34    28.9     190    36.4  191.32    71.5   191.8
    99.9  190.89   120.8  191.31   248.8  189.44   255.5  190.07     263  188.94
   283.9  189.64   298.1  188.47   347.4  188.39   361.6  187.32   369.1  187.98
   418.5  186.42     438  183.78   442.4  183.78   449.7  186.03   471.1  186.53
   511.1  185.75   547.2  187.12   598.1  187.48   603.4  186.82   628.8  188.55
   634.1   188.1   695.6  190.49   900.1  191.88   970.5  193.22  1009.3  194.87
#Mann= 3 , 0 , 0
       0     .11       0   418.5     .09       0   471.1     .11       0
Bank Sta=418.5,471.1
XS Rating Curve= 0 ,0
Exp/Cntr=0.3,0.1

Type RM Length L Ch R = 1 ,3500    ,500,500,500
BEGIN DESCRIPTION:
WF OF CRYSTAL CREEK TRIB NO 2 7.0
END DESCRIPTION:
XS GIS Cut Line= 3
      3855126.45     10111155.24      3854973.38     10110726.86
      3854602.03     10110340.07
#Sta/Elev= 30
  4545.1   191.4  4740.7  189.16    4791  187.86  4889.3  187.29  4921.2     186
  4944.9  186.23  4975.7  185.12  4993.1  181.12  4997.1  181.12    5008  183.65
    5022  184.95  5057.5  183.86  5085.8  186.68  5092.8  185.91  5106.9  185.98
  5114.1  186.97  5119.9  186.35    5206  188.12  5241.5  189.85  5255.6  188.89
  5309.3  189.18  5326.4  189.53  5333.3  190.87  5347.5  191.61  5368.6  191.81
  5389.9  190.92    5411   191.7  5474.8  192.08    5489  193.33  5536.2  194.51
#Mann= 5 ,-1 , 0
  4545.1     .17       0  4975.7     .09       0    5022     .17       0
  5119.9     .11       0  5309.3     .17       0
Bank Sta=4975.7,5022
XS Rating Curve= 0 ,0
Exp/Cntr=0.3,0.1

Type RM Length L Ch R = 1 ,3000    ,497,497,497
BEGIN DESCRIPTION:
WF OF CRYSTAL CREEK TRIB NO 2 6.0
END DESCRIPTION:
XS GIS Cut Line= 3
      3855343.47     10111077.16      3855290.27     10110605.05
      3855334.69     10110175.24
#Sta/Elev= 30
  4524.9  191.71  4557.9  191.97  4561.2  192.12  4571.3  190.85  4601.5  190.04
  4708.1  188.34  4742.4  188.23  4752.4  187.57  4792.7  186.85    4803  187.27
    4843  185.59  4873.2  185.89  4923.5  183.81  4943.6  181.63  4963.7  181.42
  4970.5  179.73  4970.8  179.23  4974.9  179.23  4977.9  183.42  5004.5   182.7
  5022.1  184.17  5064.3  185.96    5121  187.95  5214.9  189.95  5235.2  190.82
  5317.4  191.74    5386  191.38  5396.1  191.94  5426.2   191.5  5432.1  191.94
#Mann= 5 ,-1 , 0
  4524.9     .17       0  4557.9     .11       0  4873.2     .07       0
  5064.3     .17       0  5317.4     .11       0
Bank Sta=4873.2,5064.3
XS Rating Curve= 0 ,0
Exp/Cntr=0.3,0.1

Type RM Length L Ch R = 1 ,2503    ,503,503,503
BEGIN DESCRIPTION:
WF OF CRYSTAL CREEK TRIB NO 2 5.0
END DESCRIPTION:
XS GIS Cut Line= 3
      3855625.59     10111042.38      3855668.24     10110676.86
      3855638.61      10110209.1
#Sta/Elev= 30
    4632  191.41  4703.8  190.32  4764.2  188.56  4785.2  188.63  4834.7   186.9
  4915.2  185.02    4952   183.5    4957  183.67  4985.7  181.74 4988.41181.2623
  4995.4  180.03  5003.4  179.92  5003.8  179.42  5007.9  179.42  5008.2  179.92
  5015.8  181.29  5025.8  180.96  5045.9   181.7  5065.8  181.35  5075.9  181.56
  5083.1  182.44    5126  184.37  5186.2  185.72  5196.2  185.57  5216.2  186.91
  5233.3  187.22  5306.4  189.33  5346.5  190.13  5406.6  190.72  5468.7  190.76
#Mann= 5 ,-1 , 0
    4632     .11       0 4988.41     .06       0  5015.8     .11       0
  5065.8     .17       0  5233.3     .11       0
Bank Sta=4988.41,5015.8
XS Rating Curve= 0 ,0
Exp/Cntr=0.3,0.1

Type RM Length L Ch R = 1 ,2000    ,500,500,500
BEGIN DESCRIPTION:
WF OF CRYSTAL CREEK TRIB NO 2 4.0
END DESCRIPTION:
XS GIS Cut Line= 3
      3856372.07      10110742.9      3855991.29     10110544.23
      3855682.45     10110200.89
#Sta/Elev= 30
  4570.5  188.71  4671.4  187.64  4677.1  187.17  4687.9  187.46  4693.5  186.94
    4710  186.79  4781.9  184.51  4870.2  182.99  4908.8  182.77  4952.9  181.61
  4958.8   180.5  4969.4  180.96    4975  179.61  4981.3  179.07  5005.5  179.19
  5011.8  178.78  5018.5  179.52  5032.7  178.67  5044.5  178.67  5044.9  178.17
    5049  178.17  5049.3  178.67  5068.6  179.44  5075.3  180.71  5082.8  181.45
  5089.5  182.34  5103.7  182.31  5160.5  184.24  5330.2  188.68  5461.8  190.45
#Mann= 3 , 0 , 0
  4570.5     .11       0  4952.9     .06       0  5082.8     .11       0
Bank Sta=4952.9,5082.8
XS Rating Curve= 0 ,0
Exp/Cntr=0.3,0.1

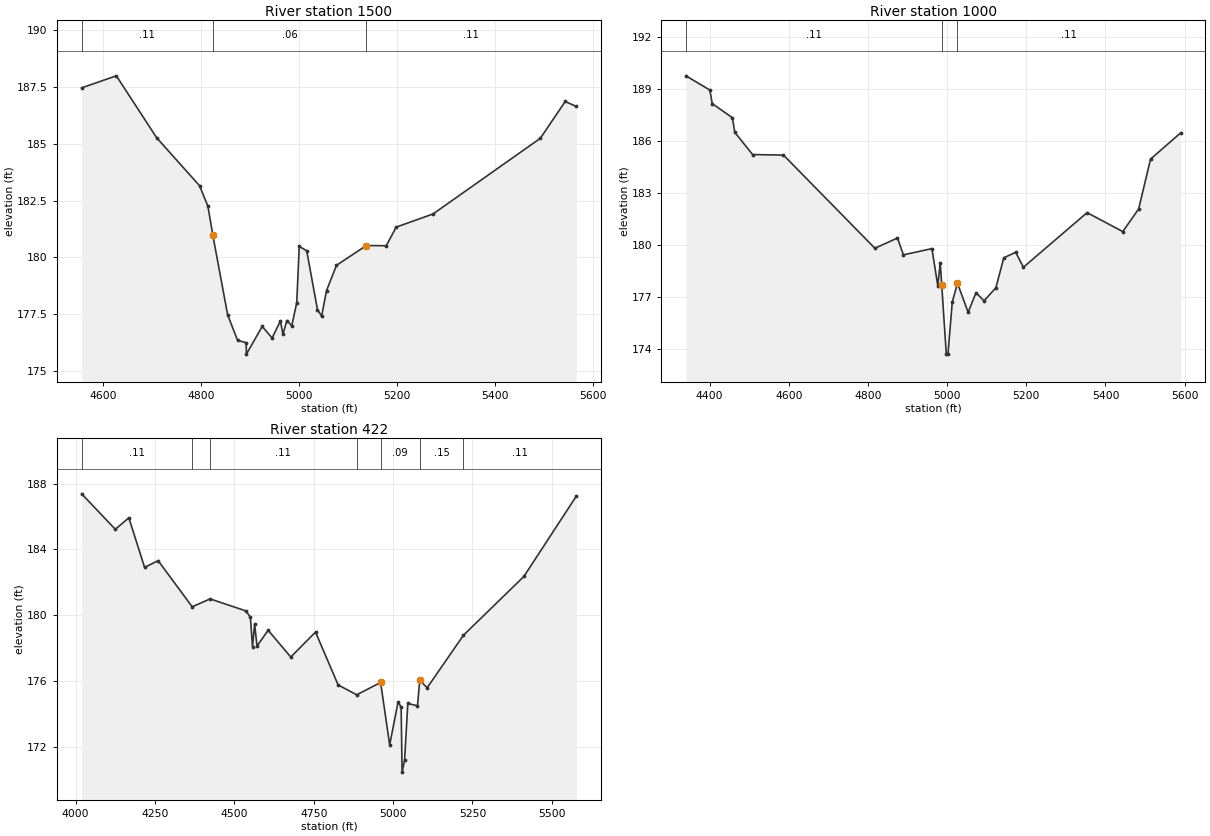
Type RM Length L Ch R = 1 ,1500    ,500,500,500
BEGIN DESCRIPTION:
WF OF CRYSTAL CREEK TRIB NO 2 3.0
END DESCRIPTION:
XS GIS Cut Line= 3
      3856411.18      10110716.9      3856358.54     10110276.03
      3856263.61     10109718.65
#Sta/Elev= 30
    4556  187.46  4626.8  187.99  4709.2  185.26  4796.7  183.15  4813.6  182.25
  4823.7  180.97  4853.9  177.47  4874.1  176.35  4891.8  176.24  4892.2  175.74
  4924.4  176.96  4944.6  176.45  4961.6   177.2  4966.7  176.61  4974.8  177.22
  4984.8  176.99  4994.9  178.01    5000  180.48  5015.2  180.29  5037.2   177.7
  5045.6  177.41  5055.7  178.54    5076  179.65  5136.9  180.52  5177.5  180.51
  5197.8  181.33    5273  181.91  5491.9  185.24  5542.7  186.86  5565.4  186.64
#Mann= 3 , 0 , 0
    4556     .11       0  4823.7     .06       0  5136.9     .11       0
Bank Sta=4823.7,5136.9
XS Rating Curve= 0 ,0
Exp/Cntr=0.3,0.1

Type RM Length L Ch R = 1 ,1000    ,578,578,578
BEGIN DESCRIPTION:
WF OF CRYSTAL CREEK TRIB NO 2 2.0
END DESCRIPTION:
XS GIS Cut Line= 3
      3856445.89     10110721.23      3856814.25     10110174.07
      3856780.15     10109585.06
#Sta/Elev= 30
  4340.4  189.74  4400.7  188.92  4406.7  188.14  4457.7  187.33  4463.7  186.49
  4508.7  185.21  4586.7  185.18  4817.6  179.82  4874.6  180.41  4889.6  179.44
  4961.6   179.8  4976.5  177.67  4982.6  178.99 4986.42177.7196  4997.9  173.73
  5002.2  173.73    5013  176.72  5026.1  177.81  5053.1  176.14  5073.1  177.27
  5093.2  176.79  5123.2  177.55  5143.2  179.27  5173.3  179.59  5192.8  178.73
  5353.6  181.87  5443.7  180.78  5483.8  182.08  5513.9  184.95    5590  186.46
#Mann= 3 , 0 , 0
  4340.4     .11       0 4986.42     .09       0  5026.1     .11       0
Bank Sta=4986.42,5026.1
XS Rating Curve= 0 ,0
Exp/Cntr=0.3,0.1

Type RM Length L Ch R = 1 ,422     ,0,0,0
BEGIN DESCRIPTION:
WF OF CRYSTAL CREEK TRIB NO 2 1.0
END DESCRIPTION:
XS GIS Cut Line= 3
       3856535.3     10110697.79      3857278.24     10110056.86
      3857175.06     10109488.55
#Sta/Elev= 30
  4018.8  187.39  4124.9  185.23  4167.5  185.93  4217.1  182.91  4259.8  183.32
  4367.1  180.51  4423.5  180.99  4536.3  180.26  4550.5  179.87  4557.2  178.09
  4563.8  179.46  4571.4  178.12  4606.5  179.08  4677.8  177.45  4755.7  178.97
    4827  175.75  4885.5  175.15  4960.9   175.9  4989.4   172.1    5016  174.73
  5025.6  174.39  5028.5  170.44  5036.4  171.16  5046.5  174.62    5077  174.48
  5084.1  176.03  5107.5  175.58    5222  178.78  5412.4  182.36  5577.6  187.25
#Mann= 7 ,-1 , 0
  4018.8     .11       0  4367.1     .17       0  4423.5     .11       0
  4885.5     .15       0  4960.9     .09       0  5084.1     .15       0
    5222     .11       0
Bank Sta=4960.9,5084.1
XS Rating Curve= 0 ,0
Exp/Cntr=0.3,0.1

Chan Stop Cuts=-1
Use User Specified Reach Order=0
Composite Channel Slope=5

--- WF OF CRYSTAL CREEK TRIB NO 2.g10 (geometry) ---

Geom Title=Existing Conditions
Program Version=4.10

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
River Reach=WF OF CRYSTAL CR,Reach-1

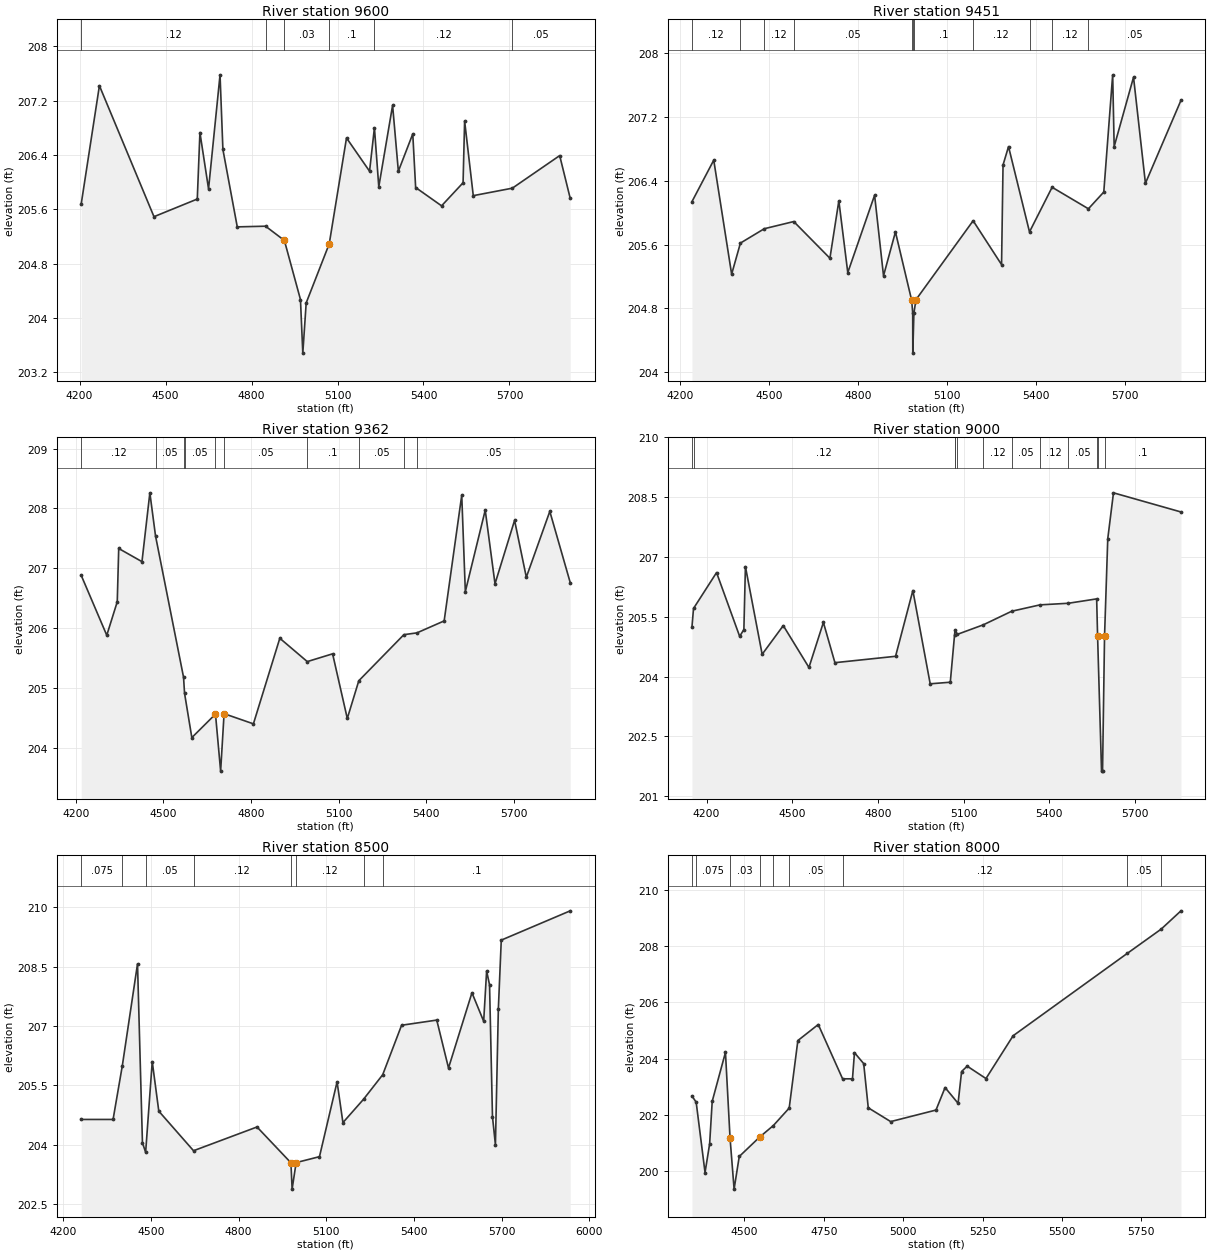
Type RM Length L Ch R = 1 ,9600    ,149,149,149
BEGIN DESCRIPTION:
WF OF CRYSTAL CREEK TRIB NO 2 19.0
END DESCRIPTION:
XS GIS Cut Line= 3
       3852101.1     10114079.99      3851308.58     10114131.69
      3850401.26     10114223.93
#Sta/Elev= 30
  4205.8  205.68  4269.2  207.42  4459.6  205.49  4610.7  205.75  4619.9  206.73
    4650   205.9  4690.1  207.58  4700.1  206.48  4750.2  205.34  4848.9  205.35
  4914.6  205.14  4970.7  204.27  4978.9  203.48  4990.7  204.22  5071.1  205.09
  5131.4  206.65  5211.8  206.16  5228.8   206.8    5244  205.93  5292.2  207.13
  5312.3  206.16  5362.6  206.71  5372.6  205.92  5463.1  205.65  5538.1  205.99
  5543.5   206.9  5573.7   205.8    5710  205.91  5875.2  206.39    5912  205.76
#Mann= 6 ,-1 , 0
  4205.8     .12       0  4848.9      .1       0  4914.6     .03       0
  5071.1      .1       0  5228.8     .12       0    5710     .05       0
Bank Sta=4914.6,5071.1
XS Rating Curve= 0 ,0
Exp/Cntr=0.3,0.1

Type RM Length L Ch R = 1 ,9451    ,89,89,89
BEGIN DESCRIPTION:
Mapping XS 278f4bd2
END DESCRIPTION:
XS GIS Cut Line= 3
      3852050.98     10113915.35      3851295.23     10113983.35
      3850408.43     10114053.95
#Sta/Elev= 30
  4241.2  206.14  4314.6  206.66  4374.9  205.23  4404.5  205.62  4484.9   205.8
  4584.3  205.89  4706.2  205.43  4736.3  206.15  4766.4  205.25  4856.8  206.22
  4886.9  205.21  4927.1  205.76  4981.9   204.9  4985.3  204.74  4985.6  204.24
  4989.3  204.74  4996.2  204.91    5189   205.9  5284.8  205.35  5289.8   206.6
  5308.3  206.83    5379  205.76  5455.2  206.32  5577.6  206.05  5629.4  206.26
  5659.4  207.73  5664.4  206.83  5729.7   207.7  5769.8  206.37  5889.6  207.41
#Mann= 11 ,-1 , 0
  4241.2     .12       0  4404.5     .05       0  4484.9     .12       0
  4584.3     .05       0  4981.9      .1       0  4985.3     .07       0
  4989.3      .1       0    5189     .12       0    5379     .05       0
  5455.2     .12       0  5577.6     .05       0
Bank Sta=4981.9,4996.2
XS Rating Curve= 0 ,0
Exp/Cntr=0.3,0.1

Type RM Length L Ch R = 1 ,9362    ,362,362,362
BEGIN DESCRIPTION:
WF OF CRYSTAL CREEK TRIB NO 2 18.0
END DESCRIPTION:
XS GIS Cut Line= 3
      3852064.94     10113825.06      3851287.22     10113894.35
      3850398.26     10113981.31
#Sta/Elev= 30
  4219.2  206.88  4306.6  205.88  4342.5  206.44  4347.5  207.33  4427.1  207.11
  4454.1  208.26  4473.5  207.54  4569.4  205.18  4572.9  204.91  4597.8  204.17
 4678.77 204.563  4696.4  203.61  4708.2  204.57  4808.6   204.4    4899  205.83
    4993  205.44  5079.7  205.57    5130  204.49  5169.4  205.12  5323.7  205.89
  5368.4  205.92  5461.6  206.12  5521.8  208.22  5534.1  206.61  5602.2  207.97
  5635.7  206.74  5702.7   207.8  5742.9  206.85  5823.3  207.95  5893.2  206.76
#Mann= 10 ,-1 , 0
  4219.2     .12       0  4473.5     .05       0  4569.4     .12       0
  4572.9     .05       0 4678.77     .07       0  4708.2     .05       0
    4993      .1       0  5169.4     .05       0  5323.7     .12       0
  5368.4     .05       0
Bank Sta=4678.77,4708.2
XS Rating Curve= 0 ,0
Exp/Cntr=0.3,0.1

Type RM Length L Ch R = 1 ,9000    ,500,500,500
BEGIN DESCRIPTION:
Mapping XS 735f228f
END DESCRIPTION:
XS GIS Cut Line= 3
      3852142.98     10113663.07      3851301.26     10113536.43
      3850442.17     10113602.25
#Sta/Elev= 30
  4148.8  205.25  4154.2  205.71  4234.9  206.61  4315.8  205.01  4330.6  205.18
    4336  206.76  4394.6  204.56  4468.6  205.28  4558.5  204.23  4609.1  205.36
  4649.5  204.35  4861.9  204.51  4922.5  206.16  4983.2  203.82  5053.6  203.86
  5068.6  205.05  5070.1  205.16  5078.2  205.06  5169.4   205.3  5268.6  205.64
  5367.9   205.8  5467.1  205.84  5566.3  205.95  5569.5  205.03  5583.4  201.63
  5586.9  201.63  5593.9 205.011  5605.2  207.46  5625.2  208.61  5861.6  208.13
#Mann= 12 ,-1 , 0
  4148.8     .05       0  4154.2     .12       0  5068.6      .1       0
  5070.1     .12       0  5078.2      .1       0  5169.4     .12       0
  5268.6     .05       0  5367.9     .12       0  5467.1     .05       0
  5566.3      .1       0  5569.5     .07       0  5593.9      .1       0
Bank Sta=5569.5,5593.9
XS Rating Curve= 0 ,0
Exp/Cntr=0.3,0.1

Type RM Length L Ch R = 1 ,8500    ,500,500,500
BEGIN DESCRIPTION:
WF OF CRYSTAL CREEK TRIB NO 2 17.0
END DESCRIPTION:
XS GIS Cut Line= 3
      3852225.39      10113441.7      3851563.98     10113112.97
      3850632.72     10113038.95
#Sta/Elev= 30
  4261.4  204.64  4370.3  204.64    4402     206  4453.9  208.57  4470.8  204.05
  4481.7  203.81  4504.3   206.1  4526.7  204.85  4645.5  203.85  4862.7  204.45
  4978.7 203.546  4982.8  202.88  4996.5  203.55  5076.4   203.7  5136.6  205.59
  5156.6  204.56  5227.1  205.15  5292.7  205.77  5357.3  207.02  5477.6  207.15
  5517.8  205.94    5598  207.84  5638.1  207.12  5648.2  208.39  5658.2  208.04
  5668.2  204.71  5678.3     204  5688.3  207.43  5698.3  209.17  5934.2  209.91
#Mann= 8 ,-1 , 0
  4261.4    .075       0    4402      .1       0  4481.7     .05       0
  4645.5     .12       0  4978.7     .07       0  4996.5     .12       0
  5227.1     .05       0  5292.7      .1       0
Bank Sta=4978.7,4996.5
XS Rating Curve= 0 ,0
Exp/Cntr=0.3,0.1

Type RM Length L Ch R = 1 ,8000    ,500,500,500
BEGIN DESCRIPTION:
WF OF CRYSTAL CREEK TRIB NO 2 16.0
END DESCRIPTION:
XS GIS Cut Line= 3
      3852439.83     10113177.83      3851915.77      10112769.1
      3851117.82     10112411.06
#Sta/Elev= 30
  4335.4  202.67  4348.6  202.45  4376.5  199.95    4391  200.97  4399.1  202.48
  4440.8  204.22  4455.2  201.18    4468  199.36  4484.2  200.52  4548.4  201.21
  4591.6  201.62  4641.4  202.24  4668.7  204.64  4732.9  205.21  4809.5  203.28
  4840.6  203.28  4846.9  204.21  4875.9  203.82  4890.3  202.25  4960.9  201.76
  5103.5  202.17  5132.1  202.97    5173  202.41  5184.1  203.54  5201.7  203.73
  5260.8  203.29  5346.2  204.81  5705.9  207.74  5812.3   208.6  5874.6  209.25
#Mann= 9 ,-1 , 0
  4335.4     .05       0  4348.6    .075       0  4455.2     .03       0
  4548.4     .05       0  4591.6    .075       0  4641.4     .05       0
  4809.5     .12       0  5705.9     .05       0  5812.3    .075       0
Bank Sta=4455.2,4548.4
XS Rating Curve= 0 ,0
Exp/Cntr=0.3,0.1