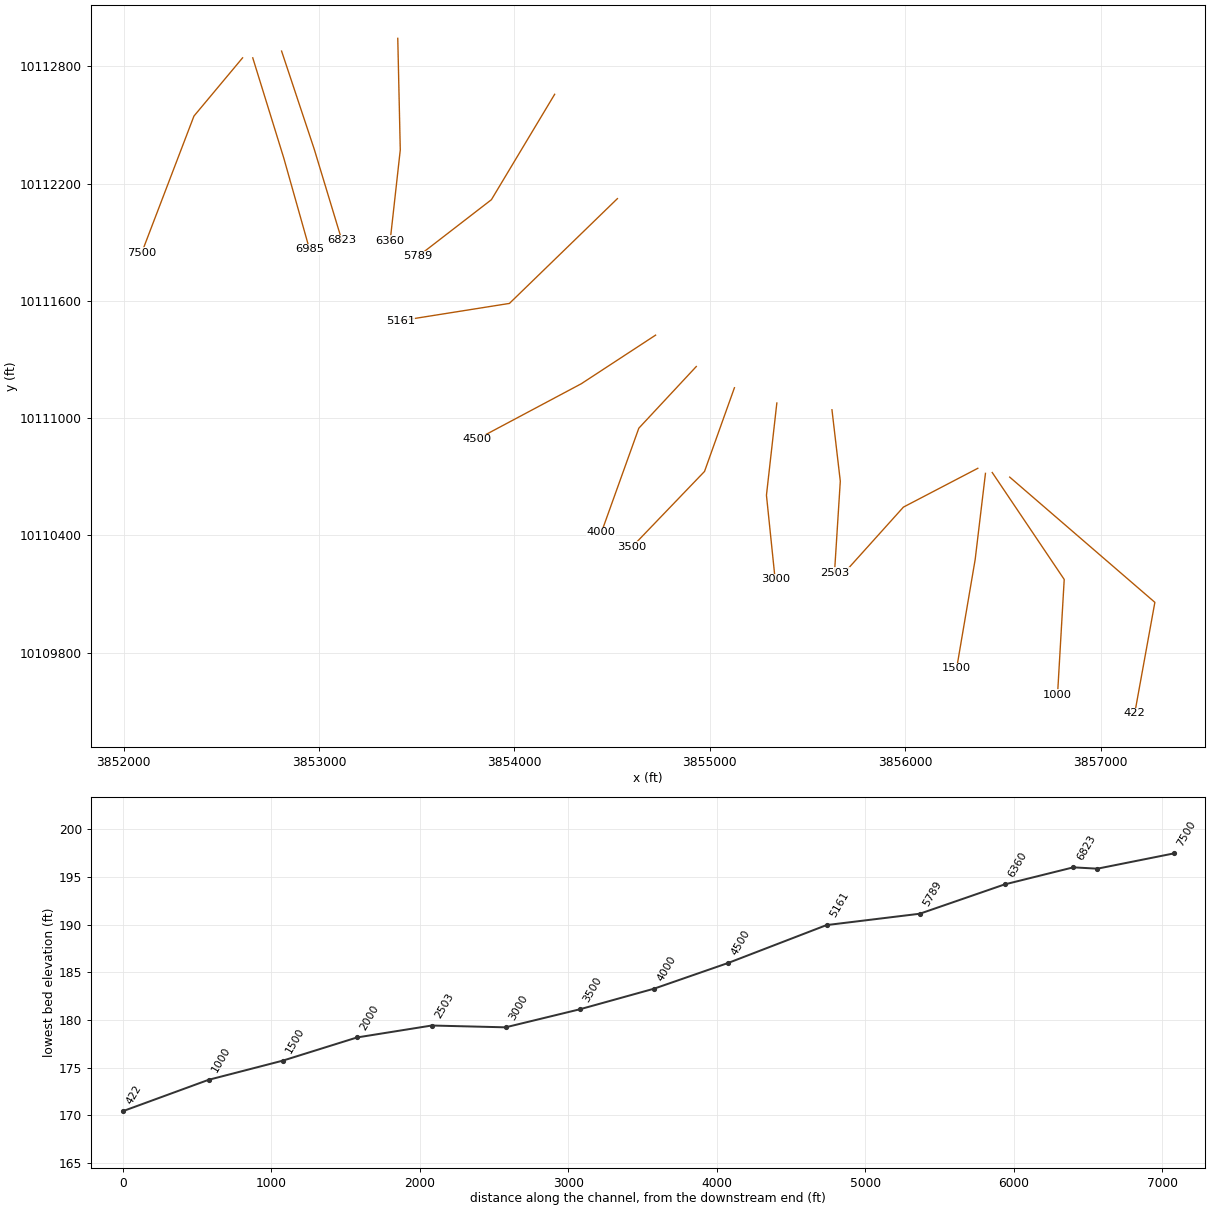
HEC-RAS study WF OF CRYSTAL CREEK TRIB NO 2.prj: WF OF CRYSTAL CREEK TRIB NO 2 Base Level Engineering

--- WF OF CRYSTAL CREEK TRIB NO 2.g10 (geometry) --- (continued)

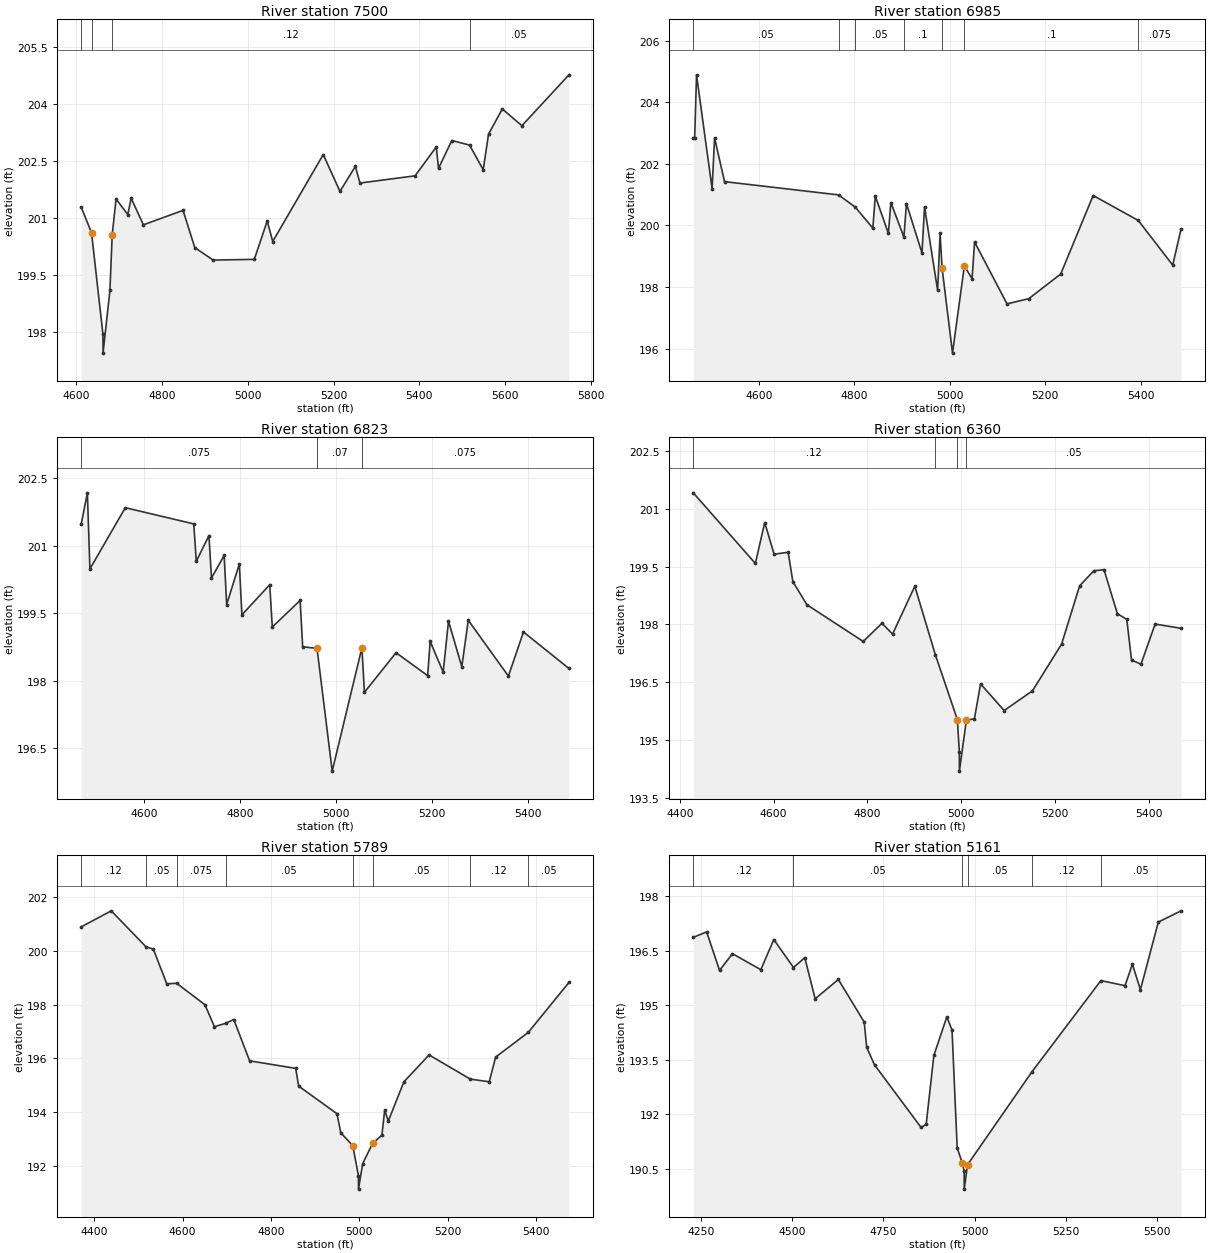
Type RM Length L Ch R = 1 ,7500    ,515,515,515
BEGIN DESCRIPTION:
WF OF CRYSTAL CREEK TRIB NO 2 15.0
END DESCRIPTION:
XS GIS Cut Line= 3
      3852609.08     10112843.61      3852360.18     10112545.57
      3852092.85     10111846.01
#Sta/Elev= 30
  4611.7   201.3  4635.8  200.62  4662.4  197.95  4662.7  197.45  4678.7   199.1
    4684  200.56    4693  201.51  4720.4   201.1  4728.2  201.53  4756.8  200.83
  4849.2  201.21  4876.6  200.23  4919.5   199.9  5015.4  199.92  5045.4  200.93
  5058.3  200.39  5176.1  202.68  5215.1  201.71    5251  202.37  5261.7  201.93
  5390.2  202.12  5439.6  202.88  5444.9  202.32  5475.9  203.05  5517.2  202.93
  5549.1  202.28  5561.5  203.22  5593.6  203.88  5639.3  203.44  5748.9  204.78
#Mann= 4 ,-1 , 0
  4611.7     .05       0  4635.8     .07       0    4684     .12       0
  5517.2     .05       0
Bank Sta=4635.8,4684
XS Rating Curve= 0 ,0
Exp/Cntr=0.3,0.1

Type RM Length L Ch R = 1 ,6985    ,162,162,162
BEGIN DESCRIPTION:
WF OF CRYSTAL CREEK TRIB NO 2 14.0
END DESCRIPTION:
XS GIS Cut Line= 3
      3852661.17     10112843.63      3852820.03     10112330.46
      3852951.51     10111864.35
#Sta/Elev= 30
  4462.8  202.84  4465.7  202.84  4469.6  204.89  4502.2  201.19  4507.4  202.84
  4528.3  201.42  4767.1  200.99  4802.2  200.59  4838.8  199.91    4844  200.95
  4871.4  199.74  4876.6  200.74  4903.9  199.62  4909.2  200.71  4941.8   199.1
  4947.1   200.6  4974.5  197.89  4979.7  199.74  4983.8 198.622  5005.7  195.85
  5030.5  198.68  5046.7  198.27  5051.9  199.46  5119.9  197.45  5165.6  197.62
  5232.3  198.42  5300.3  200.97  5394.7  200.16  5466.9  198.71  5484.3  199.88
#Mann= 7 ,-1 , 0
  4462.8     .05       0  4767.1    .075       0  4802.2     .05       0
  4903.9      .1       0  4983.8     .07       0  5030.5      .1       0
  5394.7    .075       0
Bank Sta=4983.8,5030.5
XS Rating Curve= 0 ,0
Exp/Cntr=0.3,0.1

Type RM Length L Ch R = 1 ,6823    ,463,463,463
BEGIN DESCRIPTION:
WF OF CRYSTAL CREEK TRIB NO 2 13.0
END DESCRIPTION:
XS GIS Cut Line= 3
      3852808.76      10112878.3      3852976.28     10112374.73
       3853116.9     10111910.46
#Sta/Elev= 30
  4469.3  201.47  4482.2  202.17  4487.5  200.48  4561.2  201.84  4703.8  201.48
    4709  200.65  4735.4  201.22  4740.7  200.28  4767.1  200.78  4772.3  199.69
  4798.7  200.59    4804  199.46    4862  200.13  4867.3  199.19  4925.3  199.78
  4930.6  198.75 4960.47 198.717  4992.1  195.99    5054  198.73  5059.2  197.74
  5125.1  198.62  5190.9  198.11  5196.1  198.87  5223.2  198.19  5234.3  199.32
    5262  198.31  5275.5  199.34  5359.1   198.1  5390.4  199.08  5485.1  198.27
#Mann= 3 , 0 , 0
  4469.3    .075       0 4960.47     .07       0    5054    .075       0
Bank Sta=4960.47,5054
XS Rating Curve= 0 ,0
Exp/Cntr=0.3,0.1

Type RM Length L Ch R = 1 ,6360    ,571,571,571
BEGIN DESCRIPTION:
WF OF CRYSTAL CREEK TRIB NO 2 12.0
END DESCRIPTION:
XS GIS Cut Line= 3
      3853403.36     10112943.45      3853416.19     10112372.19
      3853364.29     10111906.07
#Sta/Elev= 30
  4428.6  201.41    4561  199.58    4581  200.64    4601  199.82    4631  199.87
    4641  199.11    4671  198.51  4791.1  197.56  4831.1  198.03  4853.7  197.75
  4901.1  198.99  4945.1  197.21 4991.93 195.534  4996.1   194.7  4996.3   194.2
  5011.2  195.53  5028.2  195.55  5041.4  196.46  5091.7  195.77  5152.1  196.28
  5214.2  197.49  5252.7     199  5282.9  199.39  5304.7  199.42  5333.2  198.28
  5353.3  198.13  5363.4  197.08  5383.5  196.97  5413.7  198.01    5469   197.9
#Mann= 4 ,-1 , 0
  4428.6     .12       0  4945.1     .05       0 4991.93     .03       0
  5011.2     .05       0
Bank Sta=4991.93,5011.2
XS Rating Curve= 0 ,0
Exp/Cntr=0.3,0.1

Type RM Length L Ch R = 1 ,5789    ,628,628,628
BEGIN DESCRIPTION:
WF OF CRYSTAL CREEK TRIB NO 2 11.0
END DESCRIPTION:
XS GIS Cut Line= 3
      3854206.32       10112657.      3853882.51     10112117.51
      3853507.56     10111828.02
#Sta/Elev= 30
  4370.8   200.9  4438.8   201.5  4517.3  200.16  4534.1  200.07  4564.3  198.78
  4586.7   198.8  4650.7     198  4672.1  197.18  4697.6  197.31  4715.9  197.45
  4751.7  195.91  4855.9  195.63  4862.5  194.97  4949.2  193.94  4957.8  193.23
    4985  192.75  4997.7  191.63  4997.9  191.13  5007.3  192.08    5030  192.84
  5050.8  193.14  5057.1  194.07  5065.3  193.67  5100.6  195.13  5157.5  196.13
  5250.7  195.23  5293.5  195.13    5308  196.05  5381.8  196.97  5473.7  198.83
#Mann= 8 ,-1 , 0
  4370.8     .12       0  4517.3     .05       0  4586.7    .075       0
  4697.6     .05       0    4985     .03       0    5030     .05       0
  5250.7     .12       0  5381.8     .05       0
Bank Sta=4985,5030
XS Rating Curve= 0 ,0
Exp/Cntr=0.3,0.1

Type RM Length L Ch R = 1 ,5161    ,661,661,661
BEGIN DESCRIPTION:
WF OF CRYSTAL CREEK TRIB NO 2 10.0
END DESCRIPTION:
XS GIS Cut Line= 3
      3854527.49     10112123.13       3853974.8     10111586.71
      3853416.38     10111498.13
#Sta/Elev= 30
  4229.8  196.87  4266.4  197.02  4301.7  195.96  4337.1  196.42  4414.8  195.98
  4450.3  196.81  4504.2  196.04  4535.2  196.31  4563.5  195.18    4627  195.71
  4697.8  194.54  4704.7  193.84  4726.1  193.36  4853.4  191.64  4867.5  191.72
  4888.6  193.62  4924.1  194.68  4938.3  194.32  4952.4  191.08  4966.6  190.65
  4971.5  190.44  4971.8  189.94  4980.7  190.61  5157.2  193.17    5346  195.68
    5412  195.54  5432.3  196.13  5454.2  195.43  5503.2  197.29  5565.4   197.6
#Mann= 6 ,-1 , 0
  4229.8     .12       0  4504.2     .05       0  4966.6     .03       0
  4980.7     .05       0  5157.2     .12       0    5346     .05       0
Bank Sta=4966.6,4980.7
XS Rating Curve= 0 ,0
Exp/Cntr=0.3,0.1

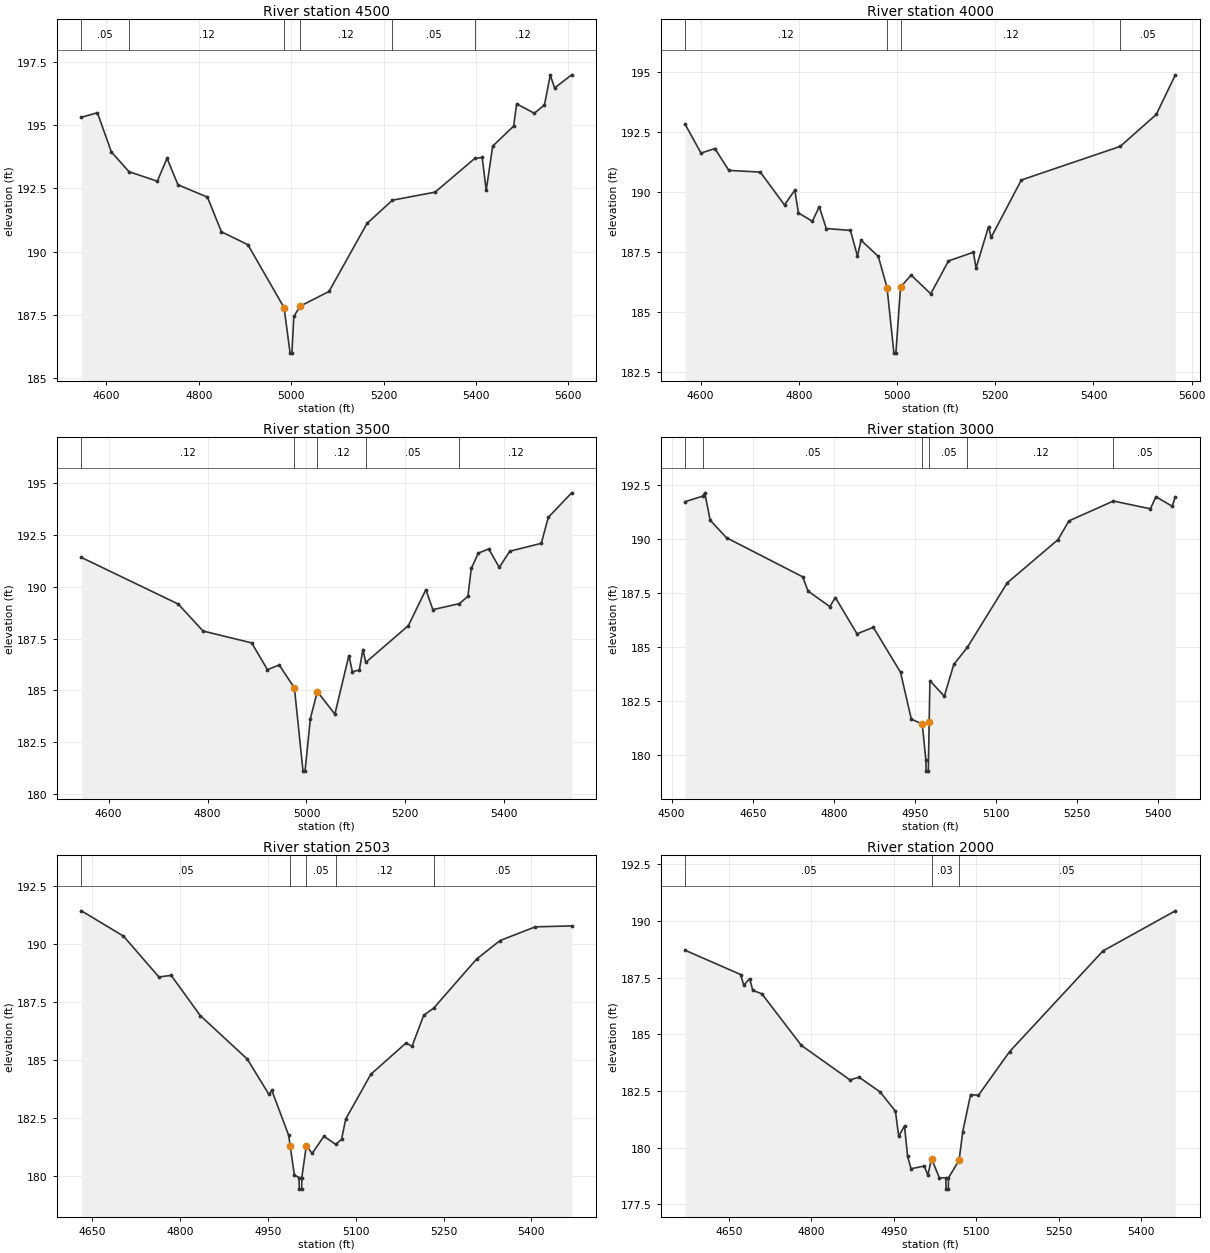
Type RM Length L Ch R = 1 ,4500    ,500,500,500
BEGIN DESCRIPTION:
WF OF CRYSTAL CREEK TRIB NO 2 9.0
END DESCRIPTION:
XS GIS Cut Line= 3
      3854722.78     10111424.33      3854342.96     10111175.82
      3853806.98     10110890.48
#Sta/Elev= 30
  4546.1  195.31  4580.7  195.49  4610.9  193.94  4648.9  193.16  4710.3  192.78
  4731.4  193.69  4755.1  192.64  4818.9  192.15  4849.1  190.78  4906.4  190.27
  4984.7  187.78  4997.8  185.98  5001.7  185.98  5005.8  187.43 5019.62 187.839
    5082  188.42  5164.2  191.11  5219.2  192.03  5311.7  192.35  5397.3  193.68
  5413.6  193.72  5422.2  192.42  5436.3  194.17  5481.6  194.96  5488.1  195.84
  5526.4  195.47  5548.3   195.8  5560.9  196.98  5570.3  196.47  5607.2  196.99
#Mann= 6 ,-1 , 0
  4546.1     .05       0  4648.9     .12       0  4984.7     .07       0
 5019.62     .12       0  5219.2     .05       0  5397.3     .12       0
Bank Sta=4984.7,5019.62
XS Rating Curve= 0 ,0
Exp/Cntr=0.3,0.1

Type RM Length L Ch R = 1 ,4000    ,500,500,500
BEGIN DESCRIPTION:
WF OF CRYSTAL CREEK TRIB NO 2 8.0
END DESCRIPTION:
XS GIS Cut Line= 3
      3854931.16     10111263.79      3854637.02     10110948.08
      3854445.58     10110414.59
#Sta/Elev= 30
  4568.5  192.81  4600.9  191.61  4629.2   191.8  4657.5  190.89  4721.6  190.82
  4770.9  189.45  4791.9  190.07  4799.2  189.12  4827.6  188.77  4841.7  189.38
  4855.9  188.47  4905.2  188.39  4919.4  187.32  4926.8  187.98  4961.9  187.31
 4979.72 186.005  4993.7  183.28  4997.7  183.28  5007.2  186.03  5028.7  186.53
  5068.7  185.75  5104.8  187.12  5155.6  187.48  5160.9  186.82  5186.4  188.55
  5191.7   188.1  5253.2  190.49  5454.6  191.89    5528  193.22  5566.8  194.87
#Mann= 4 ,-1 , 0
  4568.5     .12       0 4979.72     .07       0  5007.2     .12       0
  5454.6     .05       0
Bank Sta=4979.72,5007.2
XS Rating Curve= 0 ,0
Exp/Cntr=0.3,0.1

Type RM Length L Ch R = 1 ,3500    ,500,500,500
BEGIN DESCRIPTION:
WF OF CRYSTAL CREEK TRIB NO 2 7.0
END DESCRIPTION:
XS GIS Cut Line= 3
      3855126.45     10111155.24      3854973.38     10110726.86
      3854602.03     10110340.07
#Sta/Elev= 30
  4545.1   191.4  4740.7  189.16    4791  187.86  4889.3  187.29  4921.2     186
  4944.9  186.23  4975.7  185.12  4993.1  181.12  4997.1  181.12    5008  183.65
    5022  184.95  5057.5  183.86  5085.8  186.68  5092.8  185.91  5106.9  185.98
  5114.1  186.97  5119.9  186.35    5206  188.12  5241.5  189.85  5255.6  188.89
  5309.3  189.18  5326.4  189.53  5333.3  190.87  5347.5  191.61  5368.6  191.81
  5389.9  190.92    5411   191.7  5474.8  192.08    5489  193.33  5536.2  194.51
#Mann= 5 ,-1 , 0
  4545.1     .12       0  4975.7     .07       0    5022     .12       0
  5119.9     .05       0  5309.3     .12       0
Bank Sta=4975.7,5022
XS Rating Curve= 0 ,0
Exp/Cntr=0.3,0.1

Type RM Length L Ch R = 1 ,3000    ,497,497,497
BEGIN DESCRIPTION:
WF OF CRYSTAL CREEK TRIB NO 2 6.0
END DESCRIPTION:
XS GIS Cut Line= 3
      3855343.47     10111077.16      3855290.27     10110605.05
      3855334.69     10110175.24
#Sta/Elev= 30
  4524.9  191.71  4557.9  191.97  4561.2  192.12  4571.3  190.85  4601.5  190.04
  4742.4  188.23  4752.4  187.57  4792.7  186.85    4803  187.27    4843  185.59
  4873.2  185.89  4923.5  183.81  4943.6  181.63  4963.7  181.42  4970.5  179.73
  4970.8  179.23  4974.9  179.23 4976.56 181.519  4977.9  183.42  5004.5   182.7
  5022.1  184.17  5047.4  184.97    5121  187.95  5214.9  189.95  5235.2  190.82
  5317.4  191.74    5386  191.38  5396.1  191.94  5426.2   191.5  5432.1  191.94
#Mann= 6 ,-1 , 0
  4524.9     .12       0  4557.9     .05       0  4963.7     .07       0
 4976.56     .05       0  5047.4     .12       0  5317.4     .05       0
Bank Sta=4963.7,4976.56
XS Rating Curve= 0 ,0
Exp/Cntr=0.3,0.1

Type RM Length L Ch R = 1 ,2503    ,503,503,503
BEGIN DESCRIPTION:
WF OF CRYSTAL CREEK TRIB NO 2 5.0
END DESCRIPTION:
XS GIS Cut Line= 3
      3855625.59     10111042.38      3855668.24     10110676.86
      3855638.61      10110209.1
#Sta/Elev= 30
    4632  191.41  4703.8  190.32  4764.2  188.56  4785.2  188.63  4834.7   186.9
  4915.2  185.02    4952   183.5    4957  183.67  4985.7  181.74 4988.41 181.262
  4995.4  180.03  5003.4  179.92  5003.8  179.42  5007.9  179.42  5008.2  179.92
  5015.8  181.29  5025.8  180.96  5045.9   181.7  5065.8  181.35  5075.9  181.56
  5083.1  182.44    5126  184.37  5186.2  185.72  5196.2  185.57  5216.2  186.91
  5233.3  187.22  5306.4  189.33  5346.5  190.13  5406.6  190.72  5468.7  190.76
#Mann= 5 ,-1 , 0
    4632     .05       0 4988.41     .03       0  5015.8     .05       0
  5065.8     .12       0  5233.3     .05       0
Bank Sta=4988.41,5015.8
XS Rating Curve= 0 ,0
Exp/Cntr=0.3,0.1

Type RM Length L Ch R = 1 ,2000    ,500,500,500
BEGIN DESCRIPTION:
WF OF CRYSTAL CREEK TRIB NO 2 4.0
END DESCRIPTION:
XS GIS Cut Line= 3
      3856372.07      10110742.9      3855991.29     10110544.23
      3855682.45     10110200.89
#Sta/Elev= 30
  4570.5  188.71  4671.4  187.64  4677.1  187.17  4687.9  187.46  4693.5  186.94
    4710  186.79  4781.9  184.51  4870.2  182.99  4886.7  183.11  4924.9  182.46
  4952.9  181.61  4958.8   180.5  4969.4  180.96    4975  179.61  4981.3  179.07
  5005.5  179.19  5011.8  178.78  5018.5  179.52  5032.7  178.67  5044.5  178.67
  5044.9  178.17    5049  178.17  5049.3  178.67  5068.6  179.44  5075.3  180.71
  5089.5  182.34  5103.7  182.31  5160.5  184.24  5330.2  188.68  5461.8  190.45
#Mann= 3 , 0 , 0
  4570.5     .05       0  5018.5     .03       0  5068.6     .05       0
Bank Sta=5018.5,5068.6
XS Rating Curve= 0 ,0
Exp/Cntr=0.3,0.1

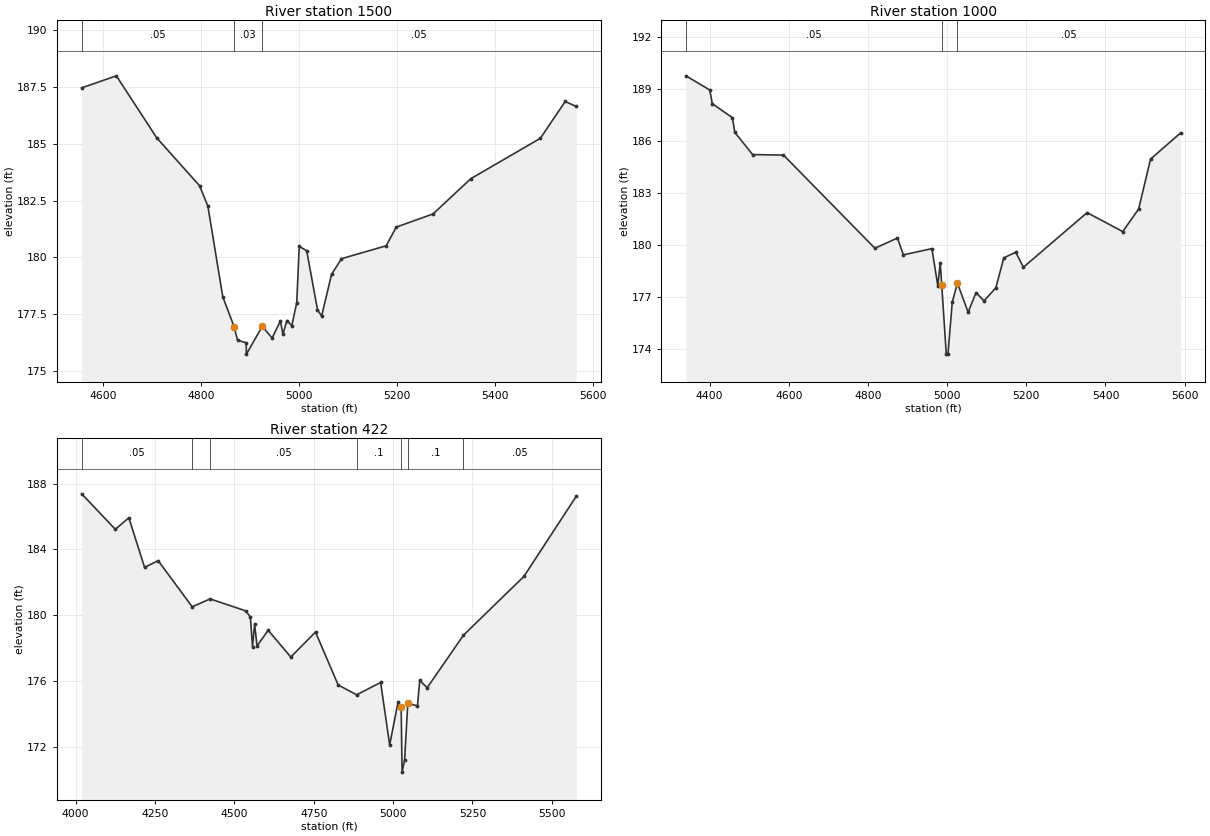
Type RM Length L Ch R = 1 ,1500    ,500,500,500
BEGIN DESCRIPTION:
WF OF CRYSTAL CREEK TRIB NO 2 3.0
END DESCRIPTION:
XS GIS Cut Line= 3
      3856411.18      10110716.9      3856358.54     10110276.03
      3856263.61     10109718.65
#Sta/Elev= 30
    4556  187.46  4626.8  187.99  4709.2  185.26  4796.7  183.15  4813.6  182.25
  4843.9  178.27  4866.9 176.956  4874.1  176.35  4891.8  176.24  4892.2  175.74
  4924.4  176.96  4944.6  176.45  4961.6   177.2  4966.7  176.61  4974.8  177.22
  4984.8  176.99  4994.9  178.01    5000  180.48  5015.2  180.29  5037.2   177.7
  5045.6  177.41  5065.9  179.25  5086.2  179.94  5177.5  180.51  5197.8  181.33
    5273  181.91  5349.9  183.46  5491.9  185.24  5542.7  186.86  5565.4  186.64
#Mann= 3 , 0 , 0
    4556     .05       0  4866.9     .03       0  4924.4     .05       0
Bank Sta=4866.9,4924.4
XS Rating Curve= 0 ,0
Exp/Cntr=0.3,0.1

Type RM Length L Ch R = 1 ,1000    ,578,578,578
BEGIN DESCRIPTION:
WF OF CRYSTAL CREEK TRIB NO 2 2.0
END DESCRIPTION:
XS GIS Cut Line= 3
      3856445.89     10110721.23      3856814.25     10110174.07
      3856780.15     10109585.06
#Sta/Elev= 30
  4340.4  189.74  4400.7  188.92  4406.7  188.14  4457.7  187.33  4463.7  186.49
  4508.7  185.21  4586.7  185.18  4817.6  179.82  4874.6  180.41  4889.6  179.44
  4961.6   179.8  4976.5  177.67  4982.6  178.99 4986.42  177.72  4997.9  173.73
  5002.2  173.73    5013  176.72  5026.1  177.81  5053.1  176.14  5073.1  177.27
  5093.2  176.79  5123.2  177.55  5143.2  179.27  5173.3  179.59  5192.8  178.73
  5353.6  181.87  5443.7  180.78  5483.8  182.08  5513.9  184.95    5590  186.46
#Mann= 3 , 0 , 0
  4340.4     .05       0 4986.42     .07       0  5026.1     .05       0
Bank Sta=4986.42,5026.1
XS Rating Curve= 0 ,0
Exp/Cntr=0.3,0.1

Type RM Length L Ch R = 1 ,422     ,0,0,0
BEGIN DESCRIPTION:
WF OF CRYSTAL CREEK TRIB NO 2 1.0
END DESCRIPTION:
XS GIS Cut Line= 3
       3856535.3     10110697.79      3857278.24     10110056.86
      3857175.06     10109488.55
#Sta/Elev= 30
  4018.8  187.39  4124.9  185.23  4167.5  185.93  4217.1  182.91  4259.8  183.32
  4367.1  180.51  4423.5  180.99  4536.3  180.26  4550.5  179.87  4557.2  178.09
  4563.8  179.46  4571.4  178.12  4606.5  179.08  4677.8  177.45  4755.7  178.97
    4827  175.75  4885.5  175.15  4960.9   175.9  4989.4   172.1    5016  174.73
  5025.6  174.39  5028.5  170.44  5036.4  171.16  5046.5  174.62    5077  174.48
  5084.1  176.03  5107.5  175.58    5222  178.78  5412.4  182.36  5577.6  187.25
#Mann= 7 ,-1 , 0
  4018.8     .05       0  4367.1     .12       0  4423.5     .05       0
  4885.5      .1       0  5025.6     .07       0  5046.5      .1       0
    5222     .05       0
Bank Sta=5025.6,5046.5
XS Rating Curve= 0 ,0
Exp/Cntr=0.3,0.1