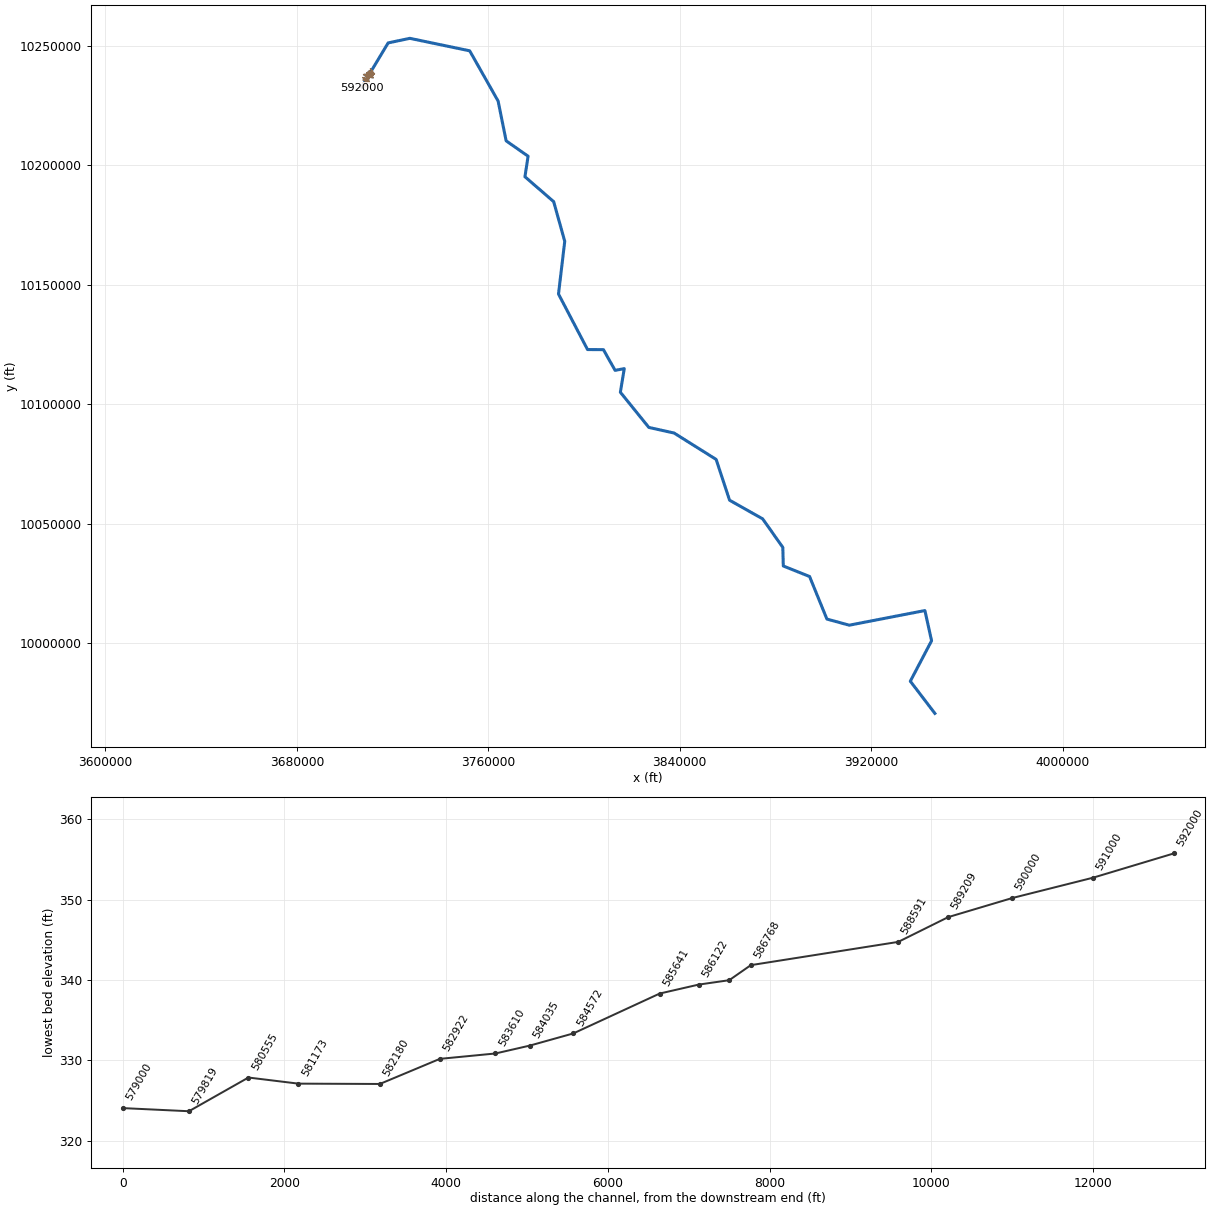
--- WFSJ Main.prj (project) ---

Proj Title=WFSJ Main Base Level Engineering
Current Plan=p01
Default Exp/Contr=0.3,0.1
English Units
Geom File=g02
Geom File=g01
Flow File=f01
Flow File=f02
Plan File=p01
Plan File=p02
Y Axis Title=Elevation
X Axis Title(PF)=Main Channel Distance
X Axis Title(XS)=Station
BEGIN DESCRIPTION:
WFSJ Main
END DESCRIPTION:
DSS File=dss
DSS Export Rating Curves= 0
DSS Export Rating Curve Sorted= 0
DSS Export Volume Flow Curves= 0
DXF OffsetX= 0
DXF OffsetY= 0
DXF ScaleX= 1
DXF ScaleY= 10

--- WFSJ Main.p01 (plan) ---

Plan Title=Multiple Run
Program Version=4.10
Short Identifier=Multiple Run
Geom File=g01
Flow File=f01
Subcritical Flow
K Sum by GR= 0
Std Step Tol= 0.01
Critical Tol= 0.01
Num of Std Step Trials= 20
Max Error Tol= 0.3
Flow Tol Ratio= 0.001
Split Flow NTrial= 30
Split Flow Tol= 0.02
Split Flow Ratio= 0.02
Log Output Level= 0
Friction Slope Method= 1
Unsteady Friction Slope Method= 2
Unsteady Bridges Friction Slope Method= 1
Parabolic Critical Depth
Global Vel Dist= 1 , 1 , 1
Global Log Level= 0
CheckData=True
Encroach Param=-1 ,0,0, 0
BEGIN DESCRIPTION:
Multiple Run
END DESCRIPTION:
Computation Interval=1HOUR
Output Interval=1HOUR
Run HTab= 0
Run UNet= 0
Run PostProcess= 0
Run WQNet= 0
UNET Theta= 1
UNET Theta Warmup= 1
UNET ZTol= 0.02
UNET ZSATol= 0.05
UNET MxIter= 20
UNET MaxInSteps= 0
UNET DtIC= 0
UNET DtMin= 0
UNET MaxCRTS= 20
UNET WFStab= 2
UNET SFStab= 1
UNET WFX= 1
UNET SFX= 1
UNET DSS MLevel= 4
UNET DZMax Abort= 100
UNET Convert EG Bridges= 0
UNET Use Existing IB Tables=-1
UNET Froude Reduction=False
UNET Froude Limit= 1
UNET Froude Power= 10
UNET Time Slicing=0,0, 5
UNET Junction Losses=0
Instantaneous Interval=1HOUR
DSS File=dss
Write IC File= 0
Write IC File at Sim End=0
Echo Input=False
Echo Parameters=False
Echo Output=False
Write Detailed= 0
WQ AD Non Conservative
WQ ULTIMATE=-1
WQ Max Comp Step=1HOUR
WQ Output Interval=15MIN
WQ Output Selected Increments= 0
WQ Output face flow=0
WQ Output face velocity=0
WQ Output face area=0
WQ Output face dispersion=0
WQ Output cell volume=0
WQ Output cell surface area=0
WQ Output cell continuity=0
WQ Output cumulative cell continuity=0
WQ Output face conc=0
WQ Output face dconc_dx=0
WQ Output face courant=0
WQ Output face peclet=0
WQ Output face adv mass=0
WQ Output face disp mass=0
WQ Output cell mass=0
WQ Output cell source sink temp=0
WQ Output cell source sink nsm=0
WQ Output MaxMinRange=-1
WQ Daily Max Min Mean=-1
WQ Daily Range=0
WQ Daily Time=0
WQ Create Restart=0
WQ Fixed Restart=0
WQ System Summary=0
WQ Use Fixed Temperature=0
Sorting and Armoring Iterations= 10
XS Update Threshold= 0.02
Hydraulics Update Threshold= 0.02
Energy Slope Method= 1
Volume Change Method= 0
XS Weighting Method= 0
Number of US Weighted Cross Sections= 1
Number of DS Weighted Cross Sections= 1
Upstream XS Weight=0.25
Main XS Weight=0.5
Downstream XS Weight=0.25
Number of DS XS's Weighted with US Boundary= 1
Upstream Boundary Weight= 1
Weight of XSs Associated with US Boundary= 0
Number of US XS's Weighted with DS Boundary= 1
Downstream Boundary Weight= 0.5
Weight of XSs Associated with DS Boundary= 0.5
Sediment Output Level= 4
Mass or Volume Output= 0
Output Increment Type= 1
Profile and TS Output Increment= 10
XS Output Flag= 0
XS Output Increment= 10
Disregard all LS=0
Disregard all Conn=0
Disregard all Breaches=0
Disregard all Pumps=0

--- WFSJ Main.p02 (plan) ---

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Plan Title=OrigBLE
Short Identifier=OrigBLE
Geom File=g02
Flow File=f02
Global Vel Dist= 0 , 0 , 0

--- WFSJ Main.f01 (steady flow) ---

Flow Title=Multiple
Program Version=4.10
Number of Profiles= 7
Profile Names=10-year,25-year,50-year,1pct_min,100-year,1pct_plu,500-year
River Rch & RM=WFSJ Main,Reach-1         ,592000
     636     861    1163     516    1559    4708    2898
River Rch & RM=WFSJ Main,Reach-1         ,586768
     795    1075    1449     641    1936    5847    3574
River Rch & RM=WFSJ Main,Reach-1         ,581173
    1383    1919    2633    1182    3571   10784    6808
River Rch & RM=WFSJ Main,Reach-1         ,575465
    1974    2766    3820    1725    5208   15728   10028
River Rch & RM=WFSJ Main,Reach-1         ,560093
    2976    4231    5899    2686    8113   24501   15894
River Rch & RM=WFSJ Main,Reach-1         ,552602
    3603    5117    7130    3241    9788   29559   19104
River Rch & RM=WFSJ Main,Reach-1         ,534727
    4151    5920    8273    3771   11387   34388   22341
River Rch & RM=WFSJ Main,Reach-1         ,528000
    5296    7580   10620    4851   14651   44245   28857
River Rch & RM=WFSJ Main,Reach-1         ,507843
    6485    9339   13142    6028   18203   54972   36138
River Rch & RM=WFSJ Main,Reach-1         ,503841
    6964   10065   14199    6529   19718   59547   39339
River Rch & RM=WFSJ Main,Reach-1         ,493536
    7076   10178   14311    6557   19803   59804   39225
River Rch & RM=WFSJ Main,Reach-1         ,480076
    9172   13215   18610    8536   25779   77851   51141
River Rch & RM=WFSJ Main,Reach-1         ,466567
    9506   13703   19303    8857   26749   80781   53095
River Rch & RM=WFSJ Main,Reach-1         ,464744
    9944   14338   20203    9271   27999   84556   55591
River Rch & RM=WFSJ Main,Reach-1         ,462000
    9946   14339   20198    9266   27982   84504   55524
River Rch & RM=WFSJ Main,Reach-1         ,454000
   10356   14885   20929    9582   28938   87391   57180
River Rch & RM=WFSJ Main,Reach-1         ,438838
   11862   17049   23980   10982   33164  100154   65522
River Rch & RM=WFSJ Main,Reach-1         ,432522
   14154   20429   28819   13234   39967  120698   79400
River Rch & RM=WFSJ Main,Reach-1         ,421771
   14876   21412   30154   13823   41746  126071   82611
River Rch & RM=WFSJ Main,Reach-1         ,412236
   14205   20397   28672   13118   39615  119635   78107
River Rch & RM=WFSJ Main,Reach-1         ,400924
   16858   24208   34047   15584   47062  142125   92815
River Rch & RM=WFSJ Main,Reach-1         ,398000
   16593   23827   33506   15332   46303  139833   91298
River Rch & RM=WFSJ Main,Reach-1         ,393000
   16441   23554   33069   15107   45622  137776   89650
River Rch & RM=WFSJ Main,Reach-1         ,385020
   16362   23400   32813   14971   45212  136538   88623
River Rch & RM=WFSJ Main,Reach-1         ,378407
   16098   22947   32106   14615   44136  133289   86110
River Rch & RM=WFSJ Main,Reach-1         ,366000
   16769   23913   33469   15240   46024  138990   89844
River Rch & RM=WFSJ Main,Reach-1         ,365000
   16846   24016   33606   15299   46203  139531   90153
River Rch & RM=WFSJ Main,Reach-1         ,364000
   17731   25218   35239   16020   48379  146102   94096
River Rch & RM=WFSJ Main,Reach-1         ,359000
   18559   26474   37064   16879   50975  153942   99542
River Rch & RM=WFSJ Main,Reach-1         ,355571
   18881   26807   37416   16988   51302  154930   99524
River Rch & RM=WFSJ Main,Reach-1         ,344615
   19777   28027   39074   17718   53508  161592  103532
River Rch & RM=WFSJ Main,Reach-1         ,331705
   20114   28541   39822   18071   54575  164814  105784
River Rch & RM=WFSJ Main,Reach-1         ,329000
   20703   29289   40789   18475   55794  168495  107699
River Rch & RM=WFSJ Main,Reach-1         ,322270
   20744   29208   40551   18310   55294  166985  106027
River Rch & RM=WFSJ Main,Reach-1         ,304350
   25456   36591   51541   23621   71335  215428  140927
River Rch & RM=WFSJ Main,Reach-1         ,283475
   25698   36928   52006   23830   71966  217334  142117
River Rch & RM=WFSJ Main,Reach-1         ,275312
   25823   37054   52134   23865   72071  217651  142034
River Rch & RM=WFSJ Main,Reach-1         ,257000
   34307   49403   69711   32004   96651  291881  191562
River Rch & RM=WFSJ Main,Reach-1         ,251058
   35768   51276   72156   33036   99766  301289  196530
River Rch & RM=WFSJ Main,Reach-1         ,237000
   36453   52266   73559   33683  101721  307193  200433
River Rch & RM=WFSJ Main,Reach-1         ,229000
   37142   53100   74599   34097  102972  310970  202093
River Rch & RM=WFSJ Main,Reach-1         ,219000
   37181   53134   74627   34101  102982  311001  202001
River Rch & RM=WFSJ Main,Reach-1         ,213000
   37565   53712   75467   34499  104184  314631  204520
River Rch & RM=WFSJ Main,Reach-1         ,200834
   38857   55558   78068   35691  107785  325505  211615
River Rch & RM=WFSJ Main,Reach-1         ,199000
   38991   55749   78335   35813  108153  326617  212334
River Rch & RM=WFSJ Main,Reach-1         ,196239
   40208   57421   80634   36842  111260  336000  218099
River Rch & RM=WFSJ Main,Reach-1         ,176000
   39324   56205   78960   36091  108992  329151  213881
River Rch & RM=WFSJ Main,Reach-1         ,169000
   40746   58195   81730   37346  112784  340602  221129
River Rch & RM=WFSJ Main,Reach-1         ,153000
   41779   59539   83506   38108  115083  347545  224967
River Rch & RM=WFSJ Main,Reach-1         ,140657
   41583   59187   82945   37819  114211  344912  222878
River Rch & RM=WFSJ Main,Reach-1         ,120679
   41758   59407   83225   37934  114558  345960  223398
River Rch & RM=WFSJ Main,Reach-1         ,112000
   51972   74084  103983   47507  143468  433266  281306
River Rch & RM=WFSJ Main,Reach-1         ,100000
   58352   82564  115394   52500  158548  478807  307819
River Rch & RM=WFSJ Main,Reach-1         ,81000
   58516   82792  115710   52643  158978  480106  308636
River Rch & RM=WFSJ Main,Reach-1         ,79000
   58372   82552  115339   52458  158420  478421  307363
River Rch & RM=WFSJ Main,Reach-1         ,69357
   58231   82298  114933   52249  157788  476512  305848
River Rch & RM=WFSJ Main,Reach-1         ,61268
   58046   81991  114461   52014  157081  474377  304243
River Rch & RM=WFSJ Main,Reach-1         ,53139
   74732  105480  147295   66972  202251  610788  392033
River Rch & RM=WFSJ Main,Reach-1         ,46149
   79550  112185  156620   71201  215023  649359  416415
River Rch & RM=WFSJ Main,Reach-1         ,35030
   79184  111606  155751   70779  213749  645512  413643
River Rch & RM=WFSJ Main,Reach-1         ,29279
   78525  110555  154169   70005  211413  638457  408485
River Rch & RM=WFSJ Main,Reach-1         ,17000
   78081  109854  153120   69497  209877  633818  405147
River Rch & RM=WFSJ Main,Reach-1         ,11416
   79349  111435  155152   70344  212435  641543  409099
River Rch & RM=WFSJ Main,Reach-1         ,4000
   79103  111051  154580   70067  211599  639019  407286
Boundary for River Rch & Prof#=WFSJ Main,Reach-1         , 1
Up Type= 0
Dn Type= 3
Dn Slope=0.0002
Boundary for River Rch & Prof#=WFSJ Main,Reach-1         , 2
Up Type= 0
Dn Type= 3
Dn Slope=0.0002
Boundary for River Rch & Prof#=WFSJ Main,Reach-1         , 3
Up Type= 0
Dn Type= 3
Dn Slope=0.0002
Boundary for River Rch & Prof#=WFSJ Main,Reach-1         , 4
Up Type= 0
Dn Type= 3
Dn Slope=0.0002
Boundary for River Rch & Prof#=WFSJ Main,Reach-1         , 5
Up Type= 0
Dn Type= 3
Dn Slope=0.0002
Boundary for River Rch & Prof#=WFSJ Main,Reach-1         , 6
Up Type= 0
Dn Type= 3
Dn Slope=0.0002
Boundary for River Rch & Prof#=WFSJ Main,Reach-1         , 7
Up Type= 0
Dn Type= 3
Dn Slope=0.0002
Observed WS=WFSJ Main       ,Reach-1         ,470276  ,140,,,,,232.39,,
Observed WS=WFSJ Main       ,Reach-1         ,322388  ,0,,,,,206.23,,
Observed WS=WFSJ Main       ,Reach-1         ,304007  ,0,,,,,162.18,,
Observed WS=WFSJ Main       ,Reach-1         ,255705  ,539,,,,,133.33,,
Observed WS=WFSJ Main       ,Reach-1         ,223922  ,470,,,,,122.02,,
Observed WS=WFSJ Main       ,Reach-1         ,213000  ,0,,,,,116.5,,
Observed WS=WFSJ Main       ,Reach-1         ,211000  ,855,,,,,114.43,,
Observed WS=WFSJ Main       ,Reach-1         ,196239  ,150,,,,,107.67,,
Observed WS=WFSJ Main       ,Reach-1         ,192000  ,600,,,,,104.44,,
Observed WS=WFSJ Main       ,Reach-1         ,186000  ,370,,,,,102.57,,
Observed WS=WFSJ Main       ,Reach-1         ,100000  ,1200,,,,,71.2,,
Observed WS=WFSJ Main       ,Reach-1         ,93000   ,800,,,,,65.59,,
Observed WS=WFSJ Main       ,Reach-1         ,91000   ,0,,,,,66.16,,
Observed WS=WFSJ Main       ,Reach-1         ,89478   ,730,,,,,65.5,,
Observed WS=WFSJ Main       ,Reach-1         ,87000   ,450,,,,,64.38,,
Observed WS=WFSJ Main       ,Reach-1         ,61268   ,0,,,,,55.05,,
Observed WS=WFSJ Main       ,Reach-1         ,50735   ,0,,,,,54.38,,
Observed WS=WFSJ Main       ,Reach-1         ,49307   ,800,,,,,54.53,,
Observed WS=WFSJ Main       ,Reach-1         ,19241   ,390,,,,,52.33,,
Observed WS=WFSJ Main       ,Reach-1         ,16000   ,30,,,,,52.51,,
Observed WS=WFSJ Main       ,Reach-1         ,5268    ,800,,,,,52.45,,
Observed WS=WFSJ Main       ,Reach-1         ,3713    ,0,,,,,41.9,,
DSS Import GetInterval= 0
DSS Import GetPeak= 0
DSS Import FillOption= 0

--- WFSJ Main.f02 (steady flow) ---

Flow Title=Orig_Submitted_BLE_Flows
Program Version=4.10
Number of Profiles= 7
Profile Names=10-year,25-year,50-year,1pct_min,100-year,1pct_plu,500-year
River Rch & RM=WFSJ Main,Reach-1         ,592000
     636     844    1011     397    1199    3621    1685
River Rch & RM=WFSJ Main,Reach-1         ,586768
     795    1054    1260     493    1489    4497    2078
River Rch & RM=WFSJ Main,Reach-1         ,581173
    1383    1881    2289     910    2747    8296    3958
River Rch & RM=WFSJ Main,Reach-1         ,575465
    1974    2712    3322    1327    4006   12098    5830
River Rch & RM=WFSJ Main,Reach-1         ,560093
    2976    4148    5130    2067    6241   18847    9241
River Rch & RM=WFSJ Main,Reach-1         ,552602
    3603    5017    6200    2493    7529   22737   11107
River Rch & RM=WFSJ Main,Reach-1         ,534727
    4151    5804    7193    2900    8759   26452   12989
River Rch & RM=WFSJ Main,Reach-1         ,528000
    5296    7432    9235    3732   11270   34036   16777
River Rch & RM=WFSJ Main,Reach-1         ,507843
    6485    9156   11427    4637   14002   42287   21010
River Rch & RM=WFSJ Main,Reach-1         ,503841
    6964    9868   12347    5022   15167   45805   22872
River Rch & RM=WFSJ Main,Reach-1         ,493536
    7076    9979   12445    5044   15233   46003   22805
River Rch & RM=WFSJ Main,Reach-1         ,480076
    9172   12956   16183    6566   19830   59887   29733
River Rch & RM=WFSJ Main,Reach-1         ,466567
    9506   13434   16786    6813   20576   62138   30869
River Rch & RM=WFSJ Main,Reach-1         ,464744
    9944   14057   17568    7132   21538   65044   32320
River Rch & RM=WFSJ Main,Reach-1         ,462000
    9946   14058   17564    7127   21525   65003   32281
River Rch & RM=WFSJ Main,Reach-1         ,454000
   10356    7296    9100    7371   22260   67225   16622
River Rch & RM=WFSJ Main,Reach-1         ,438838
   11862   16715   20852    8447   25511   77041   38094
River Rch & RM=WFSJ Main,Reach-1         ,432522
   14154   20028   25060   10180   30744   92845   46163
River Rch & RM=WFSJ Main,Reach-1         ,421771
   14876   20992   26221   10633   32112   96977   48030
River Rch & RM=WFSJ Main,Reach-1         ,412236
    1769    2491    3106    1257    3796   11463    5657
River Rch & RM=WFSJ Main,Reach-1         ,400924
    2100    2956    3688    1493    4509   13618    6722
River Rch & RM=WFSJ Main,Reach-1         ,398000
    2067    2910    3629    1469    4437   13399    6612
River Rch & RM=WFSJ Main,Reach-1         ,393000
    2048    2877    3582    1448    4371   13201    6493
River Rch & RM=WFSJ Main,Reach-1         ,385020
    2038    2858    3554    1435    4332   13083    6418
River Rch & RM=WFSJ Main,Reach-1         ,378407
    2005    2802    3478    1400    4229   12772    6236
River Rch & RM=WFSJ Main,Reach-1         ,366000
    2089    2920    3625    1460    4410   13318    6507
River Rch & RM=WFSJ Main,Reach-1         ,365000
    2098    2933    3640    1466    4427   13370    6529
River Rch & RM=WFSJ Main,Reach-1         ,364000
    2098    3080    3817    1535    4636   13999    6815
River Rch & RM=WFSJ Main,Reach-1         ,359000
    2034    3071    3814    1617    4884   14751    7569
River Rch & RM=WFSJ Main,Reach-1         ,355571
    1999    3077    3810    1628    4916   14845    7568
River Rch & RM=WFSJ Main,Reach-1         ,344615
    1971    3149    3894    1698    5127   15483    8248
River Rch & RM=WFSJ Main,Reach-1         ,331705
    2004    3207    3968    1732    5229   15792    9193
River Rch & RM=WFSJ Main,Reach-1         ,329000
    1934    3219    3976    1770    5346   16145    9360
River Rch & RM=WFSJ Main,Reach-1         ,322270
   14521   25772   31736   14084   42534  128450   77055
River Rch & RM=WFSJ Main,Reach-1         ,304350
   17819   28699   40336   17262   52130  157429  105696
River Rch & RM=WFSJ Main,Reach-1         ,283475
   18502   29687   40700   22914   69198  208976  107414
River Rch & RM=WFSJ Main,Reach-1         ,275312
   20658   32695   45334   23865   72071  217651  115609
River Rch & RM=WFSJ Main,Reach-1         ,257000
   32592   48435   69711   33481  101111  305351  183766
River Rch & RM=WFSJ Main,Reach-1         ,251058
   35410   57811   77175   34560  104371  315195  190817
River Rch & RM=WFSJ Main,Reach-1         ,237000
   36089   58415   80595   35756  107981  326098  196937
River Rch & RM=WFSJ Main,Reach-1         ,229000
   36771   59868   82383   36195  109308  330106  198568
River Rch & RM=WFSJ Main,Reach-1         ,219000
   37553   60427   84361   36724  110904  334925  199652
River Rch & RM=WFSJ Main,Reach-1         ,213000
   38317   62137   85311   37152  112198  338833  202142
River Rch & RM=WFSJ Main,Reach-1         ,200834
   40799   65362   89608   38436  116076  350544  209154
River Rch & RM=WFSJ Main,Reach-1         ,199000
   41330   65587   91278   38568  116473  351743  211100
River Rch & RM=WFSJ Main,Reach-1         ,196239
   42621   68117   94658   40242  121530  367015  216831
River Rch & RM=WFSJ Main,Reach-1         ,176000
   43650   68879   96125   40533  122407  369662  215125
River Rch & RM=WFSJ Main,Reach-1         ,169000
   45636   71318  100208   42517  128400  387763  221129
River Rch & RM=WFSJ Main,Reach-1         ,153000
   47210   75883  103838   44556  134558  406360  224967
River Rch & RM=WFSJ Main,Reach-1         ,140657
   48236   77756  103861   44801  135296  408587  225469
River Rch & RM=WFSJ Main,Reach-1         ,120679
   48857   78627  104935   45229  136588  412489  227295
River Rch & RM=WFSJ Main,Reach-1         ,112000
   58208   87157  126588   54815  165540  499923  269857
River Rch & RM=WFSJ Main,Reach-1         ,100000
   65354   93087  140479   58558  176842  534054  304240
River Rch & RM=WFSJ Main,Reach-1         ,81000
   65538   90909  140864   58717  177322  535503  306841
River Rch & RM=WFSJ Main,Reach-1         ,79000
   65376   90645  140413   58511  176700  533624  307363
River Rch & RM=WFSJ Main,Reach-1         ,69357
   65219   90367  139918   58277  175994  531494  305848
River Rch & RM=WFSJ Main,Reach-1         ,61268
   65591   90029  140339   58016  175206  529112  309549
River Rch & RM=WFSJ Main,Reach-1         ,53139
   76227  103412  166507   69548  210030  634282  376078
River Rch & RM=WFSJ Main,Reach-1         ,46149
   79550  109985  170240   73939  223293  674334  399468
River Rch & RM=WFSJ Main,Reach-1         ,35030
   79184  109417  169295   73501  221970  670339  396808
River Rch & RM=WFSJ Main,Reach-1         ,29279
   78525  108388  167575   72698  219545  663014  394235
River Rch & RM=WFSJ Main,Reach-1         ,17000
   78081  107700  166434   72170  217949  658195  393369
River Rch & RM=WFSJ Main,Reach-1         ,11416
   79349  109250  168644   73049  220605  666218  392449
River Rch & RM=WFSJ Main,Reach-1         ,4000
   79103  108873  168022   72762  219737  663596  390710
Boundary for River Rch & Prof#=WFSJ Main,Reach-1         , 1
Up Type= 0
Dn Type= 3
Dn Slope=0.0002
Boundary for River Rch & Prof#=WFSJ Main,Reach-1         , 2
Up Type= 0
Dn Type= 3
Dn Slope=0.0002
Boundary for River Rch & Prof#=WFSJ Main,Reach-1         , 3
Up Type= 0
Dn Type= 3
Dn Slope=0.0002
Boundary for River Rch & Prof#=WFSJ Main,Reach-1         , 4
Up Type= 0
Dn Type= 3
Dn Slope=0.0002
Boundary for River Rch & Prof#=WFSJ Main,Reach-1         , 5
Up Type= 0
Dn Type= 3
Dn Slope=0.0002
Boundary for River Rch & Prof#=WFSJ Main,Reach-1         , 6
Up Type= 0
Dn Type= 3
Dn Slope=0.0002
Boundary for River Rch & Prof#=WFSJ Main,Reach-1         , 7
Up Type= 0
Dn Type= 3
Dn Slope=0.0002
DSS Import GetInterval= 0
DSS Import GetPeak= 0
DSS Import FillOption= 0

--- WFSJ Main.g01 (geometry) ---

Geom Title=Existing Conditions
Program Version=4.10

River Reach=WFSJ Main       ,Reach-1
Reach XY= 30
      3707123.23     10232721.84      3718159.19     10251114.99
       3727229.4     10253027.01      3752230.38     10247804.85
      3764106.22     10226786.19       3767453.1      10210161.4
      3776625.36     10203720.49      3775311.79     10195132.45
      3787308.32     10184734.02      3791941.05     10168139.34
      3789332.49     10146084.65      3801462.57     10122862.83
      3808096.84     10122819.21      3812977.85     10114166.98
      3816807.03     10114872.96      3815178.23     10105016.84
      3827071.82     10090292.25      3837638.14     10087944.41
      3855198.83     10076909.22      3860802.62     10059852.95
      3874647.25     10052042.01      3883056.55      10040101.6
      3883251.71     10032345.01      3894234.56      10027939.1
      3901478.43     10010139.79      3910812.66     10007581.09
       3942418.2     10013698.49      3945205.69     10001061.19
      3936326.63      9984146.92      3946578.23      9970696.84

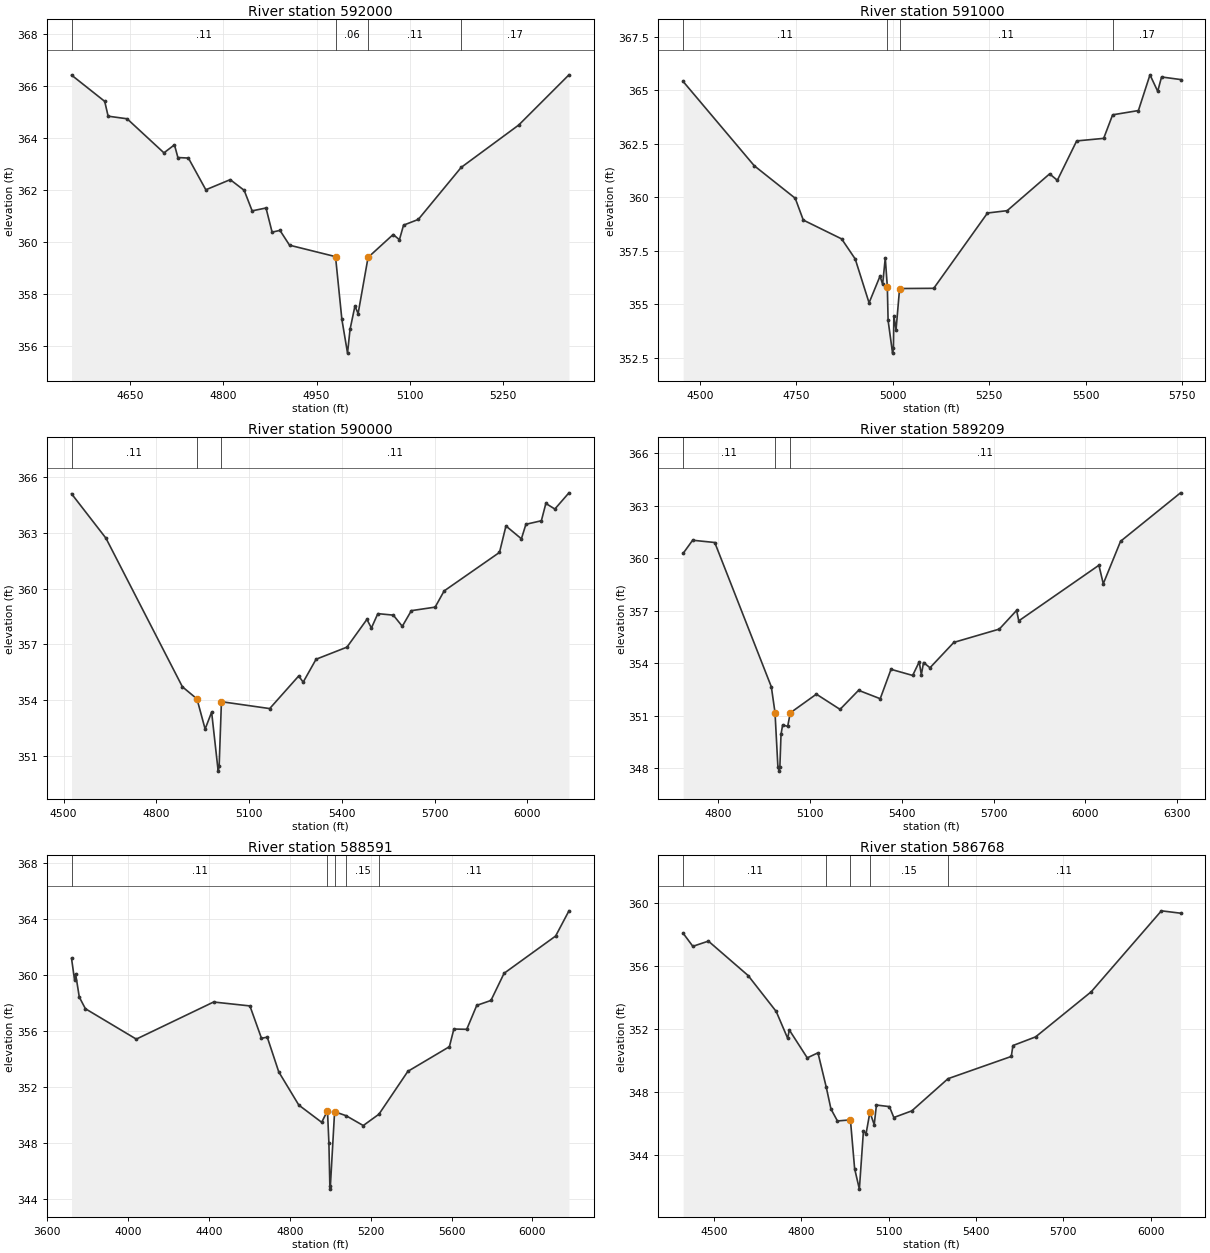
Type RM Length L Ch R = 1 ,592000  ,1000,1000,1000
BEGIN DESCRIPTION:
WFSJ Main 581.0
END DESCRIPTION:
XS GIS Cut Line= 3
      3707117.85     10233111.08      3707314.96     10232713.57
      3707267.86      10232361.1
#Sta/Elev= 30
  4556.3  366.43  4609.6  365.42  4615.1  364.85  4645.6  364.75  4704.8  363.44
  4721.7  363.75  4727.2  363.26  4744.1  363.24  4772.1  362.02  4811.3  362.41
  4833.7     362  4846.5  361.21  4868.8  361.32  4878.6  360.39  4891.2  360.46
  4906.6  359.89  4980.5  359.45  4990.7  357.04  4999.8  355.74  5003.8  356.65
  5011.7  357.55  5016.8  357.26  5032.8  359.42  5073.1   360.3  5083.2   360.1
  5089.8  360.66  5113.5  360.88  5182.4  362.88  5274.9  364.51  5355.6  366.44
#Mann= 4 ,-1 , 0
  4556.3     .11       0  4980.5     .06       0  5032.8     .11       0
  5182.4     .17       0
Bank Sta=4980.5,5032.8
XS Rating Curve= 0 ,0
Exp/Cntr=0.3,0.1

Type RM Length L Ch R = 1 ,591000  ,1000,1000,1000
BEGIN DESCRIPTION:
WFSJ Main 580.0
END DESCRIPTION:
XS GIS Cut Line= 4
      3707517.82     10233411.11      3707880.34     10233006.84
      3708001.94     10232784.03      3707990.63      10232291.9
#Sta/Elev= 30
    4457  365.42  4641.3  361.48  4747.5  359.96  4768.4  358.94  4867.8  358.06
    4903  357.12  4938.9  355.07  4967.3  356.32    4974  355.94  4980.9  357.17
 4986.25  355.81  4988.2  354.25  4999.8  352.72    5002  352.97  5003.1  354.47
  5008.8  353.81    5018  355.74  5106.5  355.75  5245.8  359.27  5296.8  359.38
  5406.8   361.1  5426.8   360.8  5476.9  362.64  5546.9  362.76  5570.1  363.86
  5636.9  364.06  5666.9  365.73  5686.9  364.96  5696.9  365.63  5746.1  365.51
#Mann= 4 ,-1 , 0
    4457     .11       0 4986.25     .06       0    5018     .11       0
  5570.1     .17       0
Bank Sta=4986.25,5018
XS Rating Curve= 0 ,0
Exp/Cntr=0.3,0.1

Type RM Length L Ch R = 1 ,590000  ,791,791,791
BEGIN DESCRIPTION:
WFSJ Main 579.0
END DESCRIPTION:
XS GIS Cut Line= 3
      3707826.56     10233740.08      3708278.23     10233594.99
      3709183.52     10232911.88
#Sta/Elev= 30
  4525.6  365.09    4637   362.7  4884.1  354.72  4931.2  354.07  4957.6  352.45
  4978.6  353.36  4999.8  350.19  5002.9  350.44  5010.3  353.92  5166.4  353.55
  5260.1   355.3  5274.7  354.97  5316.3   356.2  5416.2  356.85  5480.7  358.34
  5495.3  357.88  5516.1  358.65  5566.1  358.57  5595.2  357.97  5624.4  358.81
  5701.4     359  5730.5  359.87  5909.5  361.94  5930.4  363.36  5980.3  362.67
  5994.9  363.45  6044.9  363.64  6059.4  364.57  6088.5  364.27  6134.1  365.14
#Mann= 3 ,-1 , 0
  4525.6     .11       0  4931.2     .06       0  5010.3     .11       0
Bank Sta=4931.2,5010.3
XS Rating Curve= 0 ,0
Exp/Cntr=0.3,0.1

Type RM Length L Ch R = 1 ,589209  ,618,618,618
BEGIN DESCRIPTION:
WFSJ Main 578.0
END DESCRIPTION:
XS GIS Cut Line= 4
       3708202.8      10234260.5      3708420.56     10234116.27
      3708528.05     10233830.59      3709266.33     10233072.51
#Sta/Elev= 30
    4686  360.27  4717.1  361.02  4789.3  360.89  4974.1  352.64  4986.1  351.17
  4995.5  348.07  4999.8  347.82    5002  348.07  5005.7  349.92    5011  350.46
  5027.5  350.38  5035.9  351.15  5121.2  352.22  5198.5  351.35    5259  352.44
  5329.7  351.96    5365  353.64  5435.7  353.29  5457.1  354.07    5464  353.33
  5471.2  354.03  5492.3  353.73  5570.2  355.18  5718.7  355.94  5775.2  357.01
  5782.2  356.41    6044  359.59  6058.2  358.53  6114.7  360.96  6310.6  363.73
#Mann= 3 , 0 , 0
    4686     .11       0  4986.1     .06       0  5035.9     .11       0
Bank Sta=4986.1,5035.9
XS Rating Curve= 0 ,0
Exp/Cntr=0.3,0.1

Type RM Length L Ch R = 1 ,588591  ,1823,1823,1823
BEGIN DESCRIPTION:
Mapping XS e04d3abc
END DESCRIPTION:
XS GIS Cut Line= 4
      3707689.68     10234474.16      3708444.84     10234560.96
      3708983.03     10234109.57      3709625.37      10233345.7
#Sta/Elev= 30
  3720.2  361.21  3735.2  359.67  3740.3  360.11  3758.6  358.45  3788.8  357.62
  4040.5  355.45    4423   358.1  4602.6  357.82  4659.8  355.51  4688.4  355.59
  4745.3  353.11  4844.5  350.74  4957.7  349.51  4986.3  350.34  4993.3  348.05
    4998  344.99  4999.8  344.74  5021.5  350.27  5078.7  349.98  5163.3  349.28
  5240.9  350.09  5383.9  353.15  5589.4  354.91  5611.5  356.17  5675.2  356.15
  5724.7  357.86  5794.9  358.21  5859.9  360.15  6114.9  362.81  6180.8  364.61
#Mann= 5 ,-1 , 0
  3720.2     .11       0  4986.3     .06       0  5021.5     .11       0
  5078.7     .15       0  5240.9     .11       0
Bank Sta=4986.3,5021.5
XS Rating Curve= 0 ,0
Exp/Cntr=0.3,0.1

Type RM Length L Ch R = 1 ,586768  ,267,267,267
BEGIN DESCRIPTION:
WFSJ Main 577.0
END DESCRIPTION:
XS GIS Cut Line= 4
      3708674.24     10234862.53      3708937.43       10234970.
      3709361.91     10234760.37      3710213.92     10234337.93
#Sta/Elev= 30
  4394.4  358.07  4427.8  357.24  4481.2  357.57  4617.6  355.39  4714.2  353.11
  4753.5  351.41  4759.1  351.94  4820.8  350.17  4857.6  350.49  4886.2   348.3
  4902.2  346.93  4924.5  346.17  4969.1  346.24  4983.5  343.15  4999.8  341.85
  5013.8  345.54  5022.8  345.36  5036.1  346.73  5050.8  345.93  5058.4  347.18
    5103  347.08  5118.2  346.39  5179.9  346.81  5304.3  348.85  5521.7  350.26
  5527.3  350.95  5605.2   351.5  5796.3  354.36  6037.3  359.49  6103.1  359.34
#Mann= 5 ,-1 , 0
  4394.4     .11       0  4886.2     .15       0  4969.1     .09       0
  5036.1     .15       0  5304.3     .11       0
Bank Sta=4969.1,5036.1
XS Rating Curve= 0 ,0
Exp/Cntr=0.3,0.1

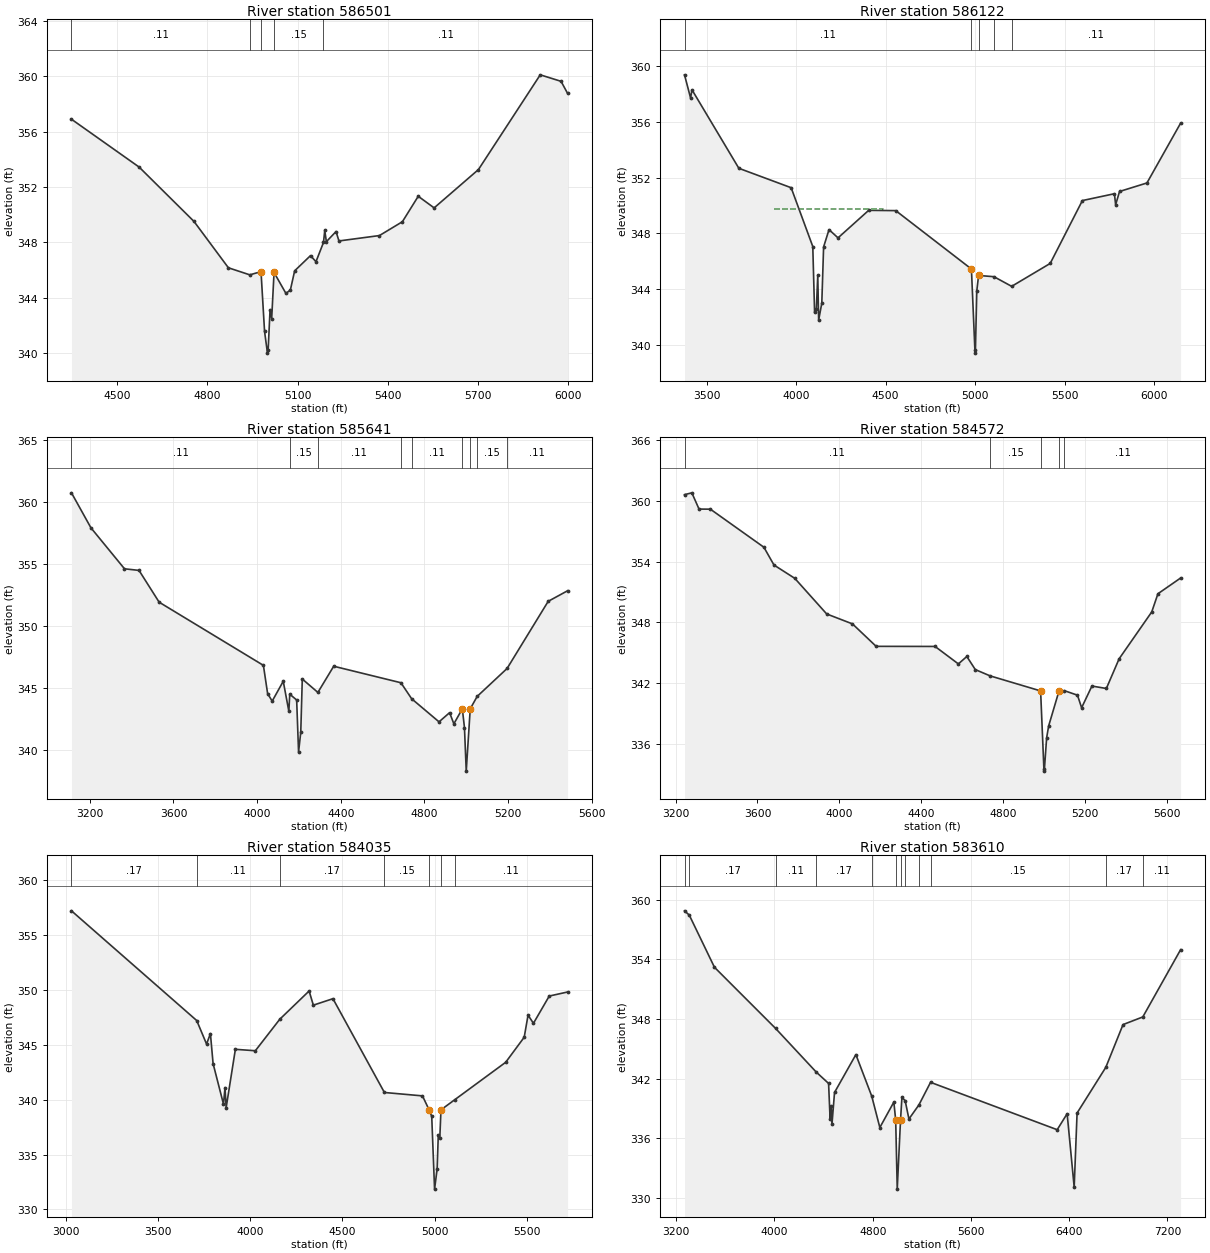
Type RM Length L Ch R = 1 ,586501  ,379,379,379
BEGIN DESCRIPTION:
WFSJ Main 576.0
END DESCRIPTION:
XS GIS Cut Line= 3
      3708759.96     10234983.91      3709034.22      10235133.2
      3710267.82     10234611.08
#Sta/Elev= 30
  4347.2  356.89  4572.5  353.43  4755.2   349.5  4869.7  346.15  4940.9  345.64
  4978.3  345.87  4990.1  341.55  4999.8  339.98    5002  340.18  5008.4  343.12
  5013.8  342.48  5021.7  345.81  5061.2   344.3    5076  344.54  5090.3  345.93
  5143.1  347.03  5161.3  346.59  5186.3  347.98  5190.5  348.85  5195.9  348.04
  5228.1  348.77  5237.8  348.09  5372.6  348.48    5449  349.48  5501.8  351.32
  5554.7  350.48  5702.2  353.25    5908   360.1  5977.3  359.63    5999  358.76
#Mann= 5 ,-1 , 0
  4347.2     .11       0  4940.9     .15       0  4978.3     .09       0
  5021.7     .15       0  5186.3     .11       0
Bank Sta=4978.3,5021.7
XS Rating Curve= 0 ,0
Exp/Cntr=0.3,0.1

Type RM Length L Ch R = 1 ,586122  ,481,481,481
BEGIN DESCRIPTION:
Mapping XS b6025ac1
END DESCRIPTION:
XS GIS Cut Line= 4
      3707756.46       10235470.      3709318.94     10235272.08
       3709961.3     10235244.31      3710224.81     10234755.43
#Sta/Elev= 30
  3375.7  359.35  3409.7  357.69  3417.4  358.28  3679.5  352.66  3971.8  351.27
  4092.8  347.06  4102.9  342.35  4112.9   342.6  4120.6  345.01  4125.6  341.79
  4143.2  343.01  4153.3  347.03  4183.5  348.27  4233.9  347.68  4405.3  349.65
  4556.5  349.63  4979.6  345.45  4999.8  339.43    5002  339.63  5009.6  343.88
  5019.6  344.99  5105.6   344.9  5204.6  344.21    5420  345.85  5599.9  350.35
  5779.1  350.84  5785.7  350.05  5807.6     351  5960.8  351.61    6149  355.89
#Mann= 5 ,-1 , 0
  3375.7     .11       0  4979.6     .06       0  5019.6     .11       0
  5105.6     .15       0  5204.6     .11       0
#XS Ineff= 1 ,-1
    3875  4485.9  349.78
Permanent Ineff=
       F
Bank Sta=4979.6,5019.6
XS Rating Curve= 0 ,0
Exp/Cntr=0.3,0.1

Type RM Length L Ch R = 1 ,585641  ,1069,1069,1069
BEGIN DESCRIPTION:
Mapping XS a9c090c9
END DESCRIPTION:
XS GIS Cut Line= 3
      3707784.23     10236084.58      3709166.16     10235640.14
      3710074.37     10235491.08
#Sta/Elev= 30
  3112.3  360.74  3205.4  357.92  3365.8  354.62  3435.3  354.49  3531.5  351.93
    4030  346.84  4050.2  344.56    4072  343.96  4124.9  345.56  4151.7  343.14
  4155.9  344.52    4189  344.05  4198.1  339.86  4208.6  341.45  4215.9  345.74
  4290.5  344.66  4366.1  346.77  4687.5  345.44  4738.8  344.15  4869.7  342.29
  4920.3  343.03  4940.6  342.13  4981.1  343.34  4991.3  341.83  4999.8  338.32
  5018.9  343.34  5052.1  344.34  5195.1  346.59  5391.7     352  5484.3  352.85
#Mann= 9 ,-1 , 0
  3112.3     .11       0  4155.9     .15       0  4290.5     .11       0
  4687.5     .15       0  4738.8     .11       0  4981.1     .06       0
  5018.9     .11       0  5052.1     .15       0  5195.1     .11       0
#XS Ineff= 1 ,-1
    3920  4366.1  346.77
Permanent Ineff=
       F
Bank Sta=4981.1,5018.9
XS Rating Curve= 0 ,0
Exp/Cntr=0.3,0.1

Type RM Length L Ch R = 1 ,584572  ,537,537,537
BEGIN DESCRIPTION:
WFSJ Main 575.0
END DESCRIPTION:
XS GIS Cut Line= 4
      3707655.77     10236584.58      3709256.44     10236160.97
      3709468.25     10236174.86      3710017.82     10236111.07
#Sta/Elev= 30
  3243.9  360.59  3279.7  360.77  3314.8  359.17  3370.2  359.16  3631.4  355.41
  3680.5  353.66    3782  352.35  3937.8  348.84  4063.7  347.86  4179.2  345.65
  4466.7  345.64  4580.5  343.92  4621.8  344.65  4663.2  343.36  4735.6  342.74
  4981.9  341.26    4998  333.56  4999.8  333.36  5011.3  336.64  5021.3  337.82
  5071.5  341.24  5098.3  341.28  5161.9  340.84    5182   339.6  5232.3  341.74
  5302.8   341.5    5365  344.42  5524.3  349.04  5554.5  350.83  5665.2  352.38
#Mann= 5 ,-1 , 0
  3243.9     .11       0  4735.6     .15       0  4981.9     .09       0
  5071.5     .15       0  5098.3     .11       0
Bank Sta=4981.9,5071.5
XS Rating Curve= 0 ,0
Exp/Cntr=0.3,0.1

Type RM Length L Ch R = 1 ,584035  ,425,425,425
BEGIN DESCRIPTION:
WFSJ Main 574.0
END DESCRIPTION:
XS GIS Cut Line= 3
      3707940.44     10237768.64      3709357.14     10236699.17
      3710092.17     10236156.67
#Sta/Elev= 30
    3032  357.19  3710.8   347.2  3764.1  345.06    3785  346.01  3799.5  343.28
  3855.8  339.59  3864.1   341.1  3870.3  339.27  3920.3  344.58  4028.5  344.45
    4161  347.32  4319.9  349.89  4342.8   348.6    4449  349.19  4727.9  340.65
  4934.3  340.34  4969.8  339.08  4984.4  338.48  4999.8  331.85  5013.7  333.68
  5019.9  336.75  5028.3  336.55  5034.5  339.07  5109.9     340  5385.3   343.4
  5485.6  345.68  5506.4  347.69  5535.7  346.95  5621.3  349.43  5720.6   349.8
#Mann= 7 ,-1 , 0
    3032     .17       0  3710.8     .11       0    4161     .17       0
  4727.9     .15       0  4969.8     .09       0  5034.5     .15       0
  5109.9     .11       0
#XS Ineff= 1 ,-1
    3300  4319.9  349.89
Permanent Ineff=
       F
Bank Sta=4969.8,5034.5
XS Rating Curve= 0 ,0
Exp/Cntr=0.3,0.1

Type RM Length L Ch R = 1 ,583610  ,688,688,688
BEGIN DESCRIPTION:
Mapping XS 853c9f54
END DESCRIPTION:
XS GIS Cut Line= 3
      3708124.52     10237924.85      3709780.75     10236810.28
      3711801.56      10236508.2
#Sta/Elev= 30
  3267.6  358.88  3306.4  358.45  3511.4   353.2  4008.8  347.05  4341.1  342.64
  4440.8  341.51  4453.2  337.91  4462.2  339.23  4468.2  337.38  4489.2   340.6
  4663.1  344.41  4792.1  340.23  4858.1  337.07  4972.1  339.63  4987.1  337.85
  4999.8  330.87 5026.61  337.83    5038  340.11  5064.4  339.77    5095  337.93
  5176.5  339.35  5271.1  341.62  6302.2  336.85  6383.3  338.46  6440.6  331.07
  6464.2  338.53  6698.2  343.13  6838.3  347.43  6999.4   348.2  7307.2  354.97
#Mann= 12 ,-1 , 0
  3267.6     .11       0  3306.4     .17       0  4008.8     .11       0
  4341.1     .17       0  4792.1     .11       0  4987.1     .09       0
 5026.61     .11       0  5064.4     .15       0  5176.5     .15       0
  5271.1     .15       0  6698.2     .17       0  6999.4     .11       0
#XS Ineff= 2 ,-1
    4045  4663.1  344.41  5271.1    6650  341.62
Permanent Ineff=
       F       F
Bank Sta=4987.1,5026.61
XS Rating Curve= 0 ,0
Exp/Cntr=0.3,0.1

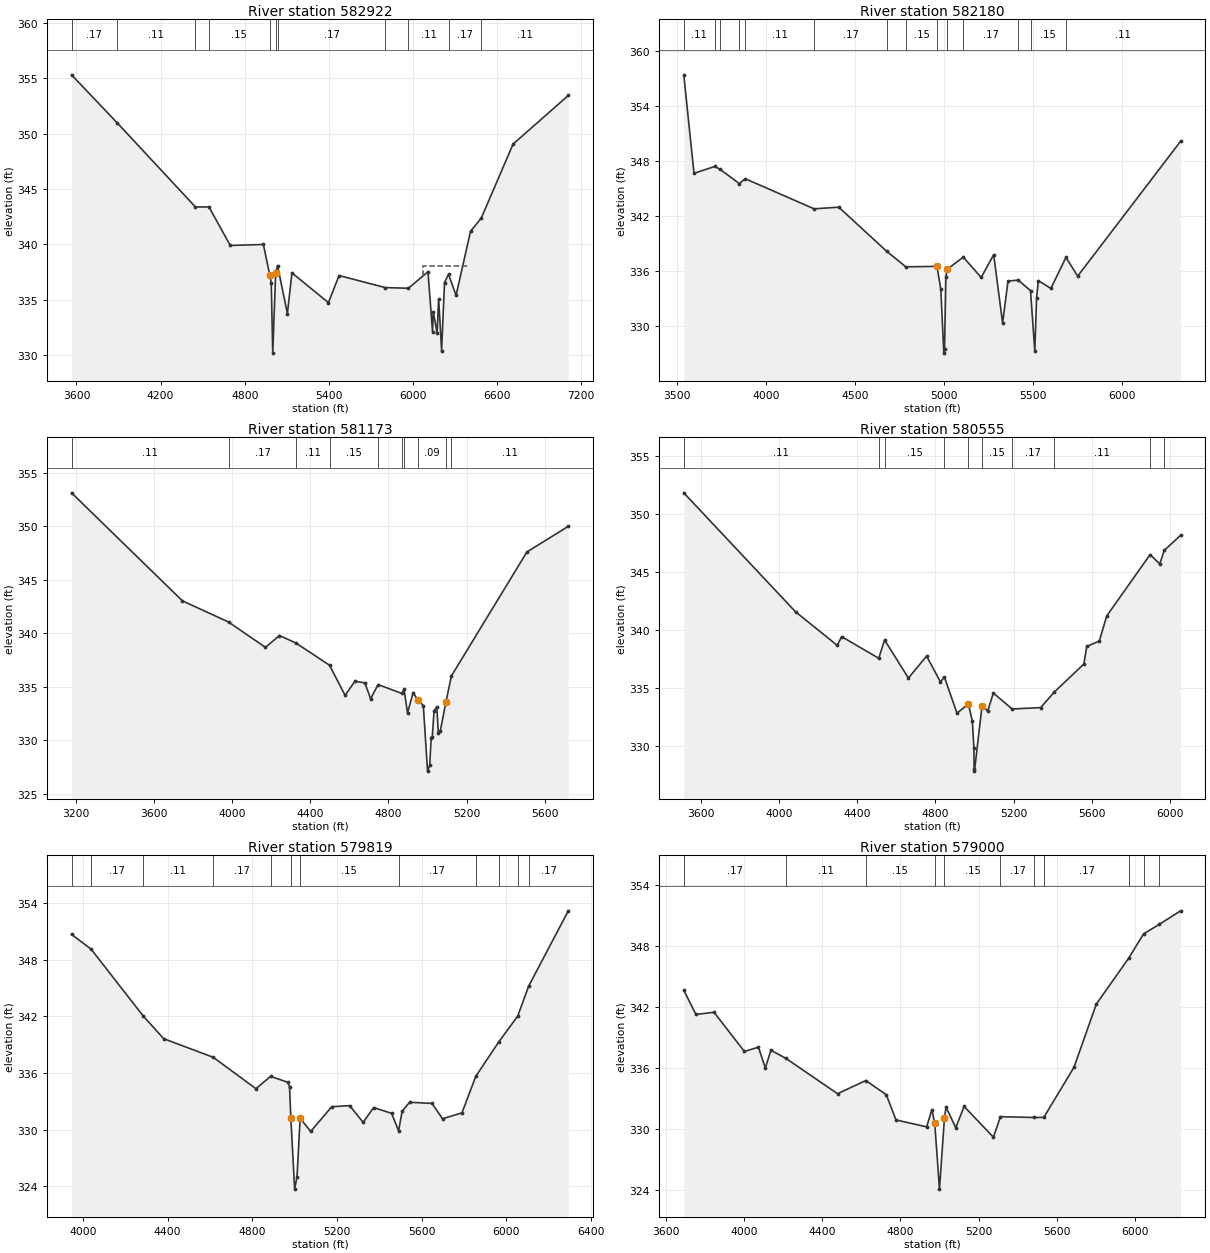
Type RM Length L Ch R = 1 ,582922  ,742,742,742
BEGIN DESCRIPTION:
WFSJ Main 573.0
END DESCRIPTION:
XS GIS Cut Line= 3
      3708516.88     10238035.96      3709714.77     10237351.95
      3711780.78     10236709.57
#Sta/Elev= 30
  3564.6   355.3  3887.9     351  4448.8  343.38  4544.5  343.39  4696.9  339.91
    4933     340  4978.7  337.23  4989.1  336.55  4999.8   330.2  5020.6  337.46
  5033.7   338.1  5104.3  333.77  5136.6  337.44    5397  334.75  5472.6   337.2
  5802.2  336.11  5967.3  336.05  6106.7  337.54  6139.3  332.13  6144.5  333.94
  6171.8  332.02    6183   335.1  6203.9  330.43  6224.9  336.56  6253.2  337.31
  6307.2  335.41  6410.1  341.18  6486.6  342.37  6713.5  349.05  7107.6  353.44
#Mann= 11 ,-1 , 0
  3564.6     .17       0  3887.9     .11       0  4448.8     .17       0
  4544.5     .15       0  4978.7     .09       0  5020.6     .15       0
  5033.7     .17       0  5802.2     .17       0  5967.3     .11       0
  6253.2     .17       0  6486.6     .11       0
#XS Ineff= 1 ,-1
  6067.8    6400   338.1
Permanent Ineff=
       T
Bank Sta=4978.7,5020.6
XS Rating Curve= 0 ,0
Exp/Cntr=0.3,0.1

Type RM Length L Ch R = 1 ,582180  ,1007,1007,1007
BEGIN DESCRIPTION:
WFSJ Main 572.0
END DESCRIPTION:
XS GIS Cut Line= 3
      3709225.22     10238459.56      3710367.55     10237424.86
      3711613.43     10237299.93
#Sta/Elev= 30
  3537.6  357.36  3595.1  346.65  3712.2  347.39  3742.4  347.07  3850.2  345.52
  3882.8  346.06  4270.7  342.78  4409.1  342.96  4678.5  338.16  4786.1  336.47
  4961.3  336.52  4982.9  334.02  4999.8  327.08  5003.8  327.58  5011.3  335.33
    5018   336.2  5109.3  337.52  5209.8  335.31  5280.2  337.79  5330.4  330.36
  5360.6  334.91  5418.3  335.03  5487.3  333.87  5511.3  327.28  5521.4  333.11
  5531.4  334.96  5601.8  334.12  5686.5  337.49  5752.5  335.46    6331  350.13
#Mann= 14 ,-1 , 0
  3537.6     .11       0  3712.2     .17       0  3742.4     .11       0
  3850.2     .17       0  3882.8     .11       0  4270.7     .17       0
  4678.5     .17       0  4786.1     .15       0  4961.3     .09       0
    5018     .15       0  5109.3     .17       0  5418.3     .17       0
  5487.3     .15       0  5686.5     .11       0
#XS Ineff= 2 ,-1
                          5280.2    5850  337.79
Permanent Ineff=
       F       F
Bank Sta=4961.3,5018
XS Rating Curve= 0 ,0
Exp/Cntr=0.3,0.1

Type RM Length L Ch R = 1 ,581173  ,618,618,618
BEGIN DESCRIPTION:
WFSJ Main 571.0
END DESCRIPTION:
XS GIS Cut Line= 3
      3709475.17     10238730.43      3710843.25     10237765.14
      3711633.87     10237407.97
#Sta/Elev= 30
  3178.2  353.14  3745.7  343.04  3981.7  341.06  4170.6  338.69    4242   339.8
  4328.1  339.08  4498.3  337.02  4578.1   334.2  4628.6  335.53  4679.1  335.37
  4708.7  333.89  4746.7  335.21  4868.9  334.38  4879.8  334.78  4897.4  332.55
    4926  334.46  4949.2  333.79  4978.3  333.25  4999.8  327.12  5011.2  327.68
  5018.5  330.25    5024  330.28  5033.2  332.76  5047.1  333.12  5055.1  330.71
  5064.7  330.83  5093.4  333.54    5122  336.02  5508.3  347.61  5720.1  350.01
#Mann= 10 ,-1 , 0
  3178.2     .11       0  3981.7     .17       0  4328.1     .11       0
  4498.3     .15       0  4746.7     .15       0  4868.9     .17       0
  4879.8     .15       0  4949.2     .09       0  5093.4     .15       0
    5122     .11       0
Bank Sta=4949.2,5093.4
XS Rating Curve= 0 ,0
Exp/Cntr=0.3,0.1

Type RM Length L Ch R = 1 ,580555  ,736,736,736
BEGIN DESCRIPTION:
Mapping XS 067ed6a7
END DESCRIPTION:
XS GIS Cut Line= 3
      3709836.31     10239112.35      3711527.27     10237765.14
      3711732.14     10237449.16
#Sta/Elev= 30
  3514.4   351.8  4085.7  341.57  4298.7  338.69  4321.2  339.44  4510.6  337.58
  4540.6  339.15  4662.3  335.88  4755.2  337.77  4825.6  335.56  4846.4  335.95
  4910.5  332.86  4968.8  333.65    4989  332.17    4997  329.87    4998  328.08
  4999.8  327.88  5038.6  333.51  5067.5  333.05  5096.3  334.59  5192.4  333.22
  5338.1  333.34  5407.9  334.68  5559.1  337.09  5573.6   338.6  5637.6  339.06
  5675.7  341.22  5897.2  346.49  5946.7  345.69  5969.7  346.85    6053  348.15
#Mann= 10 ,-1 , 0
  3514.4     .11       0  4510.6     .17       0  4540.6     .15       0
  4846.4     .15       0  4968.8     .09       0  5038.6     .15       0
  5192.4     .17       0  5407.9     .11       0  5897.2     .17       0
  5969.7     .11       0
Bank Sta=4968.8,5038.6
XS Rating Curve= 0 ,0
Exp/Cntr=0.3,0.1

Type RM Length L Ch R = 1 ,579819  ,819,819,819
BEGIN DESCRIPTION:
WFSJ Main 570.0
END DESCRIPTION:
XS GIS Cut Line= 3
      3710267.82      10239461.1      3711235.61     10238744.31
      3712067.87     10237961.05
#Sta/Elev= 30
  3945.6  350.71  4038.5  349.13  4284.4  342.05  4381.2  339.64  4615.2  337.67
  4816.9  334.34  4886.3  335.65  4967.2  335.02  4975.6  334.56  4981.8  331.24
  4999.8  323.69  5011.1  324.99  5025.7   331.2  5075.8  329.81  5175.1  332.43
    5260  332.54  5323.6  330.77  5372.9  332.34  5457.9  331.73    5491  329.87
  5507.7  331.95  5542.8   332.9  5648.8  332.78  5698.6  331.15  5790.5  331.78
  5855.6  335.65  5964.6  339.31  6053.9  342.04  6105.3  345.21  6292.8   353.2
#Mann= 12 ,-1 , 0
  3945.6     .11       0  4038.5     .17       0  4284.4     .11       0
  4615.2     .17       0  4886.3     .15       0  4981.8     .09       0
  5025.7     .15       0    5491     .17       0  5855.6     .11       0
  5964.6     .17       0  6053.9     .11       0  6105.3     .17       0
Bank Sta=4981.8,5025.7
XS Rating Curve= 0 ,0
Exp/Cntr=0.3,0.1

Type RM Length L Ch R = 1 ,579000  ,1000,1000,1000
BEGIN DESCRIPTION:
WFSJ Main 569.0
END DESCRIPTION:
XS GIS Cut Line= 3
       3710801.6     10240181.78      3711620.99     10239160.57
      3712377.67     10238185.67
#Sta/Elev= 30
  3690.7  343.66    3753  341.27  3845.5  341.49    4001  337.63    4073  338.05
  4108.2     336    4137  337.75  4214.4  336.94  4477.9  333.47  4622.7  334.77
  4727.5  333.37  4777.1  330.89    4934  330.21  4961.2  331.91  4975.6  330.54
  4999.8  324.08  5025.2  331.06  5033.3  332.15  5083.1  330.13    5126  332.22
  5275.9  329.19  5311.9  331.21  5485.4  331.13  5533.8  331.14  5688.6  336.08
  5802.7  342.29    5970  346.85  6044.4   349.2  6125.2  350.14  6234.1  351.47
#Mann= 11 ,-1 , 0
  3690.7     .17       0  4214.4     .11       0  4622.7     .15       0
  4975.6     .09       0  5025.2     .15       0  5311.9     .17       0
  5485.4     .11       0  5533.8     .17       0    5970     .11       0
  6044.4     .17       0  6125.2     .11       0
Bank Sta=4975.6,5025.2
XS Rating Curve= 0 ,0
Exp/Cntr=0.3,0.1