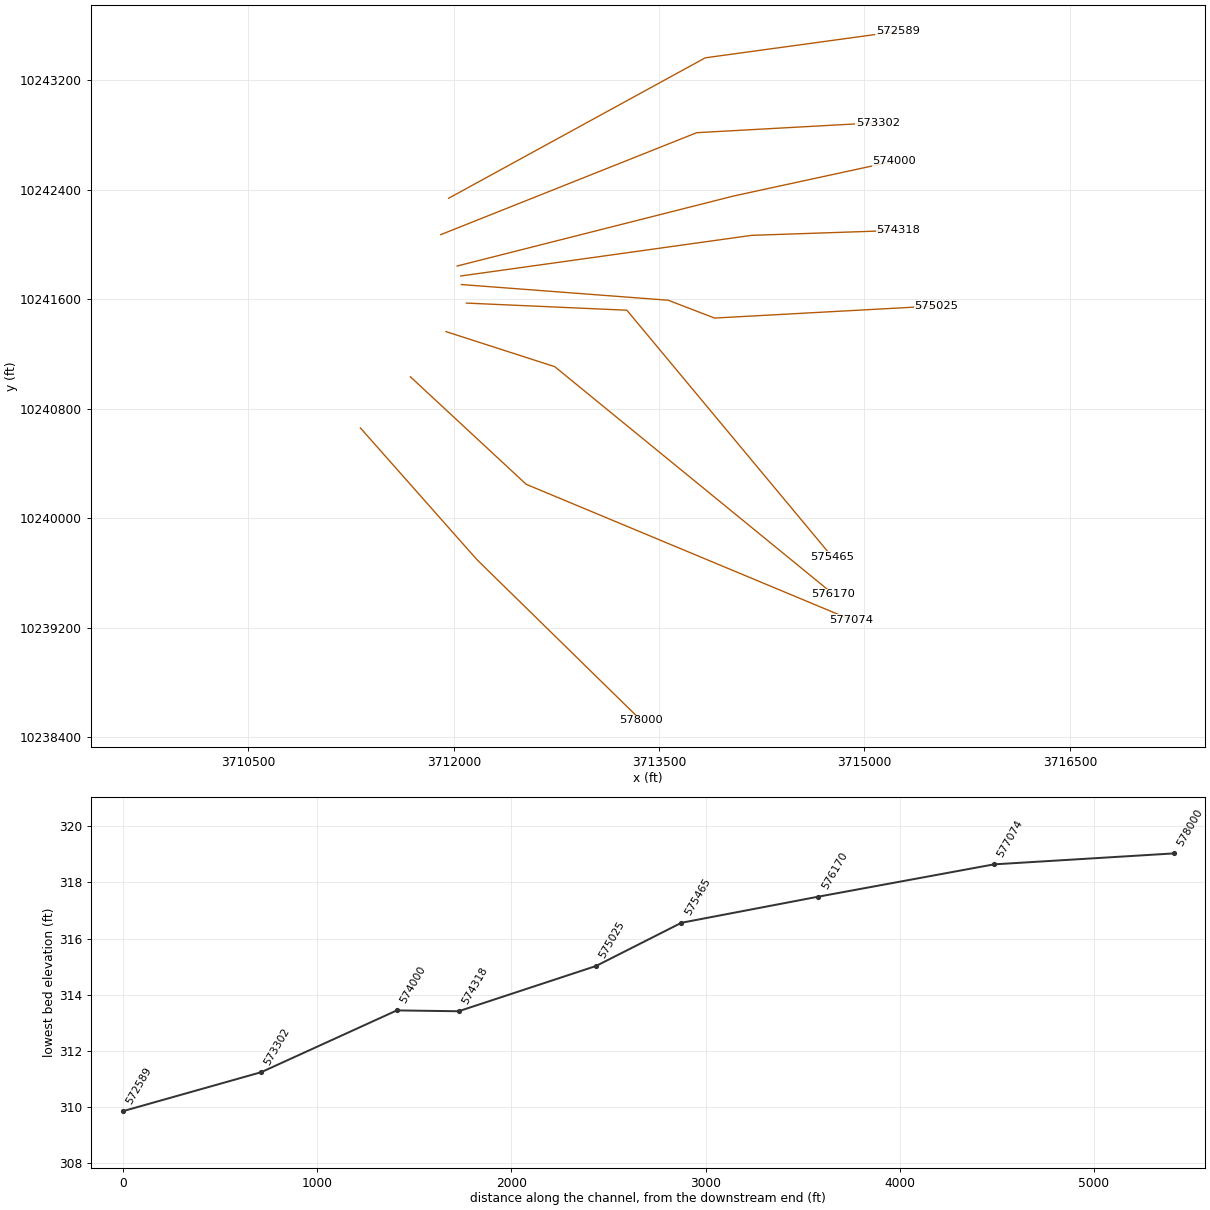
HEC-RAS study WFSJ Main.prj: WFSJ Main Base Level Engineering

--- WFSJ Main.g01 (geometry) --- (continued)

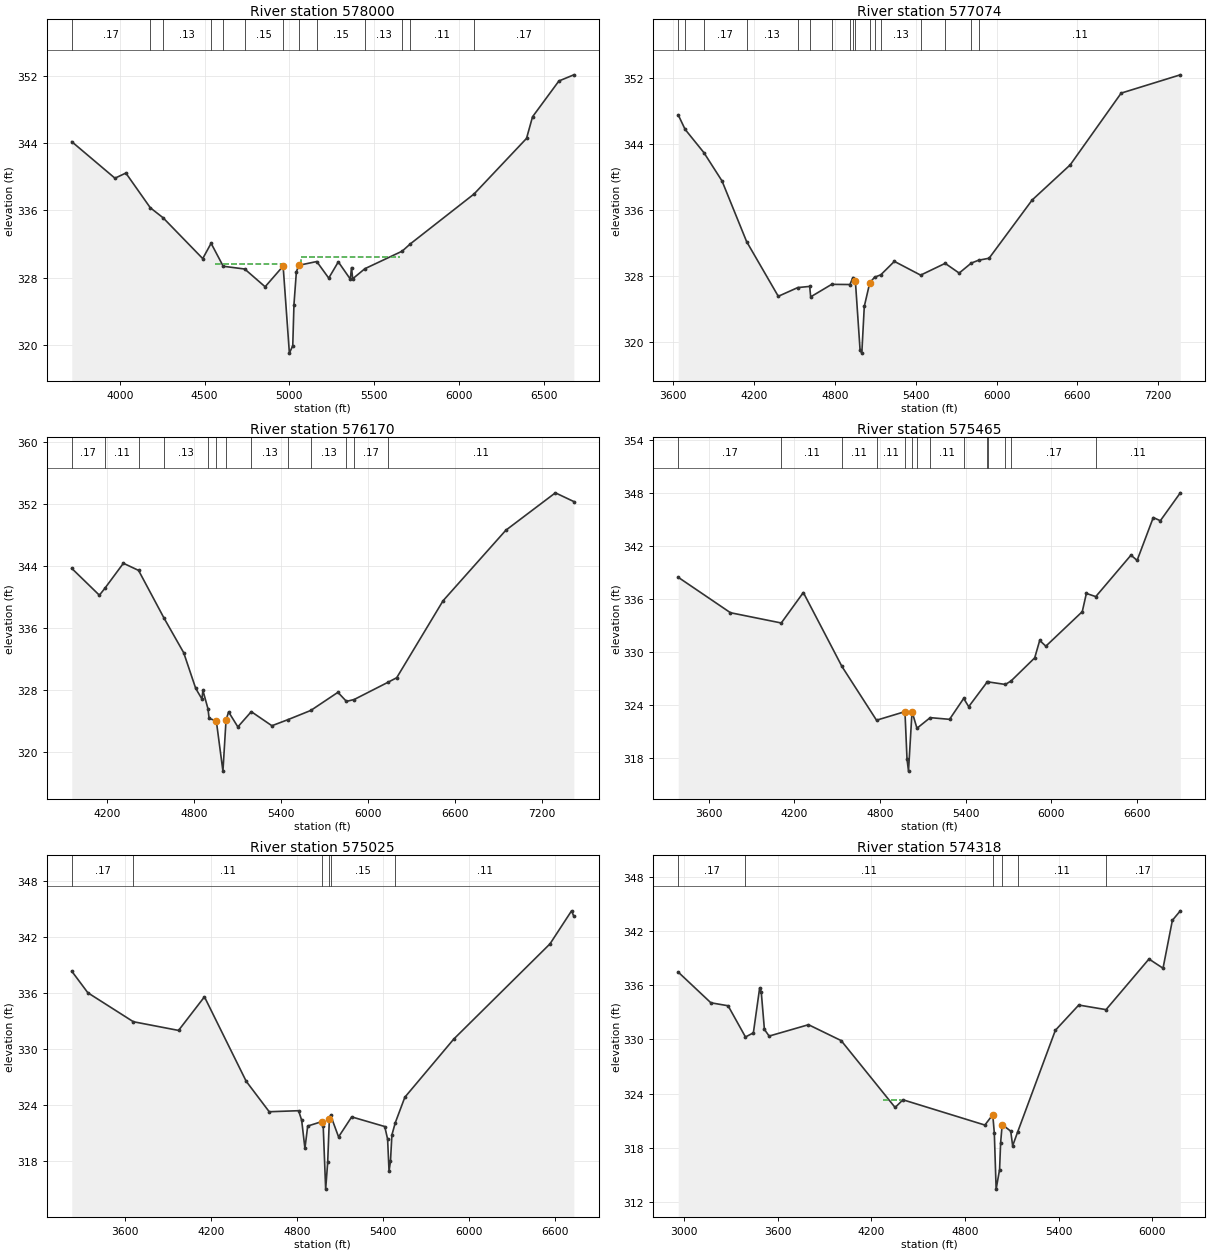
Type RM Length L Ch R = 1 ,578000  ,926,926,926
BEGIN DESCRIPTION:
WFSJ Main 568.0
END DESCRIPTION:
XS GIS Cut Line= 3
      3711317.83     10240661.09      3712168.58     10239699.66
      3713367.26     10238525.84
#Sta/Elev= 30
  3716.2  344.17  3970.9  339.83  4035.3  340.44  4179.6  336.31  4254.5  335.13
  4488.7  330.27    4538  332.09  4609.5  329.36  4736.3  329.03  4856.7  326.92
  4962.9  329.38  4999.8  319.03  5019.7  319.91  5026.8  324.81    5041  328.69
    5055  329.47  5161.1  329.92  5231.9  327.95  5288.4  329.88  5359.2  327.83
  5366.2   329.2  5373.3  327.87  5445.2  329.07  5664.8  331.15  5713.2  332.02
    6089  337.95  6398.6  344.56    6434  347.13  6589.6  351.39  6677.7  352.12
#Mann= 13 ,-1 , 0
  3716.2     .17       0  4179.6     .11       0  4254.5     .13       0
    4538     .13       0  4609.5     .15       0  4736.3     .15       0
  4962.9     .09       0    5055     .15       0  5161.1     .15       0
  5445.2     .13       0  5664.8     .17       0  5713.2     .11       0
    6089     .17       0
#XS Ineff= 2 ,-1
  5069.1    5650  330.49    4560  4956.3  329.68
Permanent Ineff=
       T       T
Bank Sta=4962.9,5055
XS Rating Curve= 0 ,0
Exp/Cntr=0.3,0.1

Type RM Length L Ch R = 1 ,577074  ,904,904,904
BEGIN DESCRIPTION:
WFSJ Main 567.0
END DESCRIPTION:
XS GIS Cut Line= 3
      3711682.66      10241035.1      3712529.01     10240249.51
      3714902.99       10239260.
#Sta/Elev= 30
  3637.2  347.56  3688.1  345.81  3827.8  342.98    3962  339.55  4144.8  332.18
  4379.8  325.54  4524.7   326.6    4613  326.74  4620.2  325.47  4776.1  326.99
  4911.5  326.97  4933.9  327.82  4952.3  327.34    4987  318.99  4999.8  318.64
  5018.2  324.31  5058.5  327.16    5094  327.85  5140.8  328.15  5241.5  329.78
  5436.5  328.11  5618.5  329.54  5722.4  328.36  5812.1  329.57  5866.5  329.92
  5944.5  330.16  6264.1  337.23  6546.8   341.5    6925  350.21  7363.9  352.43
#Mann= 17 ,-1 , 0
  3637.2     .17       0  3688.1     .11       0  3827.8     .17       0
  4144.8     .13       0  4524.7     .13       0    4613     .15       0
  4776.1     .15       0  4911.5     .15       0  4933.9     .13       0
  4952.3     .08       0  5058.5     .13       0    5094     .15       0
  5140.8     .13       0  5436.5     .17       0  5618.5     .11       0
  5812.1     .17       0  5866.5     .11       0
#XS Ineff= 2 ,-1
  5241.5    5940  329.78    4280  4933.9  327.82
Permanent Ineff=
       T       T
Bank Sta=4952.3,5058.5
XS Rating Curve= 0 ,0
Exp/Cntr=0.3,0.1

Type RM Length L Ch R = 1 ,576170  ,705,705,705
BEGIN DESCRIPTION:
WFSJ Main 566.0
END DESCRIPTION:
XS GIS Cut Line= 3
      3711943.08     10241364.97      3712737.34     10241108.89
      3714772.91     10239446.59
#Sta/Elev= 30
  3957.3  343.71  4147.7  340.24    4185  341.12  4313.2  344.37  4417.9  343.45
  4593.8  337.27  4729.3   332.8    4812  328.19  4855.1  326.81  4861.5  327.94
  4896.7  325.55  4904.6   324.3  4954.1     324  4999.8  317.49 5021.25  324.09
  5038.8  325.15  5102.7  323.21  5195.4  325.18  5337.5  323.36  5445.8  324.13
    5606  325.34  5792.7  327.68  5851.7  326.51  5904.7  326.75  6140.2     329
  6198.3  329.57  6517.8  339.52  6950.7  348.64  7292.5  353.48  7419.9  352.35
#Mann= 13 ,-1 , 0
  3957.3     .17       0    4185     .11       0  4417.9     .17       0
  4593.8     .13       0  4896.7     .13       0  4954.1     .08       0
 5021.25     .13       0  5195.4     .13       0  5445.8     .13       0
    5606     .13       0  5851.7     .11       0  5904.7     .17       0
  6140.2     .11       0
Bank Sta=4954.1,5021.25
XS Rating Curve= 0 ,0
Exp/Cntr=0.3,0.1

Type RM Length L Ch R = 1 ,575465  ,440,440,440
BEGIN DESCRIPTION:
WFSJ Main 565.0
END DESCRIPTION:
XS GIS Cut Line= 3
      3712092.37      10241573.3      3713264.25     10241521.22
      3714763.54     10239719.99
#Sta/Elev= 30
    3387  338.45  3752.8  334.45  4108.6  333.29  4263.3  336.73  4533.6  328.38
  4775.8  322.31    4975  323.28  4989.3  317.94  4999.8  316.56  5024.5  323.28
  5059.1   321.4  5151.7   322.6  5287.4  322.41  5386.2  324.77  5421.5  323.84
  5551.9  326.65  5556.1  326.64  5678.3  326.35  5717.9  326.74  5883.7  329.35
  5918.8  331.32  5961.8  330.67  6216.9  334.57  6245.6  336.63  6311.5  336.27
    6558  340.95    6601  340.36  6714.2   345.2  6763.7  344.84  6903.6  347.99
#Mann= 14 ,-1 , 0
    3387     .17       0  4108.6     .11       0  4533.6     .11       0
  4775.8     .11       0    4975     .07       0  5024.5     .11       0
  5059.1     .15       0  5151.7     .11       0  5386.2     .17       0
  5551.9     .11       0  5556.1     .17       0  5678.3     .11       0
  5717.9     .17       0  6311.5     .11       0
Bank Sta=4975,5024.5
XS Rating Curve= 0 ,0
Exp/Cntr=0.3,0.1

Type RM Length L Ch R = 1 ,575025  ,707,707,707
BEGIN DESCRIPTION:
Mapping XS bc753f61
END DESCRIPTION:
XS GIS Cut Line= 4
      3712055.91     10241708.72      3713566.34     10241594.13
      3713904.88     10241463.92      3715523.77     10241552.42
#Sta/Elev= 30
  3230.5  338.31  3342.8     336  3659.5  332.91  3974.6  331.98  4155.1  335.57
  4445.9  326.55  4606.4  323.29  4811.2   323.4  4832.6  322.38  4855.3  319.37
  4874.6  321.76  4971.9  322.23  4982.6  321.79  4999.8  315.02  5013.9  317.89
  5025.5  322.51  5034.5  322.91  5089.7   320.6  5181.1  322.74  5411.4  321.71
  5431.4  320.37  5441.5  316.93  5451.5  318.01  5461.5  320.82  5485.3  322.13
  5551.6  324.84  5892.1  331.05  6563.1  341.23  6713.4  344.76  6729.3  344.16
#Mann= 6 ,-1 , 0
  3230.5     .17       0  3659.5     .11       0  4971.9     .06       0
  5025.5     .11       0  5034.5     .15       0  5485.3     .11       0
Bank Sta=4971.9,5025.5
XS Rating Curve= 0 ,0
Exp/Cntr=0.3,0.1

Type RM Length L Ch R = 1 ,574318  ,318,318,318
BEGIN DESCRIPTION:
Mapping XS 8fdcb224
END DESCRIPTION:
XS GIS Cut Line= 3
      3712050.68     10241771.21      3714175.71     10242068.09
      3715248.63     10242104.55
#Sta/Elev= 30
  2961.5  337.46  3170.7  334.06  3281.2  333.73  3392.6  330.27  3443.3  330.73
  3483.7  335.72  3493.8  335.26    3514  331.11  3544.3  330.37  3796.7  331.63
  4006.1  329.87    4352  322.46  4402.5  323.31  4927.6  320.51  4978.1  321.66
  4988.2  319.61  4999.8  313.41  5021.9  315.58  5028.6  318.54  5038.6  320.57
  5093.4  319.83  5105.7  318.21  5137.5  319.73  5379.5  331.01  5529.6  333.81
  5704.4   333.3  5979.8  338.91  6069.9  337.89  6129.9   343.2  6180.7  344.25
#Mann= 6 ,-1 , 0
  2961.5     .17       0  3392.6     .11       0  4978.1     .06       0
  5038.6     .11       0  5137.5     .11       0  5704.4     .17       0
#XS Ineff= 1 ,-1
    4275  4392.4  323.32
Permanent Ineff=
       F
Bank Sta=4978.1,5038.6
XS Rating Curve= 0 ,0
Exp/Cntr=0.3,0.1

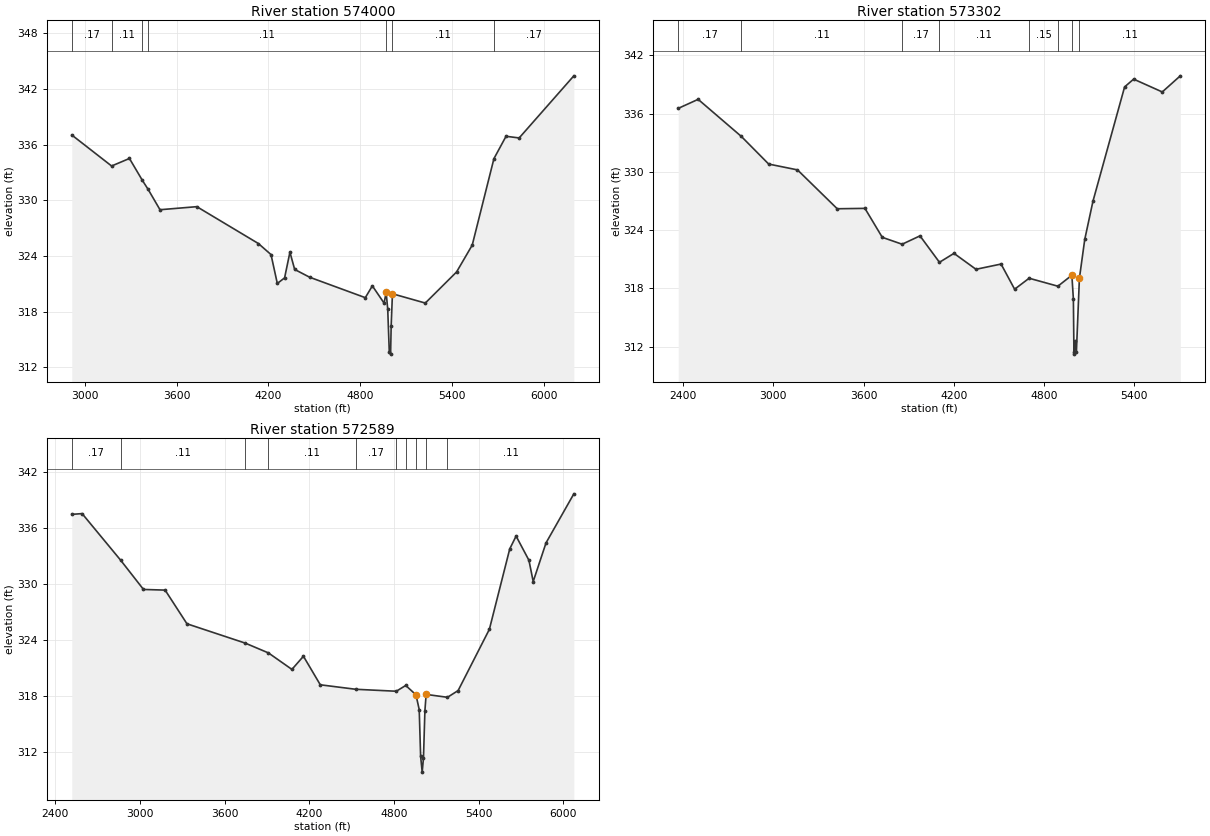
Type RM Length L Ch R = 1 ,574000  ,698,698,698
BEGIN DESCRIPTION:
WFSJ Main 564.0
END DESCRIPTION:
XS GIS Cut Line= 3
      3712024.65     10241844.13      3714046.26     10242356.01
      3715217.38     10242609.76
#Sta/Elev= 30
  2914.6  337.04  3175.1   333.7  3291.8  334.51  3376.8  332.14    3413  331.21
  3491.6  328.99  3732.5  329.32  4135.1  325.35  4217.7  324.16  4258.9  321.05
  4306.5  321.65  4341.4  324.42  4372.4  322.56  4470.5  321.72  4834.4  319.52
  4880.5  320.79  4957.4  318.93  4970.7  320.09    4981  318.29  4991.3  313.65
  4999.8  313.44  5003.5  316.47  5011.9  319.94  5226.7  318.94  5431.4  322.29
  5533.7  325.18  5675.6  334.49  5754.8   336.9  5840.7  336.72  6198.3  343.41
#Mann= 7 ,-1 , 0
  2914.6     .17       0  3175.1     .11       0  3376.8     .17       0
    3413     .11       0  4970.7     .06       0  5011.9     .11       0
  5675.6     .17       0
#XS Ineff= 1 ,-1
    4120  4341.4  324.42
Permanent Ineff=
       F
Bank Sta=4970.7,5011.9
XS Rating Curve= 0 ,0
Exp/Cntr=0.3,0.1

Type RM Length L Ch R = 1 ,573302  ,713,713,713
BEGIN DESCRIPTION:
WFSJ Main 563.0
END DESCRIPTION:
XS GIS Cut Line= 3
       3711904.9     10242073.31      3713774.67     10242818.09
      3715097.62     10242891.01
#Sta/Elev= 30
  2367.6  336.53  2499.9  337.46  2787.3  333.64  2968.9   330.8  3160.3   330.2
  3424.6   326.2  3608.7  326.24    3724  323.26  3855.9  322.55  3974.7  323.41
  4104.1  320.69  4200.7  321.61  4346.9  319.97  4513.6  320.51  4603.8  317.92
  4700.2  319.05  4891.4  318.23  4984.3  319.36  4994.4  316.91    4998  311.44
  4999.8  311.24  5004.4  312.56  5014.4  311.44  5034.4  319.04  5069.9  323.04
  5124.6  326.98  5334.9  338.74    5395  339.54  5585.3  338.22  5705.2  339.88
#Mann= 8 ,-1 , 0
  2367.6     .17       0  2787.3     .11       0  3855.9     .17       0
  4104.1     .11       0  4700.2     .15       0  4891.4     .11       0
  4984.3     .06       0  5034.4     .11       0
Bank Sta=4984.3,5034.4
XS Rating Curve= 0 ,0
Exp/Cntr=0.3,0.1

Type RM Length L Ch R = 1 ,572589  ,201,201,201
BEGIN DESCRIPTION:
WFSJ Main 562.0
END DESCRIPTION:
XS GIS Cut Line= 3
      3711962.15     10242338.91      3713837.17     10243364.97
      3715243.13     10243557.63
#Sta/Elev= 30
  2517.6  337.48  2590.9  337.56  2864.1  332.56  3025.7  329.43  3178.9  329.36
  3333.5  325.75    3746  323.68  3910.4  322.63  4077.1  320.86  4158.6  322.27
  4278.1  319.21  4529.3  318.73  4816.5  318.52  4883.3  319.14  4955.6  318.14
  4978.7  316.56  4988.8  311.54  4999.8  309.85    5009  311.38  5019.1  316.44
  5027.8  318.18  5178.8  317.87  5254.3  318.59  5475.8  325.16  5620.1  333.78
    5665  335.15  5755.9  332.56  5786.2  330.28    5877  334.42  6074.1  339.68
#Mann= 10 ,-1 , 0
  2517.6     .17       0  2864.1     .11       0    3746     .17       0
  3910.4     .11       0  4529.3     .17       0  4816.5     .11       0
  4883.3     .15       0  4955.6     .09       0  5027.8     .15       0
  5178.8     .11       0
Bank Sta=4955.6,5027.8
XS Rating Curve= 0 ,0
Exp/Cntr=0.3,0.1