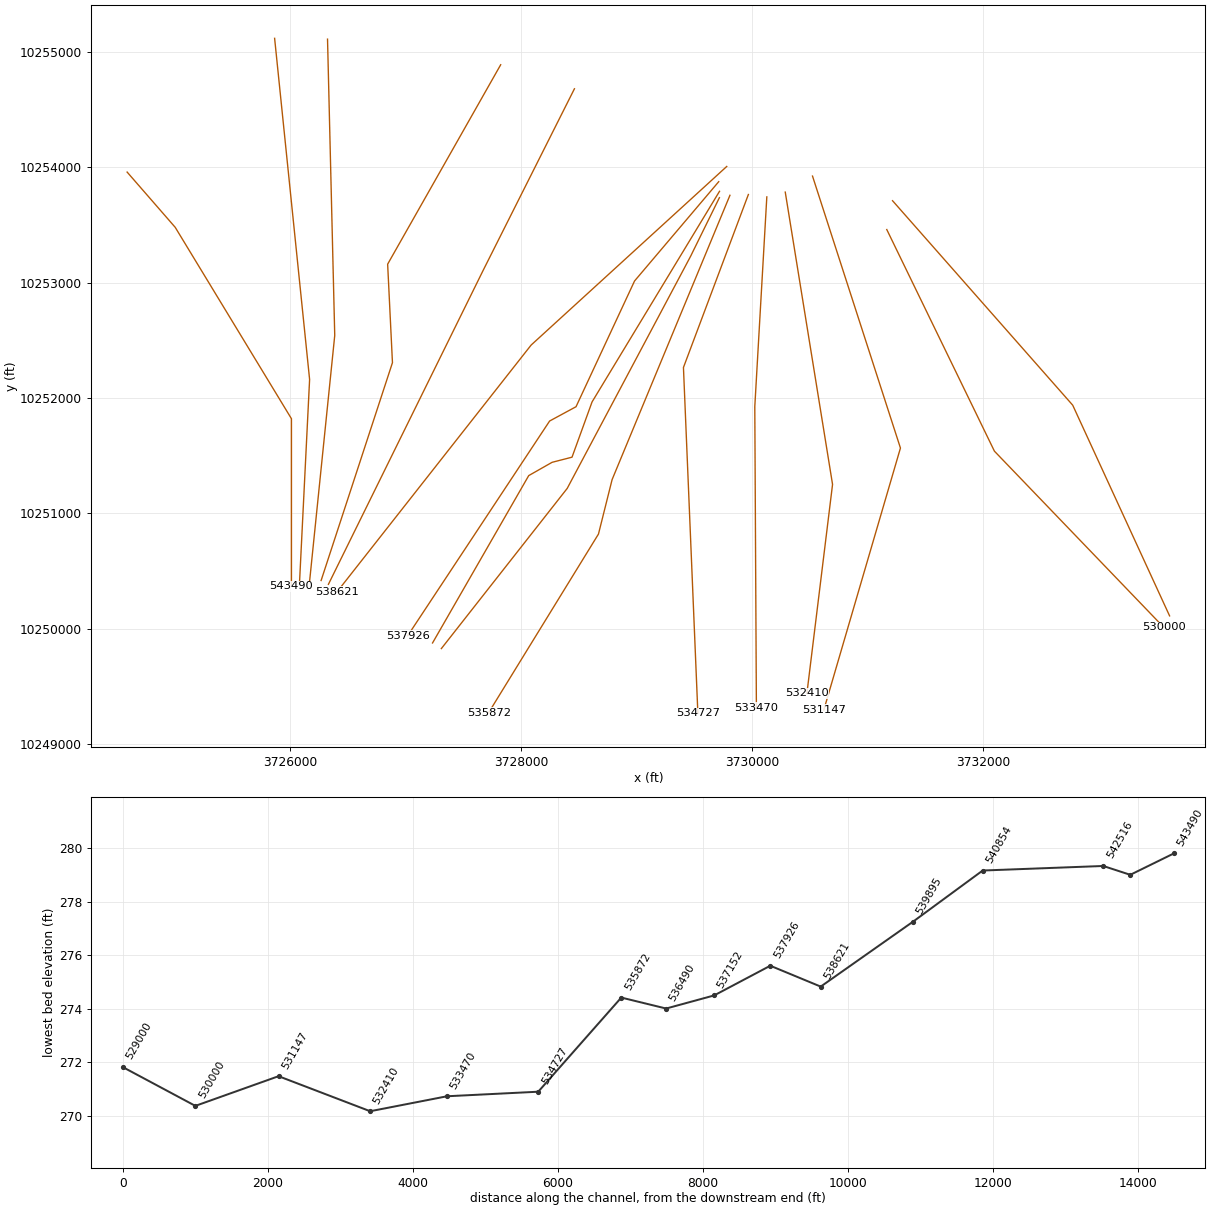
HEC-RAS study WFSJ Main.prj: WFSJ Main Base Level Engineering

--- WFSJ Main.g01 (geometry) --- (continued)

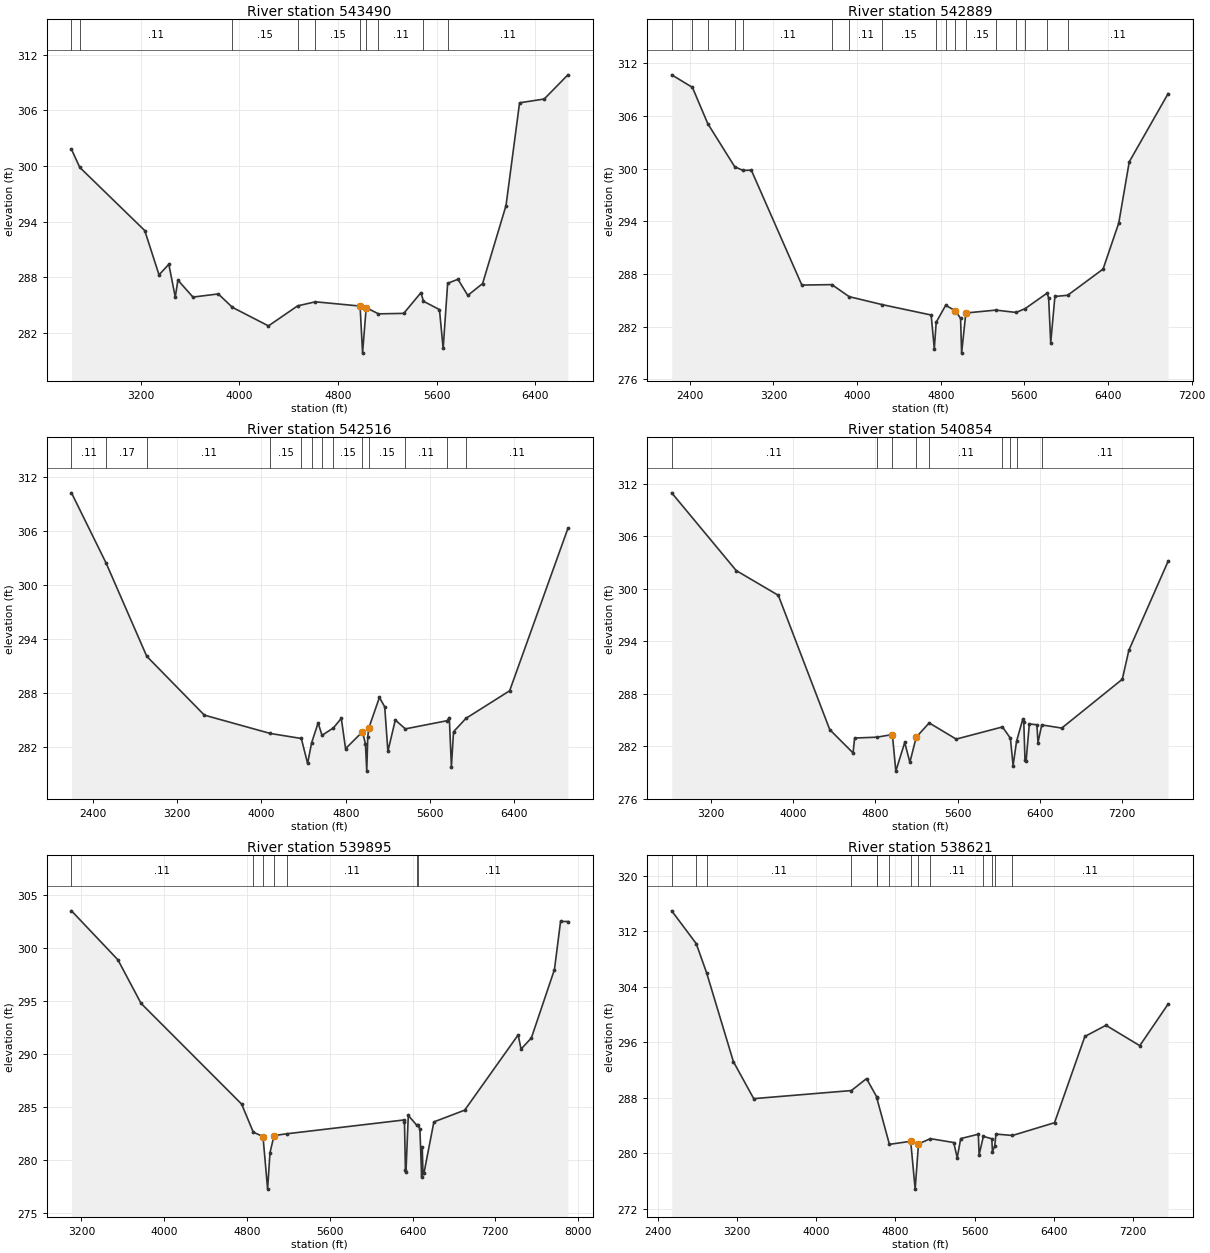
Type RM Length L Ch R = 1 ,543490  ,601,601,601
BEGIN DESCRIPTION:
WFSJ Main 535.0
END DESCRIPTION:
XS GIS Cut Line= 4
      3724586.99      10253959.4      3725003.66     10253480.24
       3726010.6     10251820.51       3726010.6     10250369.09
#Sta/Elev= 30
  2637.7   301.8  2704.9  299.85  3232.1  293.03    3348  288.25  3427.5  289.39
  3479.8  285.85  3501.1  287.68  3623.3  285.85  3828.8  286.19  3943.5  284.74
  4235.9  282.74  4472.2   284.9  4616.8  285.34  4979.4  284.88  4999.5   279.8
  5028.8  284.71  5128.5  284.04  5333.4  284.09  5473.4  286.33  5493.4   285.4
  5623.4   284.5  5653.4   280.3  5689.9  287.34  5773.4  287.77  5853.4  286.03
  5973.4  287.31  6163.4  295.73  6273.4  306.82  6473.4  307.23  6665.4  309.84
#Mann= 10 ,-1 , 0
  2637.7     .17       0  2704.9     .11       0  3943.5     .15       0
  4472.2     .11       0  4616.8     .15       0  4979.4     .09       0
  5028.8     .15       0  5128.5     .11       0  5493.4     .15       0
  5689.9     .11       0
Bank Sta=4979.4,5028.8
XS Rating Curve= 0 ,0
Exp/Cntr=0.3,0.1

Type RM Length L Ch R = 1 ,542889  ,373,373,373
BEGIN DESCRIPTION:
WFSJ Main 534.0
END DESCRIPTION:
XS GIS Cut Line= 3
      3725864.77     10255119.11      3726167.85     10252161.07
      3726080.05     10250389.97
#Sta/Elev= 30
  2227.3  310.69  2425.3  309.26  2572.3  305.13  2830.5  300.21  2909.1  299.81
  2988.8  299.83  3471.8  286.75  3759.1   286.8  3924.4  285.43  4241.6  284.52
  4708.3  283.34  4738.4   279.5  4756.6  282.52    4847  284.44  4939.5  283.83
  4989.7  282.96  4999.5     279    5040  283.57  5327.2   283.9    5521  283.63
  5607.4  284.07  5816.7  285.83  5831.6   285.3  5851.6  280.17  5891.7  285.45
  6013.8  285.59  6352.2  288.57  6502.4  293.82  6602.5  300.78  6974.1  308.55
#Mann= 17 ,-1 , 0
  2227.3     .11       0  2425.3     .17       0  2572.3     .11       0
  2830.5     .17       0  2909.1     .11       0  3759.1     .15       0
  3924.4     .11       0  4241.6     .15       0  4756.6     .11       0
    4847     .15       0  4939.5     .09       0    5040     .15       0
  5327.2     .11       0    5521     .15       0  5607.4     .11       0
  5816.7     .15       0  6013.8     .11       0
Bank Sta=4939.5,5040
XS Rating Curve= 0 ,0
Exp/Cntr=0.3,0.1

Type RM Length L Ch R = 1 ,542516  ,1662,1662,1662
BEGIN DESCRIPTION:
WFSJ Main 533.0
END DESCRIPTION:
XS GIS Cut Line= 3
       3726323.1     10255112.19       3726385.6     10252542.74
      3726167.85     10250411.04
#Sta/Elev= 30
  2196.1  310.29  2525.4  302.46  2910.5  292.11  3457.6  285.56  4083.8  283.52
  4378.3  282.96  4437.9  280.19  4476.5   282.5  4537.9   284.7  4574.7  283.31
  4682.7  284.14    4758   285.2  4798.3  281.83    4959  283.71  4987.1  282.37
  4999.5  279.33  5009.2  283.17  5019.3  284.14  5119.8  287.53  5170.1  286.48
  5200.2  281.53  5270.6  285.02  5365.9  284.03  5762.5  284.94  5783.2  285.29
  5803.3  279.83  5823.4  283.71  5941.3   285.2  6356.2  288.27  6909.1  306.33
#Mann= 13 ,-1 , 0
  2196.1     .11       0  2525.4     .17       0  2910.5     .11       0
  4083.8     .15       0  4378.3     .11       0  4476.5     .15       0
  4574.7     .11       0  4682.7     .15       0    4959     .09       0
  5019.3     .15       0  5365.9     .11       0  5762.5     .15       0
  5941.3     .11       0
Bank Sta=4959,5019.3
XS Rating Curve= 0 ,0
Exp/Cntr=0.3,0.1

Type RM Length L Ch R = 1 ,540854  ,959,959,959
BEGIN DESCRIPTION:
WFSJ Main 532.0
END DESCRIPTION:
XS GIS Cut Line= 4
      3727823.12     10254889.99      3726843.93     10253160.79
       3726885.6     10252306.63      3726267.55     10250417.74
#Sta/Elev= 30
  2818.9  310.96  3446.3  302.08  3856.1  299.25  4356.8   283.9  4583.4  281.24
  4598.9  282.94  4815.8  283.04    4966  283.34  4999.5  279.16  5086.1  282.44
  5136.2  280.17  5197.8  283.03  5324.2  284.67  5586.7  282.82  6037.4  284.21
  6114.1  282.92  6140.6   279.8  6174.1  282.56  6235.3  285.13  6244.7  284.72
  6256.3  280.39  6266.8  280.27  6298.4  284.55  6372.1  284.46  6382.7  282.42
  6419.3  284.44  6614.1  284.08  7203.3  289.66  7266.4  292.95  7648.7  303.14
#Mann= 9 ,-1 , 0
  2818.9     .11       0  4815.8     .15       0    4966     .09       0
  5197.8     .15       0  5324.2     .11       0  6037.4     .15       0
  6114.1     .11       0  6174.1     .15       0  6419.3     .11       0
Bank Sta=4966,5197.8
XS Rating Curve= 0 ,0
Exp/Cntr=0.3,0.1

Type RM Length L Ch R = 1 ,539895  ,1274,1274,1274
BEGIN DESCRIPTION:
WFSJ Main 531.0
END DESCRIPTION:
XS GIS Cut Line= 3
        3728462.     10254681.66      3727670.32     10253105.24
      3726330.81     10250384.56
#Sta/Elev= 30
  3104.4  303.54  3553.2  298.91  3776.5   294.8  4747.9  285.29  4861.3  282.63
    4955  282.22  4999.5  277.25  5022.4  280.69  5061.7  282.31  5186.1  282.48
  6314.1  283.78  6322.1  283.59    6331  279.03  6336.5  278.89    6359  284.21
  6442.1  283.27  6453.3  283.33  6471.3  282.89  6488.2   278.4  6493.8  281.22
  6500.5  278.79  6510.7  278.78  6606.1   283.6  6903.8  284.71  7420.5  291.82
  7448.5  290.48  7548.2  291.53  7771.1  297.99  7830.4  302.54    7901  302.53
#Mann= 7 ,-1 , 0
  3104.4     .11       0  4861.3     .15       0    4955     .09       0
  5061.7     .15       0  5186.1     .11       0  6442.1     .15       0
  6453.3     .11       0
Bank Sta=4955,5061.7
XS Rating Curve= 0 ,0
Exp/Cntr=0.3,0.1

Type RM Length L Ch R = 1 ,538621  ,695,695,695
BEGIN DESCRIPTION:
WFSJ Main 530.0
END DESCRIPTION:
XS GIS Cut Line= 3
      3729781.43     10254008.01      3728086.99      10252459.4
      3726406.45     10250320.53
#Sta/Elev= 30
  2539.6  314.96    2787  310.24  2892.8     306  3162.9  293.21  3368.3  287.87
  4355.4  289.04    4508  290.76  4609.3  288.17  4611.7  287.98  4739.3  281.28
  4954.4  281.72  4999.5  274.82  5033.1  281.34  5153.3   282.1  5389.1  281.54
  5424.4  279.35  5459.7  282.11  5637.7  282.74  5645.8  279.77  5688.6  282.43
  5774.1  282.08    5780  280.22  5803.3  281.03  5815.8  282.76  5982.7  282.56
  6407.7   284.4  6714.1  296.84  6927.4  298.45    7269  295.51  7555.2  301.51
#Mann= 14 ,-1 , 0
  2539.6     .11       0    2787     .17       0  2892.8     .11       0
  4355.4     .17       0  4609.3     .11       0  4611.7     .17       0
  4739.3     .15       0  4954.4     .09       0  5033.1     .15       0
  5153.3     .11       0  5688.6     .15       0    5780     .11       0
  5803.3     .15       0  5982.7     .11       0
Bank Sta=4954.4,5033.1
XS Rating Curve= 0 ,0
Exp/Cntr=0.3,0.1

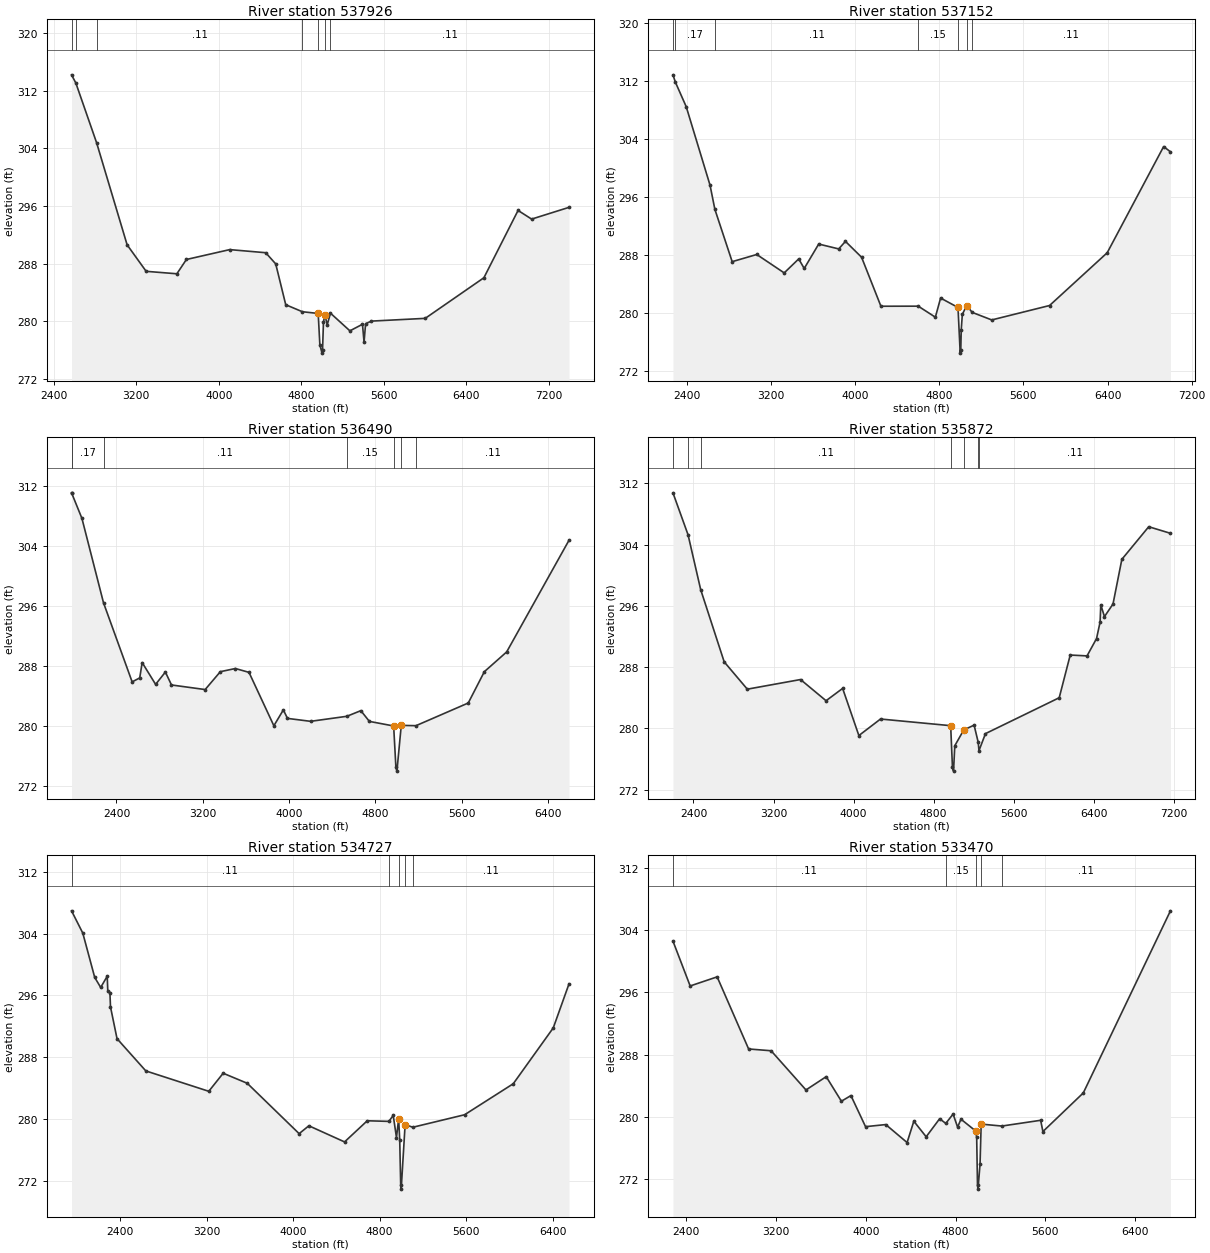
Type RM Length L Ch R = 1 ,537926  ,774,774,774
BEGIN DESCRIPTION:
WFSJ Main 529.0
END DESCRIPTION:
XS GIS Cut Line= 5
      3729711.99     10253876.07      3728982.82     10253014.96
      3728475.88     10251924.68       3728247.1     10251800.68
      3727017.53     10249938.55
#Sta/Elev= 30
  2571.7  314.18  2613.2  313.05  2814.5  304.77  3110.5  290.61    3295  286.94
  3592.7   286.6    3685  288.58    4105  289.95  4453.9  289.52  4550.9  287.97
    4648  282.31    4809  281.34  4962.6   281.1  4978.8  276.76  4999.5   275.6
    5005   276.1  5013.9  279.95  5028.2  280.88  5050.1  279.53  5081.6  281.14
    5270  278.69    5392   279.6  5407.1  277.12  5422.1  279.68  5479.3  280.04
  6000.1  280.42    6569  286.05  6900.1  295.38  7031.6  294.18  7394.1  295.81
#Mann= 7 ,-1 , 0
  2571.7     .11       0  2613.2     .17       0  2814.5     .11       0
    4809     .15       0  4962.6     .09       0  5028.2     .15       0
  5081.6     .11       0
Bank Sta=4962.6,5028.2
XS Rating Curve= 0 ,0
Exp/Cntr=0.3,0.1

Type RM Length L Ch R = 1 ,537152  ,662,662,662
BEGIN DESCRIPTION:
WFSJ Main 527.0
END DESCRIPTION:
XS GIS Cut Line= 6
      3729718.91      10253792.7      3728614.77     10251966.35
      3728441.16     10251487.18      3728268.47     10251442.55
      3728066.16     10251327.46      3727232.85     10249876.11
#Sta/Elev= 30
  2269.2  312.89  2292.2  311.88  2395.3  308.49  2621.7  297.66  2667.6  294.33
    2832  287.11  3065.7   288.1  3326.6  285.56  3464.4  287.49  3516.8  286.17
  3654.5  289.54  3844.7  288.87  3908.7  289.91    4062  287.72  4245.9  280.96
  4600.5  280.97  4763.3  279.45  4813.2  282.09  4978.4  280.79  4999.5  274.49
    5005  274.99  5009.4  277.73  5019.7  279.84    5061  281.05  5113.6  280.11
  5299.2  279.07  5848.8  281.06  6396.7  288.34    6933  302.99  6997.7  302.27
#Mann= 7 ,-1 , 0
  2269.2     .11       0  2292.2     .17       0  2667.6     .11       0
  4600.5     .15       0  4978.4     .09       0    5061     .15       0
  5113.6     .11       0
Bank Sta=4978.4,5061
XS Rating Curve= 0 ,0
Exp/Cntr=0.3,0.1

Type RM Length L Ch R = 1 ,536490  ,618,618,618
BEGIN DESCRIPTION:
WFSJ Main 528.0
END DESCRIPTION:
XS GIS Cut Line= 4
      3729717.84     10253737.43      3729468.93     10253230.24
      3728399.49     10251216.35      3727309.22     10249827.47
#Sta/Elev= 30
  1983.8  311.05  1984.6  311.03    2080  307.65  2280.1  296.41  2545.5  285.88
  2615.8  286.41  2638.4  288.45    2763  285.55  2853.5  287.19  2910.2  285.47
  3222.1  284.86  3363.1  287.24  3502.2  287.66  3628.5  287.15    3859  280.04
  3946.9  282.15  3985.2  281.02  4199.4  280.63  4535.7   281.3  4665.1  282.05
  4744.4  280.62  4969.3  280.01  4990.1   274.5  4999.5     274  5039.8  280.09
  5176.2  280.05  5660.7  283.07  5809.9  287.24  6016.8  289.87  6594.7  304.74
#Mann= 7 ,-1 , 0
  1983.8     .11       0  1984.6     .17       0  2280.1     .11       0
  4535.7     .15       0  4969.3     .09       0  5039.8     .15       0
  5176.2     .11       0
Bank Sta=4969.3,5039.8
XS Rating Curve= 0 ,0
Exp/Cntr=0.3,0.1

Type RM Length L Ch R = 1 ,535872  ,1145,1145,1145
BEGIN DESCRIPTION:
WFSJ Main 526.0
END DESCRIPTION:
XS GIS Cut Line= 4
      3729809.22     10253758.04      3728788.38     10251292.74
      3728670.32     10250820.51      3727718.92     10249271.87
#Sta/Elev= 30
    2195  310.78  2345.8   305.3  2472.1  298.13  2707.1  288.69  2938.3  285.12
  3470.3  286.38  3725.4  283.61    3891  285.22  4053.3  279.06  4269.8  281.22
  4970.9  280.35  4988.7  274.91  4999.5  274.41  5012.1  277.73  5102.1   279.8
  5205.2  280.42  5246.4  278.16  5253.7  277.08  5318.6  279.31  6055.8     284
  6165.9  289.58    6334  289.47  6428.7  291.73  6464.4  293.88  6471.3  296.15
    6508   294.6  6593.5  296.25    6682  302.09  6950.7  306.35  7167.6  305.49
#Mann= 7 ,-1 , 0
    2195     .11       0  2345.8     .17       0  2472.1     .11       0
  4970.9     .06       0  5102.1     .11       0  5246.4     .15       0
  5253.7     .11       0
Bank Sta=4970.9,5102.1
XS Rating Curve= 0 ,0
Exp/Cntr=0.3,0.1

Type RM Length L Ch R = 1 ,534727  ,1257,1257,1257
BEGIN DESCRIPTION:
WFSJ Main 525.0
END DESCRIPTION:
XS GIS Cut Line= 3
      3729968.92     10253764.93      3729406.43     10252264.96
      3729531.41     10249265.53
#Sta/Elev= 30
  1948.7  306.96  2052.9  304.07  2163.2  298.33  2218.4  297.03  2278.9  298.48
  2284.3  296.55  2303.8  296.37  2309.2  294.51  2369.7  290.39  2636.3  286.21
  3218.8  283.57  3351.9  285.91  3574.6  284.61    4055  278.08  4145.1   279.1
  4475.4  277.01  4685.5  279.75  4885.7  279.67  4925.7  280.45  4955.8  277.58
  4975.8  279.98  4985.8   277.3    4995  271.39  4999.5  270.89  5035.8  279.25
  5107.4  278.91  5586.3  280.53  6036.7  284.55    6407  291.79  6552.7   297.5
#Mann= 5 ,-1 , 0
  1948.7     .11       0  4885.7     .15       0  4975.8     .09       0
  5035.8     .15       0  5107.4     .11       0
Bank Sta=4975.8,5035.8
XS Rating Curve= 0 ,0
Exp/Cntr=0.3,0.1

Type RM Length L Ch R = 1 ,533470  ,1060,1060,1060
BEGIN DESCRIPTION:
WFSJ Main 524.0
END DESCRIPTION:
XS GIS Cut Line= 3
      3730128.66     10253744.11      3730024.49     10251924.68
      3730038.37     10249314.83
#Sta/Elev= 30
  2281.7  302.61    2435  296.84  2675.4  298.01  2955.8  288.74  3156.2  288.51
  3466.7  283.47    3647  285.18  3782.5  282.02  3867.3  282.75  3997.5  278.75
  4177.7  279.02  4367.7  276.71  4427.7  279.45  4537.7  277.45  4657.7  279.77
  4712.3  279.17  4777.7  280.37  4817.7  278.69  4847.7  279.71  4977.7  278.21
  4987.7  277.38    4995  271.22  4999.5  270.72  5017.7  273.94  5027.7  279.08
  5211.9  278.83  5557.7  279.57  5577.7  278.12  5937.7  283.09    6714   306.5
#Mann= 5 ,-1 , 0
  2281.7     .11       0  4712.3     .15       0  4977.7     .09       0
  5027.7     .15       0  5211.9     .11       0
Bank Sta=4977.7,5027.7
XS Rating Curve= 0 ,0
Exp/Cntr=0.3,0.1

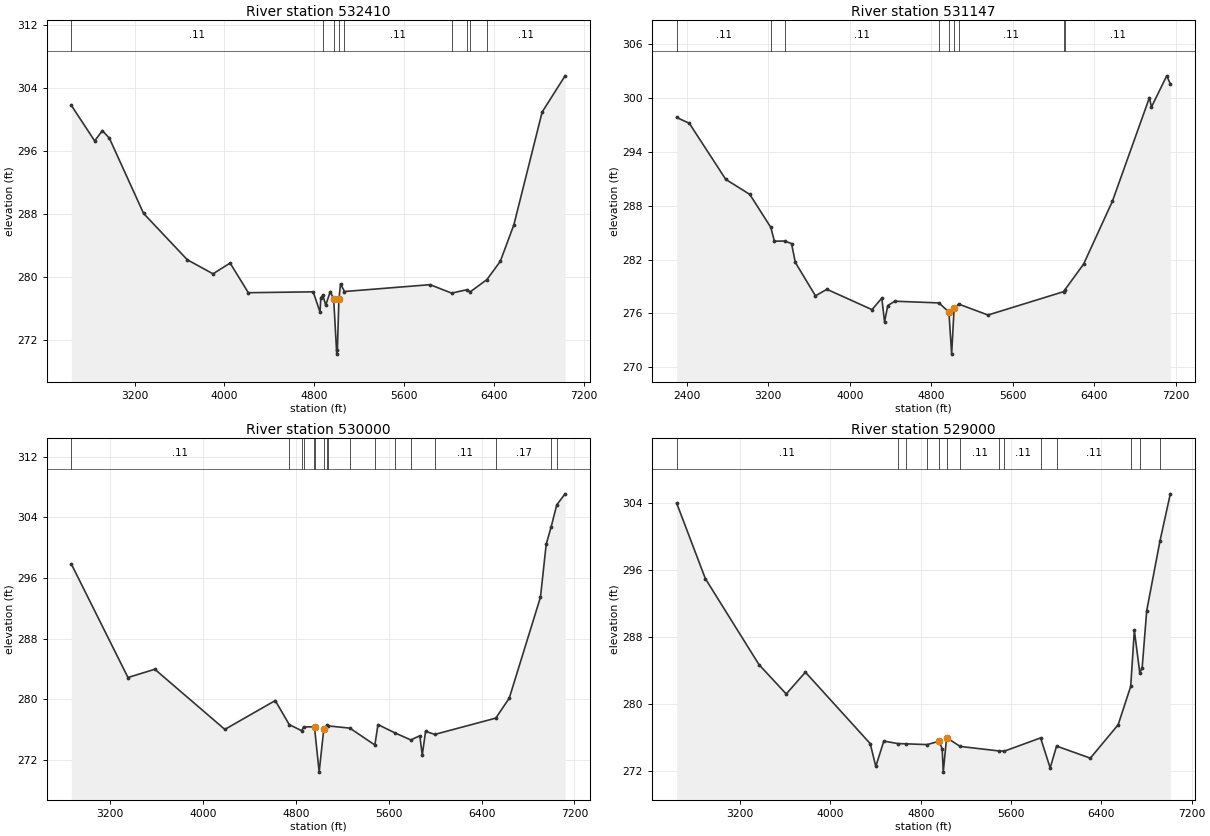
Type RM Length L Ch R = 1 ,532410  ,1263,1263,1263
BEGIN DESCRIPTION:
WFSJ Main 523.0
END DESCRIPTION:
XS GIS Cut Line= 3
      3730288.38      10253785.8       3730698.1     10251251.07
      3730475.88     10249438.58
#Sta/Elev= 30
  2637.7  301.78  2845.1  297.27  2913.7  298.57  2975.4  297.63  3280.7  288.04
  3669.5  282.16  3898.6  280.37  4050.5  281.74  4212.6  277.97    4790  278.08
  4850.8  275.49  4857.5  277.35  4875.9  277.64  4901.4  276.38    4942  278.12
  4972.3  277.12  4999.5  270.16    5005  270.66 5018.73  277.13  5033.1   279.1
  5068.3  278.12    5830  278.99  6021.2  277.92    6163  278.36  6185.5  278.06
  6335.4  279.63  6454.6  281.95  6575.5  286.59  6827.4  300.94  7031.4  305.54
#Mann= 9 ,-1 , 0
  2637.7     .11       0  4875.9     .15       0  4972.3     .09       0
 5018.73     .15       0  5068.3     .11       0  6021.2     .17       0
    6163     .11       0  6185.5     .17       0  6335.4     .11       0
Bank Sta=4972.3,5018.73
XS Rating Curve= 0 ,0
Exp/Cntr=0.3,0.1

Type RM Length L Ch R = 1 ,531147  ,1147,1147,1147
BEGIN DESCRIPTION:
WFSJ Main 522.0
END DESCRIPTION:
XS GIS Cut Line= 3
       3730524.5     10253924.64      3731286.24     10251566.31
      3730622.19     10249294.36
#Sta/Elev= 30
  2300.1  297.86  2424.8  297.21  2782.4  290.96  3018.4  289.28  3224.9   285.6
  3260.1  284.06  3360.8  284.08  3428.2   283.8  3465.5  281.69    3663  277.97
  3775.1   278.7    4218  276.43  4314.1  277.72  4340.9  275.06  4372.9  276.89
  4442.2  277.37  4875.4  277.18  4972.6  276.16  4999.5  271.47  5023.5  276.57
  5068.3  277.05  5356.2  275.83  6099.7  278.44  6107.9   278.6  6294.5  281.51
  6576.9  288.51  6940.5  300.07  6960.4  299.02  7109.9   302.5  7145.4  301.61
#Mann= 9 ,-1 , 0
  2300.1     .11       0  3224.9     .17       0  3360.8     .11       0
  4875.4     .17       0  4972.6     .09       0  5023.5     .17       0
  5068.3     .11       0  6099.7     .17       0  6107.9     .11       0
Bank Sta=4972.6,5023.5
XS Rating Curve= 0 ,0
Exp/Cntr=0.3,0.1

Type RM Length L Ch R = 1 ,530000  ,1000,1000,1000
BEGIN DESCRIPTION:
WFSJ Main 521.0
END DESCRIPTION:
XS GIS Cut Line= 3
      3731167.85     10253461.07      3732100.31     10251539.35
      3733567.85     10250011.07
#Sta/Elev= 30
    2864  297.83    3352  282.85  3583.2  283.94  4186.7     276  4621.1  279.81
  4741.4  276.64  4848.6  275.83  4865.7  276.32  4955.7  276.35  4959.6  276.26
  4999.5  270.36  5039.3  276.04  5067.3  276.61  5077.1  276.46  5264.1  276.17
  5479.7  273.94  5506.3  276.64    5655  275.52  5789.8  274.61    5867  275.16
  5888.1   272.6  5916.4  275.74  5996.4  275.34  6521.8  277.49  6637.8  280.13
  6906.7  293.46  6956.1  300.44  6998.1   302.7  7047.1  305.64  7118.8   307.1
#Mann= 17 ,-1 , 0
    2864     .11       0  4741.4     .17       0  4848.6     .15       0
  4865.7     .11       0  4955.7     .15       0  4959.6     .09       0
  5039.3     .15       0  5067.3     .11       0  5077.1     .15       0
  5264.1     .11       0  5479.7     .15       0    5655     .11       0
  5789.8     .15       0  5996.4     .11       0  6521.8     .17       0
  6998.1     .11       0  7047.1     .17       0
Bank Sta=4959.6,5039.3
XS Rating Curve= 0 ,0
Exp/Cntr=0.3,0.1

Type RM Length L Ch R = 1 ,529000  ,1000,1000,1000
BEGIN DESCRIPTION:
WFSJ Main 520.0
END DESCRIPTION:
XS GIS Cut Line= 3
      3731217.87     10253711.05      3732778.68     10251937.97
      3733617.85     10250111.08
#Sta/Elev= 30
  2637.8  303.97  2892.5  294.93  3367.8  284.65  3608.8  281.15  3778.6  283.75
  4352.6  275.22    4402  272.49  4473.1  275.52  4597.9  275.22  4668.1  275.19
  4857.5   275.1  4961.7   275.5  4990.2   274.6  4999.5  271.81    5029  275.93
  5149.6  274.88  5492.8  274.34  5541.1  274.32  5861.6   275.9  5946.4  272.31
  6003.1  274.92  6302.1  273.48  6548.5  277.47  6659.6  282.06  6691.9  288.74
  6739.8   283.7  6760.8  284.24  6801.3  291.09  6917.9  299.37  7010.4  305.06
#Mann= 14 ,-1 , 0
  2637.8     .11       0  4597.9     .17       0  4668.1     .11       0
  4857.5     .15       0  4961.7     .09       0    5029     .15       0
  5149.6     .11       0  5492.8     .15       0  5541.1     .11       0
  5861.6     .15       0  6003.1     .11       0  6659.6     .17       0
  6739.8     .11       0  6917.9     .17       0
Bank Sta=4961.7,5029
XS Rating Curve= 0 ,0
Exp/Cntr=0.3,0.1