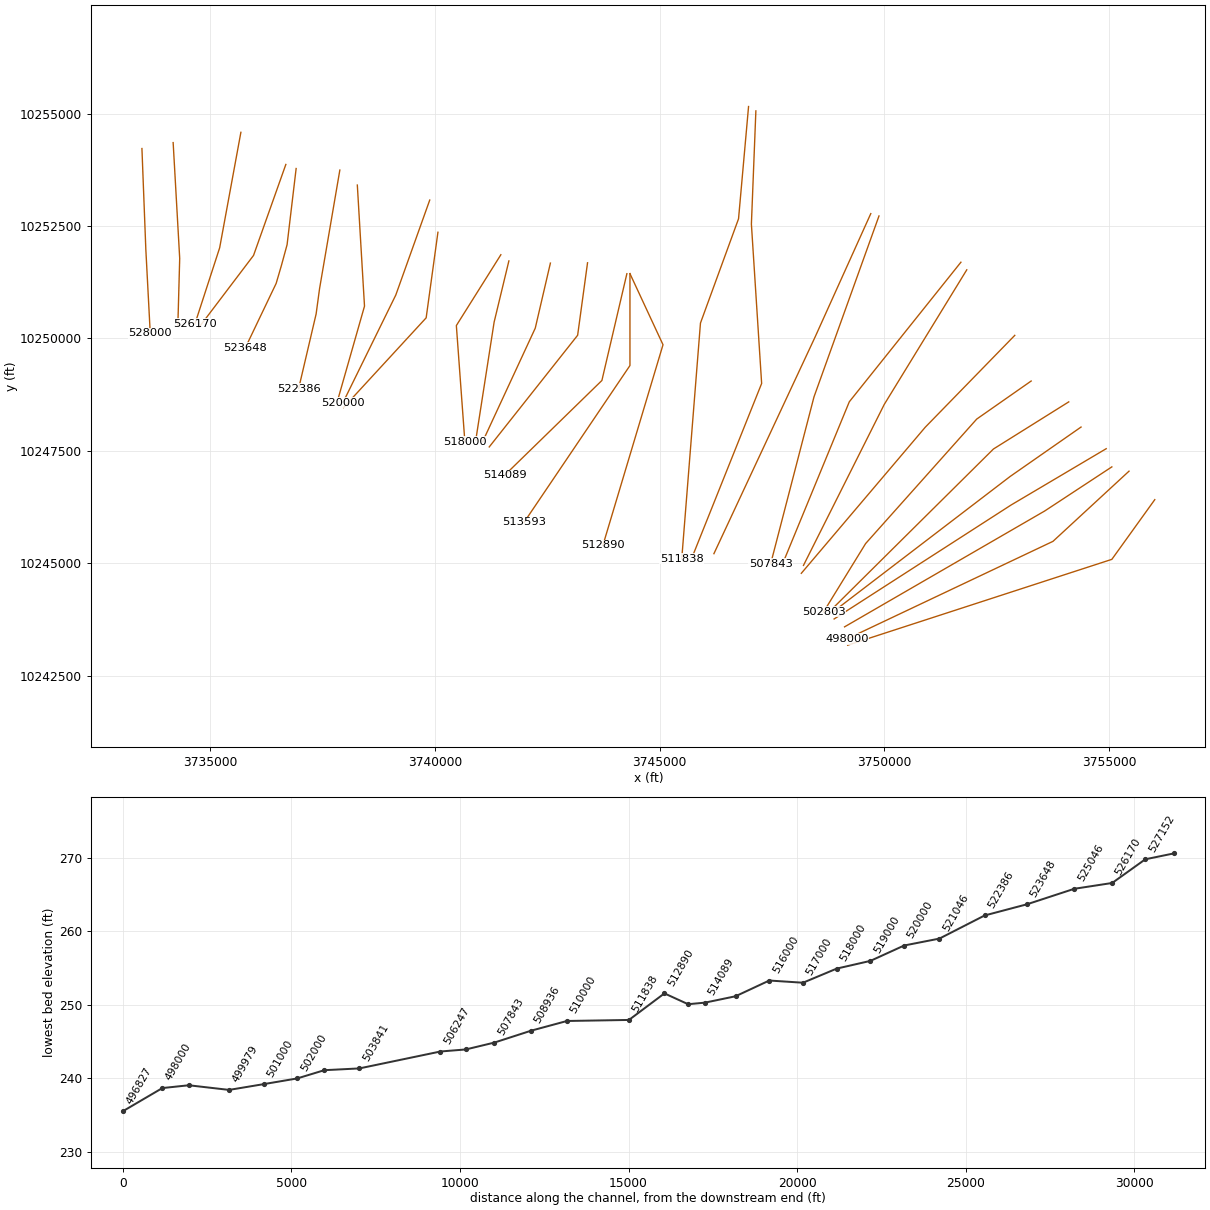
HEC-RAS study WFSJ Main.prj: WFSJ Main Base Level Engineering

--- WFSJ Main.g01 (geometry) --- (continued)

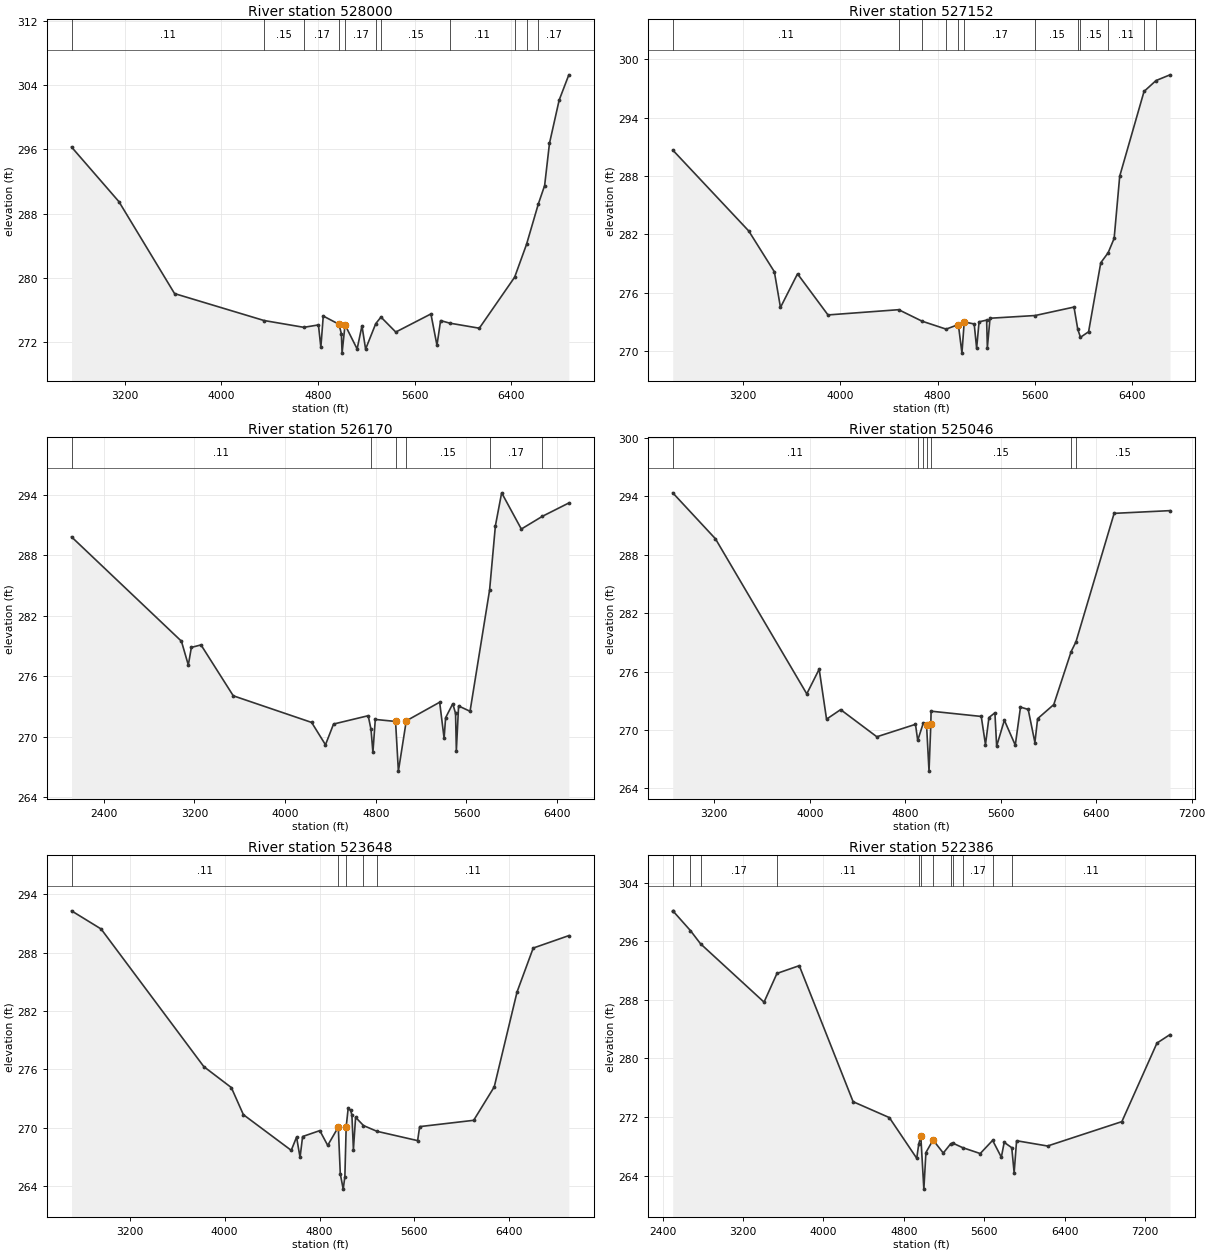
Type RM Length L Ch R = 1 ,528000  ,848,848,848
BEGIN DESCRIPTION:
WFSJ Main 519.0
END DESCRIPTION:
XS GIS Cut Line= 3
      3733482.82     10254223.33       3733569.3       10251985.
      3733667.85     10250111.08
#Sta/Elev= 30
    2760   296.3  3152.5  289.48  3612.9  278.01  4353.4  274.65  4682.9   273.8
  4803.8   274.1  4823.8  271.31  4843.8  275.21  4973.9  274.18  4993.9  272.99
  4999.5  270.58    5024  274.11  5124.1   271.1  5164.2  273.99  5194.2  271.08
  5278.3  274.26  5321.4  275.08    5444  273.21  5734.9  275.47    5785  271.56
    5815  274.64  5891.5  274.32  6135.5  273.69  6428.1  280.06  6526.3  284.15
  6624.4  289.21  6676.2  291.49  6716.3  296.76  6796.4  302.15  6876.5  305.31
#Mann= 11 ,-1 , 0
    2760     .11       0  4353.4     .15       0  4682.9     .17       0
  4973.9     .09       0    5024     .17       0  5278.3     .11       0
  5321.4     .15       0  5891.5     .11       0  6428.1     .15       0
  6526.3     .11       0  6624.4     .17       0
Bank Sta=4973.9,5024
XS Rating Curve= 0 ,0
Exp/Cntr=0.3,0.1

Type RM Length L Ch R = 1 ,527152  ,982,982,982
BEGIN DESCRIPTION:
WFSJ Main 518.0
END DESCRIPTION:
XS GIS Cut Line= 3
      3734177.27     10254355.27       3734323.1     10251778.85
      3734281.43     10250271.87
#Sta/Elev= 30
  2622.1  290.68    3247  282.35  3457.6  278.15  3507.7  274.48  3647.9  277.94
  3898.3  273.71  4479.3  274.25  4671.3  273.07  4869.4  272.25  4970.1  272.72
  4999.5  269.78  5018.2  272.99  5100.3  272.78  5120.3  270.28  5140.3     273
  5202.6  273.18  5208.5  270.34  5230.4  273.37  5601.3  273.65  5920.7  274.52
    5952  272.22  5974.1  271.41  6040.7  271.98  6140.8  279.08  6201.4  280.11
  6250.8  281.59  6296.5  287.99  6496.5  296.71  6594.9  297.83  6710.2  298.42
#Mann= 12 ,-1 , 0
  2622.1     .11       0  4479.3     .15       0  4671.3     .15       0
  4869.4     .17       0  4970.1     .09       0  5018.2     .17       0
  5601.3     .15       0    5952     .11       0  5974.1     .15       0
  6201.4     .11       0  6496.5     .15       0  6594.9     .11       0
#XS Ineff= 1 ,-1
    3430  3647.9  277.94
Permanent Ineff=
       F
Bank Sta=4970.1,5018.2
XS Rating Curve= 0 ,0
Exp/Cntr=0.3,0.1

Type RM Length L Ch R = 1 ,526170  ,1124,1124,1124
BEGIN DESCRIPTION:
WFSJ Main 517.0
END DESCRIPTION:
XS GIS Cut Line= 3
      3735684.21     10254584.39      3735211.99     10252014.96
      3734663.38     10250327.46
#Sta/Elev= 30
  2116.1  289.85  3085.4  279.48  3146.4  277.11  3173.3  278.86  3258.2  279.11
  3542.9  274.05  4234.3   271.4  4356.3  269.18  4427.5  271.24  4733.2  272.07
    4758  270.71  4774.7  268.43  4795.7   271.7  4974.5   271.5  4999.5  266.56
  5069.1  271.56  5363.6  273.41  5402.7  269.83  5416.1  271.87  5479.2  273.26
  5503.8   272.3  5510.8   268.6  5530.5  273.04  5631.6  272.51  5804.1  284.57
  5855.2  290.95  5910.4  294.23    6084  290.63  6270.6   291.9    6503  293.22
#Mann= 6 ,-1 , 0
  2116.1     .11       0    4758     .17       0  4974.5     .08       0
  5069.1     .15       0  5804.1     .17       0  6270.6     .15       0
Bank Sta=4974.5,5069.1
XS Rating Curve= 0 ,0
Exp/Cntr=0.3,0.1

Type RM Length L Ch R = 1 ,525046  ,1398,1398,1398
BEGIN DESCRIPTION:
WFSJ Main 516.0
END DESCRIPTION:
XS GIS Cut Line= 3
      3736684.23     10253869.16      3735965.81     10251845.71
      3734746.72     10250237.19
#Sta/Elev= 30
  2852.8  294.37  3210.9  289.64  3975.6  273.71  4079.4  276.25  4141.1  271.11
  4259.2  272.09  4562.5   269.3  4886.1  270.58  4904.8  268.93  4951.3   270.7
  4978.7  270.53  4999.5  265.77 5014.59  270.58  5016.8  271.93    5437  271.39
  5472.4  268.49  5501.5  271.28  5551.4  271.76    5566  268.34  5630.5     271
  5722.1  268.44  5765.7  272.35  5830.2  272.11  5886.4  268.71  5909.2  271.16
  6044.5  272.61  6190.2  278.06  6230.4  279.06    6550  292.26  7018.3  292.54
#Mann= 7 ,-1 , 0
  2852.8     .11       0  4904.8     .17       0  4951.3     .15       0
  4978.7     .09       0 5014.59     .15       0  6190.2     .11       0
  6230.4     .15       0
Bank Sta=4978.7,5014.59
XS Rating Curve= 0 ,0
Exp/Cntr=0.3,0.1

Type RM Length L Ch R = 1 ,523648  ,1262,1262,1262
BEGIN DESCRIPTION:
WFSJ Main 515.0
END DESCRIPTION:
XS GIS Cut Line= 5
      3736913.37     10253778.82      3736711.99      10252084.4
      3736586.99     10251626.07      3736468.93     10251223.29
       3735782.2      10249787.4
#Sta/Elev= 30
  2708.9   292.3  2958.4  290.43  3824.4  276.27  4056.1  274.12  4157.8  271.33
  4561.3  267.66  4606.2  269.02  4635.6  266.93  4657.1  269.08  4802.2  269.69
  4868.8  268.17    4958  270.05  4974.9  265.24  4999.5  263.67  5013.5  264.96
 5024.47  270.07  5041.4  271.99  5062.3  271.76  5072.7   271.3  5085.5  267.74
  5103.9  271.06  5170.5  270.21  5283.5  269.62  5626.9  268.66  5644.1   270.1
  6099.5  270.75  6272.9  274.19  6465.3  283.96  6601.4  288.47  6901.7  289.75
#Mann= 5 ,-1 , 0
  2708.9     .11       0    4958     .07       0 5024.47     .11       0
  5170.5     .15       0  5283.5     .11       0
Bank Sta=4958,5024.47
XS Rating Curve= 0 ,0
Exp/Cntr=0.3,0.1

Type RM Length L Ch R = 1 ,522386  ,1340,1340,1340
BEGIN DESCRIPTION:
WFSJ Main 514.0
END DESCRIPTION:
XS GIS Cut Line= 4
       3737885.6     10253744.14      3737434.21     10251105.24
      3737357.82     10250542.74      3736969.29     10248884.54
#Sta/Elev= 30
  2500.9  300.15  2502.1  300.15  2677.1  297.45  2777.4  295.65  3409.4  287.68
    3538   291.6  3759.8  292.66  4295.6  274.08  4656.1  271.91  4928.7  266.35
    4949  268.33  4969.3  269.34  4999.5  262.14    5020  267.14    5091  268.85
  5192.9  267.07  5265.3  268.31    5285  268.44  5384.6  267.81  5560.3     267
  5683.6   268.8  5770.4   266.5  5798.9  268.53    5874   267.8  5897.8  264.37
  5922.1  268.75  6230.2  268.03  6969.7  271.36  7318.9  282.09  7448.9  283.25
#Mann= 13 ,-1 , 0
  2500.9     .11       0  2502.1     .17       0  2677.1     .11       0
  2777.4     .17       0    3538     .11       0    4949     .17       0
  4969.3     .09       0    5091     .17       0  5265.3     .17       0
    5285     .11       0  5384.6     .17       0  5683.6     .15       0
    5874     .11       0
Bank Sta=4969.3,5091
XS Rating Curve= 0 ,0
Exp/Cntr=0.3,0.1

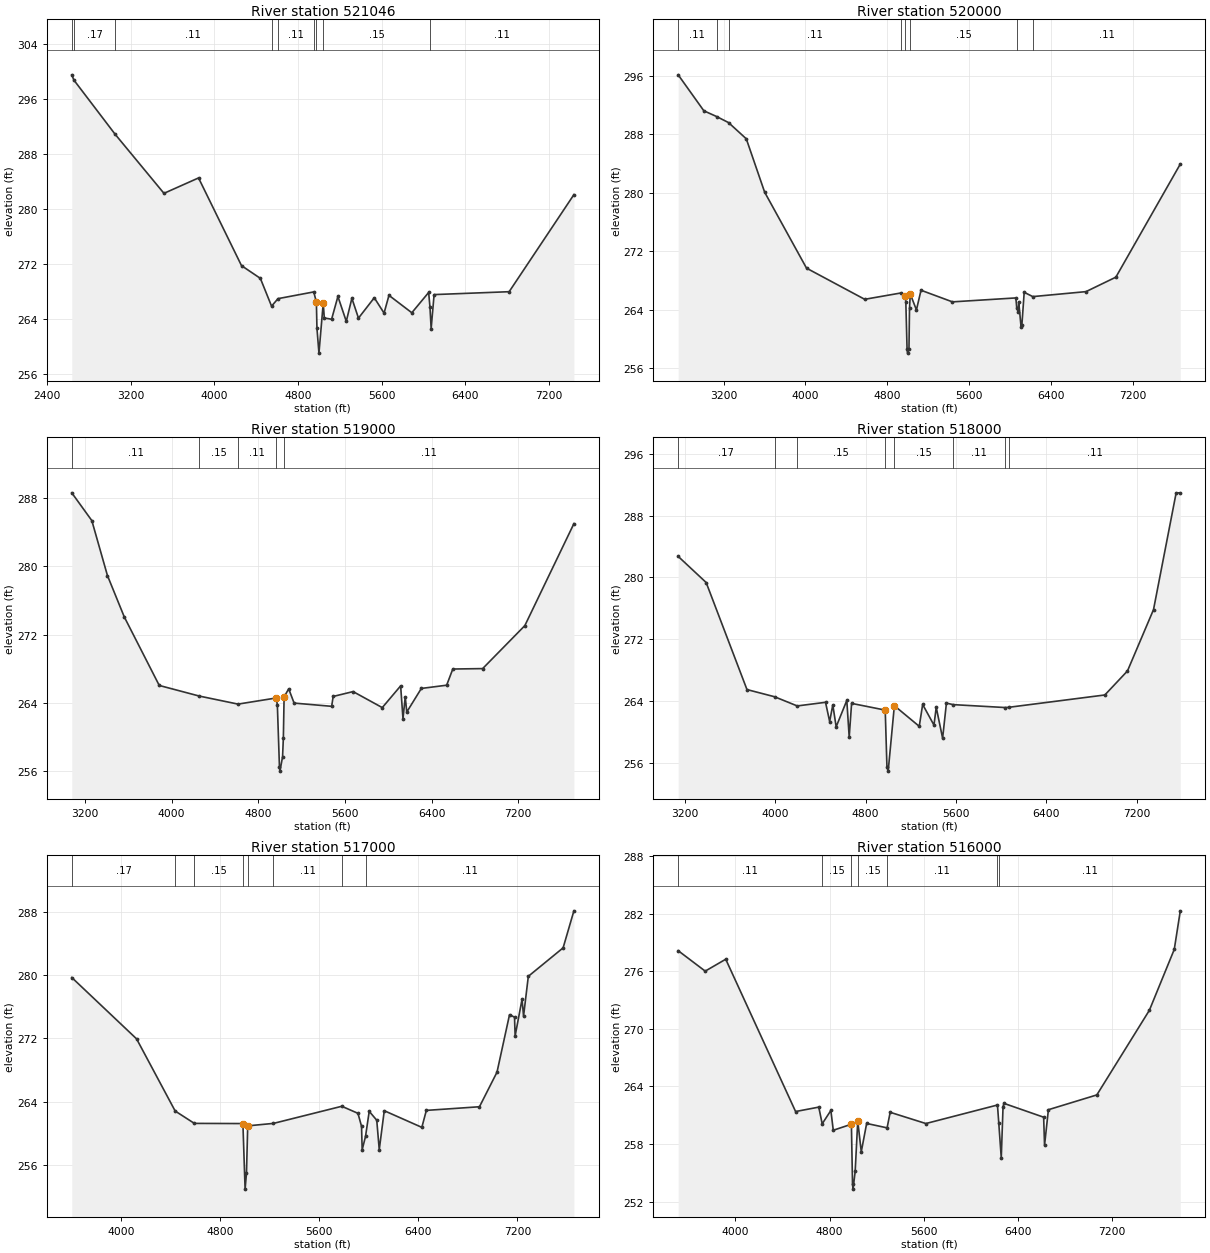
Type RM Length L Ch R = 1 ,521046  ,1046,1046,1046
BEGIN DESCRIPTION:
WFSJ Main 513.0
END DESCRIPTION:
XS GIS Cut Line= 3
      3738274.49      10253410.8      3738434.21     10250716.35
      3737857.91     10248695.81
#Sta/Elev= 30
  2636.5  299.46  2657.1  298.69  3049.9  290.84  3517.8  282.23  3848.4  284.47
  4259.1  271.72  4439.4  269.87  4546.4  265.83  4608.1  266.92  4949.9   267.9
    4975  266.41  4980.3  262.62  4999.5     259  5040.4  266.27  5050.5  264.11
  5120.6  263.93  5180.7  267.24  5260.8  263.62  5314.3  266.97  5377.3  264.09
  5528.4  267.05  5621.9  264.82  5668.8   267.4  5887.3  264.87  6048.3  267.82
  6060.6  265.72  6072.1  262.57  6100.3  267.51  6817.8  267.93  7436.8  282.04
#Mann= 9 ,-1 , 0
  2636.5     .11       0  2657.1     .17       0  3049.9     .11       0
  4546.4     .15       0  4608.1     .11       0  4949.9     .15       0
    4975     .09       0  5040.4     .15       0  6060.6     .11       0
Bank Sta=4975,5040.4
XS Rating Curve= 0 ,0
Exp/Cntr=0.3,0.1

Type RM Length L Ch R = 1 ,520000  ,1000,1000,1000
BEGIN DESCRIPTION:
WFSJ Main 512.0
END DESCRIPTION:
XS GIS Cut Line= 3
      3739885.59     10253077.44      3739130.44     10250964.74
      3737955.04      10248570.5
#Sta/Elev= 30
  2756.4  296.12  3007.5   291.2  3131.7  290.42  3248.6  289.59  3422.5  287.37
  3602.1  280.07  4011.7  269.68  4580.7  265.42  4940.2   266.3  4977.9  265.87
  4982.7   265.1    4995  258.56  4999.5  258.06  5013.4  258.56    5019  264.24
  5026.4  266.14  5086.5  263.97  5131.4  266.66  5438.6  265.07  6058.9  265.61
  6067.2   264.3  6081.4  263.66    6087  265.09  6109.5  261.68  6118.1  261.96
  6140.4  266.38  6224.4  265.79  6744.7  266.47    7037  268.45  7667.2  283.92
#Mann= 8 ,-1 , 0
  2756.4     .11       0  3131.7     .17       0  3248.6     .11       0
  4940.2     .15       0  4977.9     .09       0  5026.4     .15       0
  6067.2     .17       0  6224.4     .11       0
Bank Sta=4977.9,5026.4
XS Rating Curve= 0 ,0
Exp/Cntr=0.3,0.1

Type RM Length L Ch R = 1 ,519000  ,1000,1000,1000
BEGIN DESCRIPTION:
WFSJ Main 511.0
END DESCRIPTION:
XS GIS Cut Line= 3
      3740067.86     10252361.11      3739805.86     10250456.85
      3737967.85     10248461.07
#Sta/Elev= 30
  3077.8  288.65  3262.9  285.39    3407  278.94  3562.4  274.08  3885.4  266.03
  4256.3  264.78  4612.6  263.84  4965.5  264.56  4975.6  263.75    4995  256.47
  4999.5  255.97  5023.7  257.65  5031.1  259.88  5037.9  264.69  5080.4  265.63
  5130.2  263.96  5476.8  263.58    5491  264.74  5674.8  265.31  5944.1  263.43
  6113.7  265.98  6135.3  262.14  6156.2  264.69  6170.4  262.91  6304.8  265.68
  6538.5  266.06  6595.2  267.96  6870.8  268.01  7260.4  273.06  7713.2  285.03
#Mann= 5 ,-1 , 0
  3077.8     .11       0  4256.3     .15       0  4612.6     .11       0
  4965.5     .06       0  5037.9     .11       0
Bank Sta=4965.5,5037.9
XS Rating Curve= 0 ,0
Exp/Cntr=0.3,0.1

Type RM Length L Ch R = 1 ,518000  ,1000,1000,1000
BEGIN DESCRIPTION:
WFSJ Main 510.0
END DESCRIPTION:
XS GIS Cut Line= 3
      3741467.84     10251861.05      3740477.53     10250285.18
      3740666.72     10247704.31
#Sta/Elev= 30
  3138.8  282.72  3386.7  279.34  3748.3  265.48  3992.7  264.55  4193.7  263.36
  4444.4  263.83  4480.9  261.34  4508.8   263.5  4538.6  260.66  4632.9  264.07
  4654.1  259.32  4675.3  263.69  4973.3  262.82  4988.6  255.42  4999.5  254.92
  5054.3  263.39  5274.8  260.72  5304.9  263.55  5405.2  260.88  5425.2  263.18
  5481.8  259.18  5515.5  263.73  5574.7  263.53  6038.9  263.15  6066.3  263.18
  6919.2  264.78  7119.7  267.89  7350.4  275.83  7550.9  290.94  7587.8  290.95
#Mann= 8 ,-1 , 0
  3138.8     .17       0  3992.7     .11       0  4193.7     .15       0
  4973.3     .09       0  5054.3     .15       0  5574.7     .11       0
  6038.9     .15       0  6066.3     .11       0
Bank Sta=4973.3,5054.3
XS Rating Curve= 0 ,0
Exp/Cntr=0.3,0.1

Type RM Length L Ch R = 1 ,517000  ,1000,1000,1000
BEGIN DESCRIPTION:
WFSJ Main 509.0
END DESCRIPTION:
XS GIS Cut Line= 3
      3741646.03     10251723.33      3741317.81     10250361.53
       3740909.9     10247737.14
#Sta/Elev= 30
  3599.2  279.69  4122.9  271.95  4434.6  262.85  4589.6  261.29  4981.8  261.27
  4999.5     253  5010.6  254.99  5020.7  260.98  5228.4  261.29  5780.7  263.45
  5911.3  262.56  5940.2  260.92  5945.3  257.96  5972.4  259.65  6002.3  262.81
  6063.1  261.69  6083.3  257.98  6123.8  262.89  6427.4  260.79  6463.8  262.93
  6892.9  263.39  7034.6  267.75  7135.8     275  7176.1  274.69  7181.1  272.32
    7237  276.95  7249.1  274.82  7287.6  279.84  7568.7  283.43  7655.9   288.1
#Mann= 8 ,-1 , 0
  3599.2     .17       0  4434.6     .11       0  4589.6     .15       0
  4981.8     .09       0  5020.7     .15       0  5228.4     .11       0
  5780.7     .17       0  5972.4     .11       0
Bank Sta=4981.8,5020.7
XS Rating Curve= 0 ,0
Exp/Cntr=0.3,0.1

Type RM Length L Ch R = 1 ,516000  ,1000,1000,1000
BEGIN DESCRIPTION:
WFSJ Main 508.0
END DESCRIPTION:
XS GIS Cut Line= 3
      3742569.64     10251674.71      3742232.85     10250226.86
      3741063.62     10247704.48
#Sta/Elev= 30
  3513.5  278.13  3743.1     276  3917.6  277.24  4511.2  261.38  4708.2  261.84
  4737.2   260.1  4810.9  261.49  4831.4  259.43  4985.4  260.06    4995   253.8
  4999.5   253.3  5017.4  255.14  5039.4   260.4  5069.2  257.18    5115  260.14
  5288.7  259.68    5315   261.3  5618.2  260.13  6226.5  262.06  6237.7  260.18
  6258.8  256.56  6273.9  261.88  6281.7  262.23    6619  260.79  6626.6  257.87
  6659.3  261.57  7070.9  263.11  7517.2  271.92  7728.8  278.26  7780.2  282.28
#Mann= 7 ,-1 , 0
  3513.5     .11       0  4737.2     .15       0  4985.4     .09       0
  5039.4     .15       0  5288.7     .11       0  6226.5     .15       0
  6237.7     .11       0
Bank Sta=4985.4,5039.4
XS Rating Curve= 0 ,0
Exp/Cntr=0.3,0.1

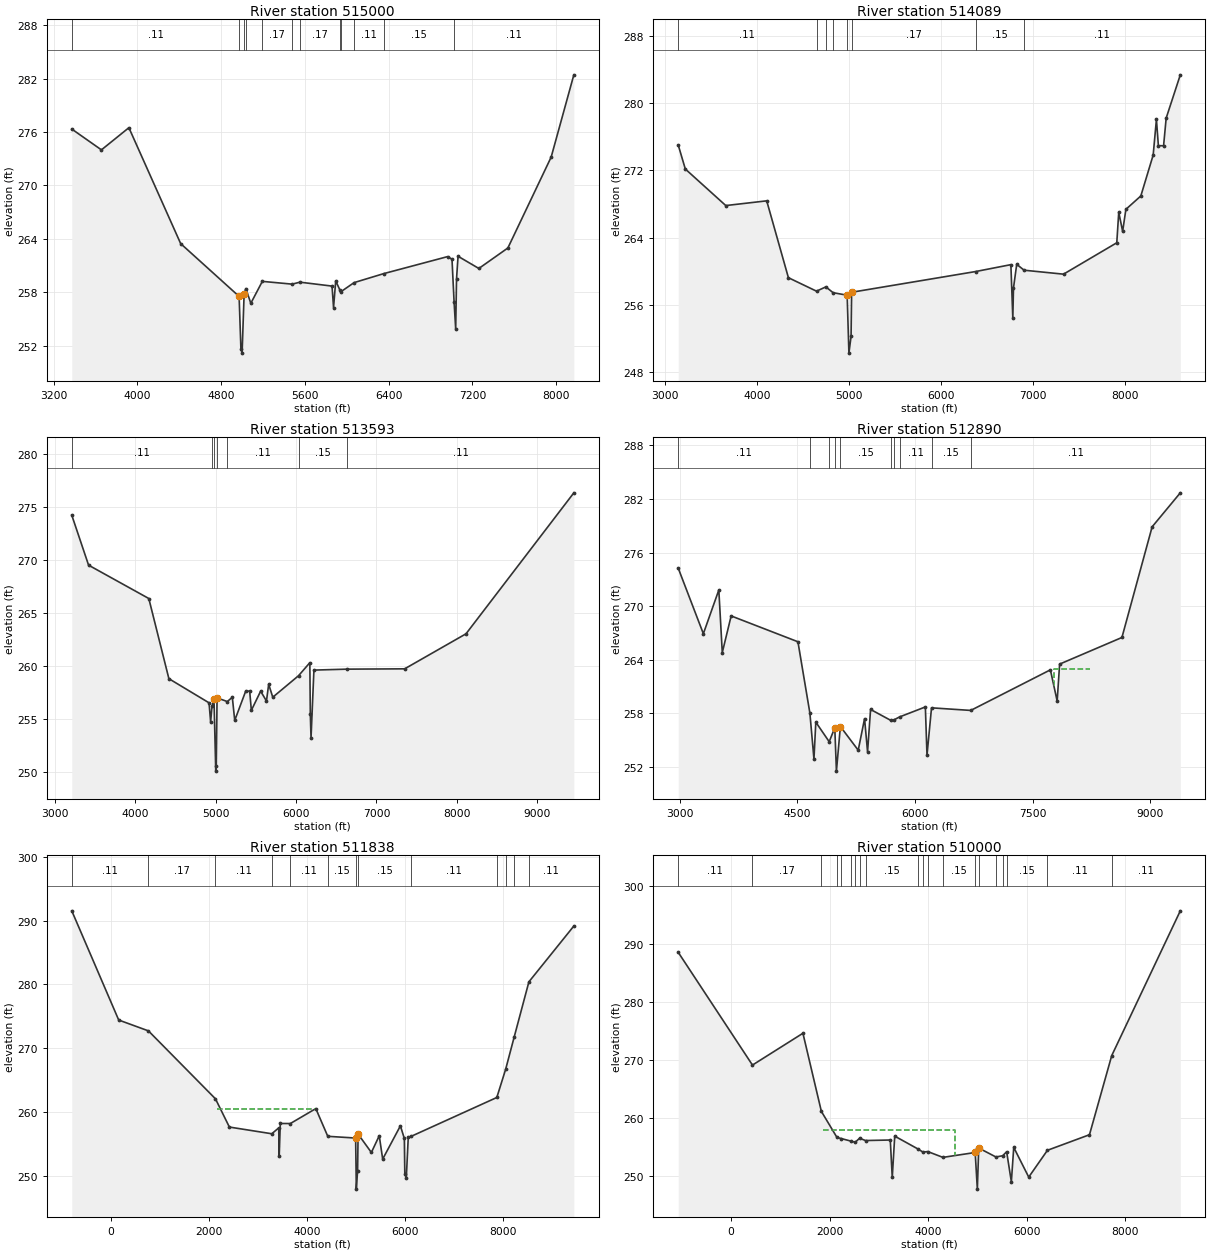
Type RM Length L Ch R = 1 ,515000  ,911,911,911
BEGIN DESCRIPTION:
WFSJ Main 507.0
END DESCRIPTION:
XS GIS Cut Line= 3
      3743396.02     10251681.64      3743175.62     10250069.24
       3741209.2     10247585.27
#Sta/Elev= 30
  3372.6  276.33  3655.8  273.99  3918.2  276.48  4412.8  263.46 4970.93  257.53
  4988.1  251.66  4999.5  251.16  5018.7  257.79  5035.1  258.41  5082.8  256.76
  5192.8  259.22  5477.2  258.91  5552.1  259.13  5858.5  258.69  5872.9  256.28
  5893.7  259.28  5932.2  258.28  5939.9  258.03  6069.1  259.08    6352  260.09
  6961.8     262  7004.3  261.71  7024.5  256.85  7039.6  253.88  7047.6  259.49
  7062.1  262.04  7260.8  260.67    7538  262.97  7951.5  273.18  8168.1  282.42
#Mann= 12 ,-1 , 0
  3372.6     .11       0 4970.93     .07       0  5018.7     .11       0
  5035.1     .15       0  5192.8     .17       0  5477.2     .15       0
  5552.1     .17       0  5932.2     .11       0  5939.9     .17       0
  6069.1     .11       0    6352     .15       0  7024.5     .11       0
Bank Sta=4970.93,5018.7
XS Rating Curve= 0 ,0
Exp/Cntr=0.3,0.1

Type RM Length L Ch R = 1 ,514089  ,496,496,496
BEGIN DESCRIPTION:
WFSJ Main 506.0
END DESCRIPTION:
XS GIS Cut Line= 3
      3744271.02      10251438.6      3743715.46     10249063.57
      3741548.83     10246952.49
#Sta/Elev= 30
    3142  275.01  3219.1  272.16  3659.5  267.82  4104.9  268.38    4341  259.25
  4646.8  257.65  4748.6  258.16  4827.3  257.47  4980.4  257.17  4999.5  250.29
  5022.9  252.27  5029.1  257.52  6377.5  259.98  6762.2   260.8  6783.4  254.43
  6790.5  258.02  6825.8  260.84  6906.1  260.14  7335.1  259.67  7914.8   263.4
  7936.2  267.03  7978.6  264.75  8013.9  267.37  8176.5  268.96  8310.9  273.82
  8346.2  278.05  8367.5  274.94  8424.1  274.92  8452.4  278.21  8606.2  283.35
#Mann= 8 ,-1 , 0
    3142     .11       0  4646.8     .15       0  4748.6     .11       0
  4827.3     .17       0  4980.4     .06       0  5029.1     .17       0
  6377.5     .15       0  6906.1     .11       0
Bank Sta=4980.4,5029.1
XS Rating Curve= 0 ,0
Exp/Cntr=0.3,0.1

Type RM Length L Ch R = 1 ,513593  ,703,703,703
BEGIN DESCRIPTION:
WFSJ Main 505.0
END DESCRIPTION:
XS GIS Cut Line= 3
      3744339.59     10251440.33      3744339.59     10249396.04
      3741984.53     10245909.02
#Sta/Elev= 30
  3206.5  274.25  3415.8  269.53  4165.8  266.38  4415.8  258.81  4915.8  256.53
  4935.8  254.73  4952.4   256.2 4977.46  256.91  4999.5  250.08  5005.8   250.6
  5015.8     257  5142.9  256.65  5205.8  257.05  5235.8  254.87  5370.7   257.6
  5421.7  257.65  5442.7  255.82  5558.5  257.63  5630.9   256.7  5658.5  258.28
  5709.4  257.06  6030.5  259.09    6171  260.32    6177  255.45  6185.9  253.21
  6221.9  259.62  6635.8  259.71  7351.9  259.74  8116.1  263.05  9458.6  276.36
#Mann= 7 ,-1 , 0
  3206.5     .11       0  4952.4     .15       0 4977.46     .09       0
  5015.8     .15       0  5142.9     .11       0  6030.5     .15       0
  6635.8     .11       0
Bank Sta=4977.46,5015.8
XS Rating Curve= 0 ,0
Exp/Cntr=0.3,0.1

Type RM Length L Ch R = 1 ,512890  ,1052,1052,1052
BEGIN DESCRIPTION:
WFSJ Main 504.0
END DESCRIPTION:
XS GIS Cut Line= 3
      3744339.58     10251440.34      3745074.84     10249858.71
      3743738.04     10245396.94
#Sta/Elev= 30
  2982.5  274.25  3302.8  266.92    3500  271.81  3544.1  264.81  3657.2  268.91
  4508.7  266.02    4661  258.05    4713   252.9  4736.7  257.03  4907.3  254.84
  4978.7   256.4  4999.5  251.55  5050.1  256.54  5277.5  253.89  5358.3  257.42
  5396.6   253.7  5434.9  258.45  5694.2  257.22  5732.4  257.28    5804  257.61
  6133.5  258.73  6154.4  253.33  6212.1  258.63    6712  258.34  7727.8  262.88
  7814.2  259.39  7845.5  263.52    8640   266.5  9025.2  278.88  9384.4  282.68
#Mann= 10 ,-1 , 0
  2982.5     .11       0    4661     .17       0  4907.3     .15       0
  4978.7     .09       0  5050.1     .15       0  5694.2     .11       0
  5732.4     .15       0    5804     .11       0  6212.1     .15       0
    6712     .11       0
#XS Ineff= 1 ,-1
    7772    8230  262.92
Permanent Ineff=
       F
Bank Sta=4978.7,5050.1
XS Rating Curve= 0 ,0
Exp/Cntr=0.3,0.1

Type RM Length L Ch R = 1 ,511838  ,1838,1838,1838
BEGIN DESCRIPTION:
WFSJ Main 503.0
END DESCRIPTION:
XS GIS Cut Line= 4
      3746978.05     10255158.19      3746755.23     10252660.69
      3745908.17     10250340.48      3745491.62      10245094.6
#Sta/Elev= 30
  -803.8  291.52   153.5  274.42   759.8  272.72  2126.9  262.08  2410.8  257.66
  3275.6  256.61  3417.1  257.53  3426.7  253.07  3449.1  258.22  3653.7  258.21
  4173.6  260.55  4417.5  256.21  4985.6  255.94  4999.5  247.94  5025.7  250.84
  5035.7  256.56  5306.6  253.68  5467.1   256.3  5537.3  252.64  5898.4  257.85
  5978.7  255.88  5988.7  250.31  6018.8  249.66  6058.9  256.05  6122.5  256.22
    7865  262.29    8046  266.73  8217.2   271.7  8519.3   280.4    9436  289.14
#Mann= 13 ,-1 , 0
  -803.8     .11       0   759.8     .17       0  2126.9     .11       0
  3275.6     .15       0  3653.7     .11       0  4417.5     .15       0
  4985.6     .09       0  5035.7     .15       0  6122.5     .11       0
    7865     .15       0    8046     .11       0  8217.2     .17       0
  8519.3     .11       0
#XS Ineff= 1 ,-1
    2150  4163.8  260.54
Permanent Ineff=
       F
Bank Sta=4985.6,5035.7
XS Rating Curve= 0 ,0
Exp/Cntr=0.3,0.1

Type RM Length L Ch R = 1 ,510000  ,1064,1064,1064
BEGIN DESCRIPTION:
WFSJ Main 502.0
END DESCRIPTION:
XS GIS Cut Line= 4
      3747140.81     10255060.56      3747041.26     10252542.35
      3747269.09     10248996.74       3745738.9     10245171.22
#Sta/Elev= 30
 -1073.1  288.59   433.9  269.17  1458.4  274.65  1832.8  261.19  2149.1  256.71
  2232.2  256.52  2424.9  256.09  2520.2  255.88  2608.3  256.56  2730.2  256.17
    3232  256.26  3272.1  249.81  3322.2  256.93  3797.3   254.7    3895  254.18
  3993.2  254.27  4300.6  253.27  4955.6  254.11  4999.5   247.8  5027.6  254.88
  5376.5  253.34  5513.7  253.55  5594.5  254.24    5690  249.06  5738.4  254.99
  6042.7  249.87  6422.6  254.49  7275.9  257.17  7727.8   270.8  9120.2  295.74
#Mann= 20 ,-1 , 0
 -1073.1     .11       0   433.9     .17       0  1832.8     .11       0
  2149.1     .17       0  2232.2     .11       0  2424.9     .17       0
  2520.2     .15       0  2608.3     .11       0  2730.2     .15       0
  3797.3     .17       0    3895     .15       0  3993.2     .17       0
  4300.6     .15       0  4955.6     .09       0  5027.6     .15       0
  5376.5     .15       0  5513.7     .11       0  5594.5     .15       0
  6422.6     .11       0  7727.8     .11       0
#XS Ineff= 1 ,-1
    1870  4544.7  257.98
Permanent Ineff=
       F
Bank Sta=4955.6,5027.6
XS Rating Curve= 0 ,0
Exp/Cntr=0.3,0.1

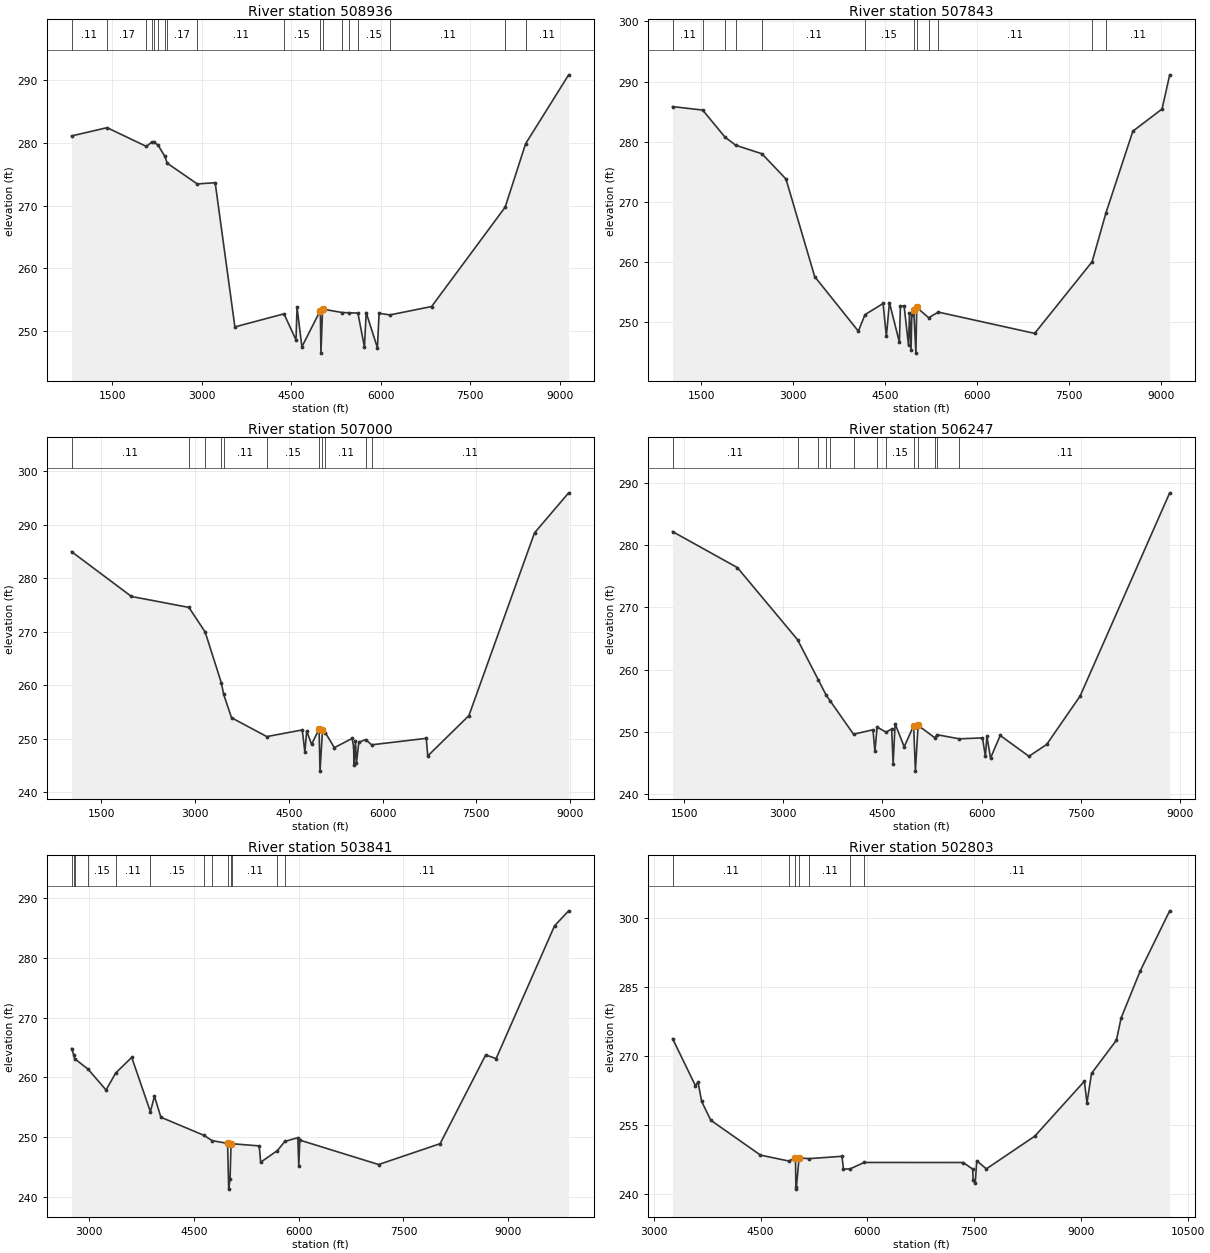
Type RM Length L Ch R = 1 ,508936  ,1093,1093,1093
BEGIN DESCRIPTION:
WFSJ Main 501.0
END DESCRIPTION:
XS GIS Cut Line= 3
      3749697.24      10252775.4      3748460.03     10250034.17
      3746207.66      10245210.3
#Sta/Elev= 30
   819.7  281.09  1415.7  282.41  2073.9  279.42  2161.1  280.08  2202.8  280.14
    2274  279.57  2383.7  277.83    2424  276.74  2927.6  273.44  3227.2  273.64
  3557.4  250.66  4380.4  252.74  4581.8  248.58  4599.1  253.79  4680.4  247.49
  4989.4  253.27  4999.5  246.48    5027   253.5  5355.4  252.95  5477.4  252.91
  5619.3  252.86  5728.9  247.43  5757.6  252.95  5945.9  247.33  5974.3  252.83
  6156.5  252.57  6854.6  253.91  8086.6  269.74  8429.5  279.85    9151  290.83
#Mann= 18 ,-1 , 0
   819.7     .11       0  1415.7     .17       0  2073.9     .11       0
  2161.1     .17       0  2202.8     .11       0    2274     .17       0
  2383.7     .11       0    2424     .17       0  2927.6     .11       0
  4380.4     .15       0  4989.4     .09       0    5027     .15       0
  5355.4     .11       0  5477.4     .17       0  5619.3     .15       0
  6156.5     .11       0  8086.6     .17       0  8429.5     .11       0
Bank Sta=4989.4,5027
XS Rating Curve= 0 ,0
Exp/Cntr=0.3,0.1

Type RM Length L Ch R = 1 ,507843  ,843,843,843
BEGIN DESCRIPTION:
WFSJ Main 500.0
END DESCRIPTION:
XS GIS Cut Line= 3
      3749879.51     10252723.26      3748434.21     10248699.85
      3747470.67     10244988.93
#Sta/Elev= 30
  1029.9  285.84  1521.1  285.26    1885  280.77  2059.5  279.42  2487.2     278
  2879.6  273.81  3348.6  257.58  4060.5  248.51  4169.1  251.26  4464.3  253.11
  4517.4  247.63  4567.4  253.27  4729.9  246.68  4746.5  252.74  4807.9  252.64
  4878.7  246.15  4894.8  251.46  4920.2  245.36  4931.8  251.12  4963.7  252.06
  4999.5  244.86  5012.4  252.46  5207.1  250.75  5365.3  251.68  6936.2  248.14
  7873.6  260.05  8100.9  268.22  8538.1  281.75  9014.5  285.44    9139  291.12
#Mann= 12 ,-1 , 0
  1029.9     .11       0  1521.1     .17       0    1885     .11       0
  2059.5     .17       0  2487.2     .11       0  4169.1     .15       0
  4963.7     .09       0  5012.4     .15       0  5207.1     .17       0
  5365.3     .11       0  7873.6     .15       0  8100.9     .11       0
Bank Sta=4963.7,5012.4
XS Rating Curve= 0 ,0
Exp/Cntr=0.3,0.1

Type RM Length L Ch R = 1 ,507000  ,753,753,753
BEGIN DESCRIPTION:
WFSJ Main 499.0
END DESCRIPTION:
XS GIS Cut Line= 3
      3751702.42     10251694.63       3749219.1     10248589.13
      3747705.03     10244910.75
#Sta/Elev= 30
  1023.7  284.97  1982.9  276.58  2901.8  274.54  3161.4  269.95    3421  260.43
  3458.4  258.27  3583.8  253.91  4147.7  250.39  4715.6  251.63  4757.2  247.47
    4786  251.43  4864.5  248.94  4984.7  251.79  4999.5  243.93  5039.2   251.6
  5086.6  251.09  5228.5  248.32  5513.6  250.04  5537.5  248.44  5542.9  245.05
  5566.9   249.5  5581.9  245.37  5620.2  249.32  5730.3  249.83  5824.6  248.85
  6699.5  250.06  6723.4  246.77  7381.7  254.31  8431.6  288.48  8977.8  295.96
#Mann= 11 ,-1 , 0
  1023.7     .11       0  2901.8     .17       0  3161.4     .11       0
    3421     .17       0  3458.4     .11       0  4147.7     .15       0
  4984.7     .09       0  5039.2     .15       0  5086.6     .11       0
  5730.3     .15       0  5824.6     .11       0
Bank Sta=4984.7,5039.2
XS Rating Curve= 0 ,0
Exp/Cntr=0.3,0.1

Type RM Length L Ch R = 1 ,506247  ,2406,2406,2406
BEGIN DESCRIPTION:
WFSJ Main 498.0
END DESCRIPTION:
XS GIS Cut Line= 3
      3751832.63     10251525.34      3749996.71     10248530.58
      3748199.84     10244949.86
#Sta/Elev= 30
  1326.4  282.21  2306.3  276.42  3217.6   264.8    3533   258.3    3651  255.85
  3707.2  255.01  4063.5  249.59  4357.6  250.31  4387.1  246.84  4420.5  250.72
  4557.2  249.93  4640.5  250.44  4662.6  244.86  4692.7  251.27    4830  247.57
  4972.8  250.97  4999.5  243.65    5040  251.02  5292.7  249.02  5327.6  249.51
  5662.8  248.85  6013.4     249  6058.1  246.05  6080.5  249.29  6135.9  245.75
  6281.9  249.39  6716.6  246.04  6984.6  247.94  7490.2  255.73  8845.4  288.45
#Mann= 13 ,-1 , 0
  1326.4     .11       0  3217.6     .17       0    3533     .11       0
    3651     .15       0  3707.2     .11       0  4063.5     .15       0
  4420.5     .17       0  4557.2     .15       0  4972.8     .09       0
    5040     .15       0  5292.7     .11       0  5327.6     .15       0
  5662.8     .11       0
Bank Sta=4972.8,5040
XS Rating Curve= 0 ,0
Exp/Cntr=0.3,0.1

Type RM Length L Ch R = 1 ,503841  ,1038,1038,1038
BEGIN DESCRIPTION:
WFSJ Main 497.0
END DESCRIPTION:
XS GIS Cut Line= 3
      3752900.37     10250067.05      3750908.17     10248022.77
      3748151.83     10244773.56
#Sta/Elev= 30
  2749.7  264.84  2785.4  263.68  2793.9  263.14  2986.9  261.39  3243.7  257.91
  3381.5  260.74  3611.3  263.36  3878.5  254.29  3936.7  256.87  4028.7  253.36
  4648.5  250.32  4761.3  249.45  4983.3  248.99  4999.5  241.35  5018.7  243.04
  5032.9  248.95  5053.5  248.93  5435.9  248.57    5457  245.84  5696.9   247.8
  5802.8  249.32  5988.3  249.94  6002.6  245.21  6016.9  249.54    7145  245.46
  8024.9  248.94  8677.3  263.76  8826.7  263.16  9663.7  285.35    9865  287.84
#Mann= 13 ,-1 , 0
  2749.7     .11       0  2785.4     .15       0  2793.9     .11       0
  2986.9     .15       0  3381.5     .11       0  3878.5     .15       0
  4648.5     .11       0  4761.3     .15       0  4983.3     .09       0
  5032.9     .15       0  5053.5     .11       0  5696.9     .15       0
  5802.8     .11       0
Bank Sta=4983.3,5032.9
XS Rating Curve= 0 ,0
Exp/Cntr=0.3,0.1

Type RM Length L Ch R = 1 ,502803  ,803,803,803
BEGIN DESCRIPTION:
WFSJ Main 496.0
END DESCRIPTION:
XS GIS Cut Line= 4
      3753264.91      10249051.4        3752054.     10248205.06
      3749583.08      10245436.4      3748646.56     10243914.56
#Sta/Elev= 30
  3264.8  273.79  3586.4  263.55  3622.2  264.38  3672.8  260.16    3801  256.07
  4497.8   248.5  4892.9  247.22  4989.8  247.87    4995  241.61  4999.5  241.11
    5040  247.87  5181.2  247.73  5641.9  248.24  5662.8  245.45  5757.4  245.52
  5952.9   246.9  7341.6  246.89  7476.2  245.46  7482.9  243.05  7511.3  242.36
    7533  247.26  7667.6  245.51  8347.3  252.61  9042.8  264.53  9079.5  259.85
  9143.3  266.23  9492.6  273.44  9558.7  278.27  9827.3  288.51   10240  301.53
#Mann= 7 ,-1 , 0
  3264.8     .11       0  4892.9     .15       0  4989.8     .09       0
    5040     .15       0  5181.2     .11       0  5757.4     .15       0
  5952.9     .11       0
Bank Sta=4989.8,5040
XS Rating Curve= 0 ,0
Exp/Cntr=0.3,0.1

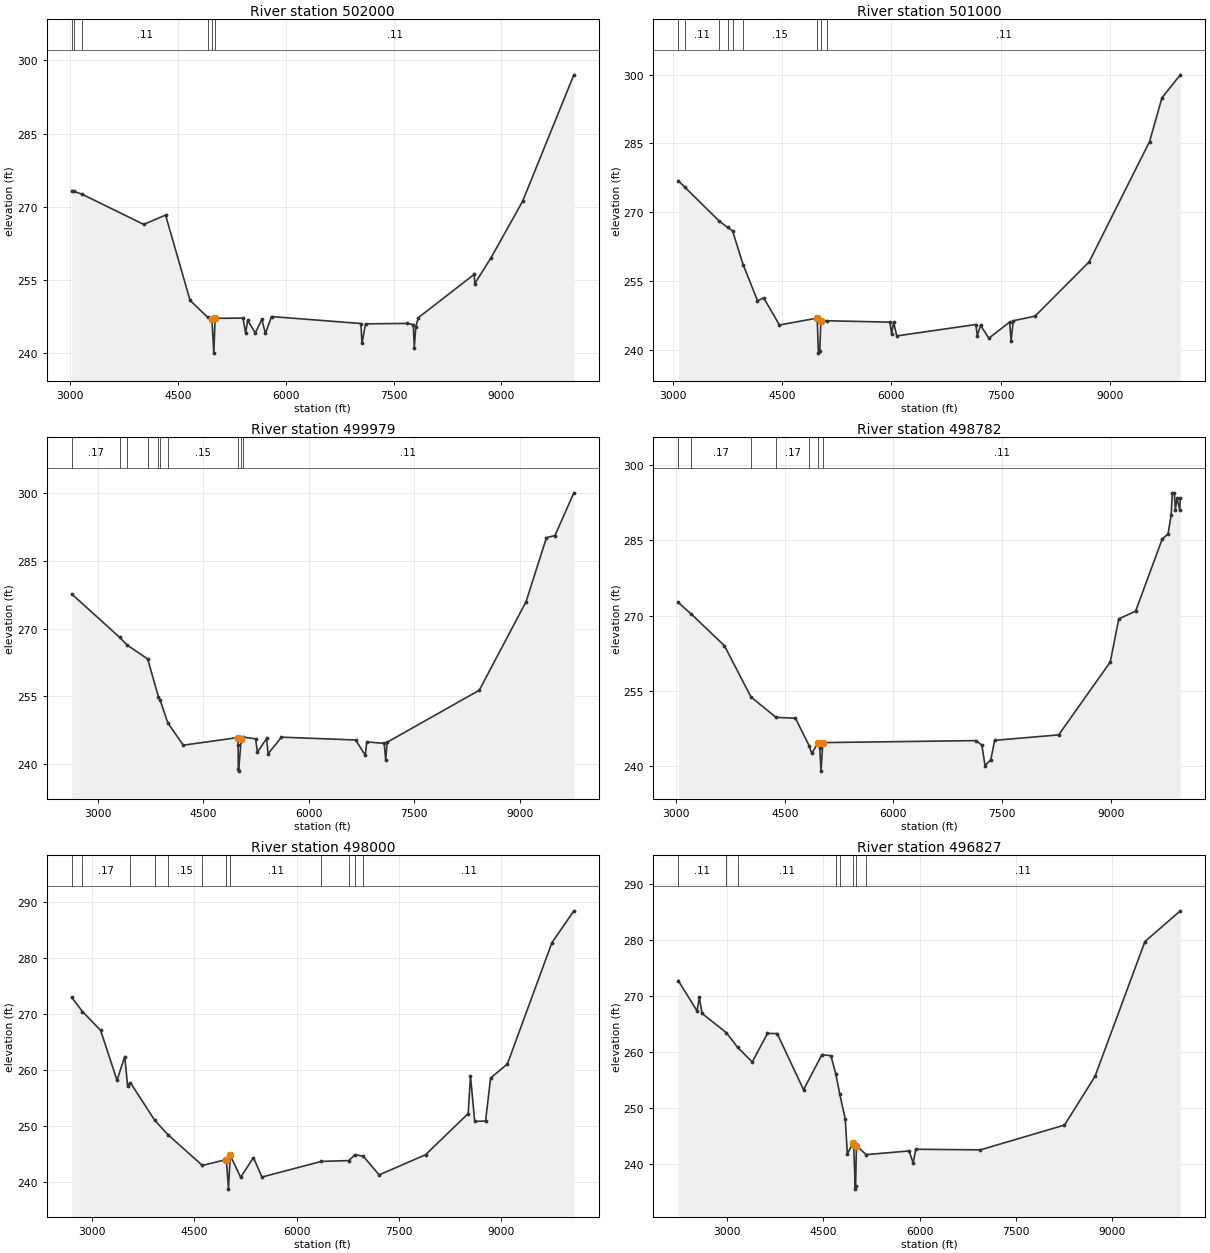
Type RM Length L Ch R = 1 ,502000  ,1000,1000,1000
BEGIN DESCRIPTION:
WFSJ Main 495.0
END DESCRIPTION:
XS GIS Cut Line= 3
      3754101.32     10248587.45      3752425.24     10247538.42
      3748867.86     10244011.08
#Sta/Elev= 30
  3022.7  273.29  3048.6  273.16  3162.3  272.59    4024  266.38  4328.1  268.29
  4668.8  250.82  4915.2  247.32  4973.3  246.91  4999.5  239.99  5017.5  247.12
  5406.4  247.18  5441.8  244.07    5470  246.74  5576.1  244.13    5668  246.92
  5717.5  244.02  5802.4  247.49  7046.9  246.06  7061.1  241.98  7110.5  245.99
  7683.3  246.08  7775.2  245.85  7789.4  241.12  7810.6  245.41  7845.9  247.26
  8623.8  256.15  8630.8  254.24  8857.1  259.54  9295.5  271.09 10009.7  297.04
#Mann= 6 ,-1 , 0
  3022.7     .11       0  3048.6     .17       0  3162.3     .11       0
  4915.2     .11       0  4973.3     .06       0  5017.5     .11       0
Bank Sta=4973.3,5017.5
XS Rating Curve= 0 ,0
Exp/Cntr=0.3,0.1

Type RM Length L Ch R = 1 ,501000  ,1021,1021,1021
BEGIN DESCRIPTION:
WFSJ Main 494.0
END DESCRIPTION:
XS GIS Cut Line= 3
      3754374.75     10248027.55      3752797.21     10246927.87
      3748853.91     10243912.96
#Sta/Elev= 30
    3077   276.9  3168.2  275.45  3637.1  268.08  3754.3  266.67  3821.8  265.91
  3966.7  258.56    4164  250.69  4250.4  251.25    4465  245.36  4983.3  246.86
  4999.5  239.21  5018.8  239.75  5033.3  246.31  5120.8  246.28  5981.1  245.98
  6003.6  243.34  6031.4  245.95  6074.3  242.97  7158.9  245.46  7179.7  243.04
  7223.3  245.29  7337.6  242.46  7622.3  245.99  7643.1  241.93  7672.1  246.28
  7971.4   247.3  8713.2  259.14  9542.1  285.42  9712.5     295  9963.8     300
#Mann= 9 ,-1 , 0
    3077     .17       0  3168.2     .11       0  3637.1     .17       0
  3754.3     .15       0  3821.8     .17       0  3966.7     .15       0
  4983.3     .09       0  5033.3     .15       0  5120.8     .11       0
Bank Sta=4983.3,5033.3
XS Rating Curve= 0 ,0
Exp/Cntr=0.3,0.1

Type RM Length L Ch R = 1 ,499979  ,1197,1197,1197
BEGIN DESCRIPTION:
WFSJ Main 493.0
END DESCRIPTION:
XS GIS Cut Line= 3
      3754934.61     10247545.75      3752821.65     10246295.05
      3748881.44     10243757.67
#Sta/Elev= 30
  2626.8  277.69  3308.5  268.08  3414.7  266.38  3706.8  263.29  3858.9  254.94
  3883.4  254.19    3992  249.16  4212.8  244.18  4984.9  245.86  4993.6   244.2
    4995  238.93  4999.5  238.43  5037.6  245.64  5055.8     246  5240.9   245.6
    5268  242.65  5398.1  245.67  5419.7  242.28    5610  245.96  6665.7  245.33
  6801.7  241.95  6823.2  244.91    7071  244.58  7092.2  240.88  7113.3  244.84
  8423.2  256.36  9088.7  275.99  9379.1  290.19    9500  290.66  9768.7  300.13
#Mann= 10 ,-1 , 0
  2626.8     .17       0  3308.5     .11       0  3414.7     .17       0
  3706.8     .15       0  3858.9     .11       0  3883.4     .17       0
    3992     .15       0  4984.9     .09       0  5037.6     .15       0
  5055.8     .11       0
Bank Sta=4984.9,5037.6
XS Rating Curve= 0 ,0
Exp/Cntr=0.3,0.1

Type RM Length L Ch R = 1 ,498782  ,782,782,782
BEGIN DESCRIPTION:
WFSJ Main 492.0
END DESCRIPTION:
XS GIS Cut Line= 3
      3755060.07      10247141.4      3753567.02      10246160.5
      3749113.91     10243582.38
#Sta/Elev= 30
  3028.4  272.65  3205.7  270.38  3665.2  264.05  4033.6  253.81  4379.1  249.76
  4646.5   249.6  4836.1  244.11  4871.6  242.59  4960.8  244.73  4982.4  243.75
  4999.5  239.06  5025.4  244.74  7140.5  245.14  7220.9  244.23    7264  240.15
  7344.4  241.37  7397.4  245.19  8281.3  246.28    8993  260.79  9110.7  269.38
  9343.4  270.92  9710.5  285.27  9790.8  286.29  9833.9  290.02  9849.7  294.44
    9877  294.48  9892.7  291.13  9914.3  293.48  9951.6  291.07  9960.4  293.36
#Mann= 7 ,-1 , 0
  3028.4     .11       0  3205.7     .17       0  4033.6     .11       0
  4379.1     .17       0  4836.1     .11       0  4960.8     .06       0
  5025.4     .11       0
Bank Sta=4960.8,5025.4
XS Rating Curve= 0 ,0
Exp/Cntr=0.3,0.1

Type RM Length L Ch R = 1 ,498000  ,1173,1173,1173
BEGIN DESCRIPTION:
WFSJ Main 491.0
END DESCRIPTION:
XS GIS Cut Line= 3
      3755442.02     10247045.92      3753750.25     10245484.65
      3749165.99     10243313.28
#Sta/Elev= 30
  2697.9  272.99  2854.3  270.47  3121.9  267.09  3362.4  258.16  3475.8  262.41
  3518.3  257.14  3557.4  257.76  3917.8  250.97  4110.5  248.43  4615.6  242.92
  4968.8  243.97  4999.5  238.68  5025.2  244.74  5178.9   240.8  5366.4  244.33
  5491.1  240.84  6363.4  243.64  6766.2  243.79  6863.1  244.86  6980.8  244.55
    7213  241.23  7894.8  244.84    8520   252.2  8554.5  258.91  8616.5   250.8
  8775.7  250.87  8849.5  258.56  9096.7  261.09  9749.6  282.77 10072.5  288.49
#Mann= 12 ,-1 , 0
  2697.9     .11       0  2854.3     .17       0  3557.4     .15       0
  3917.8     .11       0  4110.5     .15       0  4615.6     .11       0
  4968.8     .06       0  5025.2     .11       0  6363.4     .15       0
  6766.2     .11       0  6863.1     .15       0  6980.8     .11       0
Bank Sta=4968.8,5025.2
XS Rating Curve= 0 ,0
Exp/Cntr=0.3,0.1

Type RM Length L Ch R = 1 ,496827  ,1267,1267,1267
BEGIN DESCRIPTION:
WFSJ Main 490.0
END DESCRIPTION:
XS GIS Cut Line= 3
      3756014.95     10246412.25      3755060.08     10245084.11
      3749183.35     10243174.39
#Sta/Elev= 30
  2244.4  272.71  2537.2   267.3  2572.9   269.7  2615.3  266.85  2992.5  263.43
  3169.4   260.8  3396.6   258.2  3633.5  263.29  3784.5  263.27    4195  253.25
  4481.8  259.52  4620.9  259.32  4699.1  255.98  4759.1  252.44  4844.6  247.97
  4876.5  241.82  4965.5  243.72  4977.6   242.8  4999.5  235.53    5005  236.03
  5018.1  243.29  5169.2  241.68  5838.2  242.34  5901.3  240.17  5941.4  242.64
  6947.6  242.53  8256.6  246.95  8731.2  255.62  9508.5  279.67 10059.4  285.15
#Mann= 8 ,-1 , 0
  2244.4     .11       0  2992.5     .17       0  3169.4     .11       0
  4699.1     .17       0  4759.1     .15       0  4965.5     .09       0
  5018.1     .15       0  5169.2     .11       0
Bank Sta=4965.5,5018.1
XS Rating Curve= 0 ,0
Exp/Cntr=0.3,0.1