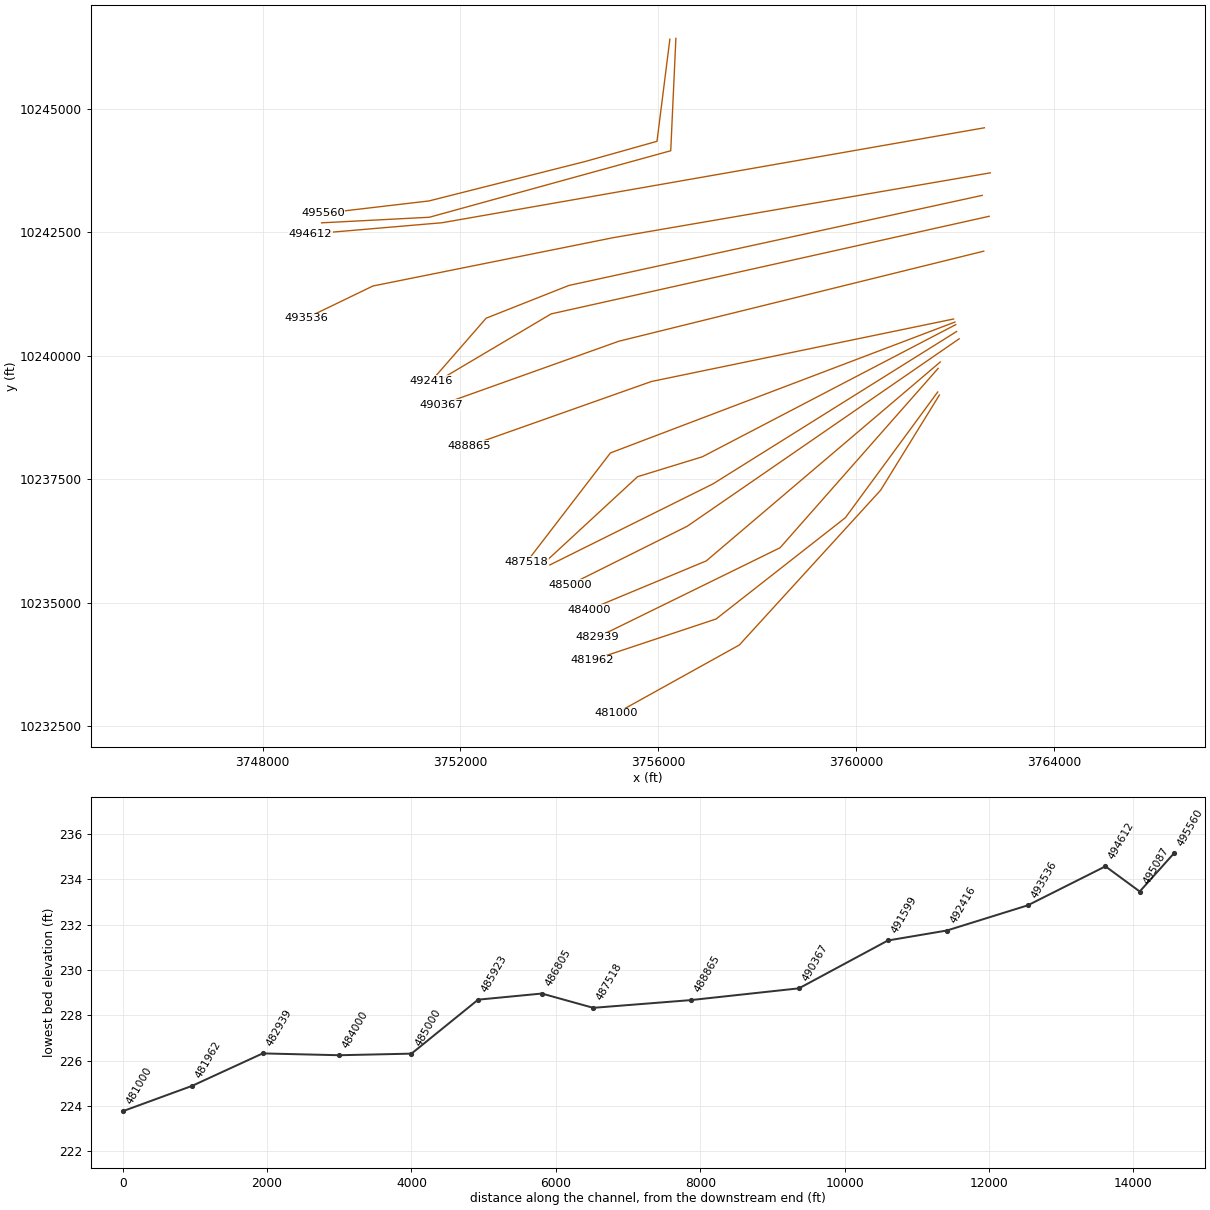
HEC-RAS study WFSJ Main.prj: WFSJ Main Base Level Engineering

--- WFSJ Main.g01 (geometry) --- (continued)

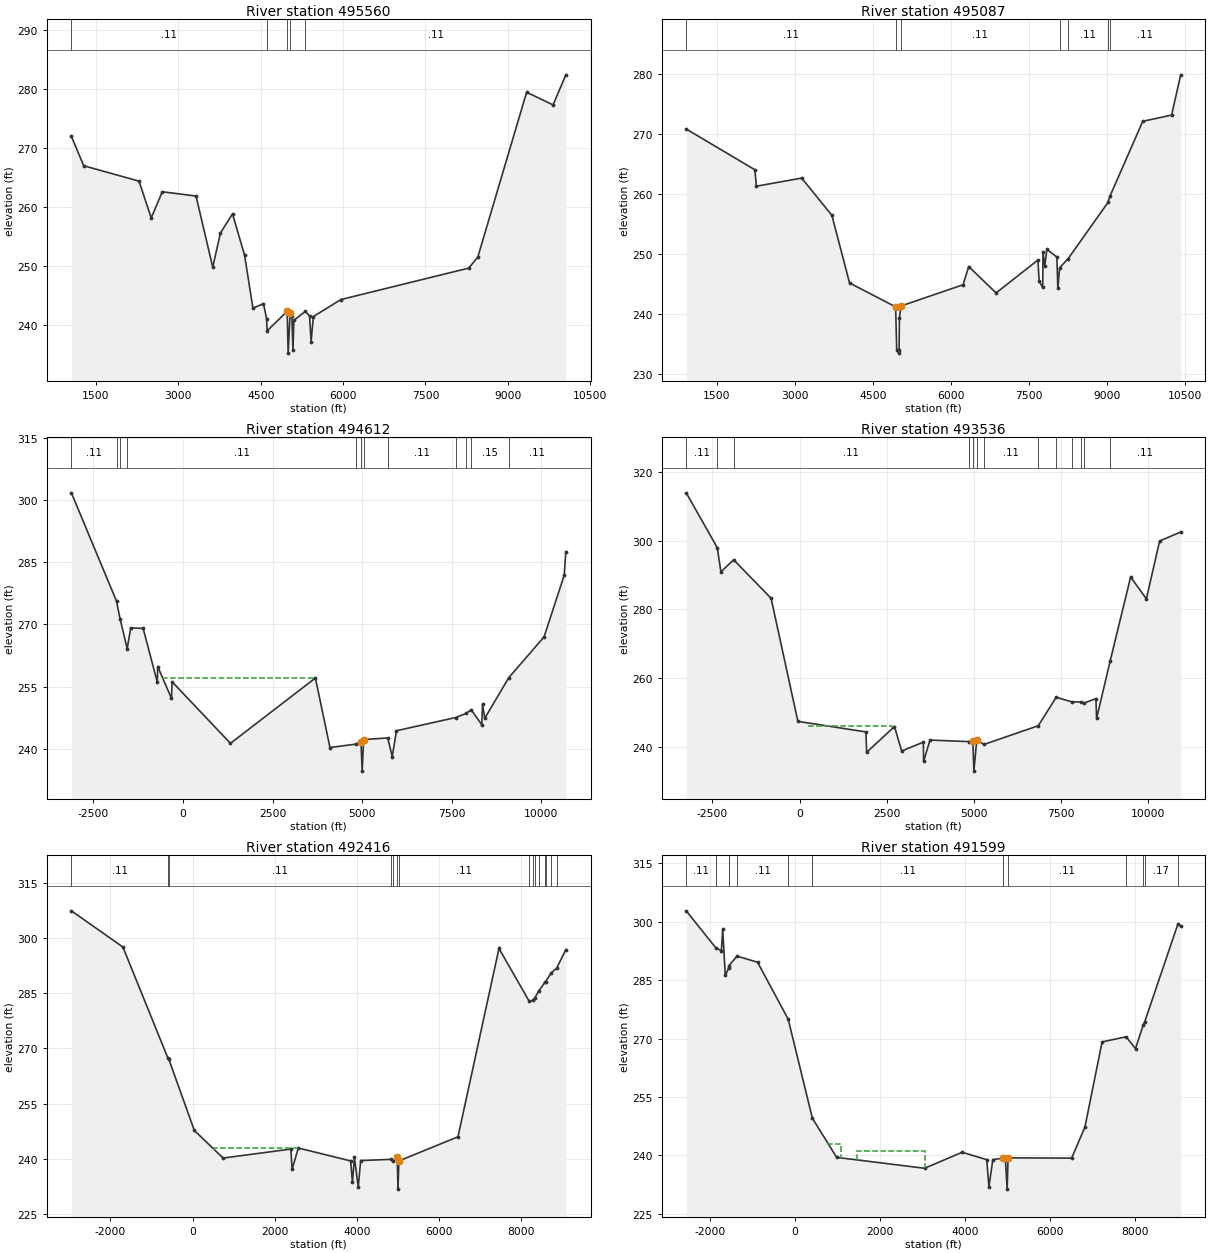
Type RM Length L Ch R = 1 ,495560  ,473,473,473
BEGIN DESCRIPTION:
WFSJ Main 489.0
END DESCRIPTION:
XS GIS Cut Line= 5
      3756231.95     10246403.55      3755971.54     10244337.59
      3754521.89      10243929.6      3751362.16     10243130.99
      3749218.06     10242879.25
#Sta/Elev= 30
  1051.5  271.97  1275.7  266.97  2283.7  264.35  2505.4   258.1    2707  262.55
  3321.7  261.82  3625.9  249.75  3766.5  255.55  3986.3  258.79  4206.2  251.76
  4357.9  242.78  4550.5  243.54  4606.4  241.01  4616.9  238.93 4982.08  242.25
  4999.5  235.14  5035.9  242.04  5067.1  241.45  5087.5  235.64    5103  240.71
  5312.6  242.23  5390.2  241.45  5417.5  237.11  5458.8  241.35  5959.6  244.24
  8287.5  249.58  8453.8  251.45    9343  279.45  9824.5   277.3 10057.7  282.41
#Mann= 5 ,-1 , 0
  1051.5     .11       0  4606.4     .15       0 4982.08     .09       0
  5035.9     .15       0  5312.6     .11       0
Bank Sta=4982.08,5035.9
XS Rating Curve= 0 ,0
Exp/Cntr=0.3,0.1

Type RM Length L Ch R = 1 ,495087  ,475,475,475
BEGIN DESCRIPTION:
WFSJ Main 488.0
END DESCRIPTION:
XS GIS Cut Line= 4
      3756353.48     10246420.92      3756249.32     10244146.61
      3751370.84     10242801.13      3749192.47      10242688.3
#Sta/Elev= 30
   907.4  270.77  2228.1  263.99  2258.7  261.25  3129.6   262.6  3711.1  256.41
  4051.5  245.14  4938.7  241.16  4959.5  233.96  4999.5  233.46  5005.3  233.96
  5011.3  239.34  5042.4  241.31  6236.6  244.84  6344.9  247.88  6872.7  243.48
  7677.3  248.96  7701.4  245.42  7770.1  244.39  7775.3  250.26  7809.7  247.99
  7849.2  250.73  8041.8  249.46  8061.1  244.24  8095.7  247.67  8260.7   249.2
  9025.6  258.54  9065.1   259.6  9695.2  272.05 10250.4  273.09   10426  279.79
#Mann= 7 ,-1 , 0
   907.4     .11       0  4938.7     .07       0  5042.4     .11       0
  8095.7     .15       0  8260.7     .11       0  9025.6     .15       0
  9065.1     .11       0
#XS Ineff= 1 ,-1
  6344.9    8375  247.88
Permanent Ineff=
       F
Bank Sta=4938.7,5042.4
XS Rating Curve= 0 ,0
Exp/Cntr=0.3,0.1

Type RM Length L Ch R = 1 ,494612  ,1076,1076,1076
BEGIN DESCRIPTION:
WFSJ Main 487.0
END DESCRIPTION:
XS GIS Cut Line= 3
      3762588.29     10244611.02      3751629.09     10242690.45
      3748971.75     10242462.68
#Sta/Elev= 30
 -3111.8  301.79 -1853.4  275.63 -1753.9  271.33 -1554.8  264.18 -1456.2  269.18
 -1109.8  269.03  -715.4  256.05    -704  259.83  -319.4  252.13  -303.3  256.16
  1325.2  241.28  3695.4  257.06  4101.2  240.27  4837.2  241.11  4967.1  241.59
  4999.5  234.57    5041   242.2  5713.3  242.58  5838.2  238.09    5957  244.33
    7605  247.51  7903.7  248.52  8039.1  249.41  8336.8  245.78  8356.9   250.8
  8419.6  247.34  9089.8  257.15 10073.2  266.99 10635.2  281.87 10681.5  287.59
#Mann= 12 ,-1 , 0
 -3111.8     .11       0 -1853.4     .17       0 -1753.9     .15       0
 -1554.8     .11       0  4837.2     .15       0  4967.1     .09       0
    5041     .15       0  5713.3     .11       0    7605     .15       0
  7903.7     .17       0  8039.1     .15       0  9089.8     .11       0
#XS Ineff= 1 ,-1
    -550  3695.4  257.06
Permanent Ineff=
       F
Bank Sta=4967.1,5041
XS Rating Curve= 0 ,0
Exp/Cntr=0.3,0.1

Type RM Length L Ch R = 1 ,493536  ,1120,1120,1120
BEGIN DESCRIPTION:
WFSJ Main 486.0
END DESCRIPTION:
XS GIS Cut Line= 4
      3762707.69     10243699.57      3755079.61     10242386.63
      3750229.35     10241410.07      3748883.83     10240759.01
#Sta/Elev= 30
 -3250.7  313.96   -2359  297.95 -2256.5  290.92 -1890.7  294.45  -816.8  283.22
     -48  247.35  1903.9  244.28  1924.1  238.33  2722.5  245.85  2928.7  238.71
  3551.2   241.3  3557.8  235.66  3740.5   241.9  4852.5  241.46  4970.8  241.55
  4999.5  232.85    5083  241.92  5290.4  240.63  6847.1  246.08  7359.6  254.36
  7815.3  253.03  8070.8  253.02  8159.3  252.69  8500.2  253.98  8520.6  248.26
  8908.9  264.95  9496.1  289.42  9947.8  283.06 10327.5  299.91 10931.9  302.55
#Mann= 13 ,-1 , 0
 -3250.7     .11       0   -2359     .17       0 -1890.7     .11       0
  4852.5     .15       0  4970.8     .09       0    5083     .15       0
  5290.4     .11       0  6847.1     .17       0  7359.6     .11       0
  7815.3     .15       0  8070.8     .17       0  8159.3     .15       0
  8908.9     .11       0
#XS Ineff= 1 ,-1
     230  2662.5  246.01
Permanent Ineff=
       F
Bank Sta=4970.8,5083
XS Rating Curve= 0 ,0
Exp/Cntr=0.3,0.1

Type RM Length L Ch R = 1 ,492416  ,817,817,817
BEGIN DESCRIPTION:
WFSJ Main 485.0
END DESCRIPTION:
XS GIS Cut Line= 4
      3762544.91     10243243.84      3754189.85     10241420.92
      3752518.85     10240759.03      3751412.45     10239489.92
#Sta/Elev= 30
 -2947.8  307.41 -1694.3  297.57  -595.9  267.28  -576.1  267.04    43.5  247.71
   743.4  240.19  2393.4  242.63  2422.7  237.08  2574.2  242.92  3847.2  239.41
  3891.1  233.69  3940.2  240.34  4033.2  232.24    4091  239.51  4835.2  239.84
    4887   239.3  4981.5  240.47  4999.5  231.74  5022.5  239.41  6459.9  245.97
    7457  297.17  8188.9  282.91  8285.6  283.04  8323.8  283.62  8429.5   285.7
  8573.3  287.95  8593.5  288.16  8717.2  290.38  8861.1  291.83  9084.8  296.86
#Mann= 15 ,-1 , 0
 -2947.8     .11       0  -595.9     .15       0  -576.1     .11       0
  4835.2     .15       0    4887     .11       0  4981.5     .06       0
  5022.5     .11       0  8188.9     .17       0  8285.6     .11       0
  8323.8     .17       0  8429.5     .11       0  8573.3     .17       0
  8593.5     .11       0  8717.2     .17       0  8861.1     .11       0
#XS Ineff= 1 ,-1
     530  2574.2  242.92
Permanent Ineff=
       F
Bank Sta=4981.5,5022.5
XS Rating Curve= 0 ,0
Exp/Cntr=0.3,0.1

Type RM Length L Ch R = 1 ,491599  ,1232,1232,1232
BEGIN DESCRIPTION:
WFSJ Main 484.0
END DESCRIPTION:
XS GIS Cut Line= 3
      3762685.94     10242820.66      3753831.78     10240845.83
      3751618.28     10239532.92
#Sta/Elev= 30
 -2558.4  302.82 -1863.3  293.33 -1730.5  292.56 -1699.7  298.06 -1638.2   286.2
 -1562.4  288.02 -1554.7  288.69 -1361.8  291.18  -879.3  289.62  -158.3  275.01
   412.6  249.52   984.7  239.46  3054.3  236.66  3940.2  240.77  4519.4  238.87
  4570.7  231.93  4662.9  238.88  4898.5  239.26    4960  238.67  4999.5   231.3
  5021.5  239.34  6518.5  239.27  6832.1  247.27  7235.5  269.13  7801.6  270.45
  8022.9  267.41  8204.2  273.48  8240.6  274.33  9021.5  299.43  9086.9  298.83
#Mann= 13 ,-1 , 0
 -2558.4     .11       0 -1863.3     .17       0 -1562.4     .11       0
 -1554.7     .17       0 -1361.8     .11       0  -158.3     .17       0
   412.6     .11       0  4898.5     .06       0  5021.5     .11       0
  7801.6     .17       0  8204.2     .11       0  8240.6     .17       0
  9021.5     .11       0
#XS Ineff= 2 ,-1
    1475  3068.3  241.22     765    1092   242.9
Permanent Ineff=
       F       F
Bank Sta=4898.5,5021.5
XS Rating Curve= 0 ,0
Exp/Cntr=0.3,0.1

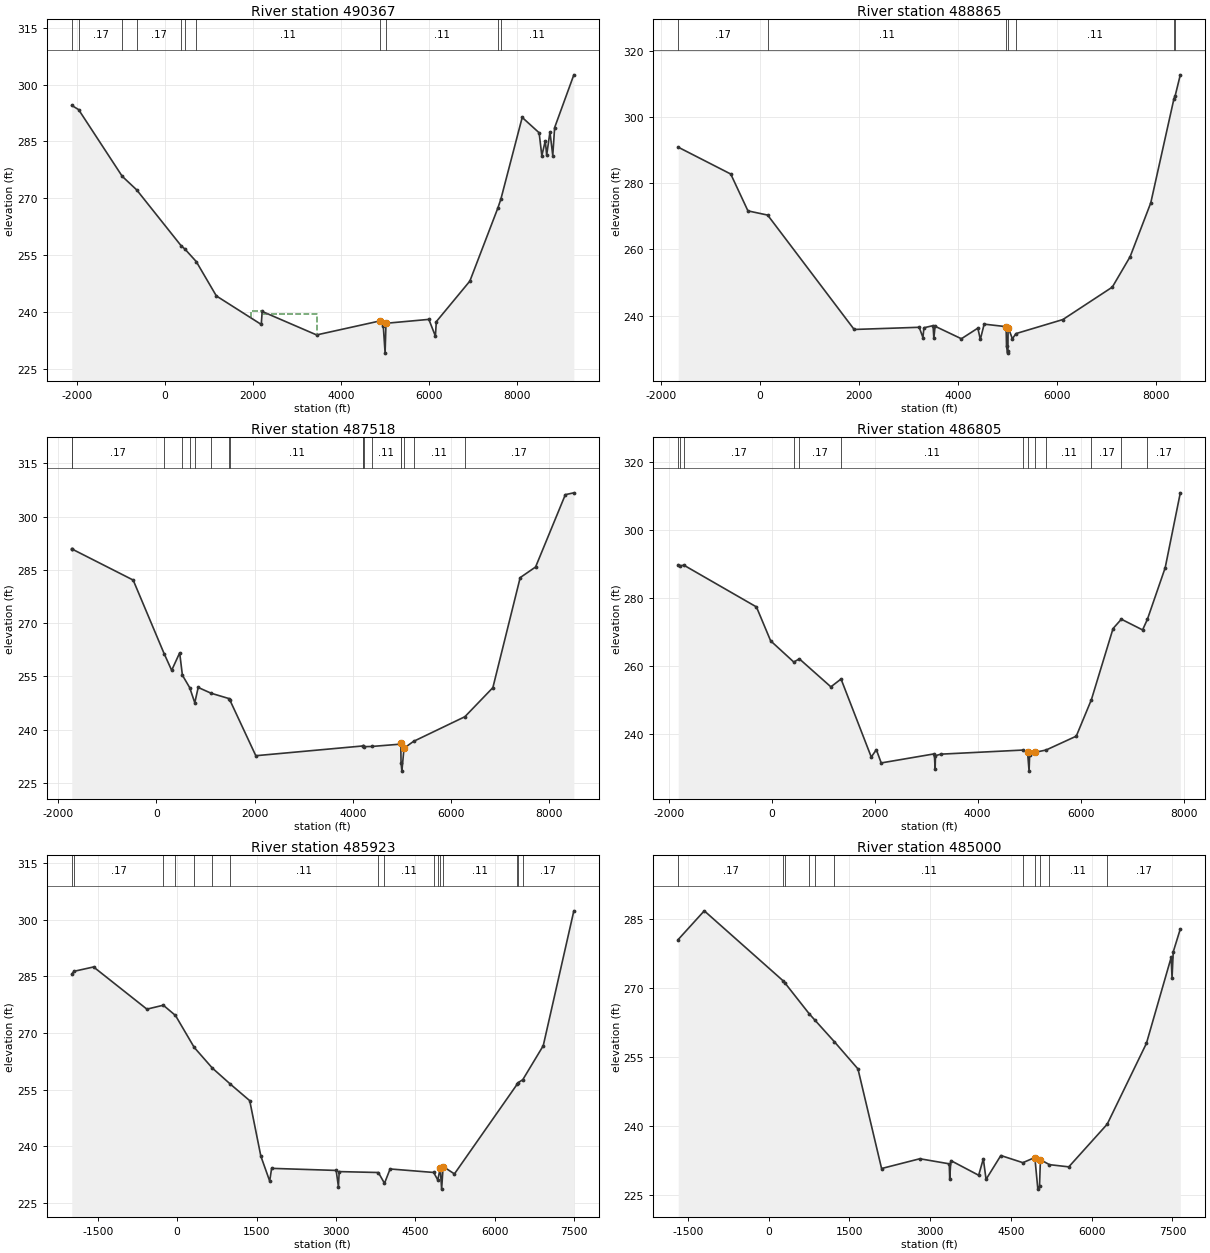
Type RM Length L Ch R = 1 ,490367  ,1502,1502,1502
BEGIN DESCRIPTION:
WFSJ Main 483.0
END DESCRIPTION:
XS GIS Cut Line= 3
      3762576.13     10242114.97       3755197.7     10240292.06
      3751617.01     10239011.69
#Sta/Elev= 30
 -2116.8  294.52 -1961.3   293.4    -971  275.82  -643.3  272.25   367.6   257.5
     453  256.63   710.9  253.33  1167.3  244.27  2187.1  236.75  2207.7  240.18
  3443.8  233.99  4881.9  237.68    4958  236.39  4999.5  229.19  5019.8  237.06
  5993.1  238.09  6141.8  233.67    6163   237.5  6924.6  248.19  7559.9  267.44
  7629.4  269.82  8113.3  291.35  8497.6   287.3  8559.1  281.25  8637.5  285.17
  8669.3  281.43  8743.8   287.5  8807.4   281.3  8849.9  288.67  9286.2  302.58
#Mann= 11 ,-1 , 0
 -2116.8     .11       0 -1961.3     .17       0    -971     .11       0
  -643.3     .17       0   367.6     .11       0     453     .17       0
   710.9     .11       0  4881.9     .06       0  5019.8     .11       0
  7559.9     .17       0  7629.4     .11       0
#XS Ineff= 2 ,-1
    2215  3462.4  239.55    1964  2207.7  240.18
Permanent Ineff=
       F       F
Bank Sta=4881.9,5019.8
XS Rating Curve= 0 ,0
Exp/Cntr=0.3,0.1

Type RM Length L Ch R = 1 ,488865  ,1347,1347,1347
BEGIN DESCRIPTION:
WFSJ Main 482.0
END DESCRIPTION:
XS GIS Cut Line= 3
      3761966.06     10240742.57       3755859.6     10239478.26
      3752182.08     10238176.48
#Sta/Elev= 30
 -1649.6  290.82  -589.4  282.72  -242.2   271.6   155.8  270.33  1902.4  235.81
  3215.4  236.47  3291.2  233.36  3310.7  236.32  3495.5  236.97  3511.4  233.13
  3536.3  236.78  4067.3  233.01  4399.6  236.21  4449.8  232.79  4526.9  237.42
  4970.1  236.66    4979  230.68  4999.5  228.67  5006.3  229.17  5009.9  235.55
  5015.2  236.31  5097.2  232.99  5168.4  234.56  6115.8   238.8  7114.2  248.59
  7474.4  257.78    7891  274.02  8358.4  305.41  8384.2  306.36  8487.5  312.66
#Mann= 7 ,-1 , 0
 -1649.6     .17       0   155.8     .11       0  4970.1     .07       0
  5015.2     .15       0  5168.4     .11       0  8358.4     .17       0
  8384.2     .11       0
Bank Sta=4970.1,5015.2
XS Rating Curve= 0 ,0
Exp/Cntr=0.3,0.1

Type RM Length L Ch R = 1 ,487518  ,713,713,713
BEGIN DESCRIPTION:
WFSJ Main 481.0
END DESCRIPTION:
XS GIS Cut Line= 3
      3761992.39     10240680.51       3755030.6     10238032.95
       3753337.9      10235828.1
#Sta/Elev= 30
 -1725.2  290.94 -1717.7  290.84  -474.4  282.12   156.2  261.41   309.9  256.71
   472.9  261.63   528.5  255.34   676.7  251.84   780.8  247.58     850  251.89
  1113.3  250.26  1478.8  248.75    1497  248.29  2023.9  232.67  4213.7  235.43
  4216.2  235.33  4218.9  235.22  4384.3  235.27  4973.3  235.93  4977.1  236.16
  4982.6  230.63  4999.5  228.33  5042.8  234.78  5237.6  236.71  6283.1  243.65
  6853.1  251.83  7409.6  282.81  7723.2   285.8  8329.6  306.17  8502.7  306.68
#Mann= 18 ,-1 , 0
 -1725.2     .11       0 -1717.7     .17       0   156.2     .11       0
   528.5     .17       0   676.7     .11       0   780.8     .17       0
  1113.3     .11       0  1478.8     .17       0    1497     .11       0
  4213.7     .15       0  4216.2     .11       0  4218.9     .15       0
  4384.3     .11       0  4973.3     .15       0  4977.1     .09       0
  5042.8     .15       0  5237.6     .11       0  6283.1     .17       0
Bank Sta=4977.1,5042.8
XS Rating Curve= 0 ,0
Exp/Cntr=0.3,0.1

Type RM Length L Ch R = 1 ,486805  ,882,882,882
BEGIN DESCRIPTION:
WFSJ Main 480.0
END DESCRIPTION:
XS GIS Cut Line= 4
      3762009.78     10240628.44      3756888.24     10237954.82
      3755579.72     10237552.43      3753668.53      10235785.4
#Sta/Elev= 30
 -1813.2   289.6 -1788.3  289.32 -1702.2   289.5  -294.6  277.24   -18.8  267.27
   431.1  261.03   538.1  261.98  1151.2  253.74    1348  256.05    1935  233.11
  2034.2  235.26  2128.1  231.37    3160  234.04    3175  229.46  3182.1  233.51
  3286.9  233.95  4888.2  235.16    4969  234.65  4999.5  228.96  5010.1  233.74
  5118.7  234.49  5331.6  235.18  5915.8  239.24  6209.6  249.98  6630.2  270.89
  6791.2  273.63  7203.5  270.48  7296.9   273.6  7642.4  288.76  7936.1  310.79
#Mann= 13 ,-1 , 0
 -1813.2     .17       0 -1788.3     .11       0 -1702.2     .17       0
   431.1     .11       0   538.1     .17       0    1348     .11       0
  4888.2     .15       0    4969     .09       0  5118.7     .15       0
  5331.6     .11       0  6209.6     .17       0  6791.2     .11       0
  7296.9     .17       0
Bank Sta=4969,5118.7
XS Rating Curve= 0 ,0
Exp/Cntr=0.3,0.1

Type RM Length L Ch R = 1 ,485923  ,923,923,923
BEGIN DESCRIPTION:
WFSJ Main 479.0
END DESCRIPTION:
XS GIS Cut Line= 3
       3762027.1     10240489.52      3757105.26     10237407.95
      3753806.67     10235767.34
#Sta/Elev= 30
 -1992.2  285.62 -1952.5  286.35 -1580.1  287.51  -571.9  276.34  -261.9  277.38
     -32  274.67   322.4  266.21   663.6  260.76  1004.9   256.5  1371.9  252.11
  1581.8  237.44  1749.2  230.82  1785.7  234.19  3005.7  233.64  3048.2  229.35
  3063.5  233.33  3803.3  233.09  3919.4  230.23  4025.3  234.03  4849.4   233.1
  4926.9   231.1  4973.4  234.27  4999.5  228.69  5027.6  234.67  5241.4  232.72
  6429.7  256.51  6446.3  256.89  6533.3  257.66  6920.1  266.65  7498.8  302.37
#Mann= 16 ,-1 , 0
 -1992.2     .11       0 -1952.5     .17       0  -261.9     .11       0
     -32     .17       0   322.4     .11       0   663.6     .17       0
  1004.9     .11       0  3803.3     .15       0  3919.4     .11       0
  4849.4     .15       0  4926.9     .11       0  4973.4     .06       0
  5027.6     .11       0  6429.7     .17       0  6446.3     .11       0
  6533.3     .17       0
Bank Sta=4973.4,5027.6
XS Rating Curve= 0 ,0
Exp/Cntr=0.3,0.1

Type RM Length L Ch R = 1 ,485000  ,1000,1000,1000
BEGIN DESCRIPTION:
WFSJ Main 478.0
END DESCRIPTION:
XS GIS Cut Line= 3
      3762079.24     10240341.99      3756581.76       10236549.
      3754214.61     10235368.01
#Sta/Elev= 30
   -1679  280.46 -1195.3  286.68     270  271.49   302.4  271.04   753.7  264.34
   858.5  262.98  1221.1  258.28  1658.6  252.39  2097.4  230.78  2807.9   232.9
  3354.2   231.8    3363  228.57    3384   232.5  3900.5  229.32  3987.1  232.89
  4037.8  228.43  4312.2   233.6  4721.5  232.05    4944  233.17  4999.5  226.31
  5030.6  226.99  5047.4   232.7  5214.4  231.62  5574.3  231.14  6287.3  240.39
    7016  257.93  7475.1  276.56  7491.9  272.13  7514.3  277.79  7645.4  282.74
#Mann= 11 ,-1 , 0
   -1679     .17       0     270     .11       0   302.4     .17       0
   753.7     .11       0   858.5     .17       0  1221.1     .11       0
  4721.5     .15       0    4944     .09       0  5047.4     .15       0
  5214.4     .11       0  6287.3     .17       0
Bank Sta=4944,5047.4
XS Rating Curve= 0 ,0
Exp/Cntr=0.3,0.1

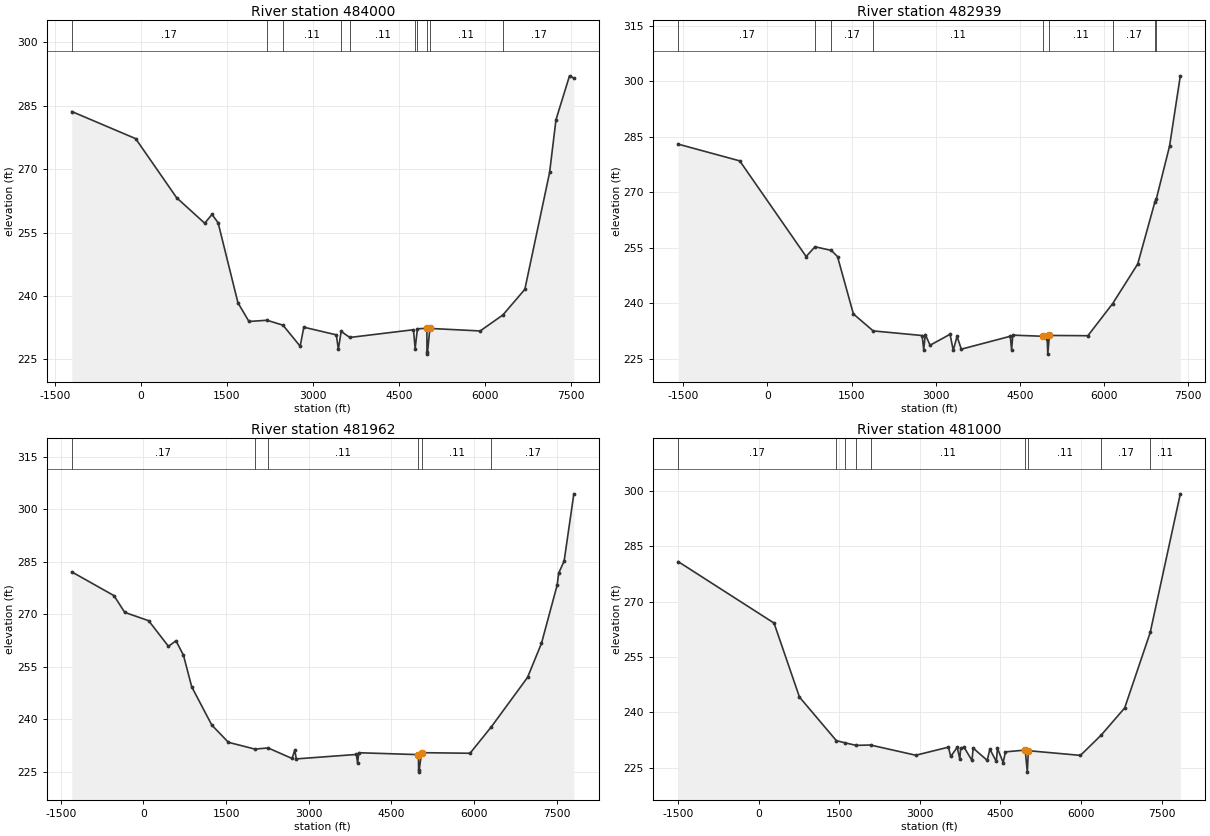
Type RM Length L Ch R = 1 ,484000  ,1061,1061,1061
BEGIN DESCRIPTION:
WFSJ Main 477.0
END DESCRIPTION:
XS GIS Cut Line= 3
      3761697.26     10239873.22      3756968.13     10235848.99
      3754607.05     10234865.29
#Sta/Elev= 30
 -1209.6  283.61   -94.3   277.2   621.8  263.22  1111.6   257.2    1239  259.27
  1345.5  257.32  1692.5  238.37  1884.7  233.96  2198.5  234.25  2478.6  233.09
  2778.6  228.11  2842.3  232.61  3410.1   230.8  3445.2   227.4  3495.2  231.62
  3644.8  230.18  4757.5  232.01  4786.5  227.55    4826  232.23  4991.4  232.36
  4993.6  226.74  4999.5  226.24  5043.6  232.32  5922.1  231.72  6319.4  235.51
  6702.1  241.56  7134.4  269.19    7246  281.68  7482.1  292.05  7557.8  291.49
#Mann= 10 ,-1 , 0
 -1209.6     .17       0  2198.5     .15       0  2478.6     .11       0
  3495.2     .15       0  3644.8     .11       0  4786.5     .15       0
    4826     .11       0  4991.4     .06       0  5043.6     .11       0
  6319.4     .17       0
Bank Sta=4991.4,5043.6
XS Rating Curve= 0 ,0
Exp/Cntr=0.3,0.1

Type RM Length L Ch R = 1 ,482939  ,977,977,977
BEGIN DESCRIPTION:
WFSJ Main 476.0
END DESCRIPTION:
XS GIS Cut Line= 3
       3761653.9     10239743.05      3758459.42     10236114.55
      3754762.15     10234300.62
#Sta/Elev= 30
 -1590.1  282.98  -493.6  278.47   690.4  252.66   848.7  255.29  1140.6   254.3
  1250.1  252.64  1532.9  237.17  1885.5  232.59  2758.7  231.34  2787.1  227.53
  2815.6  231.61    2901  228.72  3257.1  231.68  3313.6  227.33  3381.1  231.11
  3457.6  227.66  4331.3  231.14  4353.8  227.47  4376.3  231.44 4912.75  231.14
  4989.1  230.45  4999.5  226.32  5028.2  231.36  5714.3  231.29  6157.1  239.98
  6602.6  250.63  6910.5  267.45  6936.7  268.31  7170.4  282.43  7362.5  301.42
#Mann= 9 ,-1 , 0
 -1590.1     .17       0   848.7     .11       0  1140.6     .17       0
  1885.5     .11       0 4912.75     .06       0  5028.2     .11       0
  6157.1     .17       0  6910.5     .11       0  6936.7     .17       0
Bank Sta=4912.75,5028.2
XS Rating Curve= 0 ,0
Exp/Cntr=0.3,0.1

Type RM Length L Ch R = 1 ,481962  ,962,962,962
BEGIN DESCRIPTION:
WFSJ Main 475.0
END DESCRIPTION:
XS GIS Cut Line= 4
      3761645.17     10239265.56      3759778.87     10236722.18
      3757166.02     10234673.57      3754666.01     10233840.24
#Sta/Elev= 30
 -1299.8   282.1  -533.3  275.31  -339.2  270.53    95.7  268.15   454.6  260.83
   591.1  262.42   726.9  258.29   876.4  249.27  1240.9  238.34  1541.9  233.41
  2023.3  231.47  2262.4   231.8  2696.2   228.8    2746  231.11  2774.9  228.67
  3864.2  229.94  3886.8  227.43  3907.6  230.43  4990.6  229.89  4993.5  225.39
  4999.5  224.89  5046.7  230.45  5926.5  230.28    6314  237.85    6970  251.95
    7223  261.69  7507.6  278.33  7533.9  281.69  7634.1  285.21  7810.3   304.4
#Mann= 6 ,-1 , 0
 -1299.8     .17       0  2023.3     .15       0  2262.4     .11       0
  4990.6     .06       0  5046.7     .11       0    6314     .17       0
Bank Sta=4990.6,5046.7
XS Rating Curve= 0 ,0
Exp/Cntr=0.3,0.1

Type RM Length L Ch R = 1 ,481000  ,924,924,924
BEGIN DESCRIPTION:
WFSJ Main 474.0
END DESCRIPTION:
XS GIS Cut Line= 4
      3761679.89     10239204.79      3760490.67     10237277.74
      3757635.68     10234147.26      3755145.58     10232763.83
#Sta/Elev= 30
 -1501.3  280.83   283.1  264.17   756.2  244.12  1443.4   232.3    1600  231.73
  1811.4  231.03  2079.8  231.12    2922  228.35  3530.7  230.54  3573.3  228.01
  3693.5  230.49  3742.9   227.3    3757  230.18  3820.6  230.53  3969.2  226.93
  3990.8  230.29  4252.3  226.96  4302.3  229.98  4422.5  226.66  4443.5  230.24
  4549.6  226.35  4592.1  229.26  4960.3  229.75  4999.5  223.77  5018.9  229.58
  5988.9  228.31  6376.9  233.83  6812.6  241.17  7287.9  261.62  7848.6  299.21
#Mann= 9 ,-1 , 0
 -1501.3     .17       0  1443.4     .15       0    1600     .17       0
  1811.4     .15       0  2079.8     .11       0  4960.3     .06       0
  5018.9     .11       0  6376.9     .17       0  7287.9     .11       0
Bank Sta=4960.3,5018.9
XS Rating Curve= 0 ,0
Exp/Cntr=0.3,0.1