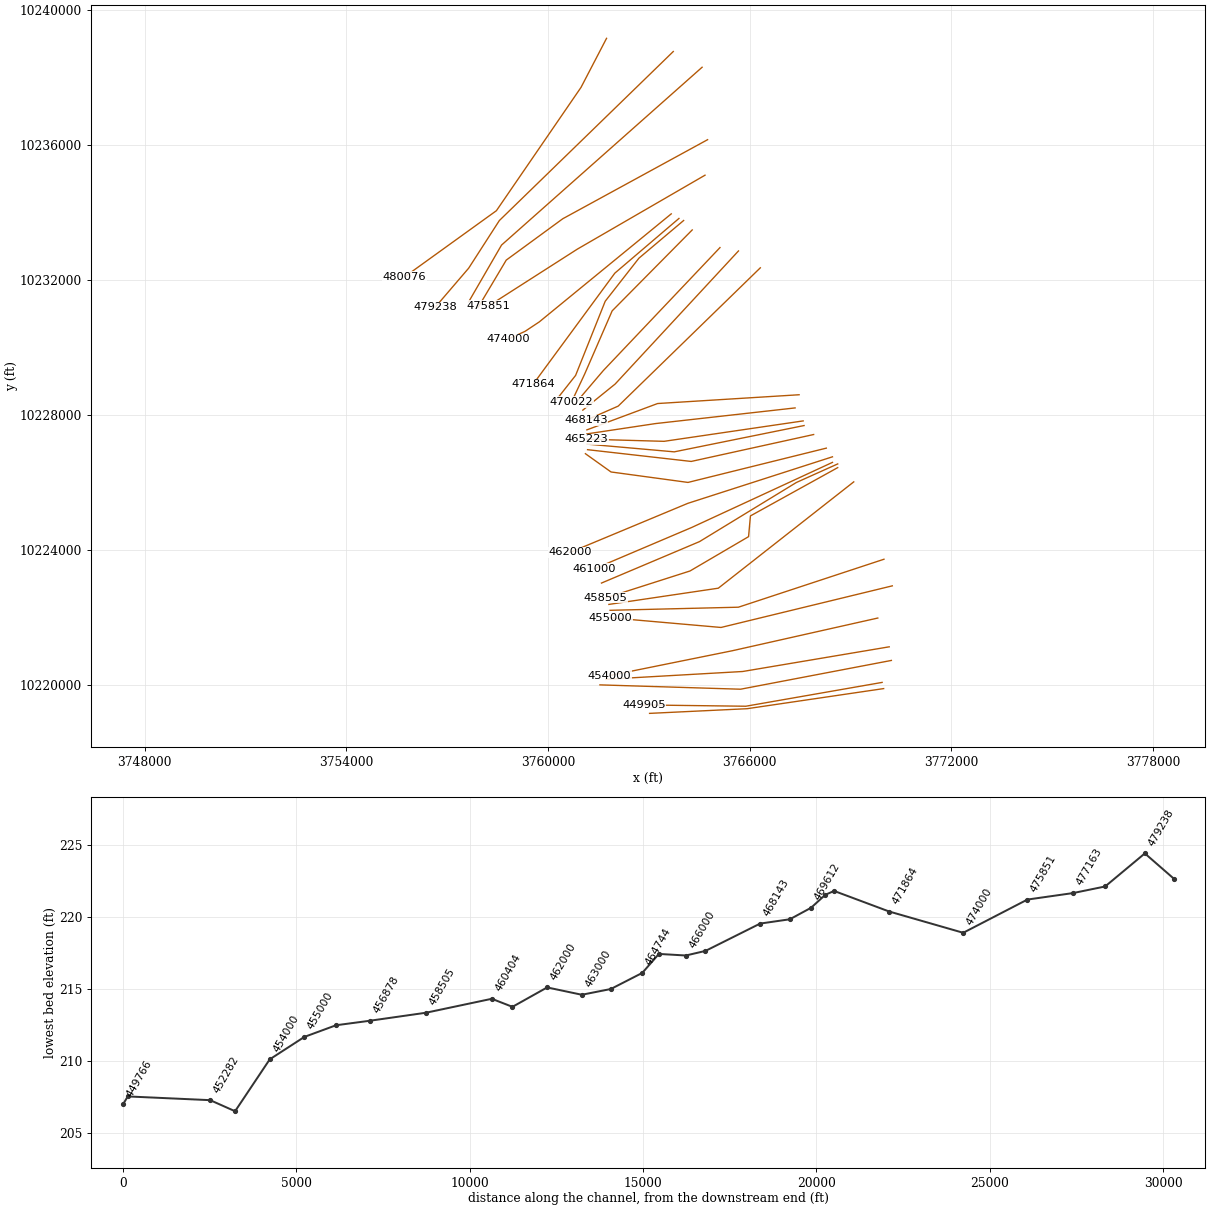
HEC-RAS study WFSJ Main.prj: WFSJ Main Base Level Engineering

--- WFSJ Main.g01 (geometry) --- (continued)

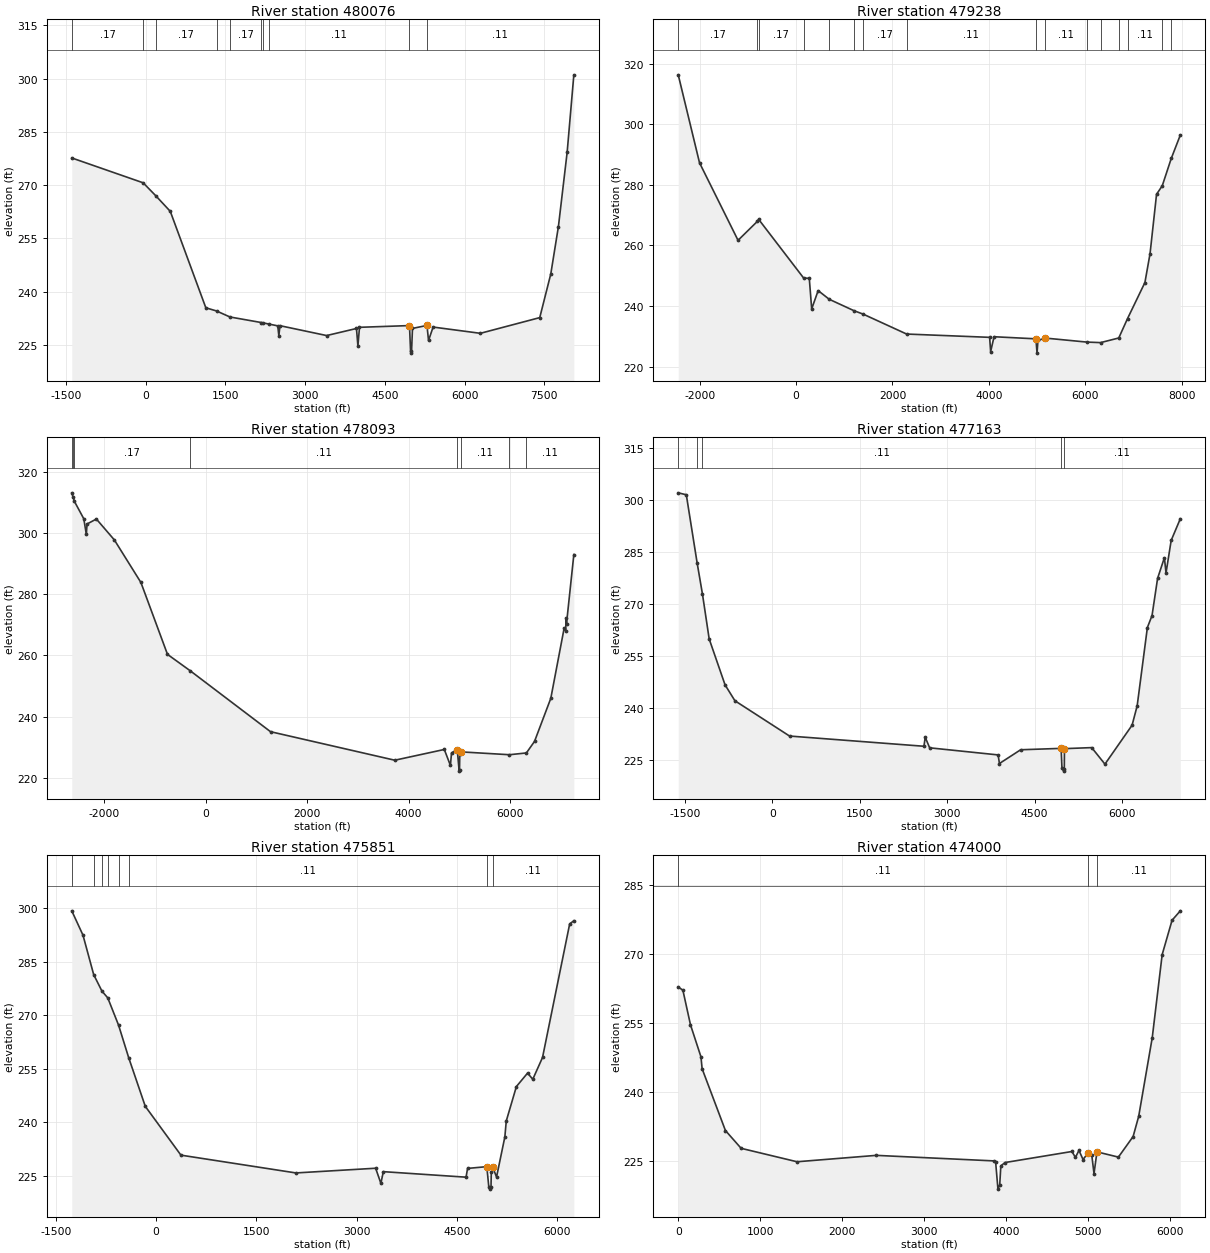
Type RM Length L Ch R = 1 ,480076  ,838,838,838
BEGIN DESCRIPTION:
WFSJ Main 473.0
END DESCRIPTION:
XS GIS Cut Line= 4
      3761742.84     10239165.76      3760983.29     10237711.77
      3758465.93     10234055.08      3755732.17     10232091.55
#Sta/Elev= 30
 -1391.7  277.65   -48.9  270.65   188.1  267.01   461.6  262.61  1130.5  235.45
  1332.2  234.55  1584.2  232.86  2172.3   231.3  2196.9  231.23  2313.4  230.88
  2483.3  230.36  2504.2  227.58  2525.2  230.41  3403.1  227.63  3964.5  229.62
  3991.6  224.67  4021.3  229.95  4961.8  230.44  4982.7  223.18  4999.5  222.68
  5018.3  229.64  5290.8  230.48  5320.3  226.24  5406.2  230.02  6295.2  228.26
  7412.5  232.68    7620  244.96  7763.8  258.34  7928.1  279.25    8054  301.06
#Mann= 10 ,-1 , 0
 -1391.7     .17       0   -48.9     .11       0   188.1     .17       0
  1332.2     .15       0  1584.2     .17       0  2172.3     .15       0
  2196.9     .17       0  2313.4     .11       0  4961.8     .06       0
  5290.8     .11       0
Bank Sta=4961.8,5290.8
XS Rating Curve= 0 ,0
Exp/Cntr=0.3,0.1

Type RM Length L Ch R = 1 ,479238  ,1145,1145,1145
BEGIN DESCRIPTION:
WFSJ Main 472.0
END DESCRIPTION:
XS GIS Cut Line= 4
      3763728.49      10238775.1      3758552.74     10233762.11
      3757641.28     10232351.52      3756642.99     10231190.47
#Sta/Elev= 30
 -2444.1  316.31 -2002.3  287.26 -1203.3  261.68  -801.3  267.95  -776.2  268.61
   156.3  249.25   274.8  249.11   324.4  239.04   458.7  245.08   688.8  242.21
    1203  238.44  1391.6  237.32    2294  230.74    4016  229.65  4037.1  224.95
  4107.9  229.85  4976.6  229.16  4999.5  224.44  5018.8  228.63  5169.9  229.41
  6028.8  228.09  6317.6  227.91  6695.1  229.44  6877.8  235.87  7237.6  247.74
  7344.1  257.28    7479  276.87  7597.8   279.7  7784.9  288.74    7972  296.42
#Mann= 16 ,-1 , 0
 -2444.1     .17       0  -801.3     .11       0  -776.2     .17       0
   156.3     .15       0   688.8     .17       0    1203     .11       0
  1391.6     .17       0    2294     .11       0  4976.6     .06       0
  5169.9     .11       0  6028.8     .17       0  6317.6     .15       0
  6695.1     .17       0  6877.8     .11       0  7597.8     .17       0
  7784.9     .11       0
Bank Sta=4976.6,5169.9
XS Rating Curve= 0 ,0
Exp/Cntr=0.3,0.1

Type RM Length L Ch R = 1 ,478093  ,930,930,930
BEGIN DESCRIPTION:
WFSJ Main 471.0
END DESCRIPTION:
XS GIS Cut Line= 3
       3764585.7     10238308.54      3758617.84     10233035.12
      3757642.87     10231355.99
#Sta/Elev= 30
 -2643.5  313.24   -2617  311.82 -2590.5  310.41 -2406.2  304.74 -2356.1  299.63
 -2341.9  303.04 -2157.9  304.66 -1804.1  297.84 -1279.6   283.9  -755.1  260.36
  -307.4     255  1277.7  235.05  3729.5  225.71  4706.6  229.23    4827  223.99
  4848.8   228.1  4961.7  229.21  4999.5  222.14  5006.6  222.64  5011.9  227.71
  5026.1  228.45  5990.8  227.51  6325.8  228.09  6486.3  231.87  6807.6  245.98
  7071.2  268.97  7101.5  268.14  7107.2  272.25  7117.2  270.41  7262.1  293.03
#Mann= 8 ,-1 , 0
 -2643.5     .17       0   -2617     .11       0 -2590.5     .17       0
  -307.4     .11       0  4961.7     .06       0  5026.1     .11       0
  5990.8     .15       0  6325.8     .11       0
Bank Sta=4961.7,5026.1
XS Rating Curve= 0 ,0
Exp/Cntr=0.3,0.1

Type RM Length L Ch R = 1 ,477163  ,1312,1312,1312
BEGIN DESCRIPTION:
WFSJ Main 470.0
END DESCRIPTION:
XS GIS Cut Line= 4
      3764748.52     10236160.14      3760440.76     10233816.37
       3758758.9     10232590.24      3757923.39     10231190.48
#Sta/Elev= 30
 -1614.7  302.04 -1476.1  301.48 -1290.5  281.81 -1198.4  272.74 -1083.8  259.85
  -811.2  246.59  -642.1     242   295.4  231.81  2601.7  228.86  2623.6  231.46
  2699.6  228.41  3874.6  226.36  3897.1  223.88    4261  227.85  4955.5  228.25
  4970.1  222.58  4999.4  221.68    5010  222.18  5013.2  228.17  5480.3  228.47
  5707.5   223.7  6173.3  234.94  6260.6  240.53  6435.8  263.15  6515.5  266.59
  6610.9  277.33  6727.7  283.31  6755.6  278.91  6844.4  288.31  7000.9  294.55
#Mann= 5 ,-1 , 0
 -1614.7     .11       0 -1290.5     .17       0 -1198.4     .11       0
  4955.5     .06       0  5013.2     .11       0
Bank Sta=4955.5,5013.2
XS Rating Curve= 0 ,0
Exp/Cntr=0.3,0.1

Type RM Length L Ch R = 1 ,475851  ,1851,1851,1851
BEGIN DESCRIPTION:
WFSJ Main 469.0
END DESCRIPTION:
XS GIS Cut Line= 3
      3764672.49     10235107.58      3760874.79     10232915.76
      3758238.04     10231233.88
#Sta/Elev= 30
 -1262.7  299.28 -1094.8  292.45  -934.8  281.39  -811.2  276.76  -724.2  274.87
  -562.4  267.21  -411.7  258.13  -162.8  244.45   370.6  230.76    2091  225.77
  3283.8  227.09  3362.5  222.85  3398.8  226.13  4636.7  224.58  4659.7  227.04
  4947.4  227.53  4977.9  221.73  4999.4  221.23    5010  221.73  5014.3  225.99
  5035.5  227.38    5093  224.63  5217.4  235.88  5238.5  240.34    5390     250
  5556.7  253.76  5635.4  252.05    5781  258.15  6187.2  295.61  6249.6   296.5
#Mann= 8 ,-1 , 0
 -1262.7     .17       0  -934.8     .11       0  -811.2     .17       0
  -724.2     .11       0  -562.4     .17       0  -411.7     .11       0
  4947.4     .06       0  5035.5     .11       0
Bank Sta=4947.4,5035.5
XS Rating Curve= 0 ,0
Exp/Cntr=0.3,0.1

Type RM Length L Ch R = 1 ,474000  ,2136,2136,2136
BEGIN DESCRIPTION:
WFSJ Main 468.0
END DESCRIPTION:
XS GIS Cut Line= 4
      3763667.85     10233961.07      3759741.84     10230757.72
      3759318.49     10230477.65       3758816.8     10230245.86
#Sta/Elev= 30
       0  262.86    56.7  262.17   149.3  254.66   277.2  247.68   291.5  245.09
   575.8  231.66   767.6  227.79  1449.7  224.87  2416.1  226.26    3859  225.05
  3872.9   224.9  3901.7  218.92  3923.5  219.88  3936.8  223.97  3987.8   224.7
  4804.2   227.1  4847.3  225.82  4890.4  227.34  4939.9  225.36  5003.8  226.83
  5046.4  226.36  5073.9  222.29    5110  227.02  5371.6  225.88  5551.4  230.36
  5619.4  234.77  5784.7  251.85  5905.8  269.91  6026.5  277.37  6127.1  279.42
#Mann= 3 , 0 , 0
       0     .11       0  5003.8     .06       0    5110     .11       0
Bank Sta=5003.8,5110
XS Rating Curve= 0 ,0
Exp/Cntr=0.3,0.1

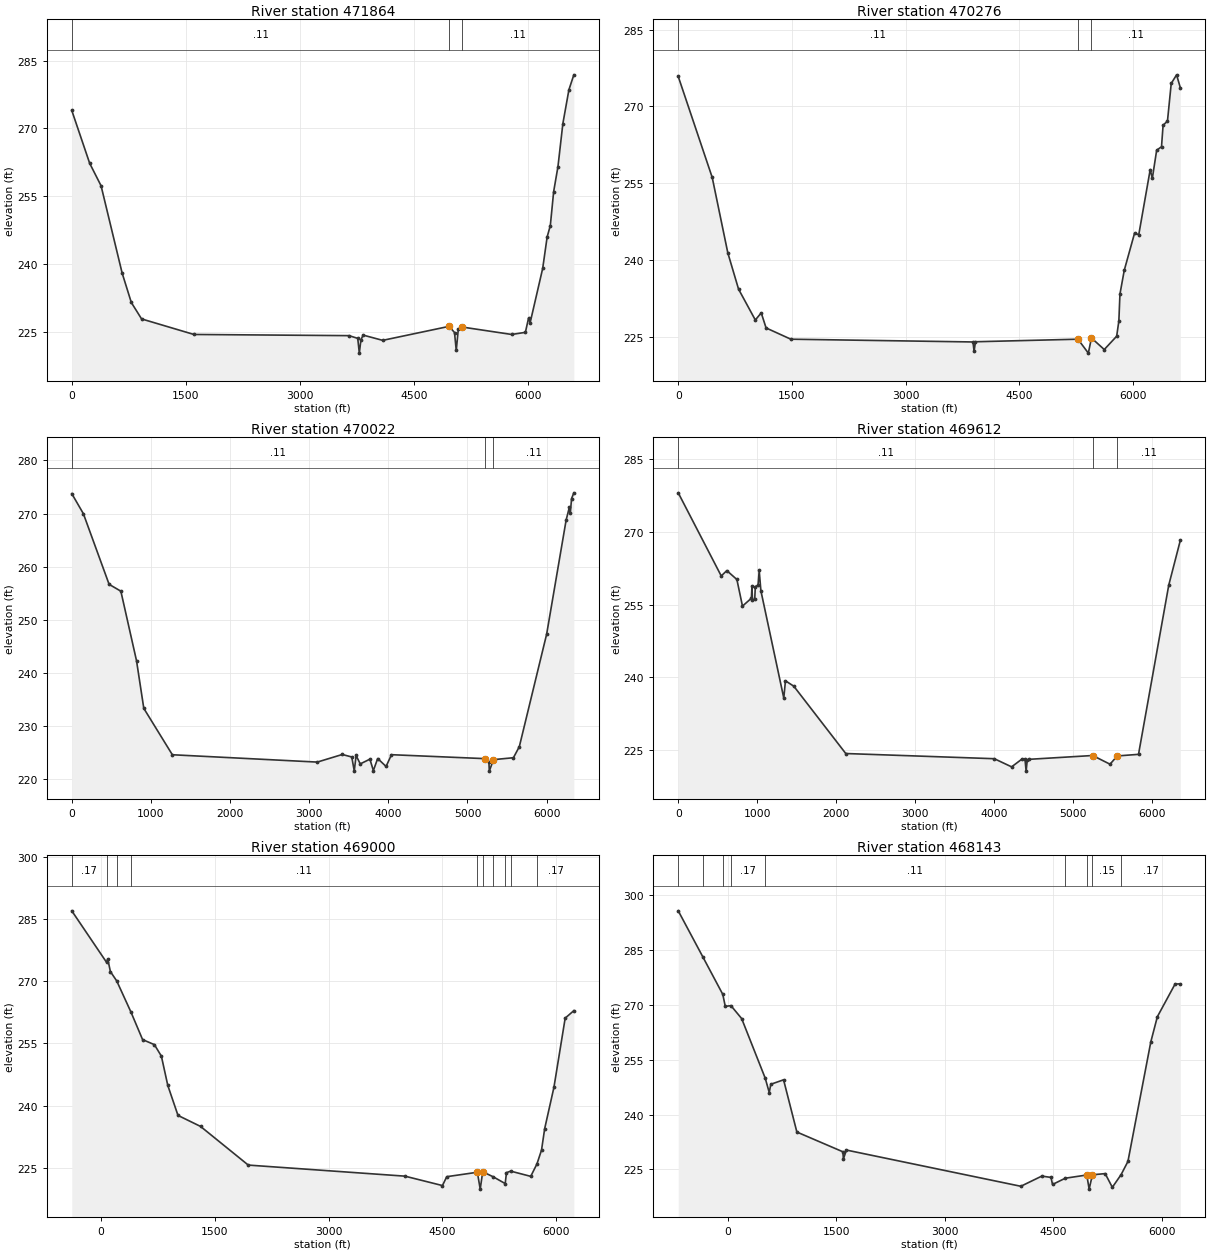
Type RM Length L Ch R = 1 ,471864  ,1588,1588,1588
BEGIN DESCRIPTION:
WFSJ Main 467.0
END DESCRIPTION:
XS GIS Cut Line= 3
      3763896.66     10233824.85      3761988.67     10232202.46
      3759558.12     10228909.06
#Sta/Elev= 30
       0  273.98   235.5   262.3   384.9  257.35   661.6  238.09   782.4  231.58
   917.3  227.95    1605  224.52    3643  224.26  3757.9  223.66  3778.7   220.4
  3799.6  223.34  3828.9  224.38  4085.7  223.22  4958.5  226.31  5029.5  224.95
  5052.5  220.99  5079.6  225.74  5129.7  226.16  5781.2  224.52  5960.9  224.99
  6002.6  228.13  6023.5  227.12  6188.4  239.11  6246.9  246.05  6288.6  248.56
  6332.5  256.07  6388.9  261.57  6453.6  271.09    6533  278.55  6597.7  281.84
#Mann= 3 , 0 , 0
       0     .11       0  4958.5     .06       0  5129.7     .11       0
Bank Sta=4958.5,5129.7
XS Rating Curve= 0 ,0
Exp/Cntr=0.3,0.1

Type RM Length L Ch R = 1 ,470276  ,254,254,254
BEGIN DESCRIPTION:
WFSJ Main 466.0
END DESCRIPTION:
XS GIS Cut Line= 5
      3764036.41     10233764.09      3762705.68     10232646.04
      3761703.08     10231369.99        3760822.     10229170.34
      3760269.05     10228471.56
#Sta/Elev= 30
       0  275.85   448.2  256.13   653.8  241.41   795.6  234.32  1016.6   228.3
  1094.7  229.69  1158.4  226.75  1484.9  224.55  3887.6  224.01  3901.5  222.16
  3919.9  224.05  5271.4  224.55  5408.6  221.83  5449.6  224.79  5618.5  222.53
  5782.1  225.13    5811  228.09  5825.4  233.36  5882.5  238.02  6017.8  245.23
  6073.8  244.97  6224.5  257.67  6252.3  255.95  6309.5  261.44  6373.6  262.14
  6394.4  266.33  6452.1  267.14  6501.8  274.49  6572.3  276.17  6621.5  273.66
#Mann= 3 , 0 , 0
       0     .11       0  5271.4     .06       0  5449.6     .11       0
Bank Sta=5271.4,5449.6
XS Rating Curve= 0 ,0
Exp/Cntr=0.3,0.1

Type RM Length L Ch R = 1 ,470022  ,410,410,410
BEGIN DESCRIPTION:
WFSJ Main 465.0
END DESCRIPTION:
XS GIS Cut Line= 4
      3764291.62     10233484.58      3761909.68      10231084.4
      3761095.44     10229218.95      3760700.48     10228380.41
#Sta/Elev= 30
       0  273.75   146.5  269.98   471.8  256.69   620.3   255.4   818.3  242.31
   910.2  233.36  1270.9  224.64  3102.3  223.26  3417.9  224.69  3537.9  224.22
  3569.4  221.58  3592.4   224.5    3645  222.92    3767  223.81  3810.7  221.66
  3865.2  223.93  3971.2  222.44  4039.8  224.65  5218.1  223.91  5270.3  223.37
  5275.8  221.56  5328.1  223.72  5580.4  224.08  5654.9  226.16  6000.4  247.34
  6246.7   268.8  6286.8  271.16  6298.9  270.02  6315.1  272.83  6343.8   273.9
#Mann= 3 , 0 , 0
       0     .11       0  5218.1     .06       0  5328.1     .11       0
Bank Sta=5218.1,5328.1
XS Rating Curve= 0 ,0
Exp/Cntr=0.3,0.1

Type RM Length L Ch R = 1 ,469612  ,612,612,612
BEGIN DESCRIPTION:
WFSJ Main 464.0
END DESCRIPTION:
XS GIS Cut Line= 3
      3765117.85     10232961.07      3761648.39     10229316.17
      3760785.55     10228307.49
#Sta/Elev= 30
       0  278.05   544.6  260.91   615.4  262.01   742.8  260.18   813.6  254.69
   926.5  256.31   933.7  258.83   940.6  255.85   968.9   256.1   976.2   258.7
  1011.4  259.02  1025.5  262.04  1046.9  257.86    1337  235.73    1358  239.29
    1464  238.17    2122  224.29  4003.6  223.22  4222.8  221.54  4357.1  223.19
  4392.3  223.09  4406.5  220.66  4420.7  222.91    4449   223.1  5249.4  223.88
    5469  222.09  5561.2  223.79  5830.1  224.12  6213.2  259.02  6359.5  268.24
#Mann= 3 , 0 , 0
       0     .11       0  5249.4     .06       0  5561.2     .11       0
Bank Sta=5249.4,5561.2
XS Rating Curve= 0 ,0
Exp/Cntr=0.3,0.1

Type RM Length L Ch R = 1 ,469000  ,857,857,857
BEGIN DESCRIPTION:
WFSJ Main 463.0
END DESCRIPTION:
XS GIS Cut Line= 3
      3765667.87     10232861.09      3761999.08     10228915.41
      3761037.57     10228141.47
#Sta/Elev= 30
  -387.8  286.99    71.7  274.55    86.4  275.39   121.6  272.34   204.8  270.09
   392.3  262.59   546.2  255.93     702  254.71   793.9  251.95   878.9  244.86
  1013.3  237.64  1310.3  234.99  1940.1  225.66  4006.4  222.99  4501.3  220.72
    4558  222.86  4961.6  223.93  4999.3  219.86  5032.3  224.04  5169.9  222.84
  5328.8   221.2  5345.8  223.83  5401.1   224.2  5665.7  222.94  5747.7  225.94
  5808.1  229.28  5849.7  234.46  5971.3  244.38  6120.1  261.11  6234.3  262.91
#Mann= 10 ,-1 , 0
  -387.8     .17       0    71.7     .11       0   204.8     .17       0
   392.3     .11       0  4961.6     .06       0  5032.3     .11       0
  5169.9     .15       0  5328.8     .11       0  5401.1     .15       0
  5747.7     .17       0
Bank Sta=4961.6,5032.3
XS Rating Curve= 0 ,0
Exp/Cntr=0.3,0.1

Type RM Length L Ch R = 1 ,468143  ,1576,1576,1576
BEGIN DESCRIPTION:
WFSJ Main 462.0
END DESCRIPTION:
XS GIS Cut Line= 3
      3766317.86     10232361.08      3762090.06     10228260.81
      3761124.34     10227837.63
#Sta/Elev= 30
  -683.8   295.8  -340.3  283.06   -67.8  272.92   -33.1  269.62      45  269.83
   193.2  266.29   519.3  249.95     575  246.02   596.3  248.28     773  249.51
     957   235.2  1593.4  229.79  1600.5  227.85  1642.8  230.26  4054.3  220.34
  4344.4  223.13  4471.5  222.77  4492.9  220.84  4669.6  222.55  4966.7  223.43
  4999.3  219.56  5044.4  223.49    5221  223.81    5320  220.06  5441.8  223.55
  5535.7  227.15  5852.3  259.92  5942.6  266.79  6187.3  275.73  6260.1   275.8
#Mann= 9 ,-1 , 0
  -683.8     .11       0  -340.3     .17       0   -67.8     .11       0
      45     .17       0   519.3     .11       0  4669.6     .15       0
  4966.7     .09       0  5044.4     .15       0  5441.8     .17       0
Bank Sta=4966.7,5044.4
XS Rating Curve= 0 ,0
Exp/Cntr=0.3,0.1

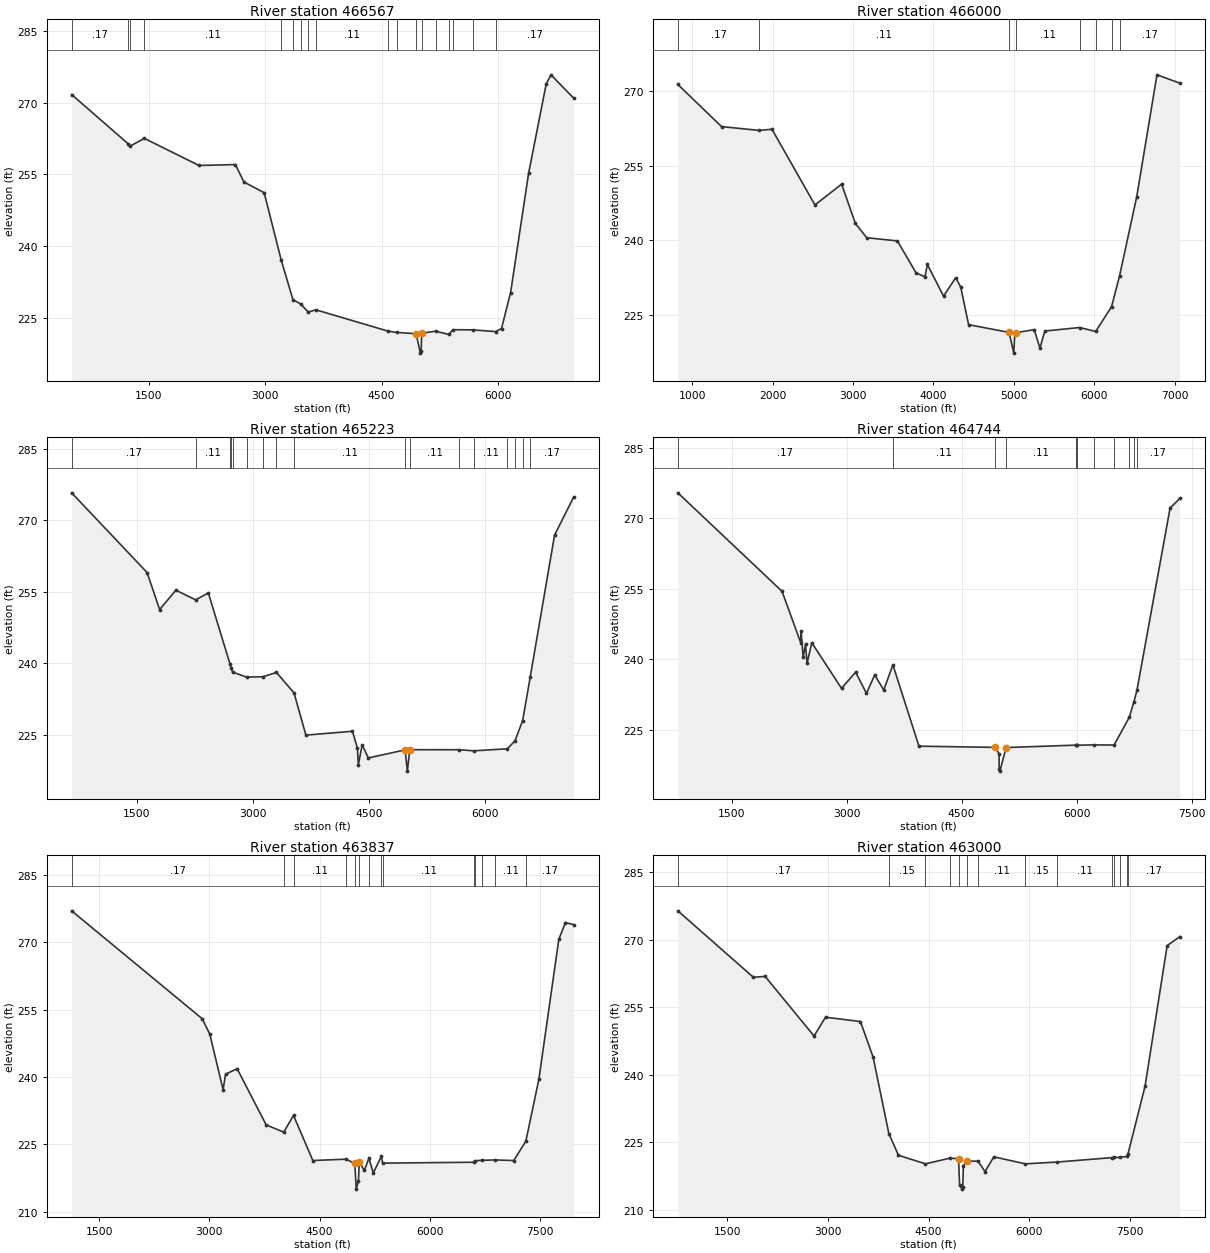
Type RM Length L Ch R = 1 ,466567  ,567,567,567
BEGIN DESCRIPTION:
WFSJ Main 461.0
END DESCRIPTION:
XS GIS Cut Line= 3
      3767472.03     10228597.19      3763261.94     10228336.77
      3761157.63     10227555.79
#Sta/Elev= 30
   509.9  271.69    1234  261.45  1258.4  260.88  1446.1  262.53    2150  256.87
  2618.1  257.06  2728.3  253.41  2988.8  251.18  3207.3  237.15  3358.9  228.85
  3457.5  227.94  3556.2  226.24  3654.9  226.71  4580.1  222.27  4695.5  221.98
  4945.7  221.72  4999.2  217.66    5010  218.16  5016.3  221.83  5197.6  222.25
  5363.9  221.56  5420.4  222.55  5675.3  222.52  5968.6  222.16  6044.4   222.8
  6161.7  230.32    6394   255.3  6620.4  273.94  6681.7  275.81  6972.6  270.95
#Mann= 18 ,-1 , 0
   509.9     .17       0    1234     .11       0  1258.4     .17       0
  1446.1     .11       0  3207.3     .17       0  3358.9     .15       0
  3457.5     .11       0  3556.2     .15       0  3654.9     .11       0
  4580.1     .15       0  4695.5     .11       0  4945.7     .09       0
  5016.3     .15       0  5197.6     .11       0  5363.9     .15       0
  5420.4     .11       0  5675.3     .15       0  5968.6     .17       0
Bank Sta=4945.7,5016.3
XS Rating Curve= 0 ,0
Exp/Cntr=0.3,0.1

Type RM Length L Ch R = 1 ,466000  ,777,777,777
BEGIN DESCRIPTION:
WFSJ Main 460.0
END DESCRIPTION:
XS GIS Cut Line= 3
      3767352.66     10228206.56      3763198.24     10227742.16
      3761156.95     10227436.17
#Sta/Elev= 30
   819.7  271.33  1363.5  262.87  1828.9   262.1  1990.5  262.33  2525.1  247.12
  2857.1   251.3  3028.2   243.4  3169.3  240.53  3551.4  239.89  3782.9  233.46
  3893.5  232.68  3923.7  235.16    4125  228.79  4275.9  232.49    4338  230.66
  4436.9  223.06    4940  221.51  4999.2  217.34  5010.5  221.25  5020.6  221.44
  5253.2  222.06    5324  218.34  5384.6  221.78  5818.6  222.49  6017.1  221.69
  6215.6  226.69  6314.8  232.89  6528.7  248.81  6780.1  273.27  7064.1   271.6
#Mann= 8 ,-1 , 0
   819.7     .17       0  1828.9     .11       0    4940     .06       0
  5020.6     .11       0  5818.6     .15       0  6017.1     .17       0
  6215.6     .11       0  6314.8     .17       0
Bank Sta=4940,5020.6
XS Rating Curve= 0 ,0
Exp/Cntr=0.3,0.1

Type RM Length L Ch R = 1 ,465223  ,479,479,479
BEGIN DESCRIPTION:
WFSJ Main 459.0
END DESCRIPTION:
XS GIS Cut Line= 3
      3767592.66     10227821.58      3763454.05     10227215.93
      3761151.84     10227280.14
#Sta/Elev= 30
   661.5  275.72  1636.6  259.03  1798.3  251.29  2008.6  255.33  2263.3  253.31
    2428  254.75  2705.8  239.97  2723.4  239.07  2740.6  238.19  2922.8  237.13
  3133.6  237.21  3308.2  238.11  3535.1  233.82  3688.2  224.99  4290.1   225.8
    4355   222.2  4365.3  218.74  4415.9  222.97  4494.8  220.21  4970.4   221.9
  4999.2  217.45  5030.5  221.94  5671.7  221.93  5854.9   221.7    6291  222.13
  6389.8  223.79  6488.7  228.01  6587.6  237.22  6901.2  266.84  7147.3  274.82
#Mann= 17 ,-1 , 0
   661.5     .17       0  2263.3     .11       0  2705.8     .17       0
  2723.4     .11       0  2740.6     .17       0  2922.8     .15       0
  3133.6     .11       0  3308.2     .17       0  3535.1     .11       0
  4970.4     .06       0  5030.5     .11       0  5671.7     .15       0
  5854.9     .11       0    6291     .15       0  6389.8     .17       0
  6488.7     .11       0  6587.6     .17       0
Bank Sta=4970.4,5030.5
XS Rating Curve= 0 ,0
Exp/Cntr=0.3,0.1

Type RM Length L Ch R = 1 ,464744  ,907,907,907
BEGIN DESCRIPTION:
WFSJ Main 458.0
END DESCRIPTION:
XS GIS Cut Line= 3
       3767620.2     10227683.94      3763756.88     10226903.93
      3761161.37     10227133.22
#Sta/Elev= 30
   798.9  275.44  2158.1  254.44  2401.5   243.5  2406.6  245.89  2433.6   240.4
  2464.2  243.15  2484.6  239.12  2545.8  243.49  2933.5  233.78  3117.3  237.21
  3259.4   232.7  3366.1  236.64  3484.4  233.42  3603.6  238.78  3943.4  221.45
 4937.64  221.19  4988.5  219.85    4990  216.63  4999.1  216.13  5080.5  221.16
  5987.2  221.67  5991.9  221.66    5999  221.65  6223.3  221.72  6488.4  221.69
  6687.3  227.62  6746.1  230.84  6786.7  233.34  7218.8  272.18  7345.8  274.24
#Mann= 12 ,-1 , 0
   798.9     .17       0  3603.6     .11       0 4937.64     .06       0
  5080.5     .11       0  5987.2     .15       0  5991.9     .11       0
    5999     .15       0  6223.3     .11       0  6488.4     .15       0
  6687.3     .17       0  6746.1     .11       0  6786.7     .17       0
Bank Sta=4937.64,5080.5
XS Rating Curve= 0 ,0
Exp/Cntr=0.3,0.1

Type RM Length L Ch R = 1 ,463837  ,837,837,837
BEGIN DESCRIPTION:
Mapping XS ab5dca74
END DESCRIPTION:
XS GIS Cut Line= 3
      3767904.68     10227417.82      3764261.59     10226619.46
      3761178.29     10226968.16
#Sta/Elev= 30
    1125  276.99    2903  252.95  3006.1  249.48  3186.6  237.16  3220.4   240.6
  3377.3  241.84  3773.2  229.31  4011.2   227.7  4145.5  231.41  4408.1  221.38
  4858.9  221.68  4979.1  220.74  4999.1  215.01  5029.4  216.92  5039.5  221.04
  5109.9  219.16  5170.9  221.89  5230.7  218.62  5341.8  222.36  5357.8   220.8
  6605.7     221  6608.9  221.31  6708.7  221.43    6890  221.51  7142.9  221.38
  7307.4  225.69  7484.9  239.47  7756.3  270.63  7846.1  274.39  7957.5  273.91
#Mann= 14 ,-1 , 0
    1125     .17       0  4011.2     .15       0  4145.5     .11       0
  4858.9     .15       0  4979.1     .09       0  5039.5     .15       0
  5170.9     .11       0  5341.8     .15       0  5357.8     .11       0
  6605.7     .15       0  6608.9     .11       0  6708.7     .15       0
    6890     .11       0  7307.4     .17       0
Bank Sta=4979.1,5039.5
XS Rating Curve= 0 ,0
Exp/Cntr=0.3,0.1

Type RM Length L Ch R = 1 ,463000  ,1000,1000,1000
BEGIN DESCRIPTION:
WFSJ Main 457.0
END DESCRIPTION:
XS GIS Cut Line= 4
      3768280.92     10227014.04      3764166.29     10225997.25
      3761875.68     10226307.45      3761114.02     10226848.87
#Sta/Elev= 30
   761.6  276.37  1887.5  261.62  2062.7  261.82  2792.3  248.59  2963.2  252.76
  3484.2   251.8  3672.9  243.92  3908.2  226.92    4051  222.12  4454.1  220.22
    4813  221.47  4946.9  221.39  4962.8  215.52  4999.1  214.61    5010  215.11
  5018.6  219.85  5079.2  220.85  5238.7  220.79  5341.5   218.5  5472.7  221.78
    5942  220.22    6419  220.62  7240.6  221.61  7261.9  221.64  7347.9  221.65
  7458.4  221.88  7472.4  222.35  7727.8  237.46  8057.4  268.65    8246  270.64
#Mann= 14 ,-1 , 0
   761.6     .17       0  3908.2     .15       0  4454.1     .11       0
    4813     .15       0  4946.9     .09       0  5079.2     .15       0
  5238.7     .11       0    5942     .15       0    6419     .11       0
  7240.6     .17       0  7261.9     .11       0  7347.9     .17       0
  7458.4     .11       0  7472.4     .17       0
Bank Sta=4946.9,5079.2
XS Rating Curve= 0 ,0
Exp/Cntr=0.3,0.1

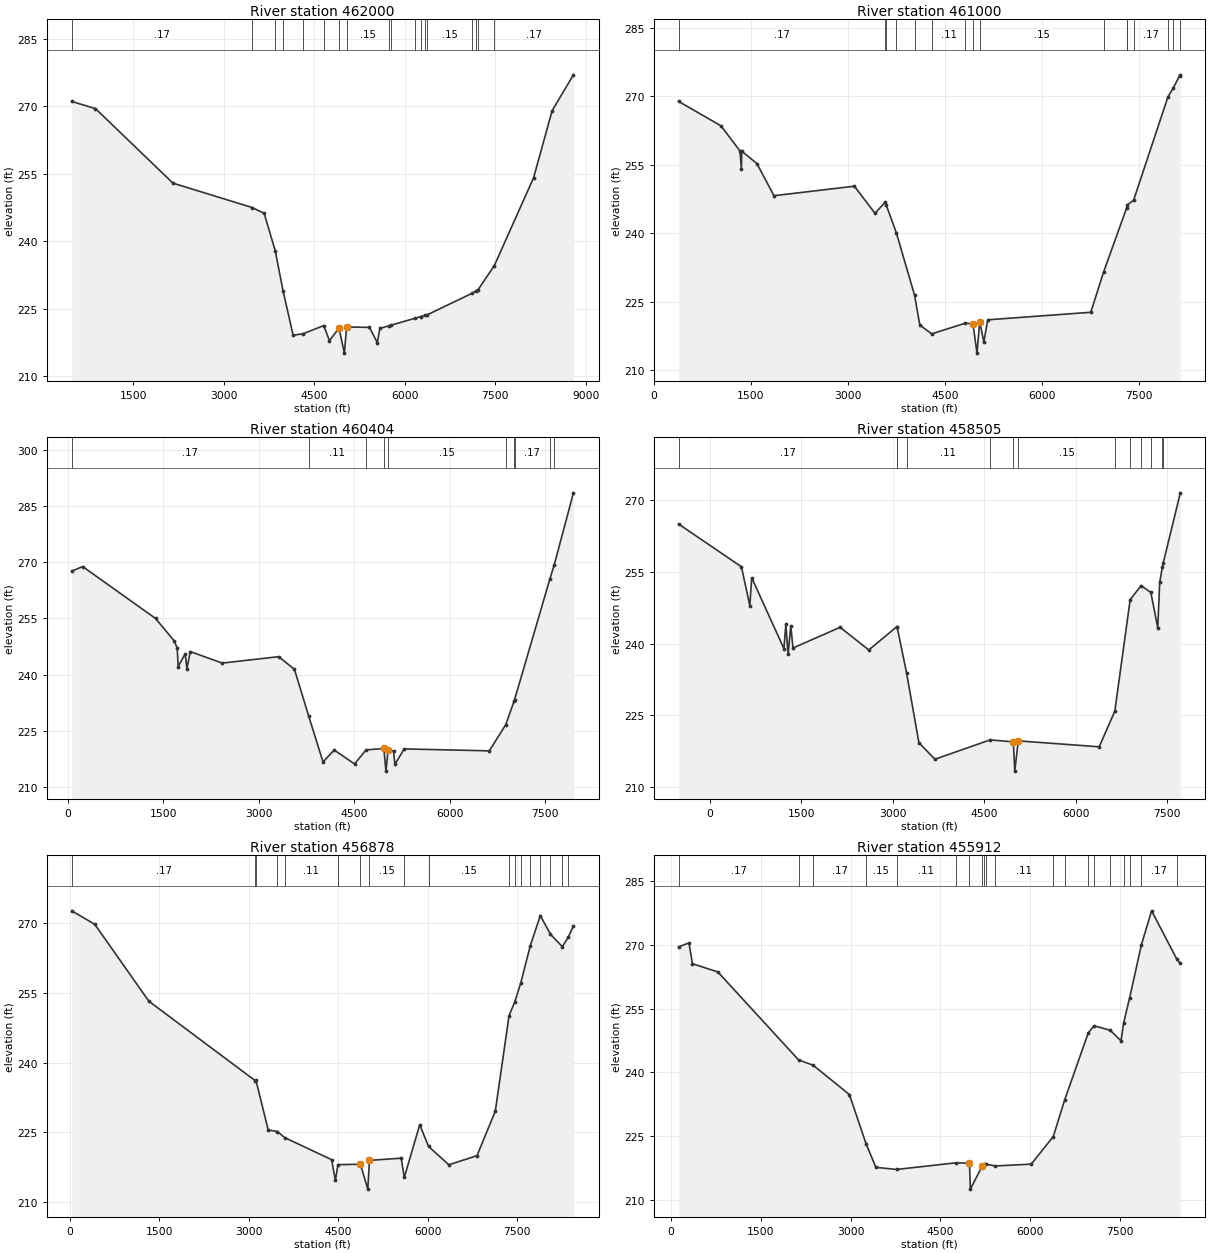
Type RM Length L Ch R = 1 ,462000  ,1000,1000,1000
BEGIN DESCRIPTION:
WFSJ Main 456.0
END DESCRIPTION:
XS GIS Cut Line= 3
      3768464.51     10226757.12      3764160.49     10225376.93
      3760655.22     10223921.55
#Sta/Elev= 30
   480.1  271.06   873.5  269.47  2157.9   252.9  3471.4  247.48  3669.1   246.2
  3852.7  237.87  3983.5   228.9  4149.1  219.11  4311.2  219.41    4658  221.25
  4750.7  217.89    4909  220.68    4999  215.12  5035.3  220.93  5414.2  220.85
  5544.2  217.46  5587.6  220.62  5738.6   221.2  5768.7  221.32  6165.1  222.85
  6270.3  223.26  6333.5   223.5  6375.5  223.66    7112   228.4  7180.8  228.96
  7217.2  229.26  7483.7  234.57  8134.6  254.09  8442.6  269.02  8795.4  276.98
#Mann= 18 ,-1 , 0
   480.1     .17       0  3471.4     .11       0  3852.7     .17       0
  3983.5     .15       0  4311.2     .11       0    4658     .15       0
    4909     .09       0  5035.3     .15       0  5738.6     .11       0
  5768.7     .15       0  6165.1     .17       0  6270.3     .15       0
  6333.5     .17       0  6375.5     .15       0    7112     .11       0
  7180.8     .17       0  7217.2     .11       0  7483.7     .17       0
Bank Sta=4909,5035.3
XS Rating Curve= 0 ,0
Exp/Cntr=0.3,0.1

Type RM Length L Ch R = 1 ,461000  ,596,596,596
BEGIN DESCRIPTION:
WFSJ Main 455.0
END DESCRIPTION:
XS GIS Cut Line= 3
      3768464.43     10226591.91      3764274.25     10224660.71
      3761380.13     10223435.18
#Sta/Elev= 30
   386.2  268.91  1041.4  263.56  1333.4  258.08  1356.3  254.16  1362.4  258.01
  1596.9  255.29  1860.4  248.26  3103.7  250.34  3421.5  244.41  3577.3   246.8
  3597.8  246.13  3752.2  240.13  4033.1  226.49  4115.2  219.92    4299  217.99
  4818.5  220.33  4937.4  220.17    4999  213.77  5041.2  220.68  5104.7   216.2
  5165.1  221.07  6758.3  222.72  6956.3  231.54  7312.9  245.58  7324.9  246.23
  7420.6  247.27  7951.5  269.92  8032.1   271.8  8130.3  274.51  8142.9  274.74
#Mann= 16 ,-1 , 0
   386.2     .17       0  3577.3     .11       0  3597.8     .17       0
  3752.2     .11       0  4033.1     .15       0    4299     .11       0
  4818.5     .15       0  4937.4     .09       0  5041.2     .15       0
  6956.3     .11       0  7312.9     .17       0  7324.9     .11       0
  7420.6     .17       0  7951.5     .11       0  8032.1     .17       0
  8130.3     .11       0
Bank Sta=4937.4,5041.2
XS Rating Curve= 0 ,0
Exp/Cntr=0.3,0.1

Type RM Length L Ch R = 1 ,460404  ,1899,1899,1899
BEGIN DESCRIPTION:
WFSJ Main 454.0
END DESCRIPTION:
XS GIS Cut Line= 4
      3768620.45     10226546.03      3767390.81     10225995.45
      3764509.36     10224242.72      3761592.03      10223013.4
#Sta/Elev= 30
    60.7  267.62   232.6  268.82  1377.4  255.01  1668.9  249.07  1718.1  247.15
  1733.6  242.19    1844  245.61  1871.2  241.66  1923.5  246.18  2425.3  243.11
  3312.6  244.82  3560.6  241.46  3783.2  229.11  4010.1  216.77  4185.5  219.95
  4506.1  216.25  4686.9  219.99  4966.8  220.36    4999  214.33  5033.4  220.03
  5118.7  219.59  5140.4  216.17    5287  220.25  6623.9  219.73  6882.3  226.71
  7011.9  232.89    7020   233.3    7577  265.57  7644.4  269.27  7946.4  288.47
#Mann= 10 ,-1 , 0
    60.7     .17       0  3783.2     .11       0  4686.9     .15       0
  4966.8     .09       0  5033.4     .15       0  6882.3     .17       0
  7011.9     .11       0    7020     .17       0    7577     .11       0
  7644.4     .17       0
Bank Sta=4966.8,5033.4
XS Rating Curve= 0 ,0
Exp/Cntr=0.3,0.1

Type RM Length L Ch R = 1 ,458505  ,1627,1627,1627
BEGIN DESCRIPTION:
WFSJ Main 453.0
END DESCRIPTION:
XS GIS Cut Line= 5
      3768620.45     10226435.91       3766023.5     10225004.38
      3765968.44     10224389.55      3764224.89     10223370.94
      3761721.29      10222573.1
#Sta/Elev= 30
  -514.7  264.95   515.5  256.03     653  247.92     684  253.74  1212.5  238.94
  1243.4     244    1281  237.74  1324.8  243.73  1360.9  239.07  2134.1  243.39
  2604.6  238.66  3064.9  243.53  3068.3  243.51  3223.6  233.89  3426.8   219.3
  3688.8  215.84  4596.5  219.89  4975.9  219.46    4999  213.36  5056.1  219.68
    6384  218.44    6640  225.86  6892.1  249.16  7071.9  252.11  7231.1  250.66
  7344.4  243.29  7376.6  252.77  7420.5  255.96  7435.8  256.89  7714.9  271.47
#Mann= 13 ,-1 , 0
  -514.7     .17       0  3064.9     .11       0  3068.3     .17       0
  3223.6     .11       0  4596.5     .15       0  4975.9     .09       0
  5056.1     .15       0    6640     .11       0  6892.1     .15       0
  7071.9     .17       0  7231.1     .11       0  7420.5     .17       0
  7435.8     .11       0
Bank Sta=4975.9,5056.1
XS Rating Curve= 0 ,0
Exp/Cntr=0.3,0.1

Type RM Length L Ch R = 1 ,456878  ,966,966,966
BEGIN DESCRIPTION:
WFSJ Main 452.0
END DESCRIPTION:
XS GIS Cut Line= 3
      3769097.67     10226013.81      3765067.85     10222861.07
      3761812.17     10222379.98
#Sta/Elev= 30
    37.4  272.71   423.8   269.8    1329  253.26  3109.1  236.18  3124.1  236.25
  3330.1  225.53  3485.1  225.19  3604.6   223.9  4392.2  219.14  4455.6  214.68
  4498.4  218.07  4875.5  218.15    4999   212.8  5026.4  218.99  5558.3  219.46
  5610.3  215.31  5869.4  226.67  6016.4  221.99  6356.9  218.04  6828.4     220
  7135.2  229.56  7366.1  250.13  7464.5  253.19  7563.7  257.25  7722.4  265.22
  7889.8  271.69  8059.9  267.66  8258.3     265  8357.5     267    8445  269.48
#Mann= 18 ,-1 , 0
    37.4     .17       0  3109.1     .11       0  3124.1     .17       0
  3485.1     .15       0  3604.6     .11       0  4498.4     .15       0
  4875.5     .09       0  5026.4     .15       0  5610.3     .11       0
  6016.4     .15       0  7366.1     .11       0  7464.5     .15       0
  7563.7     .11       0  7722.4     .17       0  7889.8     .11       0
  8059.9     .17       0  8258.3     .11       0  8357.5     .17       0
Bank Sta=4875.5,5026.4
XS Rating Curve= 0 ,0
Exp/Cntr=0.3,0.1

Type RM Length L Ch R = 1 ,455912  ,912,912,912
BEGIN DESCRIPTION:
WFSJ Main 451.0
END DESCRIPTION:
XS GIS Cut Line= 3
      3769997.01     10223719.67      3765665.61     10222297.28
      3761848.18     10222205.52
#Sta/Elev= 30
   127.4   269.5   299.7  270.44   358.1  265.54   782.2   263.6  2131.1  242.89
  2372.8  241.65  2978.9  234.75  3256.9  223.17    3421  217.62  3765.5  217.12
  4751.5  218.67  4984.2  218.61    4999  212.49  5194.3  217.86  5221.9  218.43
    5266  218.33  5417.7  217.95  6014.5  218.37  6383.2  224.86  6572.8  233.47
  6967.4  249.26    7066  250.94  7333.1  249.88  7514.9   247.4  7559.3  251.68
    7658  257.49  7855.3  270.03  8025.1  277.99  8447.2  266.59  8504.9  265.64
#Mann= 20 ,-1 , 0
   127.4     .17       0  2131.1     .11       0  2372.8     .17       0
  3256.9     .15       0  3765.5     .11       0  4751.5     .15       0
  4984.2     .09       0  5194.3     .15       0  5221.9     .11       0
    5266     .15       0  5417.7     .11       0  6383.2     .17       0
  6572.8     .11       0  6967.4     .15       0    7066     .11       0
  7333.1     .11       0  7559.3     .17       0    7658     .11       0
  7855.3     .17       0  8447.2     .11       0
Bank Sta=4984.2,5194.3
XS Rating Curve= 0 ,0
Exp/Cntr=0.3,0.1

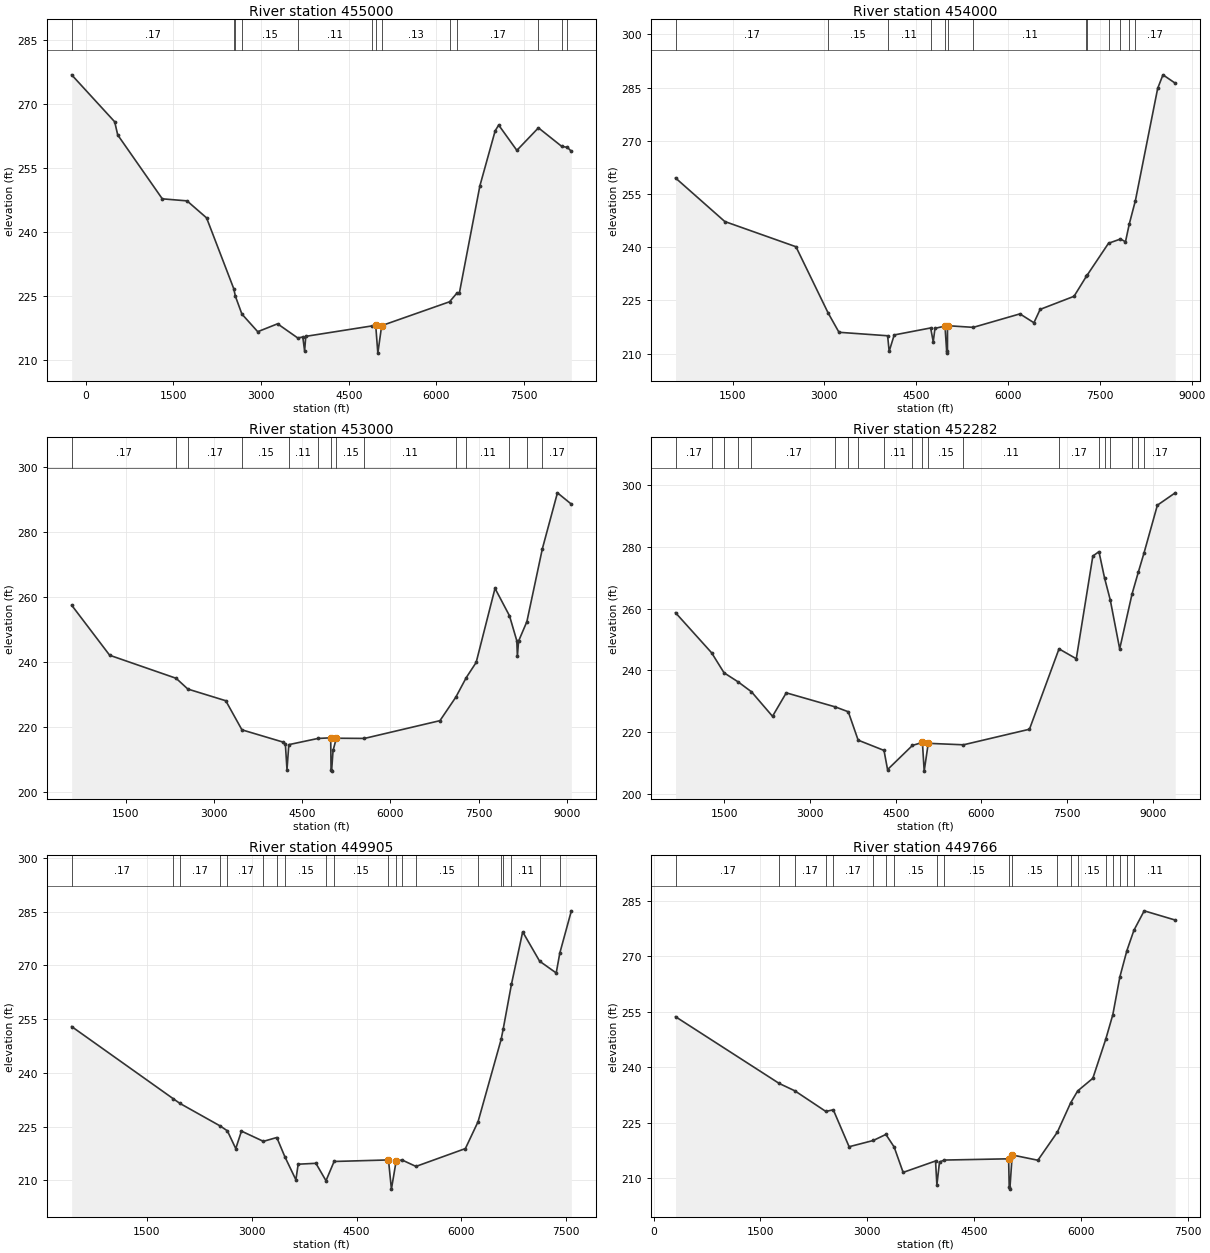
Type RM Length L Ch R = 1 ,455000  ,1000,1000,1000
BEGIN DESCRIPTION:
WFSJ Main 450.0
END DESCRIPTION:
XS GIS Cut Line= 3
      3770244.71     10222930.46      3765148.24     10221696.63
      3761848.14     10221985.28
#Sta/Elev= 30
  -243.7  276.88   493.1  265.88   545.3  262.79  1308.4  247.83  1731.8  247.35
  2066.4  243.37  2531.8  226.78  2560.6  224.98  2671.5  220.83  2942.6   216.7
  3282.2  218.55  3627.8  215.23  3714.3  215.46  3745.2  212.18  3765.2  215.61
  4900.7  218.06  4962.1   218.3    4999  211.68  5064.8  218.12  6226.8  223.71
  6356.8   225.8  6395.7  225.81    6747  250.91    7008  263.76  7068.3  265.11
  7379.4  259.18  7748.8  264.46  8146.6  260.13    8246  259.88  8312.7  258.95
#Mann= 13 ,-1 , 0
  -243.7     .17       0  2531.8     .15       0  2560.6     .17       0
  2671.5     .15       0  3627.8     .11       0  4900.7     .15       0
  4962.1     .09       0  5064.8     .13       0  6226.8     .15       0
  6356.8     .17       0  7748.8     .11       0  8146.6     .17       0
    8246     .11       0
Bank Sta=4962.1,5064.8
XS Rating Curve= 0 ,0
Exp/Cntr=0.3,0.1

Type RM Length L Ch R = 1 ,454000  ,1000,1000,1000
BEGIN DESCRIPTION:
WFSJ Main 449.0
END DESCRIPTION:
XS GIS Cut Line= 3
      3769813.43      10221976.1      3765488.37     10221007.01
      3761831.28     10220269.56
#Sta/Elev= 30
   567.7  259.53  1372.8  247.24  2535.2  240.13  3061.2  221.43  3237.9     216
  4032.5  215.02  4057.7  210.62  4140.1  215.25  4735.2  217.22  4777.9  213.32
  4805.8  217.11  4969.8  217.75    4999  210.12    5010  210.62  5010.7  217.86
  5431.7  217.39  6194.1  221.19  6422.4  218.69    6524  222.46  7077.7  226.15
  7280.7  231.83  7290.1  232.06    7641  241.11  7836.4   242.3  7918.1  241.53
  7980.2  246.55  8080.2  253.15  8444.1   284.8  8530.2  288.62  8730.7  286.26
#Mann= 13 ,-1 , 0
   567.7     .17       0  3061.2     .15       0  4032.5     .11       0
  4735.2     .15       0  4969.8     .09       0  5010.7     .15       0
  5431.7     .11       0  7280.7     .15       0  7290.1     .11       0
    7641     .15       0  7836.4     .17       0  7980.2     .11       0
  8080.2     .17       0
Bank Sta=4969.8,5010.7
XS Rating Curve= 0 ,0
Exp/Cntr=0.3,0.1

Type RM Length L Ch R = 1 ,453000  ,718,718,718
BEGIN DESCRIPTION:
WFSJ Main 448.0
END DESCRIPTION:
XS GIS Cut Line= 3
      3770152.92     10221122.67      3765792.04     10220390.66
      3761721.31     10220159.23
#Sta/Elev= 30
   578.1  257.51  1224.6  242.12    2355  235.04  2554.3  231.73  3199.3  228.14
  3474.3   219.2  4179.9   215.4  4213.3  214.74  4240.6  207.01  4271.9  214.65
  4767.2  216.55    4984  216.75    4990  207.01    4999  206.51  5024.2  212.85
  5080.1  216.62  5558.3  216.56  6842.4  222.02  7112.8  229.26  7289.1  235.23
  7458.1  239.91  7778.7  262.68  8024.9  254.25  8149.3  246.58  8159.3  241.77
  8179.3  246.45  8320.9  252.46  8583.8  274.83  8840.4  292.03  9077.3  288.55
#Mann= 14 ,-1 , 0
   578.1     .17       0    2355     .11       0  2554.3     .17       0
  3474.3     .15       0  4271.9     .11       0  4767.2     .15       0
    4984     .09       0  5080.1     .15       0  5558.3     .11       0
  7112.8     .17       0  7289.1     .11       0  8024.9     .15       0
  8320.9     .11       0  8583.8     .17       0
Bank Sta=4984,5080.1
XS Rating Curve= 0 ,0
Exp/Cntr=0.3,0.1

Type RM Length L Ch R = 1 ,452282  ,2377,2377,2377
BEGIN DESCRIPTION:
WFSJ Main 447.0
END DESCRIPTION:
XS GIS Cut Line= 3
      3770217.15      10220718.9      3765729.85     10219865.49
      3761545.35     10219993.96
#Sta/Elev= 30
   642.6  258.68  1275.1  245.67  1492.8  239.18  1741.5  236.21  1973.4  233.02
  2341.8  225.07  2582.8  232.68  3442.4  228.11  3669.2  226.54    3842  217.33
    4295     214  4357.3  207.78  4793.8  215.63  4968.1  216.58    4999  207.28
  5069.9   216.3  5687.4  215.82  6843.1  220.87  7360.8  246.95  7663.5  243.74
  7953.6  277.05  8060.5  278.49  8159.4  269.88  8258.3  262.86  8423.8  246.93
    8640  264.73  8751.2   271.9  8851.6  278.15  9084.2  293.56  9396.8  297.57
#Mann= 20 ,-1 , 0
   642.6     .17       0  1275.1     .11       0  1492.8     .17       0
  1741.5     .15       0  1973.4     .17       0  3442.4     .11       0
  3669.2     .17       0    3842     .15       0    4295     .11       0
  4793.8     .15       0  4968.1     .09       0  5069.9     .15       0
  5687.4     .11       0  7360.8     .17       0  8060.5     .15       0
  8159.4     .11       0  8258.3     .15       0    8640     .17       0
  8751.2     .11       0  8851.6     .17       0
Bank Sta=4968.1,5069.9
XS Rating Curve= 0 ,0
Exp/Cntr=0.3,0.1

Type RM Length L Ch R = 1 ,449905  ,139,139,139
BEGIN DESCRIPTION:
WFSJ Main 446.0
END DESCRIPTION:
XS GIS Cut Line= 3
      3769941.89     10220067.37      3765885.85     10219360.78
      3762851.11     10219398.87
#Sta/Elev= 30
   422.5  252.93  1872.9  232.83  1972.4  231.47  2550.6  225.15  2651.5  223.81
  2771.4  218.85  2852.6  223.74  3166.9  220.88  3358.7  221.95  3473.4  216.61
  3631.9  210.14  3664.6   214.5  3918.4  214.75  4062.7  209.89  4178.7  215.26
  4957.1  215.69    4999  207.54  5067.7  215.48  5152.9  215.66  5350.4  213.88
  6057.7  218.86  6239.4  226.38  6569.3  249.32  6600.2  252.36  6717.8  264.81
  6877.8  279.37  7120.5  271.18  7357.8  267.89  7409.4  273.46  7574.6  285.24
#Mann= 20 ,-1 , 0
   422.5     .17       0  1872.9     .11       0  1972.4     .17       0
  2550.6     .11       0  2651.5     .17       0  3166.9     .11       0
  3358.7     .17       0  3473.4     .15       0  4062.7     .11       0
  4178.7     .15       0  4957.1     .09       0  5067.7     .15       0
  5152.9     .11       0  5350.4     .15       0  6239.4     .17       0
  6569.3     .15       0  6600.2     .17       0  6717.8     .11       0
  7120.5     .17       0  7409.4     .11       0
Bank Sta=4957.1,5067.7
XS Rating Curve= 0 ,0
Exp/Cntr=0.3,0.1

Type RM Length L Ch R = 1 ,449766  ,766,766,766
BEGIN DESCRIPTION:
WFSJ Main 445.0
END DESCRIPTION:
XS GIS Cut Line= 3
      3769987.82     10219883.85      3765922.55     10219287.36
      3763022.84     10219148.99
#Sta/Elev= 30
   307.7  253.67  1763.2  235.59  1981.2  233.61  2416.6  228.02  2521.6  228.46
  2743.5  218.46  3082.2  220.15  3259.6  221.79  3375.5  218.38  3501.5  211.51
  3956.3   214.6  3975.2  208.13    4012  214.33  4079.7  214.85  4981.8  215.19
    4990  207.48    4999  206.98  5031.9  216.23  5392.3   214.8  5665.5  222.41
    5852  230.34  5950.6  233.57  6163.2  236.99  6345.2  247.61  6443.9  254.22
  6542.5  264.43  6641.2  271.56  6739.8  277.07    6884  282.34  7319.5  279.84
#Mann= 20 ,-1 , 0
   307.7     .17       0  1763.2     .17       0  1981.2     .17       0
  2416.6     .11       0  2521.6     .17       0  3082.2     .11       0
  3259.6     .17       0  3375.5     .15       0  3975.2     .11       0
  4079.7     .15       0  4981.8     .09       0  5031.9     .15       0
  5665.5     .15       0    5852     .11       0  5950.6     .15       0
  6345.2     .11       0  6443.9     .17       0  6542.5     .15       0
  6641.2     .17       0  6739.8     .11       0
Bank Sta=4981.8,5031.9
XS Rating Curve= 0 ,0
Exp/Cntr=0.3,0.1