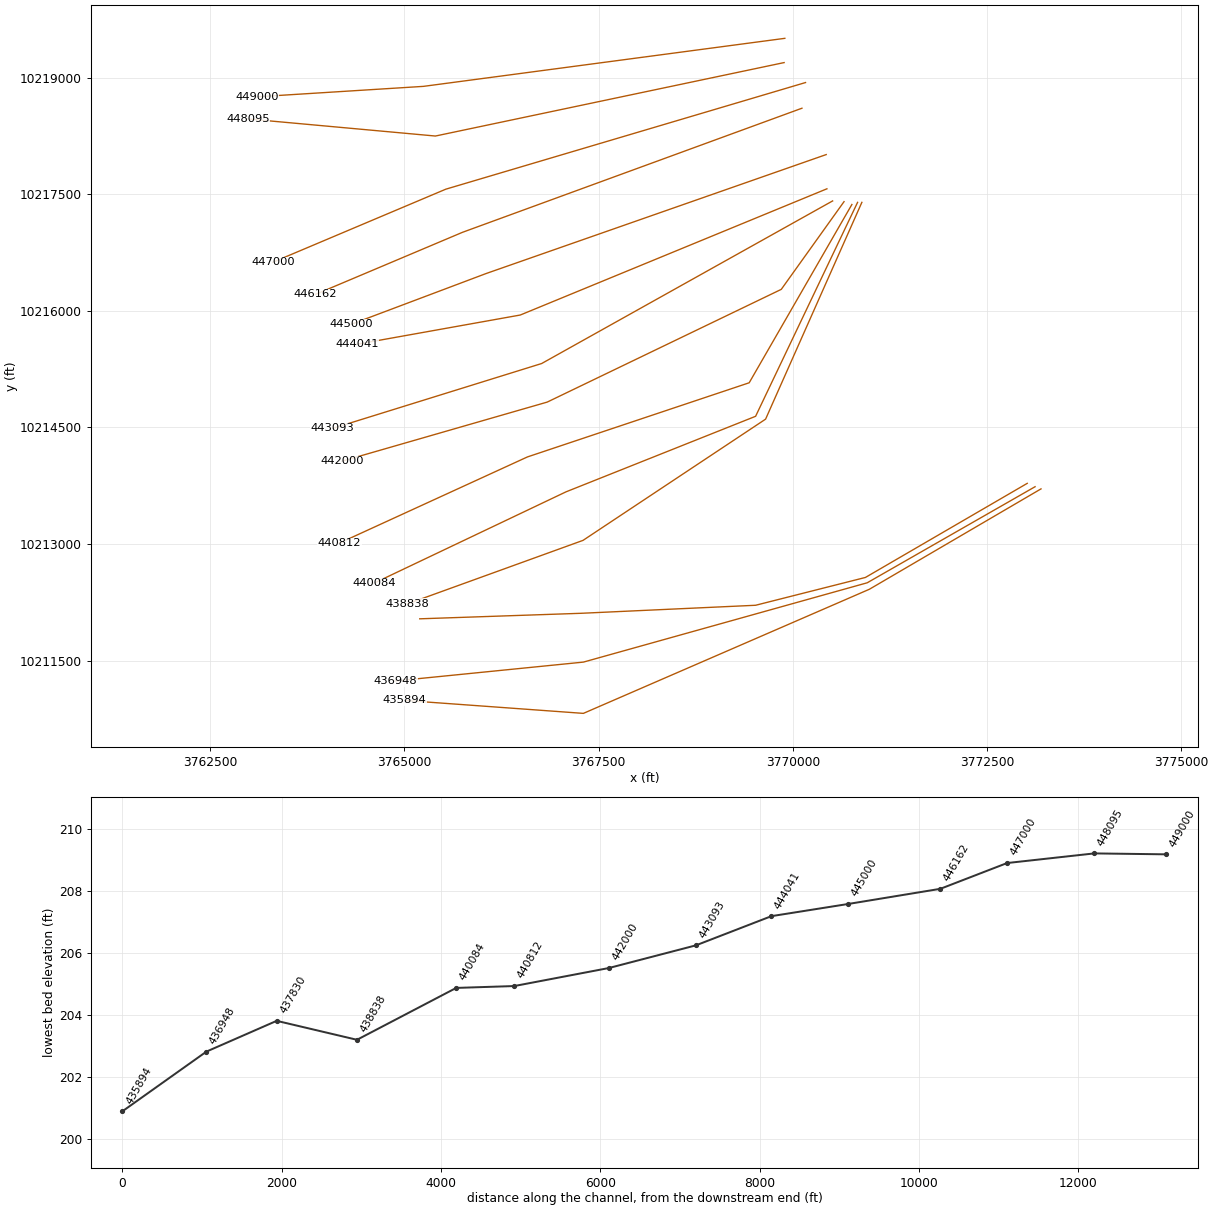
HEC-RAS study WFSJ Main.prj: WFSJ Main Base Level Engineering

--- WFSJ Main.g01 (geometry) --- (continued)

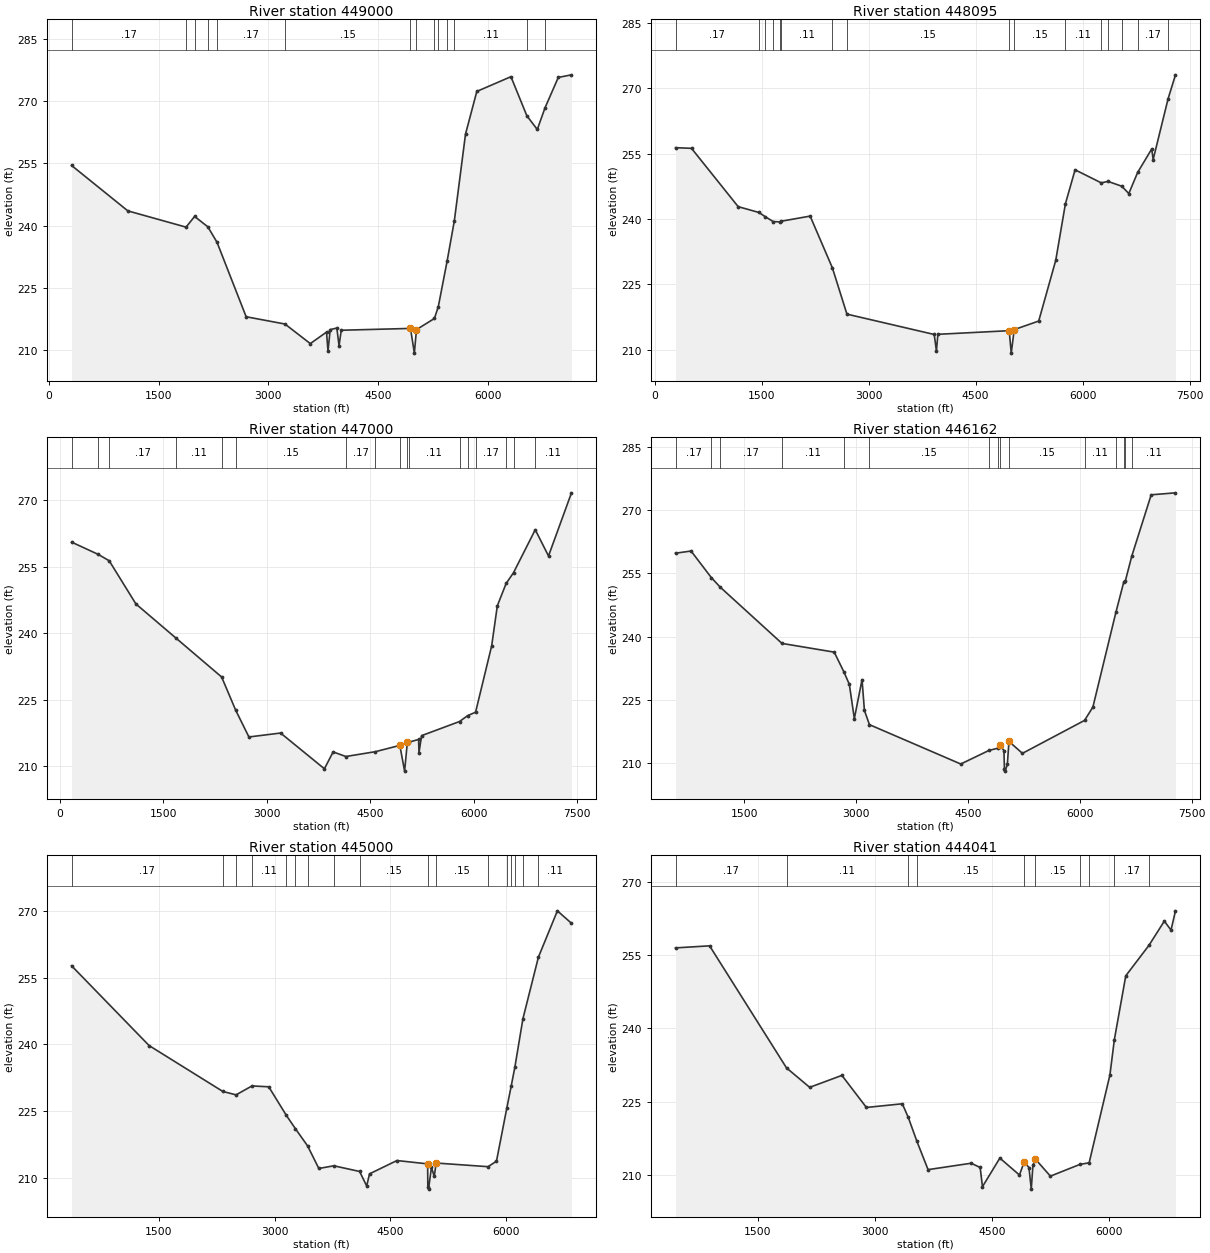
Type RM Length L Ch R = 1 ,449000  ,905,905,905
BEGIN DESCRIPTION:
WFSJ Main 444.0
END DESCRIPTION:
XS GIS Cut Line= 3
      3769895.97     10219507.59      3765245.56     10218889.51
      3763100.99     10218754.84
#Sta/Elev= 30
   308.7  254.52  1078.9  243.54  1875.7  239.61  1992.3   242.2  2173.4  239.69
  2298.9  235.96  2697.6  217.96  3228.8   216.2  3575.3  211.47  3797.2  214.25
  3817.4  209.67  3847.7  214.85  3938.5  215.23  3968.7  210.98    3999   214.7
  4946.2  215.14    4999  209.17  5027.8  214.85  5273.5  217.54  5326.8  220.41
  5447.9  231.47  5546.5  241.19  5699.1   262.1  5853.5   272.4  6320.3  275.96
  6538.6   266.5    6681  263.21  6786.8  268.44  6968.1  275.78  7148.8  276.41
#Mann= 14 ,-1 , 0
   308.7     .17       0  1875.7     .11       0  1992.3     .17       0
  2173.4     .11       0  2298.9     .17       0  3228.8     .15       0
  4946.2     .09       0  5027.8     .15       0  5273.5     .11       0
  5326.8     .15       0  5447.9     .17       0  5546.5     .11       0
  6538.6     .17       0  6786.8     .11       0
Bank Sta=4946.2,5027.8
XS Rating Curve= 0 ,0
Exp/Cntr=0.3,0.1

Type RM Length L Ch R = 1 ,448095  ,1095,1095,1095
BEGIN DESCRIPTION:
WFSJ Main 443.0
END DESCRIPTION:
XS GIS Cut Line= 3
      3769886.88     10219195.61      3765399.49     10218250.41
      3762986.07     10218470.64
#Sta/Elev= 30
   292.3  256.35   516.1   256.2  1170.2  242.82  1461.2  241.48    1549  240.53
  1660.8  239.39  1760.8  239.32  1775.1  239.47  2179.5  240.65    2491  228.78
  2695.2  218.15  3919.2  213.48  3949.9   209.7  3970.3  213.52  4970.2  214.35
    4999   209.2  5040.5   214.6  5383.8  216.56  5622.9   230.5  5758.5  243.49
    5894  251.27  6260.9  248.28  6355.3  248.61  6549.3   247.5  6647.1  245.82
  6771.1  250.67  6968.4  256.05  6988.5  253.63  7198.9  267.63  7301.6  273.07
#Mann= 16 ,-1 , 0
   292.3     .17       0  1461.2     .11       0    1549     .17       0
  1660.8     .11       0  1760.8     .17       0  1775.1     .11       0
    2491     .17       0  2695.2     .15       0  4970.2     .09       0
  5040.5     .15       0  5758.5     .11       0  6260.9     .17       0
  6355.3     .11       0  6549.3     .15       0  6771.1     .17       0
  7198.9     .11       0
Bank Sta=4970.2,5040.5
XS Rating Curve= 0 ,0
Exp/Cntr=0.3,0.1

Type RM Length L Ch R = 1 ,447000  ,838,838,838
BEGIN DESCRIPTION:
WFSJ Main 442.0
END DESCRIPTION:
XS GIS Cut Line= 3
      3770162.12     10218938.65      3765533.78     10217566.71
      3763307.19     10216626.14
#Sta/Elev= 30
   172.6  260.59   559.9  257.81   718.6  256.37  1105.3  246.63  1687.2   238.9
  2347.4  230.14    2551  222.65  2742.9   216.6  3201.8  217.49  3836.9  209.42
  3963.2  213.23  4147.6  212.19  4575.3  213.28  4929.9   214.7    4999  208.89
    5039  215.47  5057.3  215.41  5201.8  216.04  5207.2  213.05  5245.3   216.9
  5795.3  220.09  5911.6  221.41  6027.4  222.19  6260.6  237.18  6342.5  246.21
  6470.3  251.26  6576.9  253.68  6892.1  263.38  7084.2  257.46  7417.1  271.71
#Mann= 17 ,-1 , 0
   172.6     .17       0   559.9     .11       0   718.6     .17       0
  1687.2     .11       0  2347.4     .17       0    2551     .15       0
  4147.6     .17       0  4575.3     .15       0  4929.9     .09       0
    5039     .15       0  5057.3     .11       0  5795.3     .17       0
  5911.6     .11       0  6027.4     .17       0  6470.3     .11       0
  6576.9     .17       0  6892.1     .11       0
Bank Sta=4929.9,5039
XS Rating Curve= 0 ,0
Exp/Cntr=0.3,0.1

Type RM Length L Ch R = 1 ,446162  ,1162,1162,1162
BEGIN DESCRIPTION:
WFSJ Main 441.0
END DESCRIPTION:
XS GIS Cut Line= 3
      3770116.25     10218608.29       3765748.2     10217011.57
      3763857.82      10216213.2
#Sta/Elev= 30
   580.5  259.78   788.6   260.3  1061.7  253.96  1178.5  251.74  2007.7  238.37
  2708.1   236.3  2836.9  231.64  2910.5  228.67  2977.6  220.52  3080.9  229.78
  3112.8  222.47  3180.1  219.09  4404.5  209.75  4782.8  212.97    4900  213.49
  4927.5  214.24  4983.3  212.95    4990  208.56    4999  208.06  5029.3  209.67
  5050.6  215.11  5231.2  212.28  6064.2   220.1  6176.1  223.27    6486  245.86
  6591.4  253.05  6610.8  253.17  6696.9  259.07  6957.6  273.64  7283.3  274.11
#Mann= 15 ,-1 , 0
   580.5     .17       0  1061.7     .11       0  1178.5     .17       0
  2007.7     .11       0  2836.9     .17       0  3180.1     .15       0
  4782.8     .17       0    4900     .15       0  4927.5     .09       0
  5050.6     .15       0  6064.2     .11       0    6486     .15       0
  6591.4     .11       0  6610.8     .17       0  6696.9     .11       0
#XS Ineff= 1 ,-1
    2820  3080.9  229.78
Permanent Ineff=
       F
Bank Sta=4927.5,5050.6
XS Rating Curve= 0 ,0
Exp/Cntr=0.3,0.1

Type RM Length L Ch R = 1 ,445000  ,959,959,959
BEGIN DESCRIPTION:
WFSJ Main 440.0
END DESCRIPTION:
XS GIS Cut Line= 3
      3770428.22      10218011.8      3766052.66     10216481.36
      3764316.61     10215827.77
#Sta/Elev= 30
   364.5  257.64  1371.3  239.75    2328  229.47  2500.4   228.7  2706.8   230.7
  2924.7  230.51  3152.5  224.12  3270.3  221.13  3429.1  217.26  3574.9   212.2
  3769.8   212.8  4104.4  211.53  4196.4  208.27  4232.8  210.99  4589.3  213.98
  4987.5  213.23    4990  208.07    4999  207.57  5037.2   212.5  5073.2  210.41
  5098.1  213.42  5772.3   212.6  5881.3  213.84  6016.6  225.84  6071.5   230.6
  6120.6  234.97  6224.5  245.76  6425.3  259.55    6672  269.95    6855  267.16
#Mann= 17 ,-1 , 0
   364.5     .17       0    2328     .11       0  2500.4     .17       0
  2706.8     .11       0  3152.5     .17       0  3270.3     .11       0
  3429.1     .15       0  3769.8     .17       0  4104.4     .15       0
  4987.5     .09       0  5098.1     .15       0  5772.3     .17       0
  6016.6     .15       0  6071.5     .11       0  6120.6     .15       0
  6224.5     .17       0  6425.3     .11       0
Bank Sta=4987.5,5098.1
XS Rating Curve= 0 ,0
Exp/Cntr=0.3,0.1

Type RM Length L Ch R = 1 ,444041  ,948,948,948
BEGIN DESCRIPTION:
WFSJ Main 439.0
END DESCRIPTION:
XS GIS Cut Line= 3
      3770437.45     10217571.35       3766491.5     10215947.09
      3764391.46     10215571.09
#Sta/Elev= 30
   444.8  256.45   880.7  256.87  1865.5  231.94  2162.3  227.97  2574.7  230.41
  2888.3  223.86  3348.2  224.61  3424.7  221.82  3535.7  216.91  3677.8  211.16
  4229.3  212.47  4344.8   211.6  4374.2  207.68    4597  213.52  4847.7  210.06
  4908.7  212.76  4969.6  211.58    4999  207.18  5020.4  212.05  5050.9  213.33
  5243.9  209.83  5621.8  212.23    5740  212.56  6005.9  230.48  6062.9  237.73
    6209  250.75  6506.2  256.98  6702.7  261.92  6788.1  260.08  6845.4  264.02
#Mann= 10 ,-1 , 0
   444.8     .17       0  1865.5     .11       0  3424.7     .17       0
  3535.7     .15       0  4908.7     .09       0  5050.9     .15       0
  5621.8     .17       0    5740     .11       0  6062.9     .17       0
  6506.2     .11       0
Bank Sta=4908.7,5050.9
XS Rating Curve= 0 ,0
Exp/Cntr=0.3,0.1

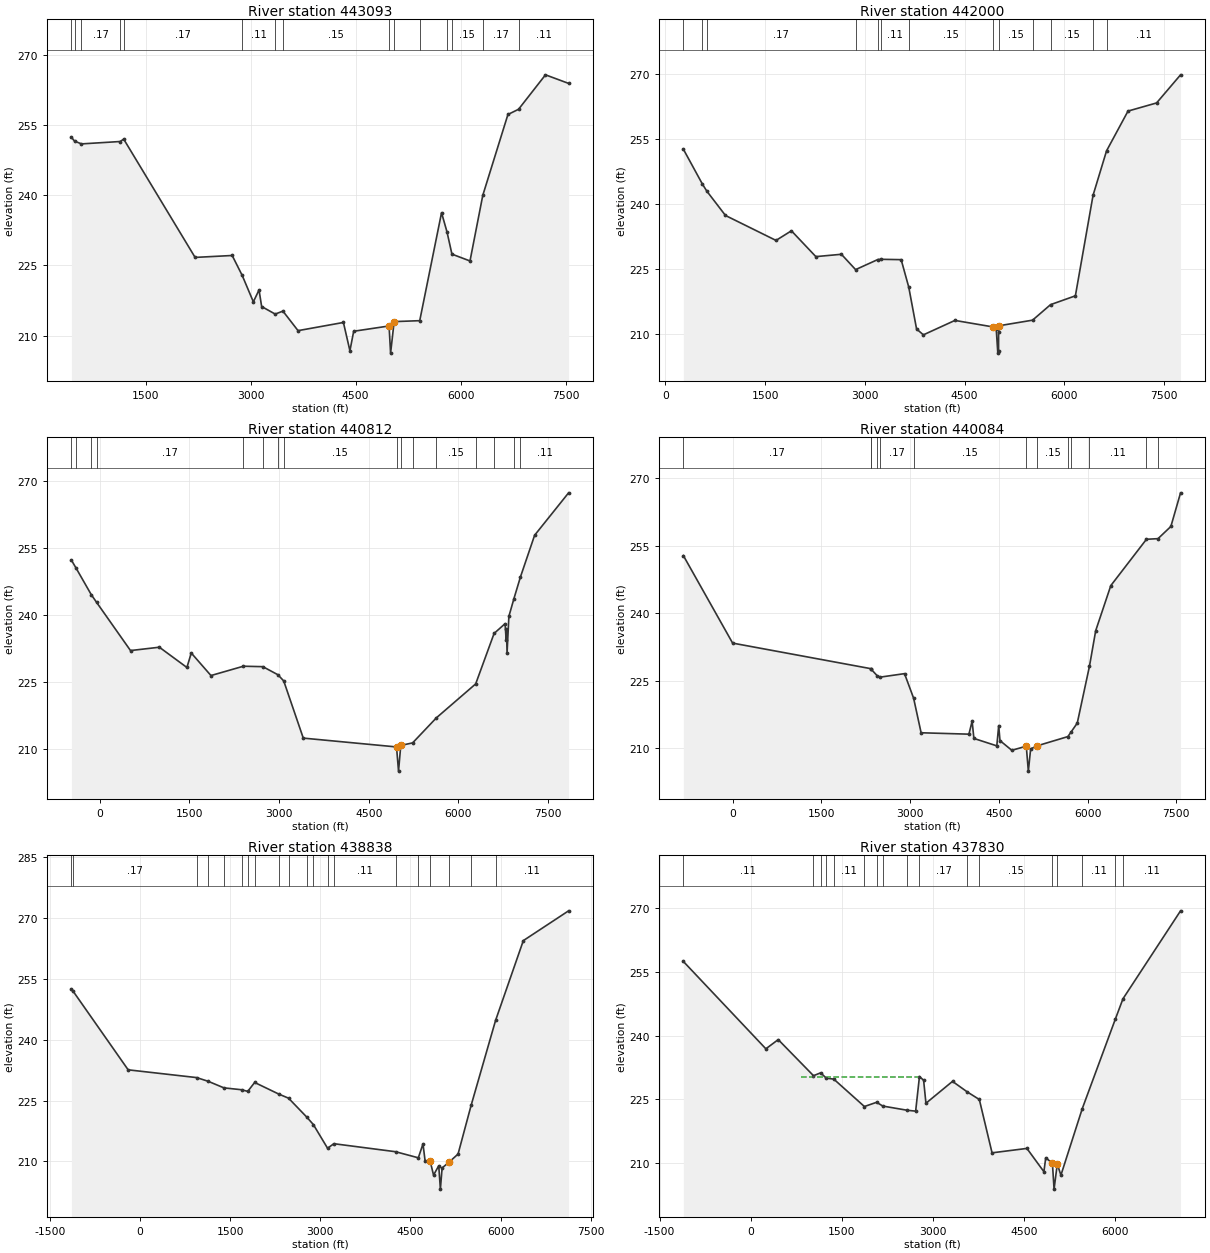
Type RM Length L Ch R = 1 ,443093  ,1093,1093,1093
BEGIN DESCRIPTION:
WFSJ Main 438.0
END DESCRIPTION:
XS GIS Cut Line= 3
      3770510.87     10217415.35       3766766.8     10215323.08
      3764078.11     10214488.02
#Sta/Elev= 30
     438  252.34   483.3  251.51   582.2  250.92  1135.8  251.43  1185.1  251.94
  2205.6  226.68  2735.4  227.09    2878  222.85    3038  217.19  3119.1  219.74
  3156.4  216.19  3349.9  214.58  3460.6  215.21  3676.5  211.04  4324.9  212.79
  4417.8  206.74  4471.5  210.91  4977.2  212.04    4999  206.24  5049.7  212.97
  5415.3  213.17  5727.1  236.23  5805.7  232.08  5875.4  227.38  6133.6  225.92
  6316.5  239.94  6675.6   257.2  6827.2  258.31  7212.3  265.67  7542.4  263.84
#Mann= 15 ,-1 , 0
     438     .17       0   483.3     .11       0   582.2     .17       0
  1135.8     .11       0  1185.1     .17       0    2878     .11       0
  3349.9     .17       0  3460.6     .15       0  4977.2     .09       0
  5049.7     .15       0  5415.3     .11       0  5805.7     .17       0
  5875.4     .15       0  6316.5     .17       0  6827.2     .11       0
#XS Ineff= 1 ,-1
  5727.1    6320  236.23
Permanent Ineff=
       F
Bank Sta=4977.2,5049.7
XS Rating Curve= 0 ,0
Exp/Cntr=0.3,0.1

Type RM Length L Ch R = 1 ,442000  ,1188,1188,1188
BEGIN DESCRIPTION:
WFSJ Main 437.0
END DESCRIPTION:
XS GIS Cut Line= 4
      3770657.69     10217406.19      3769850.13     10216277.44
        3766838.     10214826.65      3764197.69     10214065.98
#Sta/Elev= 30
   268.8  252.59   556.5   244.5   622.9  242.88   902.2  237.29  1662.3  231.53
  1894.1  233.75  2261.6  227.79  2646.1  228.33  2859.5  224.79  3192.7  227.11
    3245  227.17    3545  227.09  3659.2  220.74  3776.8  211.08  3879.1  209.73
  4353.5  213.06  4922.5  211.57  4975.4  211.02    4999  205.51    5010  206.01
  5010.6  210.31    5021  211.84  5521.6  213.12  5791.9   216.7  6165.7  218.74
  6431.5  241.95  6634.7  252.22  6957.3  261.39  7387.3  263.27  7747.7  269.76
#Mann= 13 ,-1 , 0
   268.8     .17       0   556.5     .11       0   622.9     .17       0
  2859.5     .11       0  3192.7     .17       0    3245     .11       0
  3659.2     .15       0  4922.5     .09       0    5021     .15       0
  5521.6     .17       0  5791.9     .15       0  6431.5     .17       0
  6634.7     .11       0
Bank Sta=4922.5,5021
XS Rating Curve= 0 ,0
Exp/Cntr=0.3,0.1

Type RM Length L Ch R = 1 ,440812  ,728,728,728
BEGIN DESCRIPTION:
WFSJ Main 436.0
END DESCRIPTION:
XS GIS Cut Line= 4
      3770758.63     10217369.48      3769437.19     10215075.31
      3766583.27     10214120.94      3764161.79      10213011.1
#Sta/Elev= 30
  -475.5  252.22  -400.6  250.51  -142.7  244.47   -52.7  242.73   513.6  231.95
   996.4   232.7  1457.6  228.16  1530.7   231.4  1859.9  226.35  2402.9  228.44
  2728.5  228.34  2979.1  226.54  3077.6  225.15    3405  212.33  4965.6  210.35
    4999  204.93  5036.6  210.69  5234.8  211.26    5633  216.88  6290.2  224.48
  6598.4  235.79  6782.4  237.98  6799.9  234.31  6805.4  236.82  6815.3   231.4
  6845.9  239.62  6930.3  243.59  7040.1  248.48  7276.4  257.79    7845   267.3
#Mann= 16 ,-1 , 0
  -475.5     .11       0  -400.6     .17       0  -142.7     .11       0
   -52.7     .17       0  2402.9     .11       0  2728.5     .17       0
  2979.1     .11       0  3077.6     .15       0  4965.6     .09       0
  5036.6     .15       0  5234.8     .17       0    5633     .15       0
  6290.2     .17       0  6598.4     .15       0  6930.3     .17       0
  7040.1     .11       0
Bank Sta=4965.6,5036.6
XS Rating Curve= 0 ,0
Exp/Cntr=0.3,0.1

Type RM Length L Ch R = 1 ,440084  ,1246,1246,1246
BEGIN DESCRIPTION:
WFSJ Main 435.0
END DESCRIPTION:
XS GIS Cut Line= 4
      3770832.02     10217396.97      3769519.78     10214644.01
       3767078.8     10213671.29      3764611.55     10212497.28
#Sta/Elev= 30
  -836.2   252.8    -2.9  233.34  2329.2  227.67  2337.5  227.57  2442.1  226.09
  2496.4  225.78  2904.5  226.55  3058.3  221.09  3185.1   213.4    3994  213.09
  4047.9  215.99  4077.9  212.14  4465.4  210.49  4497.7     215  4519.2  211.66
  4719.3   209.5    4964  210.42    4999  204.87  5037.8  209.81  5151.3  210.51
  5667.5  212.55  5724.6  213.62  5826.5  215.56  6032.9  228.21  6138.4  236.11
  6393.8  246.13  6996.7  256.43  7192.4  256.57  7409.7  259.28  7573.5  266.76
#Mann= 13 ,-1 , 0
  -836.2     .17       0  2329.2     .11       0  2337.5     .17       0
  2442.1     .15       0  2496.4     .17       0  3058.3     .15       0
    4964     .09       0  5151.3     .15       0  5667.5     .11       0
  5724.6     .15       0  6032.9     .11       0  6996.7     .15       0
  7192.4     .11       0
Bank Sta=4964,5151.3
XS Rating Curve= 0 ,0
Exp/Cntr=0.3,0.1

Type RM Length L Ch R = 1 ,438838  ,1008,1008,1008
BEGIN DESCRIPTION:
WFSJ Main 434.0
END DESCRIPTION:
XS GIS Cut Line= 4
      3770887.07     10217396.95      3769648.25      10214607.3
      3767299.04     10213047.28      3765042.25      10212230.8
#Sta/Elev= 30
 -1140.1  252.42 -1116.2     252  -195.8  232.56   943.4  230.65  1137.1  229.73
    1398  228.12  1690.2  227.66    1794  227.26    1909  229.45  2313.4  226.57
  2472.2  225.59  2775.6  220.93  2885.6  219.09  3122.2  213.26  3226.4  214.38
  4252.4  212.41  4632.1  210.91  4709.7  214.33  4744.1  210.23  4829.3  210.08
  4885.2  206.66  4971.9  208.94    4999   203.2  5027.9  208.41  5145.1  209.86
  5293.1  211.83  5510.2   223.8  5917.4  244.72  6379.2  264.36  7132.2  271.69
#Mann= 20 ,-1 , 0
 -1140.1     .11       0 -1116.2     .17       0   943.4     .11       0
  1137.1     .17       0    1398     .17       0  1690.2     .11       0
    1794     .17       0    1909     .11       0  2313.4     .17       0
  2472.2     .11       0  2775.6     .17       0  2885.6     .15       0
  3122.2     .17       0  3226.4     .11       0  4252.4     .11       0
  4632.1     .15       0  4829.3     .09       0  5145.1     .15       0
  5510.2     .17       0  5917.4     .11       0
Bank Sta=4829.3,5145.1
XS Rating Curve= 0 ,0
Exp/Cntr=0.3,0.1

Type RM Length L Ch R = 1 ,437830  ,882,882,882
BEGIN DESCRIPTION:
WFSJ Main 433.0
END DESCRIPTION:
XS GIS Cut Line= 5
      3773015.27      10213781.1      3770932.97      10212570.1
      3769519.78     10212212.21      3767279.49      10212109.1
      3765197.61     10212037.86
#Sta/Elev= 30
 -1109.3   257.5   250.1   236.9   453.7  239.07  1034.8  230.56  1153.6  231.24
  1244.1  229.99  1369.5  229.75  1873.7  223.29  2075.4  224.29  2176.3   223.4
  2578.7  222.41  2718.1   222.2  2780.8  230.35  2849.4  229.49  2887.7  224.06
  3325.4  229.22    3570  226.72  3767.3  224.95    3977  212.37  4551.2  213.41
  4831.5  207.92  4861.5  211.21  4971.6  209.91    4999  203.81  5051.7  209.72
  5111.7   207.1  5463.8   222.8  6010.2  243.97  6134.7  248.71  7083.1  269.44
#Mann= 17 ,-1 , 0
 -1109.3     .11       0  1034.8     .17       0  1153.6     .11       0
  1244.1     .17       0  1369.5     .11       0  1873.7     .17       0
  2075.4     .11       0  2176.3     .17       0  2578.7     .11       0
  2780.8     .17       0    3570     .11       0  3767.3     .15       0
  4971.6     .09       0  5051.7     .15       0  5463.8     .11       0
  6010.2     .17       0  6134.7     .11       0
#XS Ineff= 1 ,-1
     835  2779.3  230.36
Permanent Ineff=
       F
Bank Sta=4971.6,5051.7
XS Rating Curve= 0 ,0
Exp/Cntr=0.3,0.1

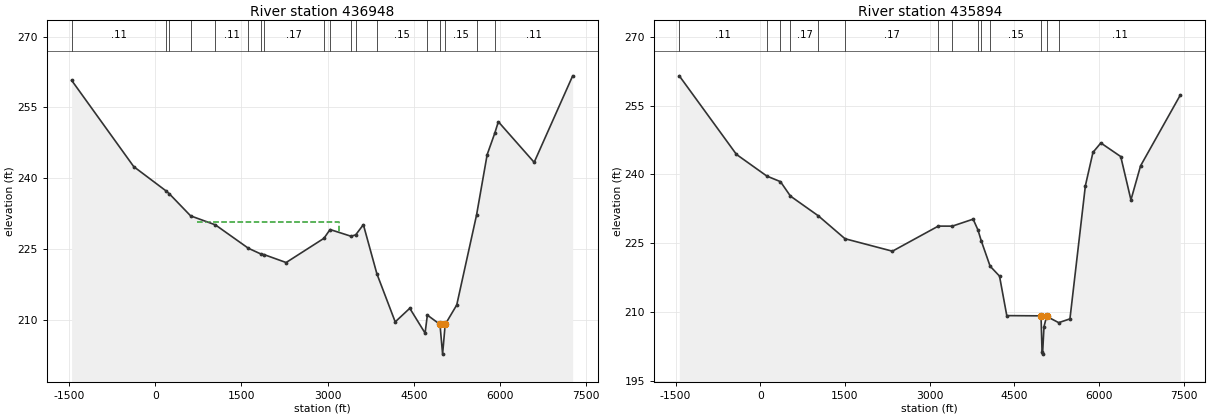
Type RM Length L Ch R = 1 ,436948  ,1054,1054,1054
BEGIN DESCRIPTION:
WFSJ Main 432.0
END DESCRIPTION:
XS GIS Cut Line= 4
      3773115.98     10213737.71      3770956.23     10212501.58
      3767303.45     10211480.75      3764881.32     10211237.84
#Sta/Elev= 30
   -1454  260.76  -373.1  242.49   192.3  237.32   244.6  236.76   616.5  232.07
  1046.7  230.17  1620.7  225.22  1835.8  224.02  1893.3  223.88  2277.3   222.2
  2934.9  227.32  3041.6  229.18  3406.8  227.76  3487.7  228.06    3621  230.21
    3856  219.82  4174.8  209.64  4428.1  212.52  4694.4  207.26  4733.8  211.08
  4953.4  209.11    4999  202.82  5043.9   209.1  5244.9  213.22  5589.1  232.22
  5774.3  245.04  5906.9  249.58  5968.5  251.99  6591.6   243.4  7261.5   261.7
#Mann= 18 ,-1 , 0
   -1454     .11       0   192.3     .17       0   244.6     .11       0
   616.5     .17       0  1046.7     .11       0  1620.7     .17       0
  1835.8     .11       0  1893.3     .17       0  2934.9     .11       0
  3041.6     .17       0  3406.8     .11       0  3487.7     .17       0
    3856     .15       0  4733.8     .12       0  4953.4     .09       0
  5043.9     .15       0  5589.1     .17       0  5906.9     .11       0
#XS Ineff= 1 ,-1
     735  3202.9   230.8
Permanent Ineff=
       F
Bank Sta=4953.4,5043.9
XS Rating Curve= 0 ,0
Exp/Cntr=0.3,0.1

Type RM Length L Ch R = 1 ,435894  ,850,850,850
BEGIN DESCRIPTION:
WFSJ Main 431.0
END DESCRIPTION:
XS GIS Cut Line= 4
      3773192.36     10213709.92        3770984.     10212418.25
      3767303.45     10210821.02      3765004.84     10210987.69
#Sta/Elev= 30
 -1435.5  261.46    -423  244.36   116.7  239.64   356.9  238.43   533.3  235.29
  1027.9  230.99  1499.9  226.01  2339.6   223.3  3152.4  228.76  3400.1  228.75
  3769.5  230.27  3854.4  227.93    3913  225.56    4070  220.04  4236.4  217.88
  4365.3  209.28  4971.9  209.23    4990   201.4    4999   200.9  5024.3  206.88
 5071.06  209.12  5284.9  207.75    5484  208.57  5757.6  237.56  5891.9  244.81
  6031.3  246.85  6383.9  243.89  6564.4  234.46  6734.8  241.87  7439.7   257.3
#Mann= 14 ,-1 , 0
 -1435.5     .11       0   116.7     .17       0   356.9     .11       0
   533.3     .17       0  1027.9     .11       0  1499.9     .17       0
  3152.4     .11       0  3400.1     .17       0  3854.4     .11       0
    3913     .17       0    4070     .15       0  4971.9     .09       0
 5071.06     .15       0  5284.9     .11       0
#XS Ineff= 1 ,-1
    1010  3769.5  230.27
Permanent Ineff=
       F
Bank Sta=4971.9,5071.06
XS Rating Curve= 0 ,0
Exp/Cntr=0.3,0.1