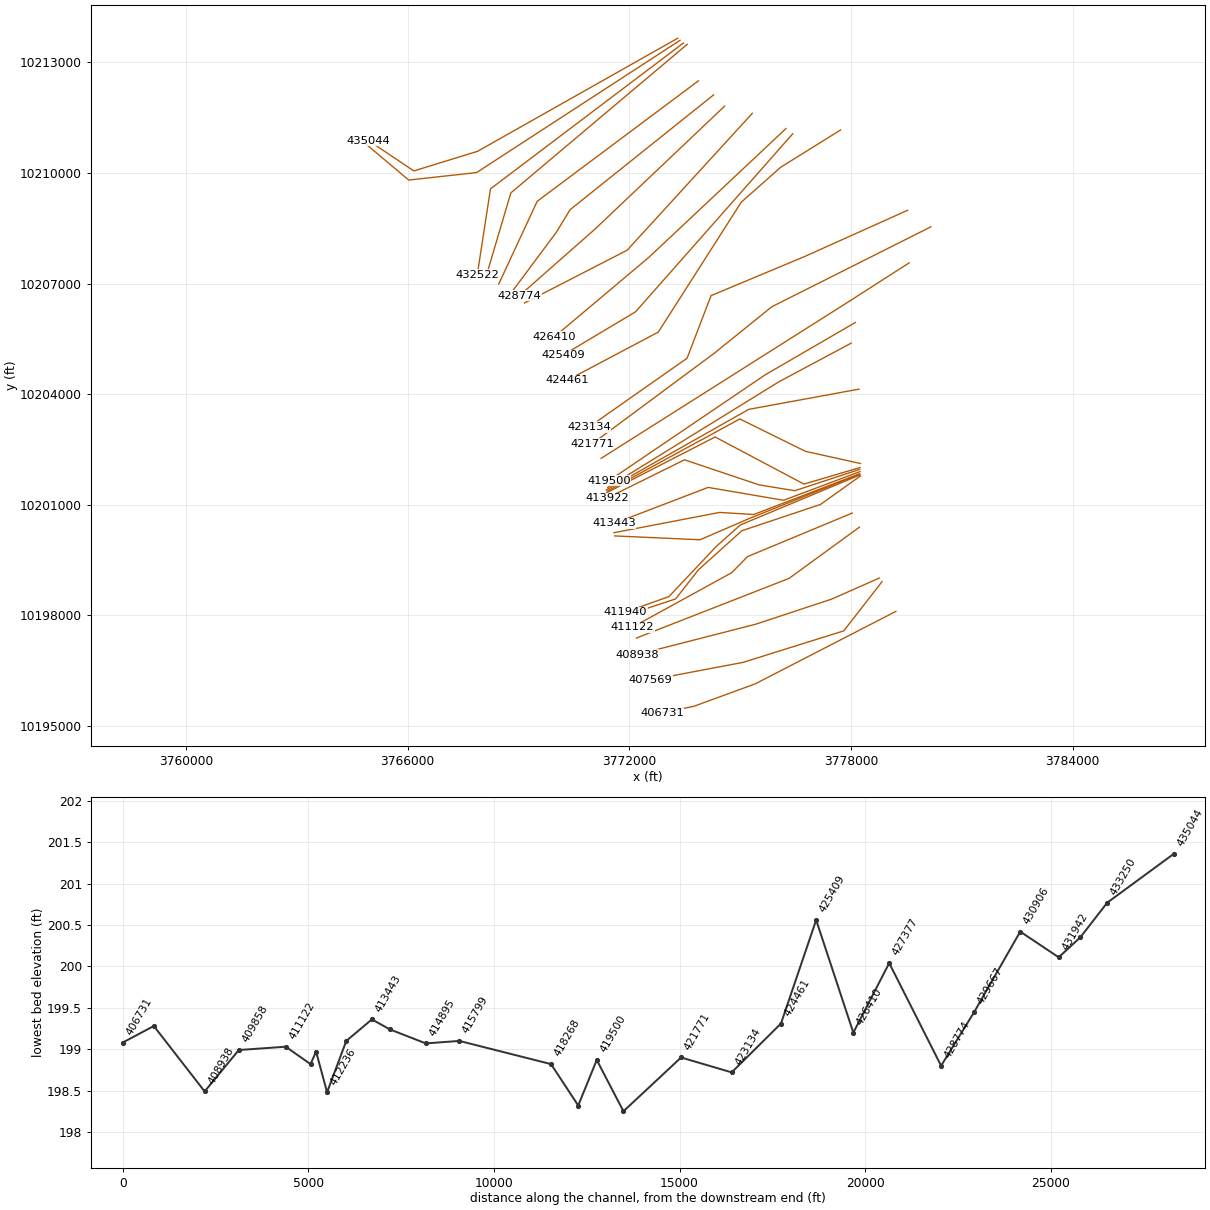
HEC-RAS study WFSJ Main.prj: WFSJ Main Base Level Engineering

--- WFSJ Main.g01 (geometry) --- (continued)

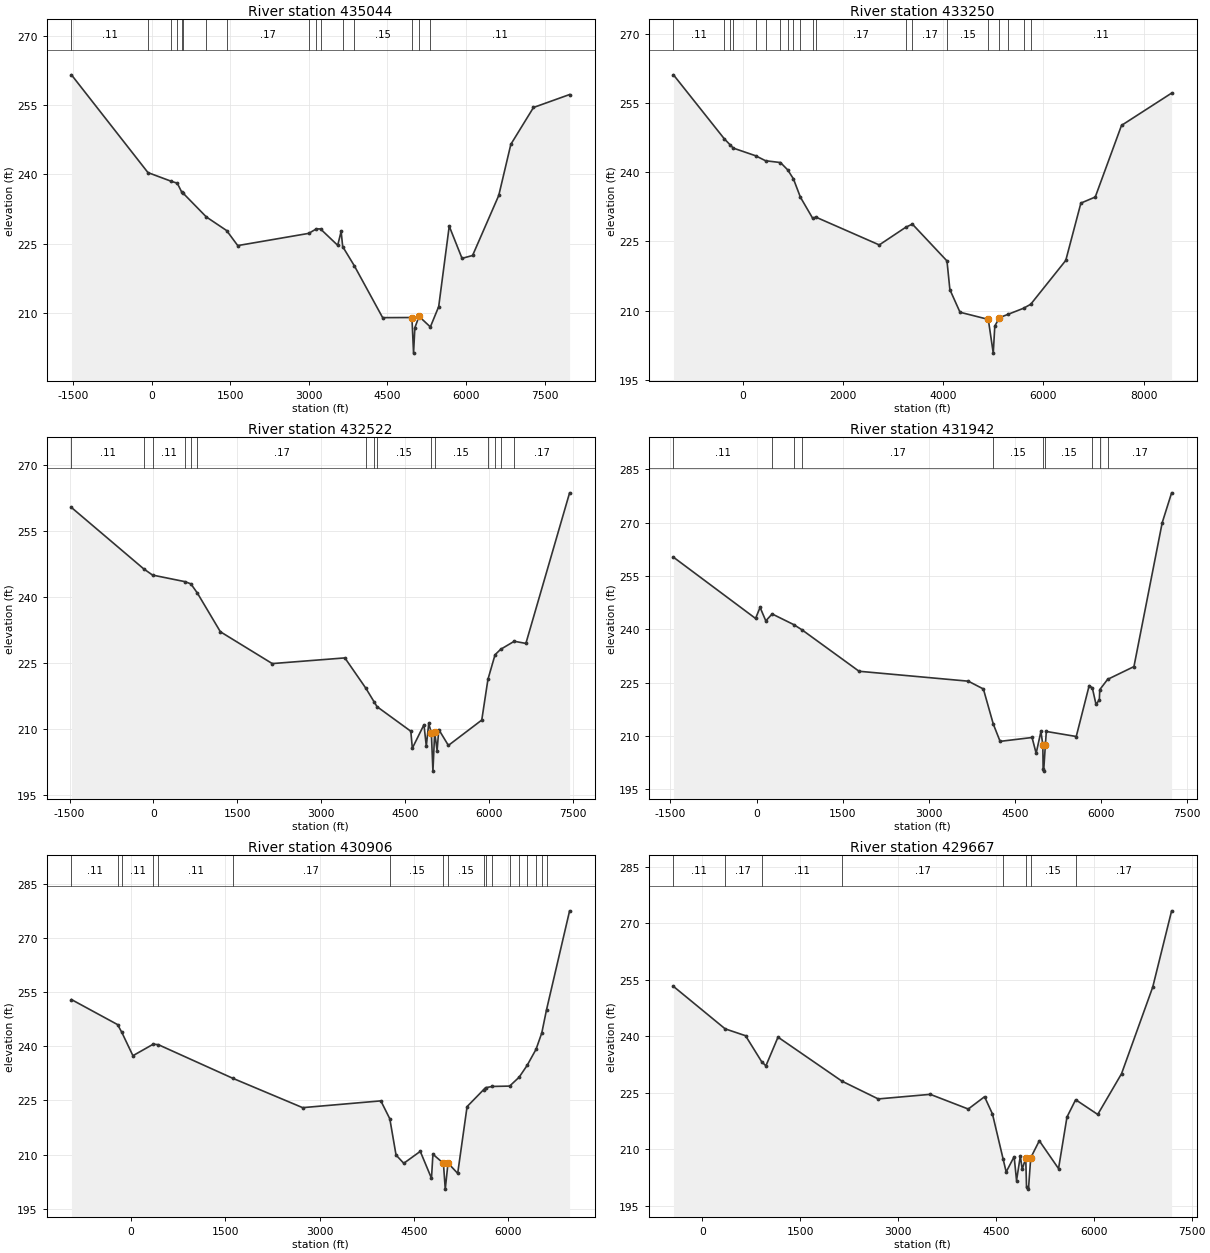
Type RM Length L Ch R = 1 ,435044  ,1794,1794,1794
BEGIN DESCRIPTION:
WFSJ Main 430.0
END DESCRIPTION:
XS GIS Cut Line= 4
      3773309.68     10213652.92      3767895.52     10210587.96
      3766170.32     10210055.72      3764941.75     10210880.88
#Sta/Elev= 30
 -1529.9  261.53   -69.4  240.39   378.7   238.5   489.7   238.1   572.6  236.23
   600.7  235.95  1044.8   230.8  1431.7  227.86  1643.8  224.61  2998.1  227.25
  3143.6  228.22  3223.2  228.21  3551.3  224.67    3617  227.68  3646.6  224.39
  3867.5  220.27  4409.3  209.03  4967.9  209.06    4999  201.36    5024  206.85
  5103.8  209.31  5319.6  207.02  5478.7  211.41  5679.9  228.81  5924.2  221.85
  6125.4  222.47  6624.9  235.45  6855.9  246.51  7287.9  254.47    7977  257.27
#Mann= 16 ,-1 , 0
 -1529.9     .11       0   -69.4     .17       0   378.7     .11       0
   489.7     .17       0   572.6     .11       0   600.7     .17       0
  1044.8     .11       0  1431.7     .17       0  2998.1     .11       0
  3143.6     .17       0  3223.2     .11       0  3646.6     .17       0
  3867.5     .15       0  4967.9     .09       0  5103.8     .15       0
  5319.6     .11       0
#XS Ineff= 1 ,-1
  5679.9    6460  228.81
Permanent Ineff=
       F
Bank Sta=4967.9,5103.8
XS Rating Curve= 0 ,0
Exp/Cntr=0.3,0.1

Type RM Length L Ch R = 1 ,433250  ,728,728,728
BEGIN DESCRIPTION:
WFSJ Main 429.0
END DESCRIPTION:
XS GIS Cut Line= 4
      3773373.96     10213597.89      3767867.85     10210011.07
      3766032.67     10209807.95      3764867.28     10210789.82
#Sta/Elev= 30
 -1383.2  261.08  -369.3  247.22  -254.4  245.93  -189.4   245.2   254.1  243.55
   455.1  242.46   752.2  242.07     895   240.5  1009.9  238.56  1149.8  234.57
  1394.6     230  1457.3  230.25  2723.8  224.22  3254.3  228.06  3384.4  228.73
  4075.1  220.75  4133.3  214.53  4335.5  209.63  4899.9  208.08    4999  200.77
  5029.7  206.64  5123.3  208.46  5299.2   209.2  5602.7  210.49  5746.5  211.36
  6445.8  220.86  6747.6  233.28  7034.4   234.6  7558.3  250.12  8558.4  257.12
#Mann= 20 ,-1 , 0
 -1383.2     .11       0  -369.3     .17       0  -254.4     .11       0
  -189.4     .17       0   254.1     .11       0   455.1     .17       0
   752.2     .11       0     895     .17       0  1009.9     .17       0
  1149.8     .17       0  1394.6     .11       0  1457.3     .17       0
  3254.3     .11       0  3384.4     .17       0  4075.1     .15       0
  4899.9     .09       0  5123.3     .15       0  5299.2     .11       0
  5602.7     .15       0  5746.5     .11       0
Bank Sta=4899.9,5123.3
XS Rating Curve= 0 ,0
Exp/Cntr=0.3,0.1

Type RM Length L Ch R = 1 ,432522  ,580,580,580
BEGIN DESCRIPTION:
WFSJ Main 428.0
END DESCRIPTION:
XS GIS Cut Line= 3
      3773465.68     10213524.44      3768244.23     10209569.36
      3767886.34     10207238.46
#Sta/Elev= 30
 -1465.5  260.24  -175.3  246.32   -15.7  244.89   561.7   243.4   670.1  242.89
   787.4  240.78  1197.9  232.01  2125.8  224.78  3424.3  226.07  3800.4  219.16
  3944.5  216.14  3999.6  214.99  4603.5  209.41  4630.7  205.56  4838.7  210.89
  4880.4  206.03    4924  211.18 4970.89  209.03    4999  200.35  5030.2  209.16
  5073.8  205.02  5103.3   209.8  5275.3  206.19  5872.2  211.95  5982.5  221.18
  6109.9  226.79  6209.9  228.02  6453.5  229.85  6661.3  229.36    7443  263.57
#Mann= 15 ,-1 , 0
 -1465.5     .11       0  -175.3     .17       0   -15.7     .11       0
   561.7     .17       0   670.1     .11       0   787.4     .17       0
  3800.4     .15       0  3944.5     .17       0  3999.6     .15       0
 4970.89     .09       0  5030.2     .15       0  5982.5     .17       0
  6109.9     .15       0  6209.9     .11       0  6453.5     .17       0
Bank Sta=4970.89,5030.2
XS Rating Curve= 0 ,0
Exp/Cntr=0.3,0.1

Type RM Length L Ch R = 1 ,431942  ,1036,1036,1036
BEGIN DESCRIPTION:
WFSJ Main 427.0
END DESCRIPTION:
XS GIS Cut Line= 3
      3773566.65     10213487.76      3768794.83     10209459.24
      3768106.58     10207128.37
#Sta/Elev= 30
 -1447.8  260.28   -17.7  243.05    60.3  246.18   160.3  242.37   270.3  244.32
   645.7  241.33   793.5  239.82  1784.4   228.2  3686.6  225.41  3949.3  223.22
  4122.5  213.32  4240.5  208.48  4797.1  209.57  4868.2  205.12  4951.6  211.27
  4984.4   207.5    4990  200.61    4999  200.11    5029  207.53  5045.5  211.27
  5566.8  209.85  5791.9  224.18  5846.6  223.52  5910.9  218.88  5968.8  220.17
  5976.1  223.02  6112.7  225.92  6571.4  229.51  7063.6  269.99  7227.5  278.39
#Mann= 10 ,-1 , 0
 -1447.8     .11       0   270.3     .17       0   645.7     .11       0
   793.5     .17       0  4122.5     .15       0  4984.4     .09       0
    5029     .15       0  5846.6     .11       0  5976.1     .15       0
  6112.7     .17       0
Bank Sta=4984.4,5029
XS Rating Curve= 0 ,0
Exp/Cntr=0.3,0.1

Type RM Length L Ch R = 1 ,430906  ,1239,1239,1239
BEGIN DESCRIPTION:
WFSJ Main 426.0
END DESCRIPTION:
XS GIS Cut Line= 3
      3773870.55     10212498.09      3769508.61     10209232.05
      3768466.97     10206986.02
#Sta/Elev= 30
  -947.9  252.98  -214.3  246.04  -147.2  243.91    29.9  237.41   353.6  240.61
   434.4  240.47    1619  231.15  2730.3  223.01  3974.3  224.89  4116.9  219.92
    4216  209.88    4339  207.58  4601.6  210.89  4779.9  203.42  4802.8   210.1
 4969.89  207.57    4999  200.42  5042.9  207.66  5196.8  204.78  5346.2   223.3
  5608.3  227.98  5639.7  228.54    5750  228.89  6022.9  228.99  6174.3  231.45
  6301.5  234.73  6443.7   239.2  6535.1  243.76  6609.7  250.13  6977.1  277.58
#Mann= 18 ,-1 , 0
  -947.9     .11       0  -214.3     .17       0  -147.2     .11       0
   353.6     .17       0   434.4     .11       0    1619     .17       0
  4116.9     .15       0 4969.89     .09       0  5042.9     .15       0
  5608.3     .17       0  5639.7     .15       0    5750     .17       0
  6022.9     .11       0  6174.3     .17       0  6301.5     .11       0
  6443.7     .17       0  6535.1     .11       0  6609.7     .17       0
Bank Sta=4969.89,5042.9
XS Rating Curve= 0 ,0
Exp/Cntr=0.3,0.1

Type RM Length L Ch R = 1 ,429667  ,893,893,893
BEGIN DESCRIPTION:
WFSJ Main 425.0
END DESCRIPTION:
XS GIS Cut Line= 4
      3774282.92     10212118.35      3770398.36     10209004.19
      3770029.44     10208396.55      3768869.15     10206835.04
#Sta/Elev= 30
  -442.2  253.28   349.9  242.01   662.4  240.19   907.6  233.34   974.4  232.18
  1160.1  239.81  2140.1  228.12  2696.5   223.4  3493.5  224.62    4076  220.72
  4325.7  223.99  4447.3  219.39  4608.9  207.54    4657  204.01  4779.2  208.07
    4816  201.73  4874.2  208.28  4902.8  204.72 4957.01   207.7  4969.1  199.95
    4999  199.45  5033.1  207.76  5164.9   212.3  5459.7   204.9  5589.1   218.6
  5722.1  223.19  6060.5  219.28  6425.3   230.1  6903.3   253.1  7192.8  273.35
#Mann= 8 ,-1 , 0
  -442.2     .11       0   349.9     .17       0   907.6     .11       0
  2140.1     .17       0  4608.9     .15       0 4957.01     .09       0
  5033.1     .15       0  5722.1     .17       0
Bank Sta=4957.01,5033.1
XS Rating Curve= 0 ,0
Exp/Cntr=0.3,0.1

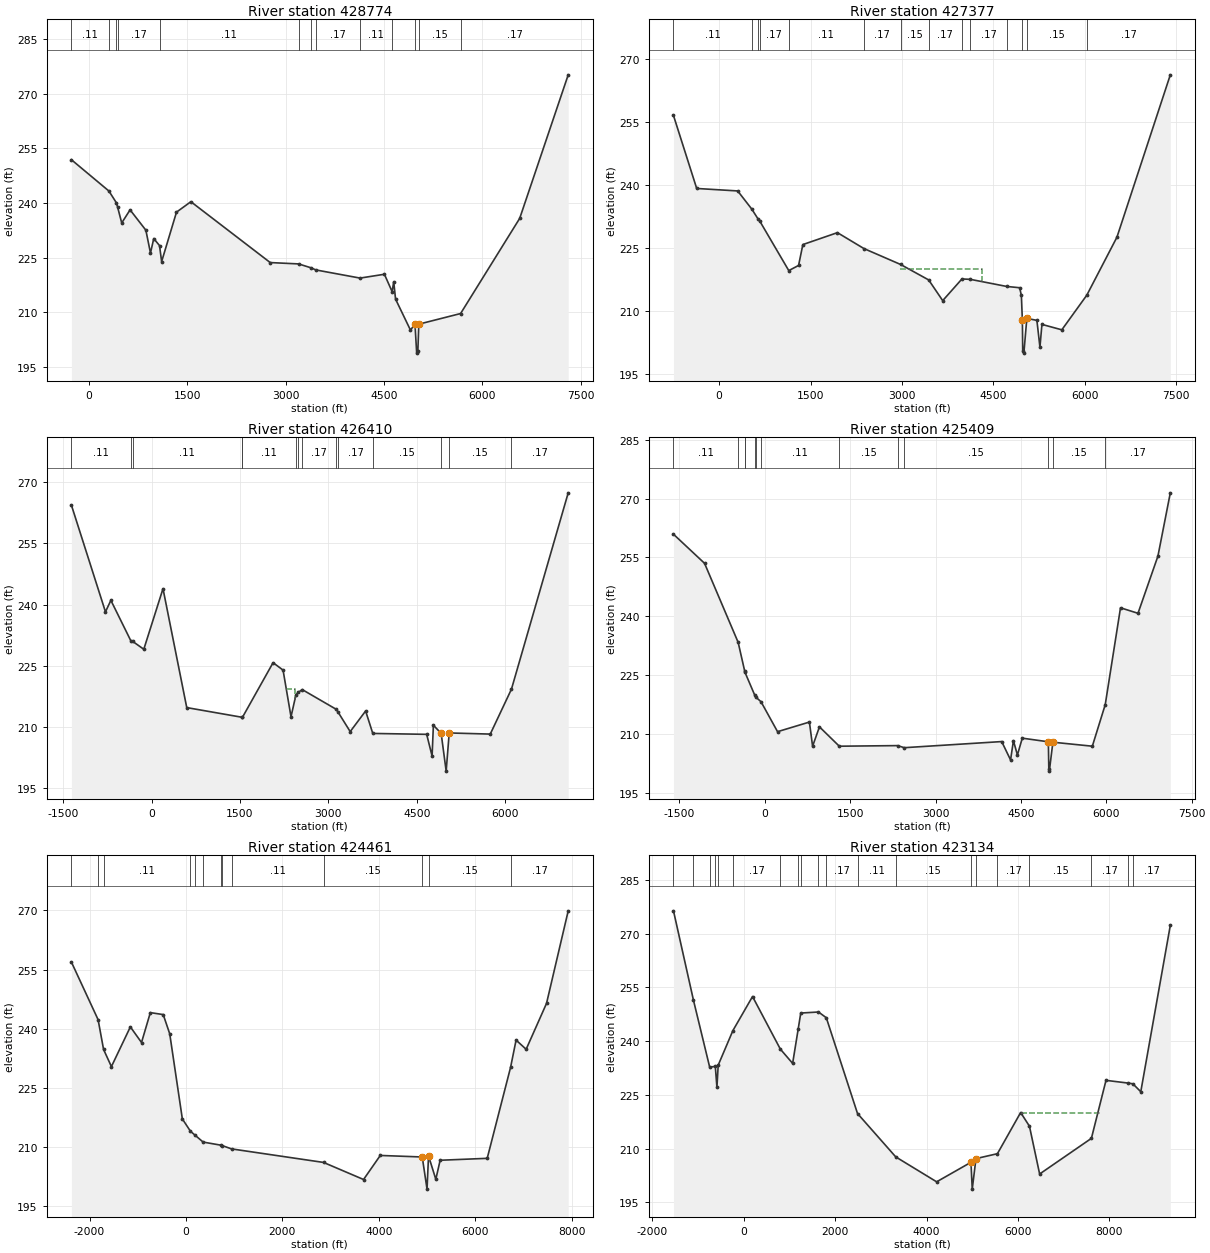
Type RM Length L Ch R = 1 ,428774  ,1397,1397,1397
BEGIN DESCRIPTION:
WFSJ Main 424.0
END DESCRIPTION:
XS GIS Cut Line= 3
      3774580.82     10211812.64      3771065.22     10208470.65
      3769025.32     10206669.46
#Sta/Elev= 30
  -263.6   251.9   308.4   243.3   420.1  240.13   439.8  238.96   503.5  234.54
   630.9  238.13   871.5  232.55   941.9  226.28   991.6  230.25  1079.8  228.32
  1111.8  223.93  1338.3   237.5  1557.5  240.37  2766.9  223.66  3199.2  223.29
  3392.7   222.2    3462  221.64  4135.9   219.4    4507  220.45  4624.8  215.67
  4648.9  218.42  4676.9  213.63  4903.7  205.14 4973.04  206.71    4999   198.8
    5017  199.48 5031.14  206.75  5668.2  209.67  6568.8  235.79  7308.3   275.2
#Mann= 13 ,-1 , 0
  -263.6     .11       0   308.4     .17       0   420.1     .11       0
   439.8     .17       0  1079.8     .11       0  3199.2     .17       0
  3392.7     .11       0    3462     .17       0  4135.9     .11       0
  4624.8     .15       0 4973.04     .09       0 5031.14     .15       0
  5668.2     .17       0
Bank Sta=4973.04,5031.14
XS Rating Curve= 0 ,0
Exp/Cntr=0.3,0.1

Type RM Length L Ch R = 1 ,427377  ,967,967,967
BEGIN DESCRIPTION:
WFSJ Main 423.0
END DESCRIPTION:
XS GIS Cut Line= 3
      3775329.56     10211617.37      3771944.12     10207906.41
      3769166.33     10206474.11
#Sta/Elev= 30
  -747.6  256.63  -366.8  239.25   305.5  238.66   537.1  234.33   638.5  232.01
   664.8  231.55  1143.4  219.69    1304  220.92  1374.3  225.89  1941.1  228.73
    2376  224.94  2977.7  221.15  3437.9  217.47    3668  212.54  3983.3   217.7
  4121.1  217.61  4716.7  215.92  4930.3  215.61    4958  213.77  4974.6  207.83
  4980.2  200.54    4999  200.04  5047.7  208.31  5212.7  207.84  5262.7  201.44
  5295.2  206.88  5621.5  205.59  6031.3  213.84  6525.5  227.65  7400.9  266.31
#Mann= 14 ,-1 , 0
  -747.6     .11       0   537.1     .17       0   638.5     .11       0
   664.8     .17       0  1143.4     .11       0    2376     .17       0
  2977.7     .15       0  3437.9     .17       0  3983.3     .15       0
  4121.1     .17       0  4716.7     .15       0  4974.6     .09       0
  5047.7     .15       0  6031.3     .17       0
#XS Ineff= 2 ,-1
    2960  4315.4  220.07     750  1941.1  228.73
Permanent Ineff=
       F       F
Bank Sta=4974.6,5047.7
XS Rating Curve= 0 ,0
Exp/Cntr=0.3,0.1

Type RM Length L Ch R = 1 ,426410  ,1001,1001,1001
BEGIN DESCRIPTION:
WFSJ Main 422.0
END DESCRIPTION:
XS GIS Cut Line= 3
        3776241.     10211205.02      3772530.06      10207711.1
       3769981.5      10205563.8
#Sta/Elev= 30
 -1359.7  264.36  -781.5  238.21  -689.7  241.03  -348.4  231.05  -321.4  230.99
    -131  229.05   194.7  243.89   597.7  214.76  1539.5  212.38  1543.1  212.39
  2062.3  225.76  2231.8  223.94  2366.6  212.52  2450.8  217.92  2491.2   218.5
  2557.2  219.17  3136.2  214.32    3169  213.56  3370.8  208.88  3632.5  213.93
    3754  208.43  4668.5  208.21  4760.2  202.89  4782.3  210.44 4914.13  208.45
    4999   199.2 5050.68  208.55  5747.2  208.27  6106.9  219.28  7069.8  267.36
#Mann= 14 ,-1 , 0
 -1359.7     .11       0  -348.4     .17       0  -321.4     .11       0
  1539.5     .15       0  1543.1     .11       0  2450.8     .17       0
  2491.2     .11       0  2557.2     .17       0  3136.2     .15       0
    3169     .17       0    3754     .15       0 4914.13     .09       0
 5050.68     .15       0  6106.9     .17       0
#XS Ineff= 2 ,-1
     350  2062.3  225.76    2280  2430.1  219.33
Permanent Ineff=
       F       F
Bank Sta=4914.13,5050.68
XS Rating Curve= 0 ,0
Exp/Cntr=0.3,0.1

Type RM Length L Ch R = 1 ,425409  ,948,948,948
BEGIN DESCRIPTION:
WFSJ Main 421.0
END DESCRIPTION:
XS GIS Cut Line= 3
      3776425.49     10211063.99      3772171.99      10206235.4
      3770202.04     10205056.55
#Sta/Elev= 30
 -1605.6  260.91 -1059.5   253.5    -469  233.36  -353.6     226  -350.5  225.78
  -179.7  219.98  -164.3  219.49   -67.4  218.24   223.1  210.61   782.9  213.06
   838.9   206.9   959.4  211.84    1308  206.91  2331.7  207.06  2450.1  206.53
  4162.2  208.09  4317.8  203.41    4368  208.32  4438.3  204.67  4523.6  208.96
  4981.8  208.03    4990  201.06    4999  200.56  5061.5  207.93  5754.7  206.91
  5981.5   217.5  6249.8  242.17  6557.1  240.77  6907.2  255.33    7125  271.46
#Mann= 13 ,-1 , 0
 -1605.6     .11       0    -469     .17       0  -353.6     .11       0
  -350.5     .17       0  -179.7     .11       0  -164.3     .17       0
   -67.4     .11       0    1308     .15       0  2331.7     .17       0
  2450.1     .15       0  4981.8     .09       0  5061.5     .15       0
  5981.5     .17       0
Bank Sta=4981.8,5061.5
XS Rating Curve= 0 ,0
Exp/Cntr=0.3,0.1

Type RM Length L Ch R = 1 ,424461  ,1327,1327,1327
BEGIN DESCRIPTION:
WFSJ Main 420.0
END DESCRIPTION:
XS GIS Cut Line= 5
      3777717.54     10211165.08      3776100.37     10210156.84
      3775032.23     10209208.49      3772786.14     10205684.62
      3770321.64     10204377.54
#Sta/Elev= 30
   -2376   256.9 -1821.9  242.28 -1708.3  234.72 -1545.9  230.38   -1153  240.45
  -921.7  236.49  -738.8  244.07  -471.7  243.57  -336.7   238.7     -75  217.11
    93.7  213.98   181.1  213.07     356  211.24   731.1  210.44     747  210.37
   946.1  209.51    2853  206.08  3682.5  201.75  4029.6  207.85  4899.6  207.46
    4999  199.31    5030  207.74  5181.2   201.8  5270.8  206.63  6246.8  207.12
  6731.2  230.18  6845.6   237.1  7054.2  234.77    7477  246.41  7926.6  269.88
#Mann= 13 ,-1 , 0
   -2376     .11       0 -1821.9     .15       0 -1708.3     .11       0
    93.7     .17       0   181.1     .11       0     356     .17       0
   731.1     .11       0     747     .17       0   946.1     .11       0
    2853     .15       0  4899.6     .09       0    5030     .15       0
  6731.2     .17       0
Bank Sta=4899.6,5030
XS Rating Curve= 0 ,0
Exp/Cntr=0.3,0.1

Type RM Length L Ch R = 1 ,423134  ,1363,1363,1363
BEGIN DESCRIPTION:
WFSJ Main 419.0
END DESCRIPTION:
XS GIS Cut Line= 5
      3779534.43     10208988.89      3776739.26     10207731.06
      3774213.65      10206672.9      3773564.78     10204975.85
      3770909.42     10203109.11
#Sta/Elev= 30
 -1535.1   276.4 -1098.6  251.48  -743.7  232.78  -620.4  232.97  -584.8  227.13
  -557.2  233.32  -235.4  242.98   193.8  252.48   802.1   237.8    1071  233.82
    1192  243.37  1248.6  247.87  1636.3  248.16  1807.2  246.56  2489.9  219.82
  3326.7  207.71  4220.4  200.76  4971.1  206.21    4999  198.72  5080.6  207.24
  5549.8  208.61  6057.8   220.1  6250.4  216.28  6473.1  202.94  7605.2  212.89
  7924.6  229.08  8410.3  228.32  8511.5  228.12  8685.2  225.91  9331.1  272.35
#Mann= 20 ,-1 , 0
 -1535.1     .11       0 -1098.6     .17       0  -743.7     .15       0
  -620.4     .17       0  -557.2     .15       0  -235.4     .17       0
   802.1     .17       0    1192     .11       0  1248.6     .17       0
  1636.3     .11       0  1807.2     .17       0  2489.9     .11       0
  3326.7     .15       0  4971.1     .09       0  5080.6     .15       0
  5549.8     .17       0  6250.4     .15       0  7605.2     .17       0
  8410.3     .15       0  8511.5     .17       0
#XS Ineff= 1 ,-1
  6085.1    7800  220.01
Permanent Ineff=
       F
Bank Sta=4971.1,5080.6
XS Rating Curve= 0 ,0
Exp/Cntr=0.3,0.1

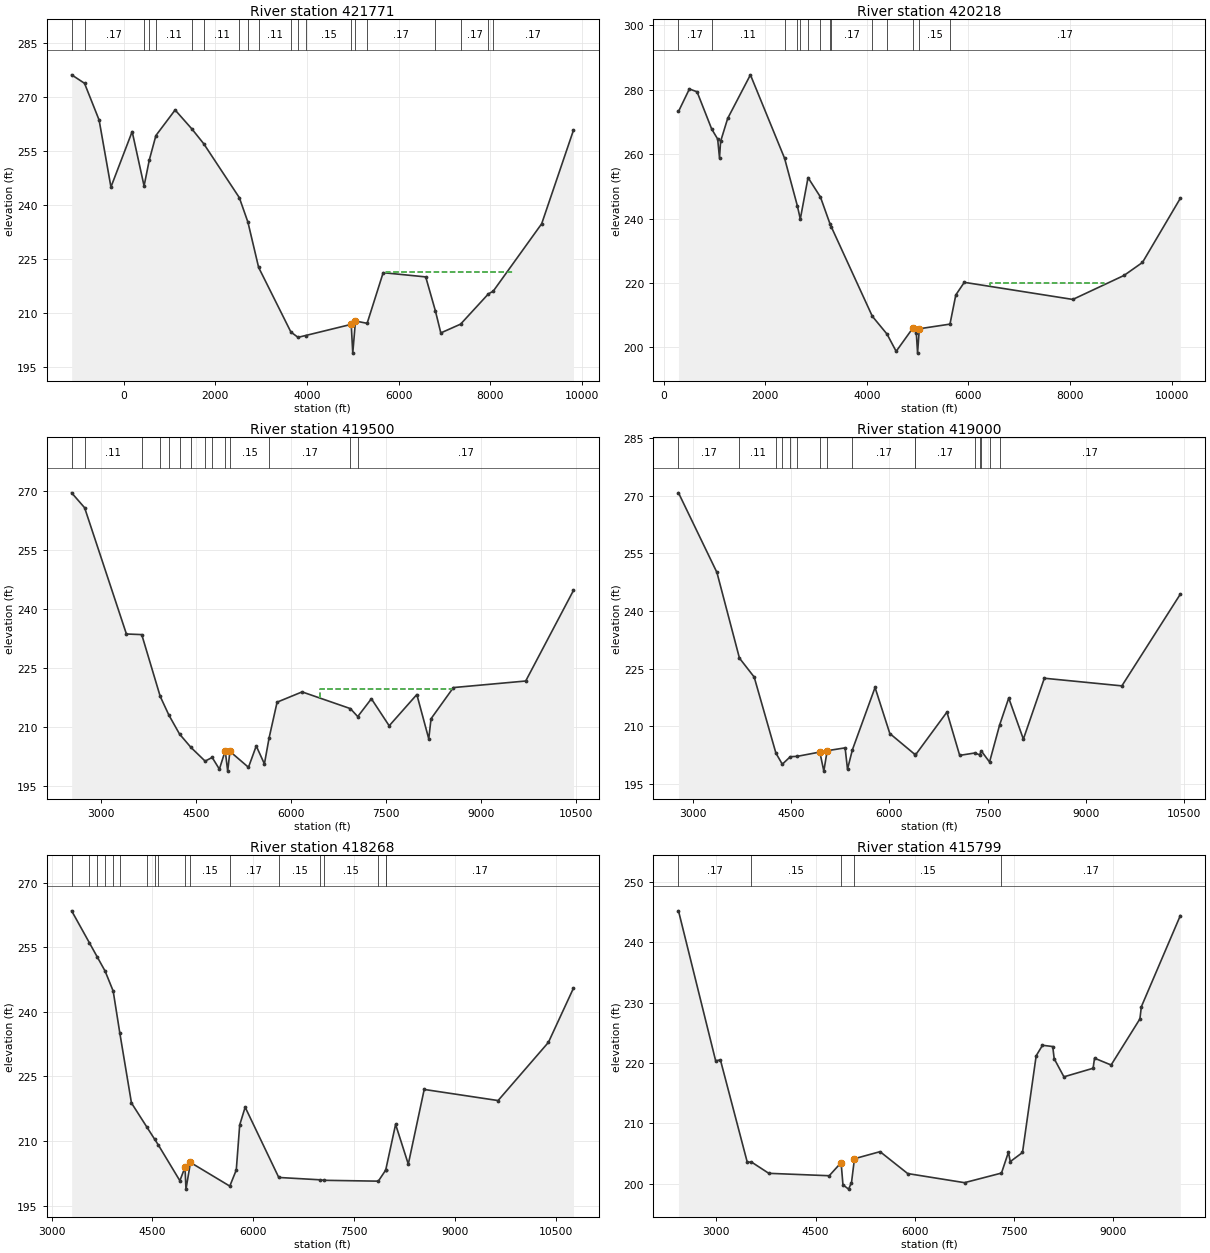
Type RM Length L Ch R = 1 ,421771  ,1553,1553,1553
BEGIN DESCRIPTION:
WFSJ Main 418.0
END DESCRIPTION:
XS GIS Cut Line= 4
      3780163.27     10208539.64      3775860.79     10206373.42
      3774293.51     10205105.63      3770989.23     10202649.88
#Sta/Elev= 30
 -1135.1  276.08  -853.9  273.73  -535.6  263.54  -277.4  244.96   185.7  260.34
   445.6  245.26   559.9  252.48   703.9  259.25  1122.9  266.33    1493  261.01
  1747.9  256.96  2523.7  242.02  2711.1  235.24  2945.1  222.67  3649.3  204.75
  3804.5  203.28  3968.6  203.78  4965.6  206.88    4999   198.9  5058.3   207.8
  5312.6  207.17  5662.7  221.21  6590.6  220.04  6800.6  210.68  6920.2   204.5
  7351.9  206.94  7958.5  215.33  8063.2  216.07    9121  234.78  9814.7  260.72
#Mann= 20 ,-1 , 0
 -1135.1     .11       0  -853.9     .17       0   445.6     .15       0
   559.9     .15       0   703.9     .11       0    1493     .11       0
  1747.9     .11       0  2523.7     .11       0  2711.1     .17       0
  2945.1     .11       0  3649.3     .11       0  3804.5     .17       0
  3968.6     .15       0  4965.6     .09       0  5058.3     .15       0
  5312.6     .17       0  6800.6     .15       0  7351.9     .17       0
  7958.5     .15       0  8063.2     .17       0
#XS Ineff= 1 ,-1
  5727.1    8500  221.28
Permanent Ineff=
       F
Bank Sta=4965.6,5058.3
XS Rating Curve= 0 ,0
Exp/Cntr=0.3,0.1

Type RM Length L Ch R = 1 ,420218  ,718,718,718
BEGIN DESCRIPTION:
WFSJ Main 417.0
END DESCRIPTION:
XS GIS Cut Line= 3
       3779574.3     10207561.34      3777897.25     10206483.23
      3771238.82     10202260.57
#Sta/Elev= 30
   292.8  273.23   507.2  280.22   658.5  279.34   945.8  267.81    1064  264.68
  1100.3  258.81  1121.4  263.93  1260.8  271.07  1708.6  284.61  2381.4   258.7
  2631.9     244  2690.5  239.85    2843  252.72  3086.7   246.7  3276.5   238.3
  3299.5  237.48  4107.6   209.7  4397.9  204.15  4577.5   198.8  4911.3  206.14
  4974.8   204.4    4999  198.25    5033  205.81  5636.7  207.25  5751.8  216.31
  5918.7  220.22  8054.6  214.91    9062  222.35  9426.1  226.39   10171   246.3
#Mann= 14 ,-1 , 0
   292.8     .17       0   945.8     .11       0  2381.4     .17       0
  2631.9     .11       0  2690.5     .17       0    2843     .11       0
  3086.7     .17       0  3276.5     .11       0  3299.5     .17       0
  4107.6     .11       0  4397.9     .15       0  4911.3     .09       0
    5033     .15       0  5636.7     .17       0
#XS Ineff= 1 ,-1
  6425.3    8660   220.1
Permanent Ineff=
       F
Bank Sta=4911.3,5033
XS Rating Curve= 0 ,0
Exp/Cntr=0.3,0.1

Type RM Length L Ch R = 1 ,419500  ,500,500,500
BEGIN DESCRIPTION:
WFSJ Main 416.0
END DESCRIPTION:
XS GIS Cut Line= 3
       3778116.9     10205944.19       3775681.1     10204526.63
      3771448.45     10201651.63
#Sta/Elev= 30
  2531.3  269.65  2736.6  265.86  3397.3  233.75  3639.9  233.59  3931.7  217.89
  4069.4  213.11    4238  208.29  4418.5  204.89  4641.9  201.42  4753.6  202.35
  4867.4  199.37  4959.9  204.05    4999  198.87  5033.9  203.89  5327.6  199.84
  5450.2  205.27  5579.5  200.71  5653.9  207.34  5780.2  216.41  6175.5  219.02
  6938.8  214.77  7055.1  212.74  7271.1  217.28  7552.5   210.4  7989.7  218.35
  8178.3  207.08  8214.2   212.2  8567.5  220.12  9711.2  221.79 10466.3  244.83
#Mann= 14 ,-1 , 0
  2531.3     .17       0  2736.6     .11       0  3639.9     .17       0
  3931.7     .11       0  4069.4     .17       0    4238     .11       0
  4418.5     .17       0  4641.9     .11       0  4753.6     .15       0
  4959.9     .09       0  5033.9     .15       0  5653.9     .17       0
  6938.8     .15       0  7055.1     .17       0
#XS Ineff= 1 ,-1
  6465.7    8565  219.64
Permanent Ineff=
       F
Bank Sta=4959.9,5033.9
XS Rating Curve= 0 ,0
Exp/Cntr=0.3,0.1

Type RM Length L Ch R = 1 ,419000  ,732,732,732
BEGIN DESCRIPTION:
WFSJ Main 415.0
END DESCRIPTION:
XS GIS Cut Line= 3
      3778007.07     10205385.15      3776049.24     10204336.04
      3771418.49     10201471.93
#Sta/Elev= 30
  2778.8  270.79  3365.9  250.06  3709.9  227.75  3935.1  222.82  4267.1  203.01
  4364.6  200.12  4486.5  202.07  4596.3  202.18  4937.8  203.29    4999  198.32
 5050.35  203.64  5324.1  204.38  5360.7  198.83  5435.2  203.86  5781.5   220.1
  6007.2  208.11  6385.8  202.73  6396.8  202.49  6879.5  213.69  7074.5  202.42
  7303.8  203.04  7378.5  202.57  7405.1  203.56  7530.5  200.69  7685.3  210.38
  7823.6  217.35  8047.3  206.65  8367.6  222.51    9552  220.52 10444.9   244.4
#Mann= 16 ,-1 , 0
  2778.8     .17       0  3709.9     .11       0  4267.1     .17       0
  4364.6     .11       0  4486.5     .17       0  4596.3     .15       0
  4937.8     .09       0 5050.35     .15       0  5435.2     .17       0
  6385.8     .15       0  6396.8     .17       0  7303.8     .11       0
  7378.5     .17       0  7405.1     .15       0  7530.5     .11       0
  7685.3     .17       0
#XS Ineff= 1 ,-1
  5781.5    8420   220.1
Permanent Ineff=
       F
Bank Sta=4937.8,5050.35
XS Rating Curve= 0 ,0
Exp/Cntr=0.3,0.1

Type RM Length L Ch R = 1 ,418268  ,2469,2469,2469
BEGIN DESCRIPTION:
WFSJ Main 414.0
END DESCRIPTION:
XS GIS Cut Line= 3
      3778216.66     10204137.31      3775231.88     10203588.27
      3771378.62     10201402.09
#Sta/Elev= 30
  3298.1  263.45  3561.1  256.06  3678.3  252.76  3795.8  249.46  3916.1  244.82
  4015.8  234.98    4188  218.83  4414.4   213.3  4534.5  210.37  4589.1  209.04
  4908.2  200.77  4984.7  203.91    4999  198.82  5066.1  205.01  5650.8  199.52
  5747.3  203.26  5798.2  213.73  5879.5  217.85  6379.3  201.53  6997.5  200.98
  7047.9  200.87  7860.1  200.67  7967.2  203.17  7971.8  203.37  8117.3  213.86
  8306.2  204.62  8542.8  221.97  9641.8  219.39 10390.4   232.9 10763.2  245.49
#Mann= 18 ,-1 , 0
  3298.1     .11       0  3561.1     .17       0  3678.3     .11       0
  3795.8     .17       0  3916.1     .11       0  4015.8     .17       0
  4414.4     .15       0  4534.5     .11       0  4589.1     .15       0
  4984.7     .09       0  5066.1     .15       0  5650.8     .17       0
  6379.3     .15       0  6997.5     .17       0  7047.9     .15       0
  7860.1     .11       0  7967.2     .15       0  7971.8     .17       0
#XS Ineff= 1 ,-1
  5879.5    8570  217.85
Permanent Ineff=
       F
Bank Sta=4984.7,5066.1
XS Rating Curve= 0 ,0
Exp/Cntr=0.3,0.1

Type RM Length L Ch R = 1 ,415799  ,904,904,904
BEGIN DESCRIPTION:
Mapping XS 037cd638
END DESCRIPTION:
XS GIS Cut Line= 4
      3778256.67     10202120.81      3776769.21     10202450.25
       3774992.3     10203328.72      3771408.53     10201372.12
#Sta/Elev= 30
  2427.2  245.22  2989.3  220.37    3061  220.52  3467.3  203.56  3530.7  203.59
    3793  201.72  4706.8  201.32  4886.3  203.49  4914.3  199.82    4999   199.1
  5043.4  200.17  5088.3  204.14  5475.3  205.31  5893.2  201.68  6752.4  200.17
  7311.5  201.76  7416.7  205.22  7444.3  203.66  7629.3  205.17  7836.2   221.2
  7931.8  222.94  8086.7  222.73  8108.6  220.71  8255.7  217.71  8696.9  219.13
  8718.8   220.8  8969.3  219.67  9404.9  227.31  9426.7  229.33   10016  244.43
#Mann= 5 ,-1 , 0
  2427.2     .17       0  3530.7     .15       0  4886.3     .09       0
  5088.3     .15       0  7311.5     .17       0
Bank Sta=4886.3,5088.3
XS Rating Curve= 0 ,0
Exp/Cntr=0.3,0.1

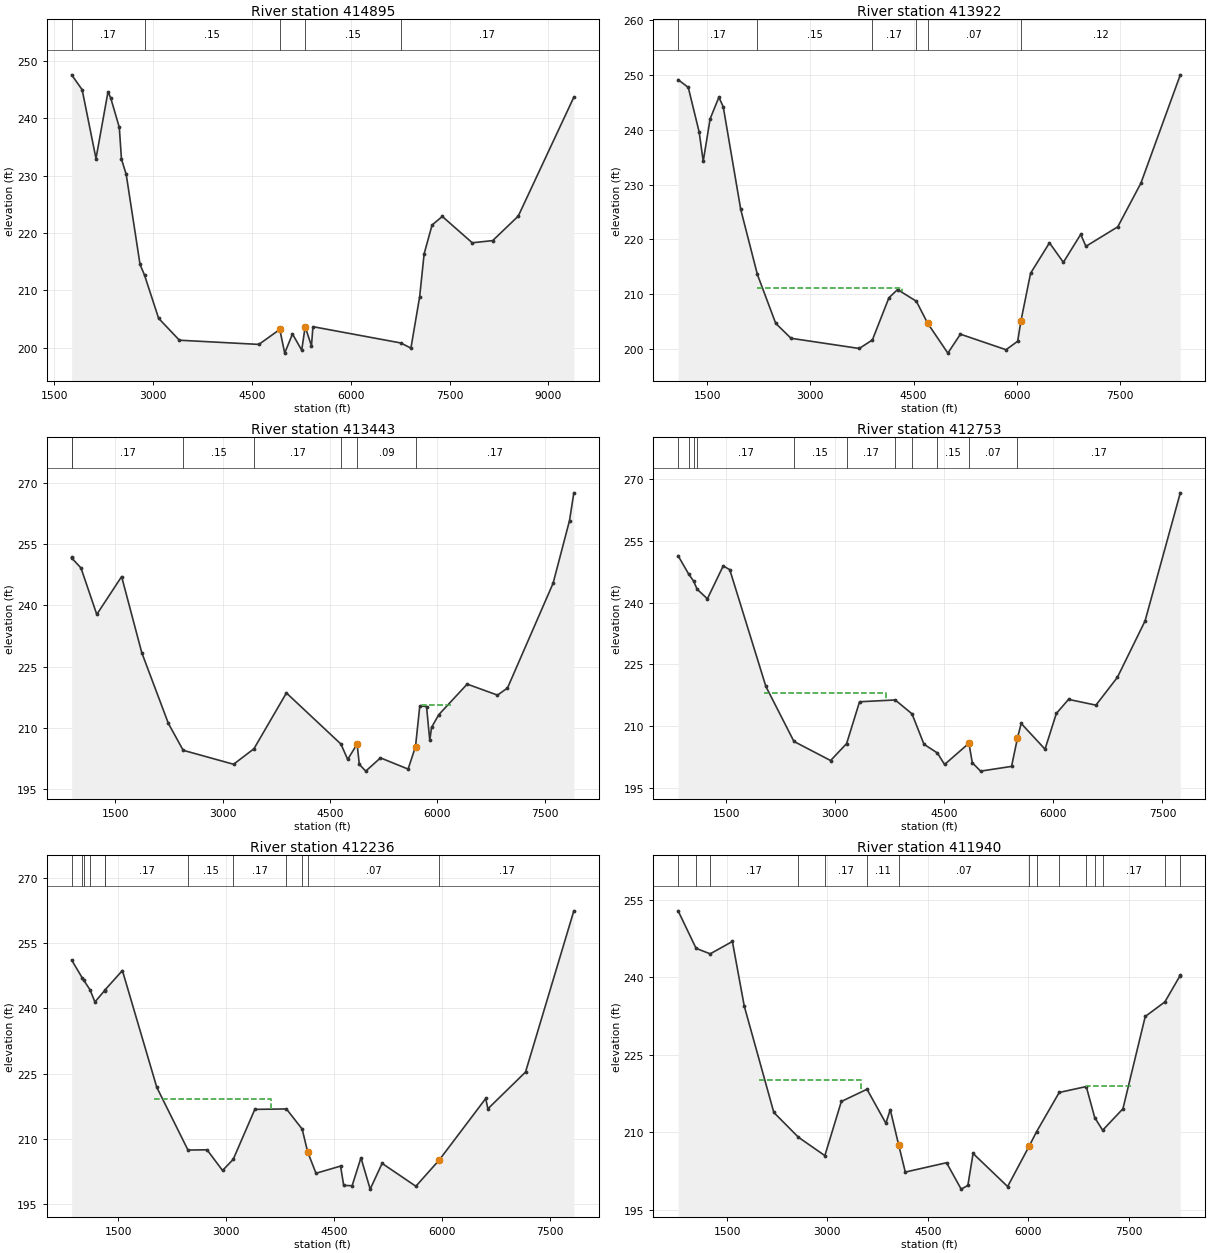
Type RM Length L Ch R = 1 ,414895  ,973,973,973
BEGIN DESCRIPTION:
WFSJ Main 413.0
END DESCRIPTION:
XS GIS Cut Line= 4
      3778246.65     10202011.01      3776729.28     10201561.79
      3774323.46     10202839.57      3771378.56     10201322.19
#Sta/Elev= 30
  1766.6  247.57    1926  244.97  2135.9  232.98  2318.1  244.61  2359.8  243.52
  2489.4  238.42  2522.6  232.88  2594.3  230.22  2804.3  214.52    2872  212.67
    3086  205.14  3401.2  201.32  4607.5  200.59  4924.6   203.2    4999  199.07
  5117.1  202.41  5257.1  199.58  5309.6  203.67  5405.3  200.33  5427.3  203.68
  6760.9  200.84    6914  199.94    7047  208.92  7114.4  216.37  7235.2   221.4
  7390.4  222.89  7844.6   218.3  8154.9  218.68  8542.7  222.95    9386  243.68
#Mann= 5 ,-1 , 0
  1766.6     .17       0    2872     .15       0  4924.6     .09       0
  5309.6     .15       0  6760.9     .17       0
Bank Sta=4924.6,5309.6
XS Rating Curve= 0 ,0
Exp/Cntr=0.3,0.1

Type RM Length L Ch R = 1 ,413922  ,479,479,479
BEGIN DESCRIPTION:
WFSJ Main 412.0
END DESCRIPTION:
XS GIS Cut Line= 5
      3778236.66      10201961.1      3776479.71      10201382.1
       3775511.4     10201541.83       3773494.9     10202220.65
      3771398.57     10201182.46
#Sta/Elev= 30
  1078.8  249.17  1226.4  247.75  1385.3  239.57  1443.6  234.26  1544.1  242.02
  1671.2  245.96  1734.7  244.21  1988.9  225.47  2230.8   213.6  2497.2  204.68
  2719.6  201.95    3711  200.09  3901.9  201.64  4141.8  209.33  4267.7  210.85
  4541.3  208.71  4703.5  204.73    4999  199.24  5181.2   202.7  5844.7  199.86
  6013.6  201.41 6061.07  205.12  6201.1  213.82  6475.7  219.38  6677.6  215.82
  6929.8  220.92  7005.3  218.74    7468   222.3  7804.4  230.27  8377.1  250.05
#Mann= 6 ,-1 , 0
  1078.8     .17       0  2230.8     .15       0  3901.9     .17       0
  4541.3     .12       0  4703.5     .07       0 6061.07     .12       0
#XS Ineff= 1 ,-1
    2230  4330.7  211.05
Permanent Ineff=
       F
Bank Sta=4703.5,6061.07
XS Rating Curve= 0 ,0
Exp/Cntr=0.3,0.1

Type RM Length L Ch R = 1 ,413443  ,690,690,690
BEGIN DESCRIPTION:
WFSJ Main 411.0
END DESCRIPTION:
XS GIS Cut Line= 4
      3778246.63      10201901.2      3776176.97     10201123.37
      3774133.79     10201471.95      3771588.21     10200493.64
#Sta/Elev= 30
   893.3  251.76   900.4  251.51  1023.6  249.18  1244.1  237.79  1590.9  247.07
  1871.9  228.43  2243.6  211.06  2450.2  204.47  3154.1  201.04  3438.3  204.85
  3891.5  218.53    4653  205.99  4746.8  202.23  4878.7  206.01  4909.2  201.02
    4999  199.36  5204.8  202.61  5590.5  199.86  5693.7  205.38  5753.7  215.38
  5847.6  215.19    5893  206.89  5917.7  210.09    6019  213.21    6415   220.7
  6838.3     218  6977.6  219.74  7614.2  245.42  7843.6   260.8  7904.1  267.61
#Mann= 7 ,-1 , 0
   893.3     .11       0   900.4     .17       0  2450.2     .15       0
  3438.3     .17       0    4653     .15       0  4878.7     .09       0
  5693.7     .17       0
#XS Ineff= 2 ,-1
    2025  3891.5  218.53  5778.4    6190  215.54
Permanent Ineff=
       F       F
Bank Sta=4878.7,5693.7
XS Rating Curve= 0 ,0
Exp/Cntr=0.3,0.1

Type RM Length L Ch R = 1 ,412753  ,517,517,517
BEGIN DESCRIPTION:
WFSJ Main 410.0
END DESCRIPTION:
XS GIS Cut Line= 4
      3778236.68     10201841.31      3775370.68     10200737.23
      3774443.25     10200793.13      3771588.19     10200244.08
#Sta/Elev= 30
   838.2  251.36   984.2  246.89  1050.4  245.23    1100  243.24  1240.5  240.91
  1458.5   248.9  1548.9  247.97  2045.7  219.64  2431.2  206.31  2935.6  201.67
  3156.1  205.79  3333.9  215.93  3824.3  216.37  4055.4     213  4220.3  205.62
  4404.7   203.5  4503.4  200.71  4838.6  205.87  4884.9  201.13    4999   199.1
  5424.6  200.25    5506  207.11  5556.9  210.67    5885  204.43  6040.8  213.09
  6208.7  216.51  6585.5  215.11  6880.8  221.87  7260.8  235.53    7746  266.63
#Mann= 11 ,-1 , 0
   838.2     .11       0   984.2     .17       0  1050.4     .11       0
    1100     .17       0  2431.2     .15       0  3156.1     .17       0
  3824.3     .11       0  4055.4     .17       0  4404.7     .15       0
  4838.6     .07       0    5506     .17       0
#XS Ineff= 1 ,-1
    2025  3691.5  217.98
Permanent Ineff=
       F
Bank Sta=4838.6,5506
XS Rating Curve= 0 ,0
Exp/Cntr=0.3,0.1

Type RM Length L Ch R = 1 ,412236  ,296,296,296
BEGIN DESCRIPTION:
Mapping XS b5999d83
END DESCRIPTION:
XS GIS Cut Line= 4
      3778229.64     10201828.27      3775214.01     10200614.73
      3773917.14     10200052.23      3771604.63      10200156.4
#Sta/Elev= 30
   850.2  251.07   997.2  246.98  1015.8  246.49  1105.3  244.25  1173.8  241.44
  1306.8  244.04  1314.9  244.24  1555.4  248.67  2033.6  221.84  2466.8  207.45
  2732.1  207.51  2947.1  202.76  3095.4  205.31  3395.7  216.79  3834.8  216.89
  4053.7  212.27  4129.4  207.06    4246  202.12  4587.2  203.77  4630.8  199.34
    4748  199.26  4870.6  205.67    4999  198.48  5164.9  204.39  5633.9  199.14
  5959.8  205.19  6604.8  219.29  6634.9  216.92  7157.9  225.36  7829.3  262.37
#Mann= 12 ,-1 , 0
   850.2     .11       0   997.2     .17       0  1015.8     .11       0
  1105.3     .17       0  1306.8     .11       0  1314.9     .17       0
  2466.8     .15       0  3095.4     .17       0  3834.8     .11       0
  4053.7     .17       0  4129.4     .07       0  5959.8     .17       0
#XS Ineff= 1 ,-1
    1990  3616.1  219.06
Permanent Ineff=
       F
Bank Sta=4129.4,5959.8
XS Rating Curve= 0 ,0
Exp/Cntr=0.3,0.1

Type RM Length L Ch R = 1 ,411940  ,150,150,150
BEGIN DESCRIPTION:
WFSJ Main 409.0
END DESCRIPTION:
XS GIS Cut Line= 5
      3778241.77     10201809.17      3775005.68     10200453.27
      3774359.85     10199875.15      3773073.39     10198510.56
      3771891.99     10198089.01
#Sta/Elev= 30
   768.8  252.82  1037.4  245.56  1248.1   244.5  1579.9  246.89  1757.2  234.39
  2199.4   213.8  2566.9  209.01  2961.9  205.45  3208.2  215.93  3591.4   218.3
  3873.9  211.71  3939.1  214.36  4065.1  207.52    4164  202.27  4780.4  204.08
    4999  198.97  5098.9  199.68    5177  205.87  5693.3  199.47 6017.99  207.36
    6125  210.06  6463.8  217.67  6868.5  218.82    6995  212.81  7113.4  210.36
  7416.4  214.52    7750  232.38  8043.8   235.2  8272.9  240.33    8274  240.26
#Mann= 15 ,-1 , 0
   768.8     .11       0  1037.4     .17       0  1248.1     .17       0
  2566.9     .15       0  2961.9     .17       0  3591.4     .11       0
  4065.1     .07       0 6017.99     .15       0    6125     .17       0
  6463.8     .17       0  6868.5     .17       0    6995     .11       0
  7113.4     .17       0  8043.8     .17       0  8272.9     .11       0
#XS Ineff= 2 ,-1
    1985  3496.9  220.05  6867.8    7530  218.85
Permanent Ineff=
       F       F
Bank Sta=4065.1,6017.99
XS Rating Curve= 0 ,0
Exp/Cntr=0.3,0.1

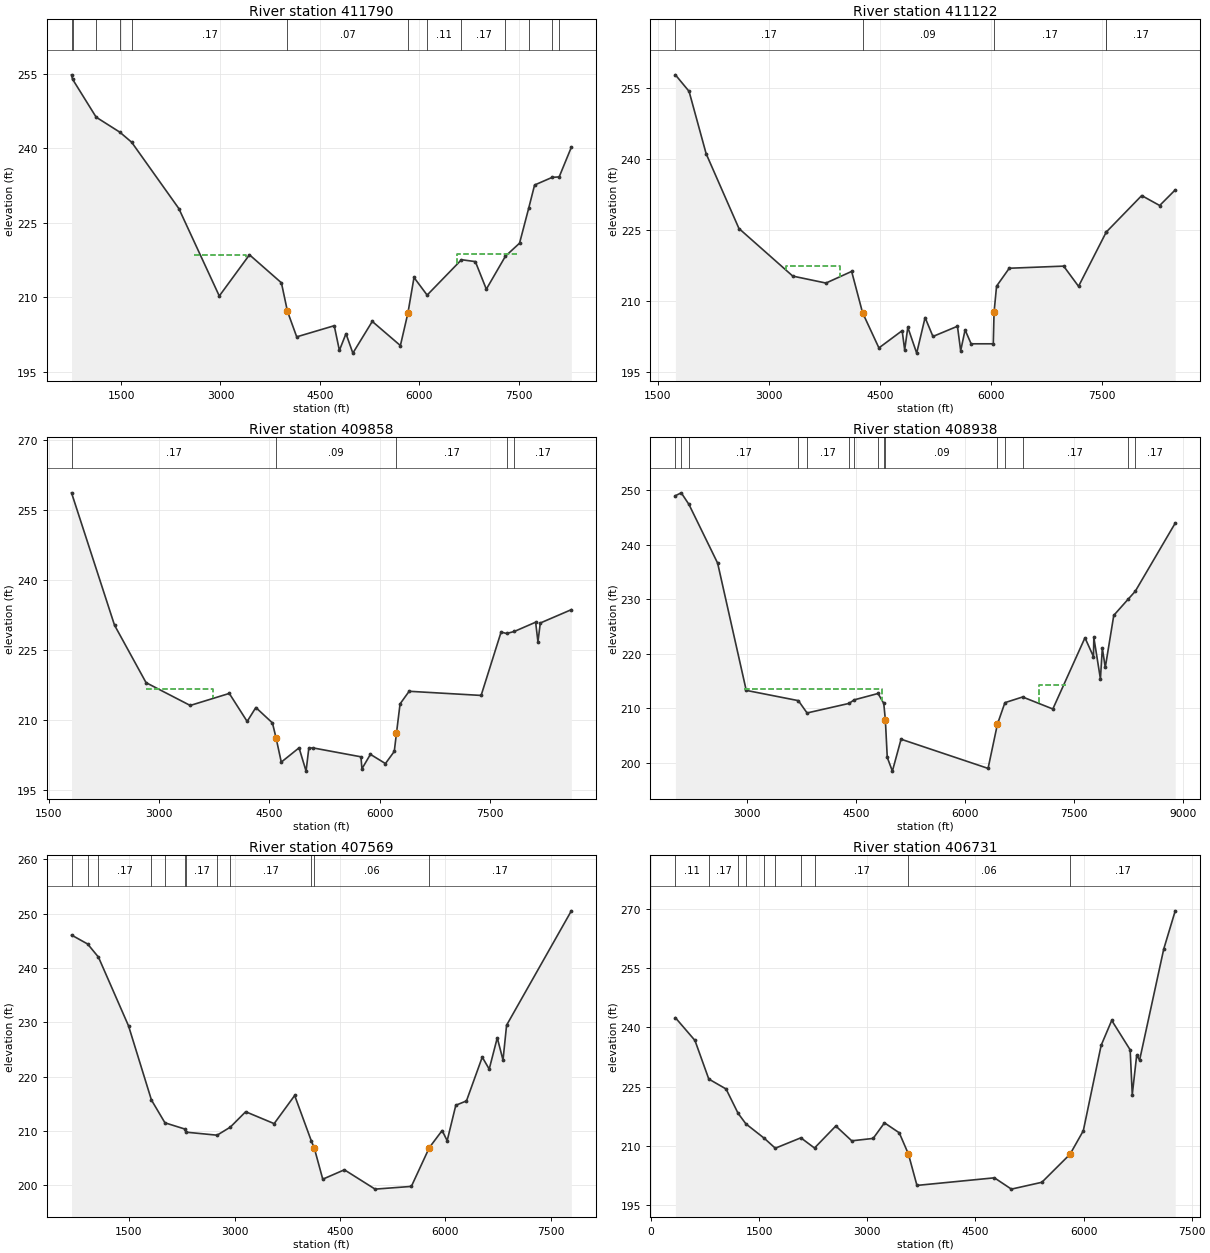
Type RM Length L Ch R = 1 ,411790  ,668,668,668
BEGIN DESCRIPTION:
Mapping XS c1504bff
END DESCRIPTION:
XS GIS Cut Line= 6
      3778255.72     10201781.43      3777177.55     10201010.56
      3775047.35     10200297.02      3773870.26     10199234.52
      3773255.68     10198448.06      3771937.97     10198010.56
#Sta/Elev= 30
   752.5  254.74   767.1  253.88  1124.3  246.23  1481.4  243.22  1659.9   241.2
  2372.3  227.87  2982.9   210.3  3438.5  218.58  3920.6  212.95  4011.7  207.22
  4151.5  202.09    4718  204.33  4795.8  199.37  4895.2  202.73    4999  198.82
    5292  205.19  5716.4  200.34    5830  206.87    5922  214.02  6120.1  210.48
  6638.6  217.59  6848.1  217.21  7013.7  211.67  7302.7  218.31  7515.2  220.91
  7655.4  228.05  7742.2   232.6  8008.2  234.14  8113.3  234.23  8297.2   240.2
#Mann= 13 ,-1 , 0
   752.5     .11       0   767.1     .17       0  1124.3     .17       0
  1481.4     .17       0  1659.9     .17       0  4011.7     .07       0
    5830     .15       0  6120.1     .11       0  6638.6     .17       0
  7302.7     .11       0  7655.4     .11       0  8008.2     .17       0
  8113.3     .11       0
#XS Ineff= 2 ,-1
    2600  3393.5  218.58  6570.5    7470  218.68
Permanent Ineff=
       F       F
Bank Sta=4011.7,5830
XS Rating Curve= 0 ,0
Exp/Cntr=0.3,0.1

Type RM Length L Ch R = 1 ,411122  ,1264,1264,1264
BEGIN DESCRIPTION:
WFSJ Main 408.0
END DESCRIPTION:
XS GIS Cut Line= 4
       3778035.2     10200776.19      3775201.86     10199595.63
      3774772.93     10199158.93      3772083.76     10197678.94
#Sta/Elev= 30
    1740  257.85  1924.5  254.36  2155.3  241.17  2598.3  225.37  3325.3  215.31
  3773.8  213.84  4120.5   216.3 4267.64  207.59  4488.8  200.13  4802.9  203.78
  4836.7  199.69  4879.2  204.49    4999  199.03  5112.5  206.55  5218.6  202.55
  5549.6  204.71  5593.2  199.53  5652.8  203.94  5734.2     201  6033.5     201
 6043.94  207.67    6078  213.19  6249.2  216.97  6984.2  217.42    7185  213.15
  7559.5  224.62  7559.6  224.62  8038.2  232.33    8281  230.23  8491.1  233.53
#Mann= 5 ,-1 , 0
    1740     .17       0 4267.64     .09       0 6043.94     .17       0
  7559.5     .11       0  7559.6     .17       0
#XS Ineff= 2 ,-1
    3230    3958  217.48  6984.2    7360  217.42
Permanent Ineff=
       F       F
Bank Sta=4267.64,6043.94
XS Rating Curve= 0 ,0
Exp/Cntr=0.3,0.1

Type RM Length L Ch R = 1 ,409858  ,920,920,920
BEGIN DESCRIPTION:
WFSJ Main 407.0
END DESCRIPTION:
XS GIS Cut Line= 3
      3778229.63     10200394.24      3776326.86     10199005.36
      3772194.92      10197387.3
#Sta/Elev= 30
  1811.3  258.66  2395.4  230.29  2824.2  217.96  3424.3  213.07  3955.3  215.65
  4198.2  209.64  4316.3  212.63  4541.9  209.32  4591.1  206.11    4662  200.92
  4903.6  203.98    4999  198.99  5035.9  203.88  5089.6  203.98  5744.7  202.06
  5758.2  199.49  5873.5  202.59  6077.6  200.61  6197.8  203.22  6227.9  207.18
  6276.5  213.41  6399.8  216.11  7378.1  215.22  7649.5  228.81  7724.1   228.5
  7828.5  228.93  8118.8  230.92  8150.3  226.73  8182.5  230.75  8604.5  233.61
#Mann= 5 ,-1 , 0
  1811.3     .17       0  4591.1     .09       0  6227.9     .17       0
  7724.1     .11       0  7828.5     .17       0
#XS Ineff= 1 ,-1
    2830  3732.5  216.57
Permanent Ineff=
       F
Bank Sta=4591.1,6227.9
XS Rating Curve= 0 ,0
Exp/Cntr=0.3,0.1

Type RM Length L Ch R = 1 ,408938  ,1369,1369,1369
BEGIN DESCRIPTION:
WFSJ Main 406.0
END DESCRIPTION:
XS GIS Cut Line= 4
      3778764.35      10199012.3      3777479.64     10198442.86
      3775424.08      10197762.3      3772209.12     10196935.99
#Sta/Elev= 30
  2007.9  248.97  2088.3   249.5  2194.4  247.38  2590.1  236.61  2984.4  213.29
  3702.8  211.41  3822.7  209.15  4400.8   210.9  4472.1  211.55  4801.3  212.72
  4880.1   210.9  4901.9  207.95  4928.4     201    4999  198.49  5118.6  204.34
    6318  198.99    6447   207.1  6550.2  211.04  6794.3  212.08  7210.7  209.88
  7653.6  222.93  7770.7  219.48  7775.9  222.99  7866.7   215.4  7892.9  221.03
  7933.6  217.49  8050.7  227.04  8245.8  229.96  8346.7  231.45  8897.9  243.95
#Mann= 15 ,-1 , 0
  2007.9     .17       0  2088.3     .11       0  2194.4     .17       0
  3702.8     .15       0  3822.7     .17       0  4400.8     .15       0
  4472.1     .17       0  4801.3     .11       0  4880.1     .15       0
  4901.9     .09       0    6447     .17       0  6550.2     .11       0
  6794.3     .17       0  8245.8     .11       0  8346.7     .17       0
#XS Ineff= 2 ,-1
  7020.1    7390  214.23    2950  4858.2  213.61
Permanent Ineff=
       F       F
Bank Sta=4901.9,6447
XS Rating Curve= 0 ,0
Exp/Cntr=0.3,0.1

Type RM Length L Ch R = 1 ,407569  ,838,838,838
BEGIN DESCRIPTION:
WFSJ Main 405.0
END DESCRIPTION:
XS GIS Cut Line= 4
      3778840.72     10198915.04      3777806.03     10197581.74
       3775083.8     10196727.58      3772563.01     10196248.42
#Sta/Elev= 30
   682.9  246.06     912  244.41  1065.4     242  1493.3  229.34    1819  215.69
  2011.1  211.49  2292.7  210.35  2309.3  209.77  2752.9  209.21  2939.9  210.69
  3158.9  213.53  3563.7  211.34  3855.5  216.52  4092.8  208.14  4135.6  206.78
    4255  201.11  4562.5  202.84    4999  199.28  5514.7  199.78  5770.8  206.94
  5952.4  210.07  6023.7  208.19  6146.5  214.72  6298.1  215.52  6522.5  223.58
  6621.6  221.38  6736.2  227.14  6817.7  223.04  6868.6  229.46  7789.6  250.52
#Mann= 12 ,-1 , 0
   682.9     .17       0     912     .11       0  1065.4     .17       0
    1819     .11       0  2011.1     .17       0  2292.7     .11       0
  2309.3     .17       0  2752.9     .11       0  2939.9     .17       0
  4092.8     .15       0  4135.6     .06       0  5770.8     .17       0
#XS Ineff= 1 ,-1
    1700  3855.5  216.52
Permanent Ineff=
       F
Bank Sta=4135.6,5770.8
XS Rating Curve= 0 ,0
Exp/Cntr=0.3,0.1

Type RM Length L Ch R = 1 ,406731  ,731,731,731
BEGIN DESCRIPTION:
WFSJ Main 404.0
END DESCRIPTION:
XS GIS Cut Line= 4
      3779215.74     10198109.52      3775410.19     10196144.24
      3773743.53     10195533.13      3772882.62     10195366.51
#Sta/Elev= 30
   337.1  242.44   608.3  236.69   800.3  226.93  1040.1  224.41  1206.3  218.28
  1315.2  215.59  1573.1   211.9    1723  209.43  2077.7  212.06  2267.2  209.48
  2562.5  215.05  2784.1   211.3  3080.9  211.91    3238  215.85    3443  213.33
  3570.3  207.95  3688.6  200.02  4763.3  201.94    4999  199.08  5421.5  200.81
 5812.81  207.91  5996.6  213.84  6244.2  235.45    6391  241.76  6646.8  234.31
  6676.1  222.99  6737.2  232.92    6778  231.73  7112.8  259.82  7272.2  269.48
#Mann= 10 ,-1 , 0
   337.1     .11       0   800.3     .17       0  1206.3     .11       0
  1315.2     .17       0  1573.1     .11       0    1723     .17       0
  2077.7     .11       0  2267.2     .17       0  3570.3     .06       0
 5812.81     .17       0
#XS Ineff= 1 ,-1
    1210    3238  215.85
Permanent Ineff=
       F
Bank Sta=3570.3,5812.81
XS Rating Curve= 0 ,0
Exp/Cntr=0.3,0.1