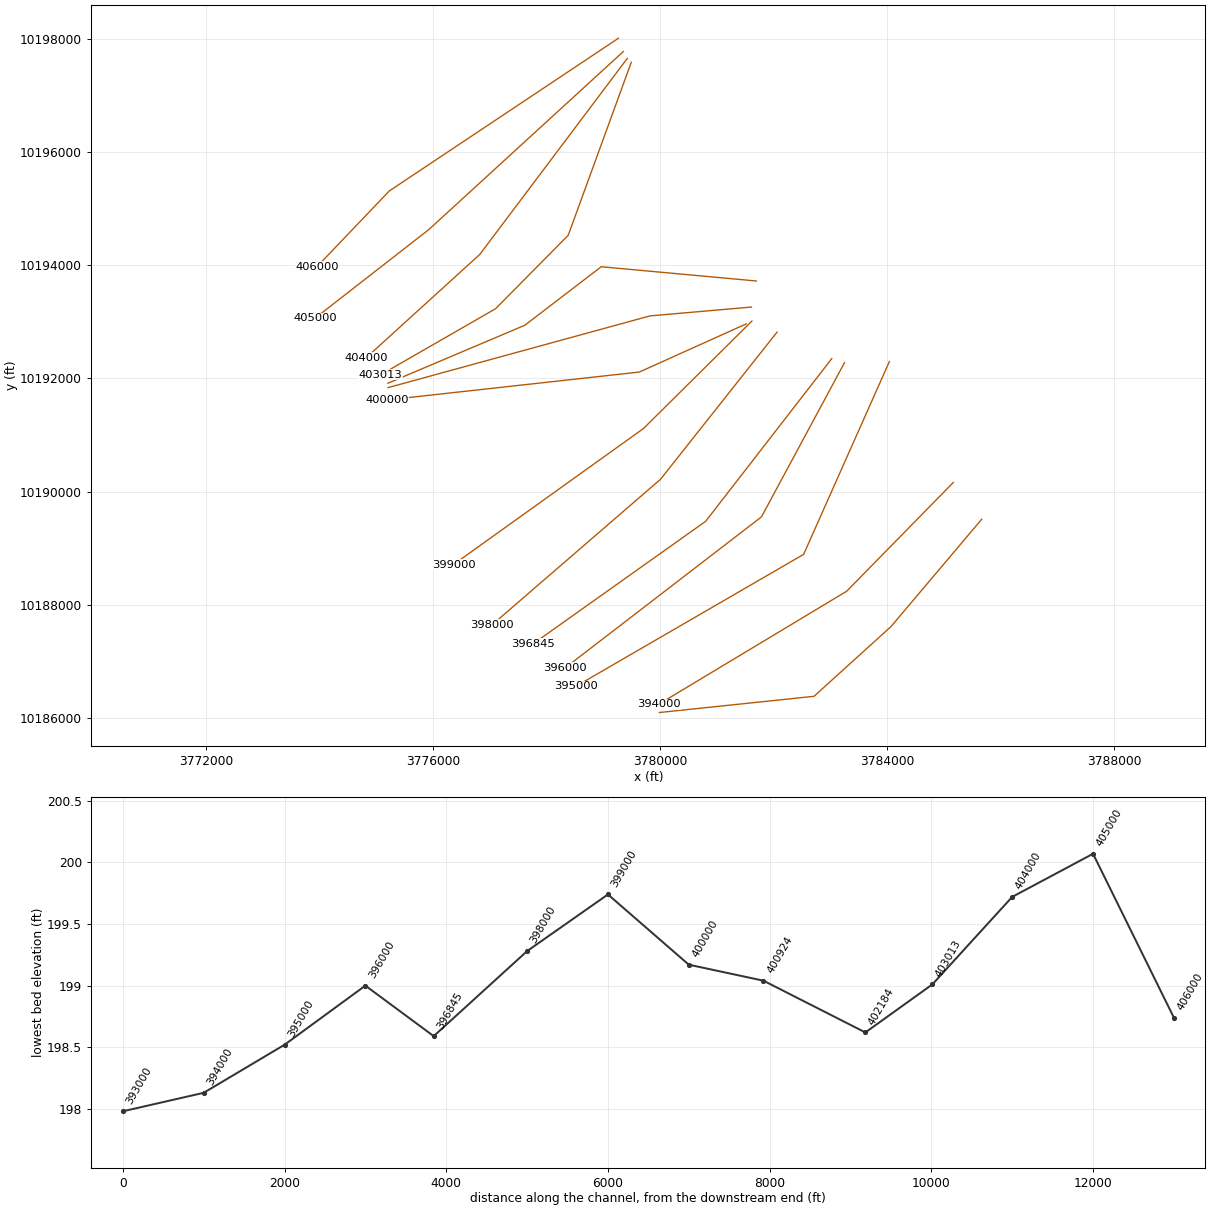
HEC-RAS study WFSJ Main.prj: WFSJ Main Base Level Engineering

--- WFSJ Main.g01 (geometry) --- (continued)

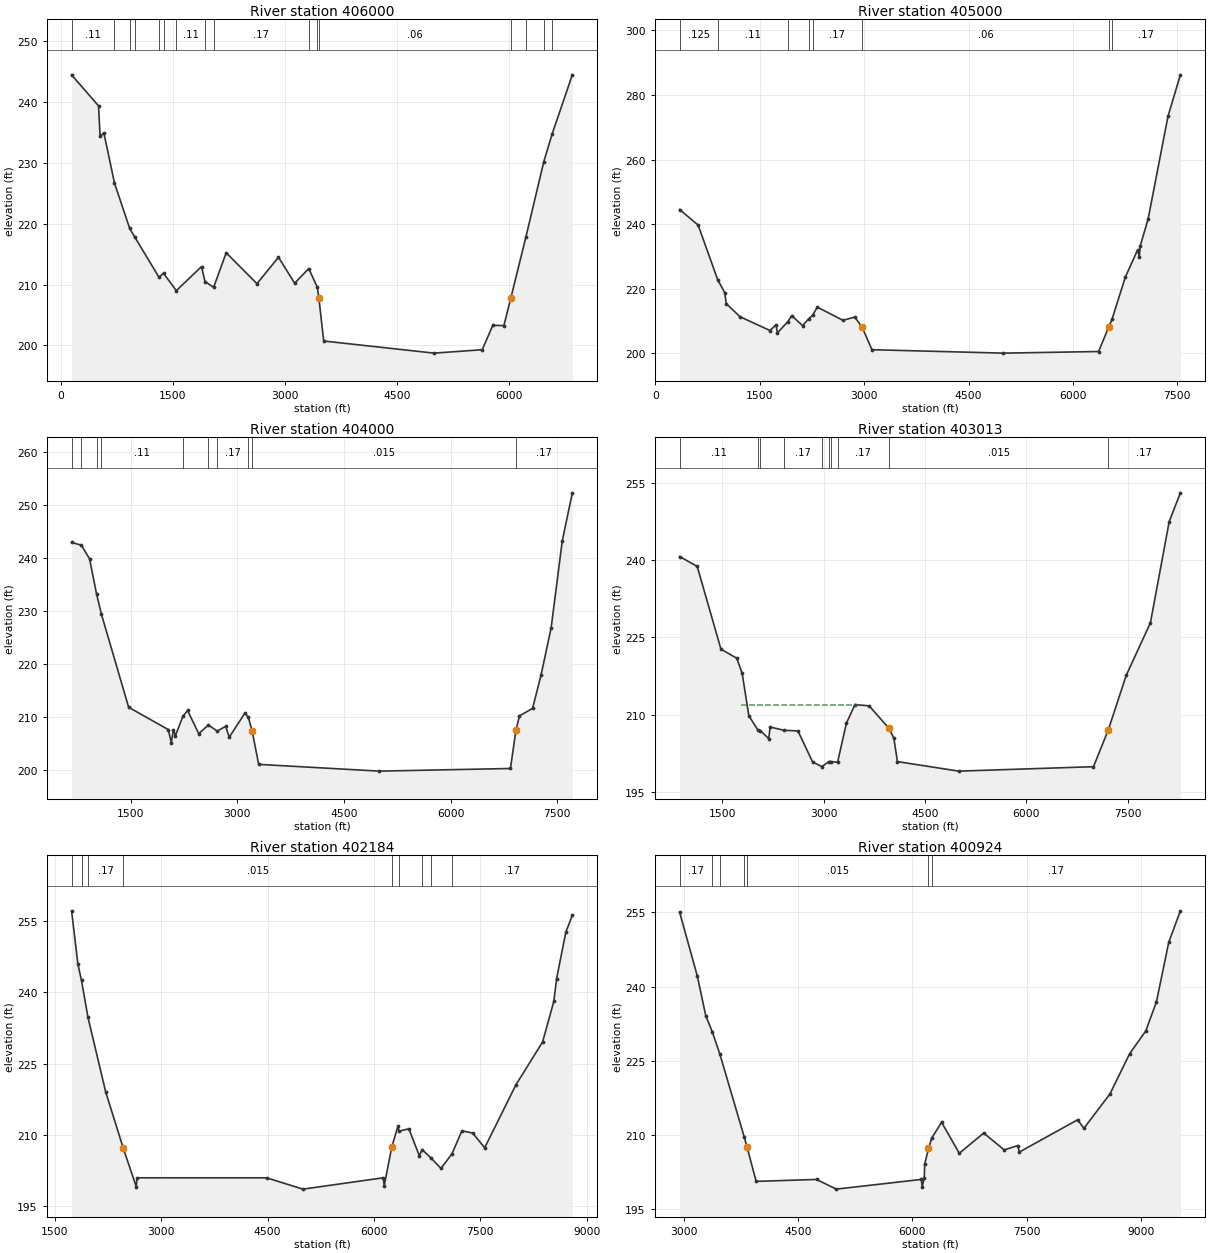
Type RM Length L Ch R = 1 ,406000  ,1000,1000,1000
BEGIN DESCRIPTION:
WFSJ Main 403.0
END DESCRIPTION:
XS GIS Cut Line= 3
      3779264.34     10198005.34      3775228.79     10195310.34
      3773952.32     10193971.12
#Sta/Elev= 30
   147.3  244.41     508  239.33     529  234.33   580.1  234.85   721.5  226.66
   924.9  219.21   993.3  217.78  1317.6  211.19  1377.7  211.84  1549.3     209
  1886.6  212.94  1933.1  210.49  2048.8  209.54    2217  215.21  2628.5  210.14
  2916.9  214.48  3133.1  210.22  3321.8  212.62  3437.5  209.53  3457.5  207.76
  3522.1  200.73    4999  198.74  5643.9   199.3  5785.4   203.3  5933.9  203.26
  6025.7  207.73  6230.2  217.88    6468  230.17  6581.3  234.78  6850.1  244.42
#Mann= 16 ,-1 , 0
   147.3     .11       0   721.5     .17       0   924.9     .11       0
   993.3     .17       0  1317.6     .11       0  1377.7     .17       0
  1549.3     .11       0  1933.1     .11       0  2048.8     .17       0
  3321.8     .11       0  3437.5     .11       0  3457.5     .06       0
  6025.7     .17       0  6230.2     .11       0    6468     .11       0
  6581.3     .17       0
#XS Ineff= 2 ,-1
    1030    2217  215.21    2218  2916.9  214.48
Permanent Ineff=
       F       F
Bank Sta=3457.5,6025.7
XS Rating Curve= 0 ,0
Exp/Cntr=0.3,0.1

Type RM Length L Ch R = 1 ,405000  ,1000,1000,1000
BEGIN DESCRIPTION:
WFSJ Main 402.0
END DESCRIPTION:
XS GIS Cut Line= 3
       3779352.9     10197772.71      3775924.02     10194627.07
      3773917.86     10193061.07
#Sta/Elev= 30
   346.8  244.54   613.2  239.71   894.4  222.77   995.5   218.8  1017.1   215.4
    1215  211.34  1646.6  207.06  1731.7  208.84  1752.7  206.35  1904.3  209.85
    1958  211.69    2114  208.59  2205.1  210.75  2257.5  211.76  2326.1  214.32
  2694.2  210.24  2864.2  211.23  2970.4   208.1  3111.6  201.13    4999  200.07
  6369.2  200.57 6513.49  208.06  6562.4  210.55  6754.5  223.64  6932.7  232.14
  6953.5  229.73  6967.9  233.24  7081.9  241.65  7367.4  273.44    7545  286.24
#Mann= 8 ,-1 , 0
   346.8    .125       0   894.4     .11       0  1904.3     .17       0
  2205.1     .11       0  2257.5     .17       0  2970.4     .06       0
 6513.49     .15       0  6562.4     .17       0
#XS Ineff= 1 ,-1
    1000  2326.1  214.32
Permanent Ineff=
       F
Bank Sta=2970.4,6513.49
XS Rating Curve= 0 ,0
Exp/Cntr=0.3,0.1

Type RM Length L Ch R = 1 ,404000  ,987,987,987
BEGIN DESCRIPTION:
WFSJ Main 401.0
END DESCRIPTION:
XS GIS Cut Line= 3
      3779422.34     10197651.18      3776822.92       10194189.
      3774817.87     10192361.09
#Sta/Elev= 30
   670.6     243   807.4  242.46   923.3   239.9  1022.2  233.21  1091.3  229.36
  1473.2   211.8  2031.5  207.57  2073.2  205.09  2102.3   207.5  2131.5  206.45
    2236  210.08  2302.3  211.19  2458.9   206.8  2594.4  208.44    2719   207.3
  2837.6   208.2  2887.6  206.14  3109.2  210.72  3156.5  209.88  3209.2  207.36
  3302.1     201    4999  199.72  6842.7  200.22  6920.4   207.5  6969.7  210.17
  7154.1  211.59  7274.4  217.97  7415.6  226.87  7571.7   243.3  7713.2  252.37
#Mann= 10 ,-1 , 0
   670.6    .125       0   807.4     .11       0  1022.2    .125       0
  1091.3     .11       0    2236     .17       0  2594.4     .11       0
    2719     .17       0  3156.5     .11       0  3209.2    .015       0
  6920.4     .17       0
#XS Ineff= 1 ,-1
    1500  3109.2  210.72
Permanent Ineff=
       F
Bank Sta=3209.2,6920.4
XS Rating Curve= 0 ,0
Exp/Cntr=0.3,0.1

Type RM Length L Ch R = 1 ,403013  ,829,829,829
BEGIN DESCRIPTION:
WFSJ Main 400.0
END DESCRIPTION:
XS GIS Cut Line= 4
      3779491.78     10197581.72      3778380.68     10194526.19
      3777100.23     10193229.04      3775073.41     10192060.92
#Sta/Elev= 30
   867.1   240.7  1127.9  238.76  1479.1   222.7  1713.1  220.94  1793.5  217.98
  1891.4   209.8  2021.6  207.07  2061.2  206.89  2187.2  205.32  2206.6  207.58
  2410.4  206.95  2618.9  206.81  2836.3  200.78  2973.6  199.89  3079.6  200.88
  3106.3  200.87  3205.7  200.73  3336.4  208.33  3463.5  211.94  3672.4  211.69
  3967.6  207.31  4038.7   205.4  4091.9  200.86    4999  199.01  6994.1  199.87
  7213.9  207.04  7478.9  217.62  7836.7  227.81  8114.7  247.46  8280.4  253.07
#Mann= 10 ,-1 , 0
   867.1     .11       0  2021.6     .17       0  2061.2     .11       0
  2410.4     .17       0  2973.6     .11       0  3079.6     .17       0
  3106.3     .11       0  3205.7     .17       0  3967.6    .015       0
  7213.9     .17       0
#XS Ineff= 1 ,-1
    1770  3538.6  211.91
Permanent Ineff=
       F
Bank Sta=3967.6,7213.9
XS Rating Curve= 0 ,0
Exp/Cntr=0.3,0.1

Type RM Length L Ch R = 1 ,402184  ,1260,1260,1260
BEGIN DESCRIPTION:
WFSJ Main 399.0
END DESCRIPTION:
XS GIS Cut Line= 4
      3781696.65      10193718.9      3778962.28     10193970.63
      3777616.79     10192937.65       3775203.6     10191913.34
#Sta/Elev= 30
  1733.9   257.1  1823.1  245.89  1873.9  242.47    1965  234.73  2214.7  219.06
  2463.7  207.19  2646.5  199.12  2656.6     201  4483.6     201    4999  198.62
  6130.1     201  6144.6  199.37    6251  207.51  6338.5  211.88  6352.7  210.79
  6491.4   211.3  6638.8  205.66  6679.3  206.91  6802.4  205.18  6944.4  202.98
  7099.6  206.03  7239.6  210.87  7391.7  210.41  7561.1  207.31  8001.4  220.53
    8378  229.54  8536.3  238.06  8575.8  242.86  8706.2  252.63  8797.7  256.14
#Mann= 9 ,-1 , 0
  1733.9     .17       0  1873.9     .11       0    1965     .17       0
  2463.7    .015       0    6251     .11       0  6352.7     .17       0
  6679.3     .11       0  6802.4     .15       0  7099.6     .17       0
#XS Ineff= 1 ,-1
  6338.5    7800   211.8
Permanent Ineff=
       F
Bank Sta=2463.7,6251
XS Rating Curve= 0 ,0
Exp/Cntr=0.3,0.1

Type RM Length L Ch R = 1 ,400924  ,924,924,924
BEGIN DESCRIPTION:
WFSJ Main 398.0
END DESCRIPTION:
XS GIS Cut Line= 3
      3781609.84     10193258.83      3779821.65     10193102.58
      3775205.15     10191835.64
#Sta/Elev= 30
  2939.7  255.06  3172.6  242.12    3283  234.14  3369.1  230.85  3467.9  226.39
  3787.2  209.68  3825.1   207.6  3945.5  200.61  4739.3     201    4999  199.04
  6116.1     201  6128.2  199.54  6155.7  201.33  6160.9  204.07  6211.1  207.26
  6255.5  209.42  6383.2  212.55  6615.8  206.29    6937  210.38  7206.6  206.97
  7382.9  207.84  7406.6  206.55    8171  213.06    8254  211.34  8596.2  218.29
  8855.4  226.44  9067.4  231.04    9208  236.97  9368.9  248.96  9521.9  255.33
#Mann= 7 ,-1 , 0
  2939.7     .17       0  3369.1     .11       0  3467.9     .17       0
  3787.2     .11       0  3825.1    .015       0  6211.1     .11       0
  6255.5     .17       0
#XS Ineff= 1 ,-1
  6383.2    8400  212.55
Permanent Ineff=
       F
Bank Sta=3825.1,6211.1
XS Rating Curve= 0 ,0
Exp/Cntr=0.3,0.1

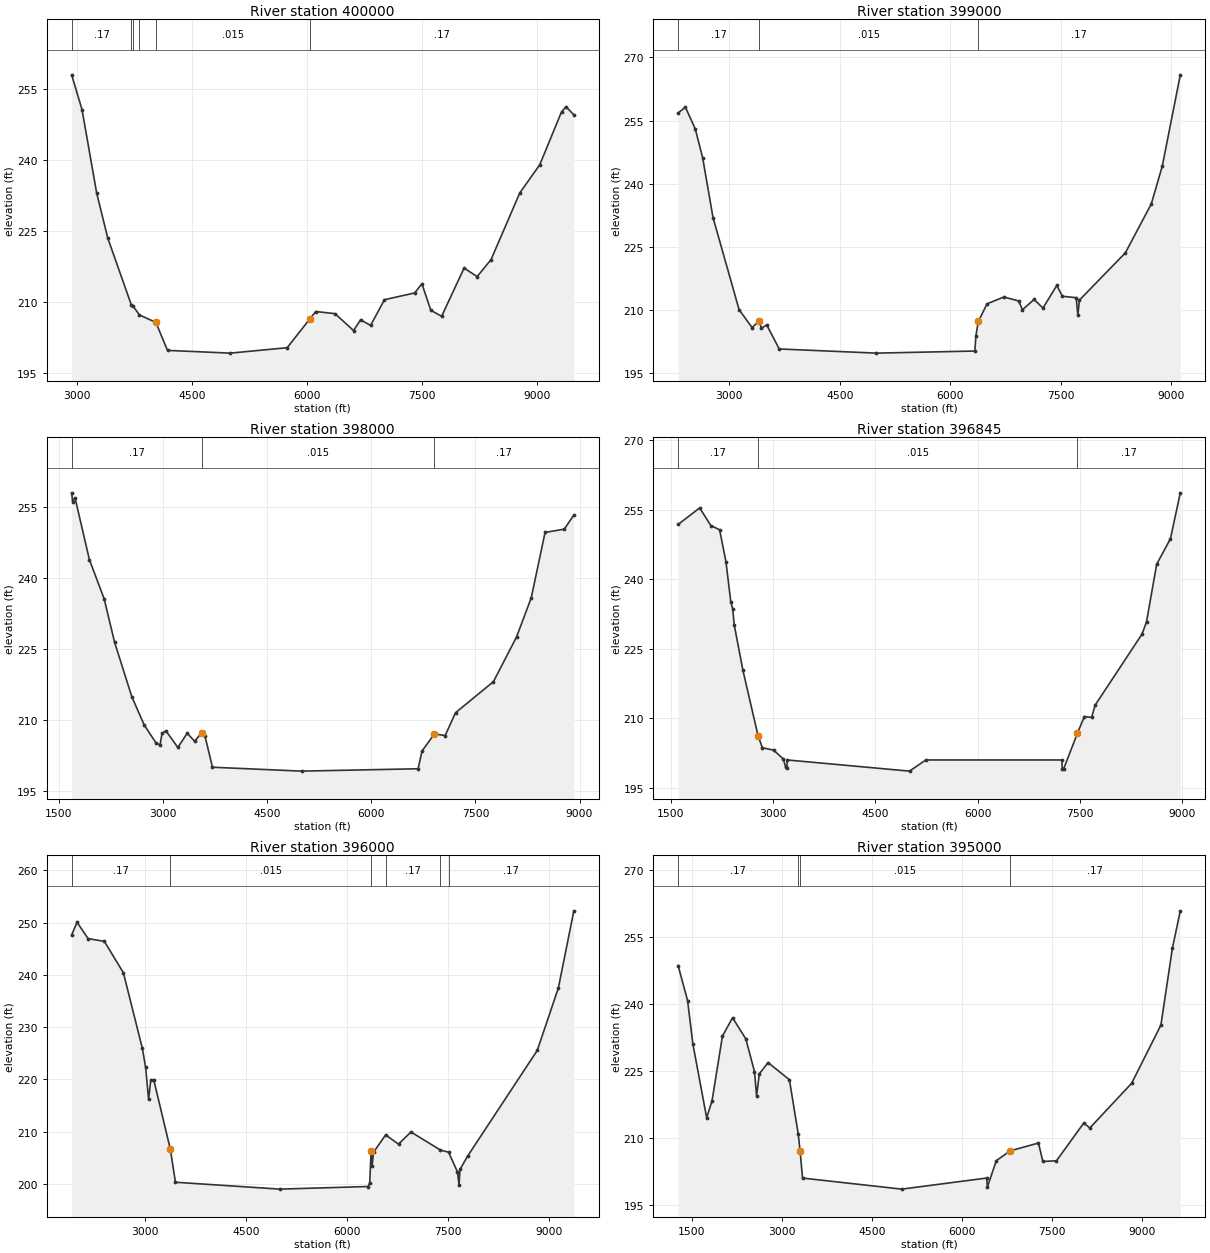
Type RM Length L Ch R = 1 ,400000  ,1000,1000,1000
BEGIN DESCRIPTION:
WFSJ Main 397.0
END DESCRIPTION:
XS GIS Cut Line= 3
      3781517.89     10192961.09       3779633.7     10192110.71
      3775186.19      10191618.2
#Sta/Elev= 30
  2932.8  258.08  3068.3  250.69  3258.8  233.05    3403  223.54    3710  209.39
  3730.1  209.16  3816.5  207.26    4030  205.66  4181.4  199.75    4999  199.17
  5740.3  200.32  6032.1  206.34  6112.6  207.98  6364.1  207.52  6605.6  203.94
  6696.2  206.23    6827  205.03  7008.1  210.48  7399.9   211.9  7495.6  213.84
  7611.7  208.24  7752.6  206.96  8044.9  217.18  8215.4  215.37  8396.5  218.98
  8770.5  233.08  9030.3  239.03  9314.7  250.26  9372.4  251.32  9474.7  249.62
#Mann= 6 ,-1 , 0
  2932.8     .17       0    3710     .11       0  3730.1     .17       0
  3816.5     .11       0    4030    .015       0  6032.1     .17       0
#XS Ineff= 1 ,-1
  7495.6    8000  213.84
Permanent Ineff=
       F
Bank Sta=4030,6032.1
XS Rating Curve= 0 ,0
Exp/Cntr=0.3,0.1

Type RM Length L Ch R = 1 ,399000  ,1000,1000,1000
BEGIN DESCRIPTION:
WFSJ Main 396.0
END DESCRIPTION:
XS GIS Cut Line= 3
      3781617.86     10193011.08       3779707.2     10191113.42
      3776358.12     10188710.22
#Sta/Elev= 30
  2307.1   256.8  2406.1  258.19  2540.5  252.98  2639.5  246.21  2780.9  231.95
  3134.4  210.08  3311.2   205.8  3403.1  207.35  3438.5  205.63  3509.2  206.46
  3678.9  200.73    4999  199.74    6334  200.24  6348.7  203.91 6381.28  207.26
  6499.8  211.46  6728.2  213.08  6929.6  212.13  6979.9  210.04  7137.1  212.49
  7258.7  210.46  7445.3  215.81  7522.7  213.26  7709.4  212.91  7731.6  208.75
  7753.5  212.35  8376.1  223.56  8728.6   235.2  8877.2  244.16  9122.1  265.87
#Mann= 3 , 0 , 0
  2307.1     .17       0  3403.1    .015       0 6381.28     .17       0
#XS Ineff= 1 ,-1
  7445.3    8030  215.81
Permanent Ineff=
       F
Bank Sta=3403.1,6381.28
XS Rating Curve= 0 ,0
Exp/Cntr=0.3,0.1

Type RM Length L Ch R = 1 ,398000  ,1155,1155,1155
BEGIN DESCRIPTION:
WFSJ Main 395.0
END DESCRIPTION:
XS GIS Cut Line= 3
      3782061.23     10192816.12      3780005.71     10190215.34
      3777043.85     10187651.17
#Sta/Elev= 30
    1685  257.88  1698.2  256.03  1733.4  256.84  1940.2  243.83  2153.4  235.55
  2303.2  226.42  2552.5   214.9  2730.5  208.98    2902  205.17  2958.1   204.8
  2986.9  207.25    3043  207.76  3214.5  204.26  3349.2  207.26  3456.6  205.56
    3556  207.36  3605.6  206.64  3713.1   200.1    4999  199.28  6674.9  199.78
  6730.9  203.51  6908.6   207.1  7064.3  206.78  7213.4  211.57  7759.6  218.12
  8092.2  227.52  8304.7   235.8  8503.2  249.54    8780  250.23  8917.6  253.21
#Mann= 3 , 0 , 0
    1685     .17       0    3556    .015       0  6908.6     .17       0
Bank Sta=3556,6908.6
XS Rating Curve= 0 ,0
Exp/Cntr=0.3,0.1

Type RM Length L Ch R = 1 ,396845  ,845,845,845
BEGIN DESCRIPTION:
WFSJ Main 394.0
END DESCRIPTION:
XS GIS Cut Line= 3
      3783024.75     10192347.34      3780802.55     10189474.11
      3777764.37     10187312.66
#Sta/Elev= 30
    1607  251.85  1922.7  255.42  2086.6  251.62  2215.2   250.7  2308.4   243.8
  2379.1  235.13    2408  233.59  2428.9  230.21  2557.4  220.32    2778  206.27
  2841.8  203.64  3005.7  203.13  3148.8  201.22  3184.1  199.39  3198.6  199.36
  3206.7     201    4999  198.59  5237.8     201    7232     201  7238.2  199.09
  7259.1  199.12  7460.7  206.79  7561.6  210.36  7668.6  210.21    7719  212.82
  8407.6   228.2  8472.7  230.82  8621.6  243.26  8823.3  248.77  8967.9  258.68
#Mann= 3 , 0 , 0
    1607     .17       0    2778    .015       0  7460.7     .17       0
Bank Sta=2778,7460.7
XS Rating Curve= 0 ,0
Exp/Cntr=0.3,0.1

Type RM Length L Ch R = 1 ,396000  ,1000,1000,1000
BEGIN DESCRIPTION:
WFSJ Main 393.0
END DESCRIPTION:
XS GIS Cut Line= 3
      3783250.48     10192277.94      3781786.23      10189552.7
      3778328.62     10186887.32
#Sta/Elev= 30
  1906.3  247.65  1986.8  250.08  2150.8  246.95  2391.9  246.43  2674.7  240.42
  2955.3  226.01  3004.8  222.35  3049.3   216.2  3081.1  219.82  3124.9  219.97
 3372.09  206.63    3448  200.32    4999     199  6311.1   199.5  6333.8  200.24
  6354.6  206.27  6369.1  203.48  6389.9  206.06  6569.8  209.38  6761.4  207.62
  6946.2  209.94    7384  206.48    7505  206.07  7637.4  202.29    7660  199.85
  7674.5  202.77  7788.4  205.33  8822.3  225.55  9135.8   237.5  9365.7  252.27
#Mann= 6 ,-1 , 0
  1906.3     .17       0 3372.09    .015       0  6354.6     .11       0
  6569.8     .17       0    7384     .11       0    7505     .17       0
Bank Sta=3372.09,6354.6
XS Rating Curve= 0 ,0
Exp/Cntr=0.3,0.1

Type RM Length L Ch R = 1 ,395000  ,1000,1000,1000
BEGIN DESCRIPTION:
WFSJ Main 392.0
END DESCRIPTION:
XS GIS Cut Line= 3
       3784040.4     10192295.28      3782529.65     10188890.83
      3778517.86     10186561.08
#Sta/Elev= 30
  1275.4  248.62  1433.2  240.77    1521  231.07  1750.4  214.53  1839.9  218.27
  2013.7  232.81  2182.1  236.92  2402.4   232.2  2547.5  224.85  2581.9  219.46
  2628.2  224.35  2773.3  226.88  3128.9  223.03  3276.3  210.85 3307.19  207.03
  3347.7     201    4999  198.52  6412.9     201  6426.8  199.02  6574.8   204.9
  6806.7   207.1    7277  208.85  7349.6  204.72  7576.6  204.87  8031.1  213.33
    8133  212.23  8828.4  222.23  9315.9  235.27    9508  252.54  9639.2  260.88
#Mann= 4 ,-1 , 0
  1275.4     .17       0  3276.3     .15       0 3307.19    .015       0
  6806.7     .17       0
Bank Sta=3307.19,6806.7
XS Rating Curve= 0 ,0
Exp/Cntr=0.3,0.1

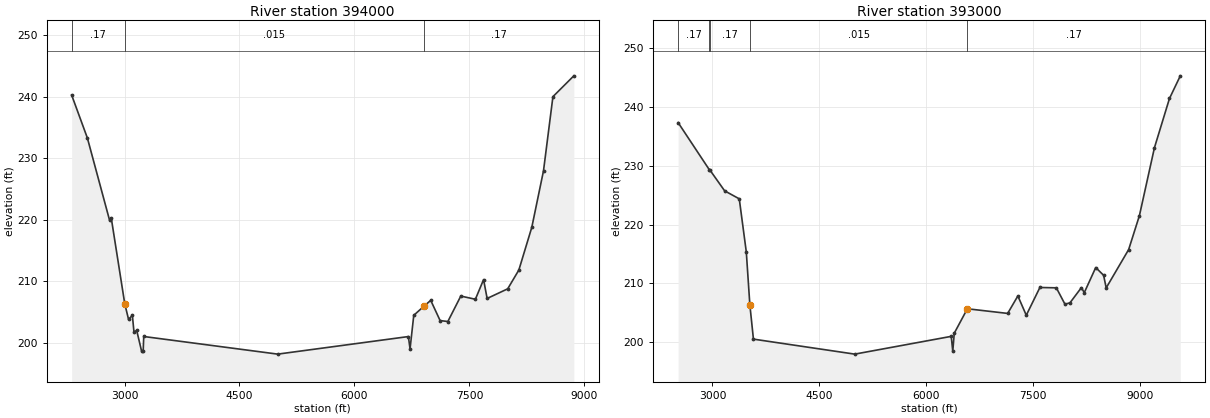
Type RM Length L Ch R = 1 ,394000  ,1000,1000,1000
BEGIN DESCRIPTION:
WFSJ Main 391.0
END DESCRIPTION:
XS GIS Cut Line= 3
      3785167.88      10190161.1      3783286.97     10188238.71
      3779978.84     10186245.51
#Sta/Elev= 30
  2310.5   240.3  2515.6  233.31  2805.5  219.91  2826.8  220.32  3003.6  206.31
    3053  203.78  3102.6  204.46  3123.7  201.71  3159.1  201.99  3222.7  198.63
    3244   198.7    3251     201    4999  198.13  6703.5  200.99  6725.3  198.99
  6773.9  204.45  6905.9  205.92  6995.2  206.88  7117.6  203.59  7218.6  203.44
  7387.5  207.58  7577.8  207.06  7684.6  210.26  7730.9  207.19  7999.4  208.76
  8144.8  211.82  8313.7  218.77  8466.4  227.97  8589.4  240.04  8862.2  243.43
#Mann= 3 ,-1 , 0
  2310.5     .17       0  3003.6    .015       0  6905.9     .17       0
Bank Sta=3003.6,6905.9
XS Rating Curve= 0 ,0
Exp/Cntr=0.3,0.1

Type RM Length L Ch R = 1 ,393000  ,1000,1000,1000
BEGIN DESCRIPTION:
WFSJ Main 390.0
END DESCRIPTION:
XS GIS Cut Line= 4
      3785667.83     10189511.04      3784067.76     10187613.91
      3782712.28     10186383.83      3779986.61     10186097.37
#Sta/Elev= 30
  2518.2  237.34  2958.4  229.29  2960.2  229.35  3171.5  225.74    3377  224.38
  3475.9  215.34  3525.5  206.39  3575.9  200.53    4999  197.98    6354     201
  6375.6  198.48  6396.5  201.54  6580.3  205.69  7146.6   204.9  7289.8  207.87
    7408  204.59  7599.1  209.31  7830.3  209.25    7951  206.47  8021.4   206.7
  8182.2  209.29  8222.5  208.43  8383.4   212.7    8494  211.38  8530.1  209.24
  8845.9  215.76  8996.7  221.52  9207.9  233.07    9419  241.44  9571.1  245.29
#Mann= 5 ,-1 , 0
  2518.2     .17       0  2958.4     .11       0  2960.2     .17       0
  3525.5    .015       0  6580.3     .17       0
Bank Sta=3525.5,6580.3
XS Rating Curve= 0 ,0
Exp/Cntr=0.3,0.1