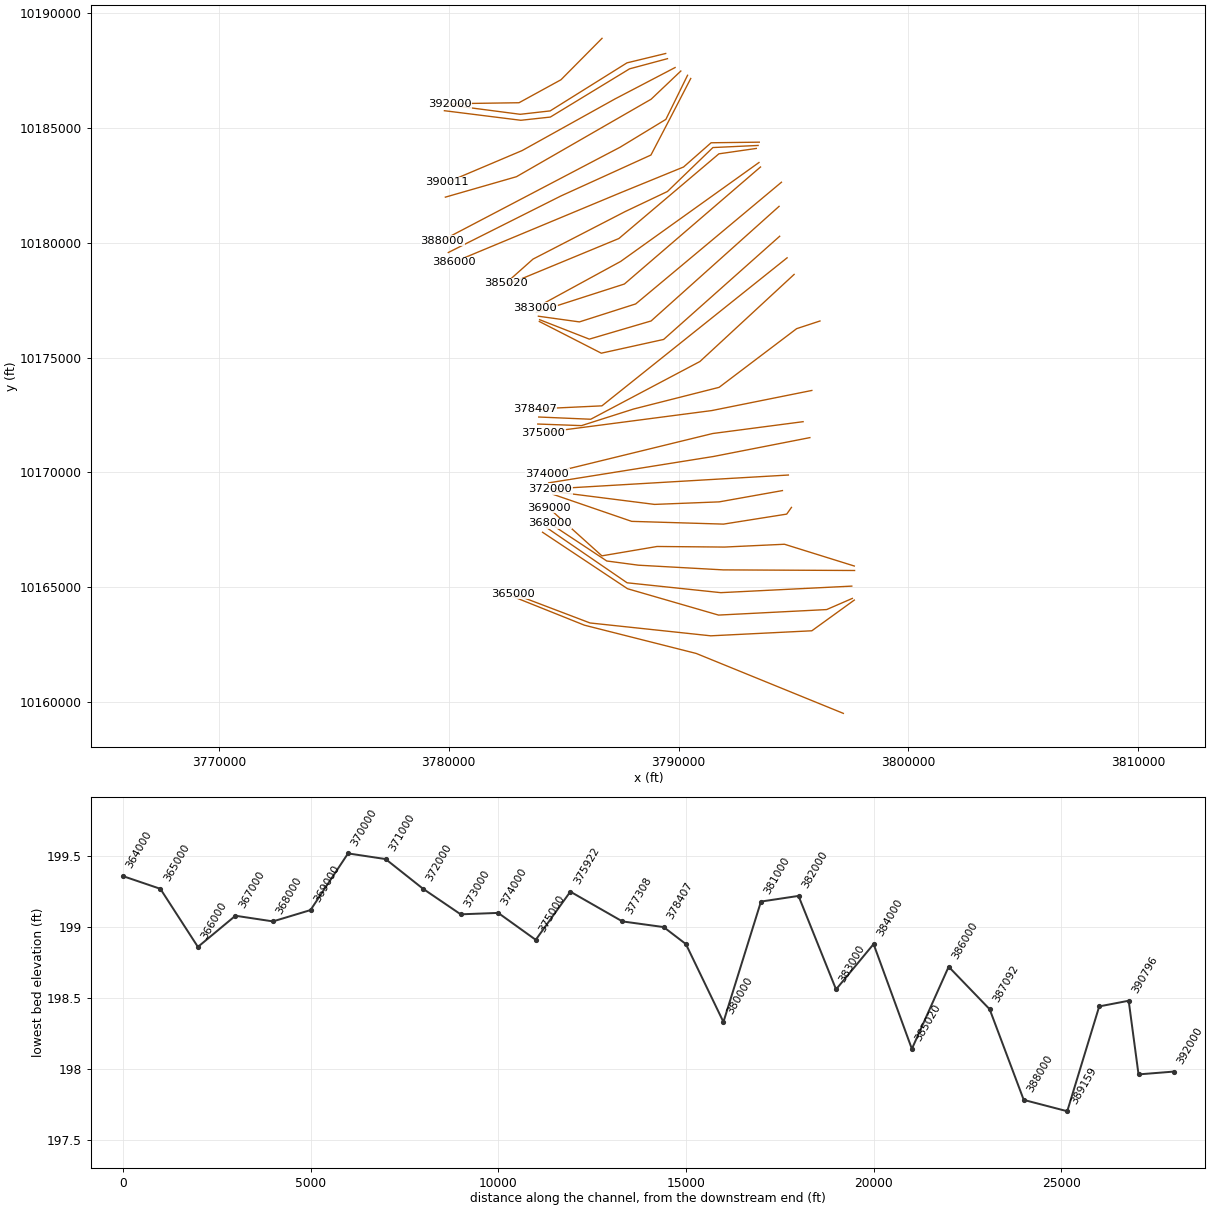
HEC-RAS study WFSJ Main.prj: WFSJ Main Base Level Engineering

--- WFSJ Main.g01 (geometry) --- (continued)

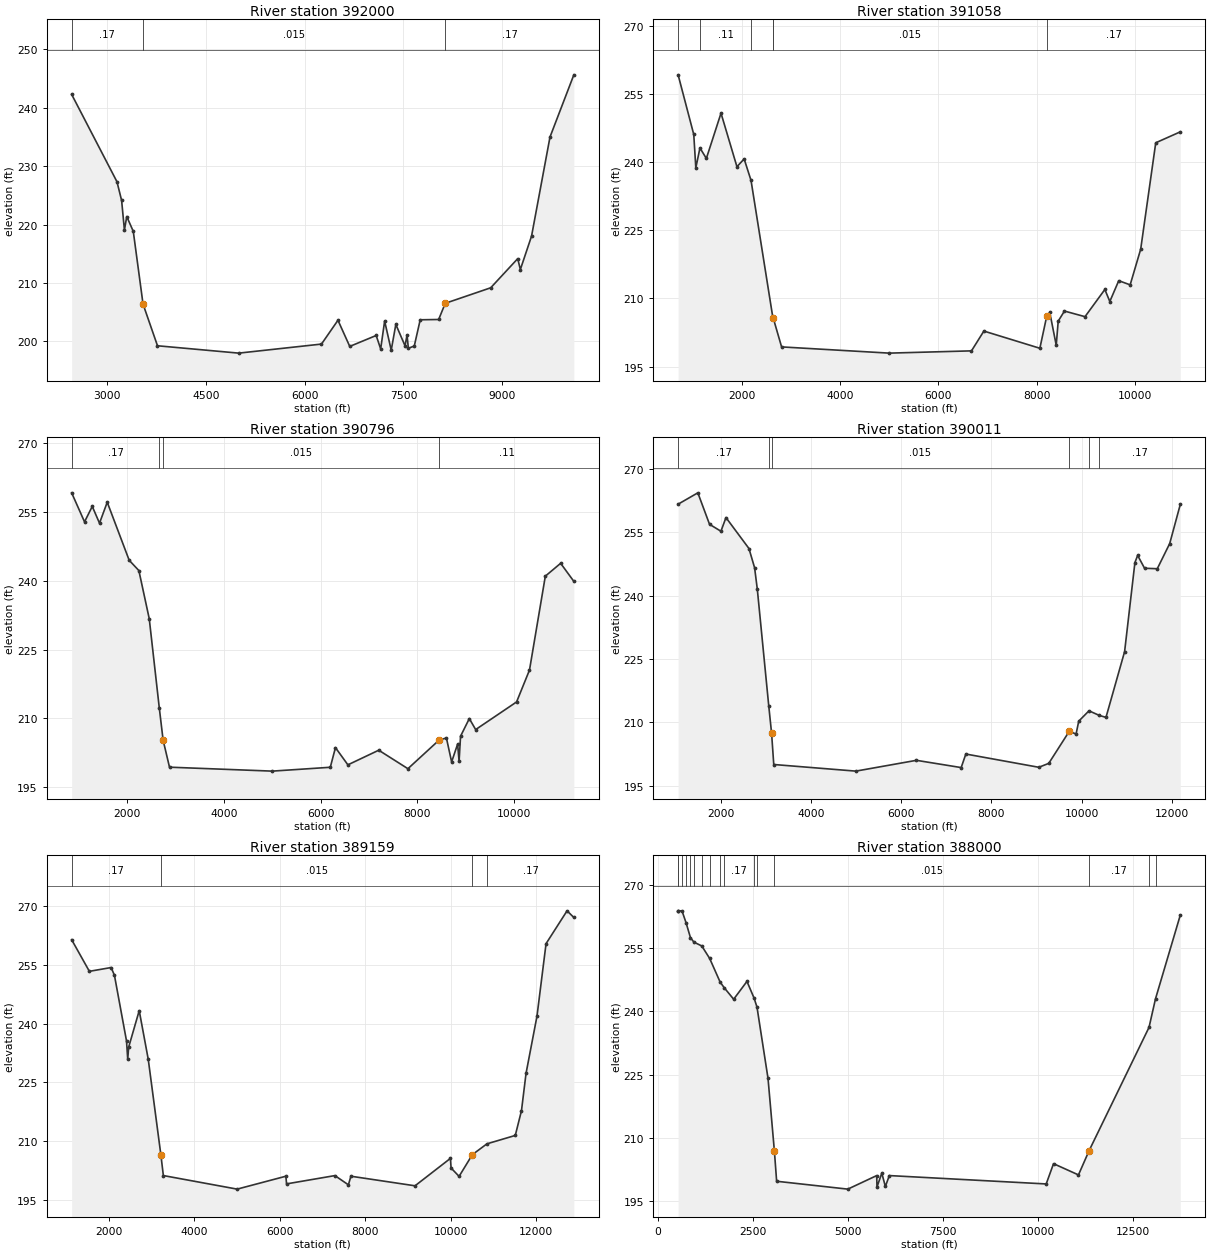
Type RM Length L Ch R = 1 ,392000  ,942,942,942
BEGIN DESCRIPTION:
WFSJ Main 389.0
END DESCRIPTION:
XS GIS Cut Line= 4
      3786670.58     10188901.16      3784885.32     10187098.32
       3783059.5     10186097.37        3780056.     10186053.97
#Sta/Elev= 30
  2462.8  242.29  3150.7  227.33  3221.4  224.12  3263.9  219.05  3299.2  221.37
  3398.2  218.84  3546.6  206.37  3765.9  199.24    4999  197.98    6255  199.53
  6505.3  203.61  6684.4  199.13  7085.5     201  7153.8   198.7  7213.9  203.47
  7313.9  198.48  7383.9   202.9  7523.9  199.22  7553.9   201.1  7573.9  198.81
  7663.9   199.2  7753.9  203.69  8033.9  203.74  8133.9  206.51    8824  209.17
  9234.1  214.16  9274.1   212.3  9444.1  218.02  9724.1  234.99   10086  245.64
#Mann= 3 ,-1 , 0
  2462.8     .17       0  3546.6    .015       0  8133.9     .17       0
Bank Sta=3546.6,8133.9
XS Rating Curve= 0 ,0
Exp/Cntr=0.3,0.1

Type RM Length L Ch R = 1 ,391058  ,262,262,262
BEGIN DESCRIPTION:
WFSJ Main 388.0
END DESCRIPTION:
XS GIS Cut Line= 5
      3789439.74     10188241.47      3787755.68     10187833.48
      3784413.67     10185741.47      3783111.58      10185593.9
      3779917.13     10186010.56
#Sta/Elev= 30
   708.4  259.27  1026.4  246.13  1068.2  238.77  1152.1  243.16  1282.4  240.85
  1580.3  250.82  1903.9  239.03  2050.5  240.74  2190.4  236.01  2637.8  205.53
  2638.4  205.49  2644.3  205.59  2811.7  199.33    4999  197.96  6671.6  198.46
  6923.2  202.82  8061.2  199.03  8202.4  206.17  8262.9  206.93    8394  199.69
  8434.3  205.01    8561  207.23  8978.9  205.99  9382.3  211.98  9483.1  209.33
  9664.7  213.92  9896.6     213 10110.7  220.86 10416.6   244.3 10915.9  246.71
#Mann= 7 ,-1 , 0
   708.4     .17       0  1152.1     .11       0  2190.4     .17       0
  2637.8     .15       0  2638.4     .08       0  2644.3    .015       0
  8202.4     .17       0
Bank Sta=2644.3,8202.4
XS Rating Curve= 0 ,0
Exp/Cntr=0.3,0.1

Type RM Length L Ch R = 1 ,390796  ,785,785,785
BEGIN DESCRIPTION:
WFSJ Main 387.0
END DESCRIPTION:
XS GIS Cut Line= 5
      3789517.82     10188015.77      3787868.53     10187573.06
       3784421.4     10185473.31      3783137.62     10185333.48
      3779812.97     10185750.15
#Sta/Elev= 30
   850.1  259.17  1116.5  252.84  1276.5  256.21  1426.1  252.55  1586.1  257.12
  2040.2  244.46  2240.1  242.22  2454.9  231.72  2662.7  212.25  2742.1  205.21
  2873.8  199.34    4999  198.48  6199.3  199.32  6305.9  203.61  6563.1  199.85
  7201.2  203.04  7804.7  199.01  8449.6  205.25  8600.8  205.71  8708.5  200.49
  8832.6  204.38  8862.8  200.63    8893  206.09  9074.4  209.94  9205.5  207.54
   10052  213.57 10318.9  220.52 10646.6     241 10963.1   243.8 11236.1  239.86
#Mann= 4 ,-1 , 0
   850.1     .17       0  2662.7     .11       0  2742.1    .015       0
  8449.6     .11       0
Bank Sta=2742.1,8449.6
XS Rating Curve= 0 ,0
Exp/Cntr=0.3,0.1

Type RM Length L Ch R = 1 ,390011  ,852,852,852
BEGIN DESCRIPTION:
WFSJ Main 386.0
END DESCRIPTION:
XS GIS Cut Line= 4
      3789848.75     10187629.25      3787233.72     10186262.06
      3783197.26     10184015.97       3779921.6     10182627.61
#Sta/Elev= 30
  1060.4  261.68  1497.4  264.37  1756.7  256.91  2009.3  255.27  2120.7  258.51
  2629.9  251.18  2755.2  246.62  2815.8  241.49  3068.5  213.92  3131.9  207.38
  3179.8  200.01    4999  198.44  6341.1     201  7332.8  199.28  7435.8  202.49
  9053.5  199.35  9273.5  200.28  9726.8  207.86    9879  207.24  9937.9  210.28
 10165.1  212.73 10396.9  211.62 10541.5  211.18 10954.2  226.76 11182.3  247.84
 11243.1  249.55   11396   246.5 11678.1  246.39 11953.4  252.35 12188.3  261.63
#Mann= 6 ,-1 , 0
  1060.4     .17       0  3068.5     .11       0  3131.9    .015       0
  9726.8     .17       0 10165.1     .11       0 10396.9     .17       0
Bank Sta=3131.9,9726.8
XS Rating Curve= 0 ,0
Exp/Cntr=0.3,0.1

Type RM Length L Ch R = 1 ,389159  ,1159,1159,1159
BEGIN DESCRIPTION:
Mapping XS 06ff7629
END DESCRIPTION:
XS GIS Cut Line= 4
       3790098.3     10187477.34      3788807.07     10186251.21
      3782947.69     10182876.64      3779855.25     10181986.89
#Sta/Elev= 30
  1123.4  261.48  1538.3  253.39  2047.9  254.36  2125.6  252.37  2408.3  235.59
  2436.6  230.92    2458  233.98  2705.6  243.34  2917.4  230.88  3212.3  206.51
  3270.8  201.17    4999   197.7  6140.2     201    6156  199.04  7288.3  201.16
  7604.3   198.8  7663.2     201  9164.7  198.55  9993.3  205.56 10008.9   203.1
 10196.2  200.96 10507.2  206.52 10848.3  209.28 11512.4  211.43 11657.6  217.77
 11763.8  227.27 12020.5  241.92   12233  260.47 12724.8  268.86 12883.6  267.16
#Mann= 4 ,-1 , 0
  1123.4     .17       0  3212.3    .015       0 10507.2     .15       0
 10848.3     .17       0
Bank Sta=3212.3,10507.2
XS Rating Curve= 0 ,0
Exp/Cntr=0.3,0.1

Type RM Length L Ch R = 1 ,388000  ,908,908,908
BEGIN DESCRIPTION:
WFSJ Main 385.0
END DESCRIPTION:
XS GIS Cut Line= 4
      3790391.28     10187292.91      3789447.26      10185372.3
      3787460.63     10184162.85      3779714.15     10180098.85
#Sta/Elev= 30
   534.1  263.89   534.2  263.89   635.9  263.92   741.8  261.12   859.1  257.54
   949.4  256.48  1156.9  255.57  1364.5   252.6  1640.4  246.97    1752  245.59
  1995.8  242.91  2345.5  247.15  2533.3  243.17  2609.9  241.02  2899.7  224.09
  3068.2  206.73  3126.3  199.65    4999  197.78  5759.7     201  5766.7  198.28
  5893.4  201.58  5987.2  198.41  6091.9     201 10219.2  199.01   10412  203.83
   11068  201.16   11350  206.96 12924.6  236.22 13095.1  243.01 13747.8  262.91
#Mann= 16 ,-1 , 0
   534.1     .11       0   534.2     .17       0   635.9     .11       0
   741.8     .17       0   859.1     .11       0   949.4     .17       0
  1156.9     .17       0  1364.5     .17       0  1640.4     .11       0
    1752     .17       0  2533.3     .11       0  2609.9     .17       0
  3068.2    .015       0   11350     .17       0 12924.6     .15       0
 13095.1     .17       0
Bank Sta=3068.2,11350
XS Rating Curve= 0 ,0
Exp/Cntr=0.3,0.1

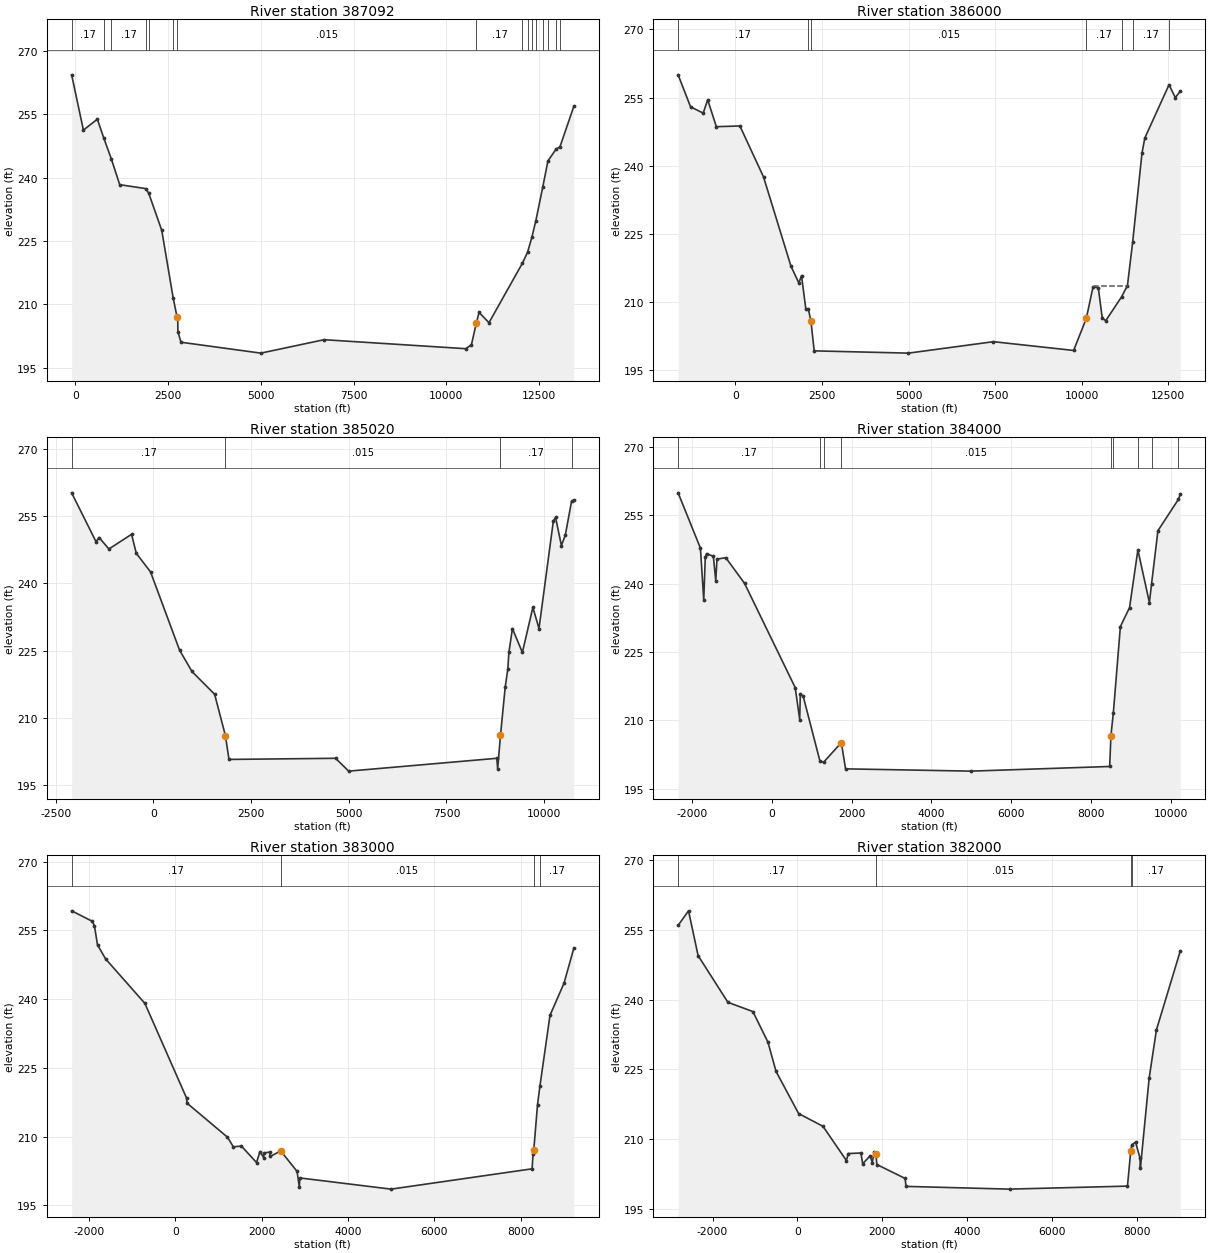
Type RM Length L Ch R = 1 ,387092  ,1092,1092,1092
BEGIN DESCRIPTION:
WFSJ Main 384.0
END DESCRIPTION:
XS GIS Cut Line= 5
      3790530.15     10187153.98      3789579.64     10185318.05
      3788798.39     10183820.65      3784879.12      10182036.8
      3779983.48     10179575.96
#Sta/Elev= 30
  -101.6  264.34   215.1  251.25   591.4  253.83   768.6  249.27   968.5  244.43
  1194.3  238.32  1896.8  237.39  1977.6  236.27  2327.7  227.51    2634  211.58
  2741.7  206.93  2758.1  206.92  2763.8   203.5  2846.5     201    4999  198.42
  6705.8   201.6   10527  199.47 10677.7  200.37 10811.6  205.58 10884.2  208.07
 11152.1  205.63 12053.9  219.73 12193.4  222.34 12307.9  225.84 12416.3  229.82
 12600.8  237.69 12741.4  243.93 12958.1  246.71 13066.5  247.31 13440.2  256.87
#Mann= 16 ,-1 , 0
  -101.6     .17       0   768.6     .11       0   968.5     .17       0
  1896.8     .11       0  1977.6     .17       0    2634     .11       0
  2741.7    .015       0 10811.6     .17       0 12053.9     .15       0
 12193.4     .17       0 12307.9     .11       0 12416.3     .17       0
 12600.8     .11       0 12741.4     .17       0 12958.1     .11       0
 13066.5     .17       0
Bank Sta=2741.7,10811.6
XS Rating Curve= 0 ,0
Exp/Cntr=0.3,0.1

Type RM Length L Ch R = 1 ,386000  ,980,980,980
BEGIN DESCRIPTION:
WFSJ Main 383.0
END DESCRIPTION:
XS GIS Cut Line= 5
      3793511.93     10184380.55      3791415.58     10184354.51
      3790217.66     10183299.82      3787476.45     10182178.92
      3780231.72     10179159.63
#Sta/Elev= 30
 -1654.1  260.01 -1294.3  252.96    -930  251.58    -800  254.51  -549.9  248.59
   130.1  248.75   812.1  237.53  1605.2  217.86    1832  214.18  1909.8  215.79
    2035  208.37  2107.9   208.4  2182.3  205.74  2275.9  199.22    4999  198.72
  7451.6  201.24  9767.6  199.31 10133.8  206.36 10328.6  213.32 10480.3  213.13
 10595.2  206.41   10696  205.87 11154.8  211.14 11322.1   213.6 11472.7  223.16
 11741.3  242.71 11823.7  246.09   12523  257.83 12704.3  254.99 12848.7  256.43
#Mann= 7 ,-1 , 0
 -1654.1     .17       0  2107.9     .11       0  2182.3    .015       0
 10133.8     .17       0 11154.8     .15       0 11472.7     .17       0
   12523     .11       0
#XS Ineff= 1 ,-1
 10350.3   11350   213.4
Permanent Ineff=
       F
Bank Sta=2182.3,10133.8
XS Rating Curve= 0 ,0
Exp/Cntr=0.3,0.1

Type RM Length L Ch R = 1 ,385020  ,1020,1020,1020
BEGIN DESCRIPTION:
WFSJ Main 382.0
END DESCRIPTION:
XS GIS Cut Line= 6
      3793459.89     10184237.32       3791493.7     10184146.18
      3789514.53     10182232.11       3787678.6     10181359.72
      3783668.18      10179289.4      3782484.07     10178235.42
#Sta/Elev= 30
 -2091.4  260.18 -1468.7   249.3 -1388.6  250.22 -1138.3  247.66  -557.7  250.93
  -437.6   246.7     -73  242.56   669.6  225.13   987.8  220.35  1567.9  215.27
  1843.7  206.05  1935.5  200.75  4662.9     201    4999  198.14  8789.6     201
  8811.8  198.64  8883.9   206.1  9005.6  216.93    9072  220.92  9099.8  224.61
  9189.7  229.91  9444.3  224.59  9713.2  234.65  9869.5  229.92 10237.5  253.93
 10294.3  254.69 10443.1  248.43 10542.1  250.71 10702.4  258.26 10761.4  258.54
#Mann= 4 ,-1 , 0
 -2091.4     .17       0  1843.7    .015       0  8883.9     .17       0
 10702.4     .11       0
Bank Sta=1843.7,8883.9
XS Rating Curve= 0 ,0
Exp/Cntr=0.3,0.1

Type RM Length L Ch R = 1 ,384000  ,1000,1000,1000
BEGIN DESCRIPTION:
WFSJ Main 381.0
END DESCRIPTION:
XS GIS Cut Line= 4
      3793381.75     10184107.12      3791754.12     10183872.74
      3787404.28     10180185.92      3782562.11     10178182.92
#Sta/Elev= 30
 -2346.5  259.95 -1786.9   247.8 -1704.4  236.41 -1665.6  245.78 -1633.9  246.59
 -1463.6  246.03   -1403  240.65 -1372.7  245.41 -1150.9  245.71  -681.8  240.09
   588.1  217.21   701.2  210.19   715.5  215.72   786.9  215.36  1209.2  201.04
  1300.7  200.84  1744.4  205.14  1850.2  199.38    4999  198.88  8469.9   199.9
  8501.1  206.66  8561.6  211.65  8737.9  230.59  8967.7  234.76    9177  247.41
  9465.5  235.86  9518.5   239.9  9679.5  251.64 10194.7  258.55 10240.1  259.61
#Mann= 9 ,-1 , 0
 -2346.5     .17       0  1209.2     .15       0  1300.7     .11       0
  1744.4    .015       0  8501.1     .15       0  8561.6     .17       0
    9177     .15       0  9518.5     .17       0 10194.7     .11       0
Bank Sta=1744.4,8501.1
XS Rating Curve= 0 ,0
Exp/Cntr=0.3,0.1

Type RM Length L Ch R = 1 ,383000  ,1000,1000,1000
BEGIN DESCRIPTION:
WFSJ Main 380.0
END DESCRIPTION:
XS GIS Cut Line= 3
       3793498.9     10183495.13      3787483.01      10179189.2
      3783767.85     10177161.07
#Sta/Elev= 30
 -2398.1  259.25   -1921  256.97 -1870.6  255.99 -1799.4  251.83 -1612.7  248.78
  -702.3  239.07   264.5   218.4   271.8  217.33  1210.4  209.89  1346.8  207.79
  1533.5  207.95  1883.7  204.36  1963.5  206.75  2049.5  205.42  2055.6  206.44
  2185.9  206.64  2200.6  205.69  2443.8  206.89  2823.4  202.42  2873.8  199.06
  2888.5     201    4999  198.56  8266.1  202.99  8287.9  206.19  8304.1     207
  8391.4  216.99  8446.2  220.95  8679.9  236.44  9004.8  243.46  9232.7   251.1
#Mann= 4 ,-1 , 0
 -2398.1     .17       0  2443.8    .015       0  8304.1     .11       0
  8446.2     .17       0
Bank Sta=2443.8,8304.1
XS Rating Curve= 0 ,0
Exp/Cntr=0.3,0.1

Type RM Length L Ch R = 1 ,382000  ,1000,1000,1000
BEGIN DESCRIPTION:
WFSJ Main 379.0
END DESCRIPTION:
XS GIS Cut Line= 3
      3793564.04     10183299.85      3787642.98     10178204.39
      3783812.15     10176971.94
#Sta/Elev= 30
 -2811.7     256 -2566.6  259.14 -2340.6   249.5 -1638.4  239.44 -1049.2  237.45
  -694.8  230.87  -503.8  224.57    28.3  215.49   602.2  212.75  1155.2  205.37
    1198  206.88  1496.4     207  1538.1  204.69  1715.9   206.4  1765.3  204.94
    1808  207.24  1850.8  206.78  1871.7  204.52  2538.8  201.52  2559.6  199.81
    4999  199.22  7778.7  199.87 7855.38  207.35  7879.7  208.75  7969.4  209.33
  8072.8  205.96  8083.3  203.72  8290.2  223.14  8461.5  233.51  9024.2  250.51
#Mann= 4 ,-1 , 0
 -2811.7     .17       0  1850.8    .015       0 7855.38     .11       0
  7879.7     .17       0
Bank Sta=1850.8,7855.38
XS Rating Curve= 0 ,0
Exp/Cntr=0.3,0.1

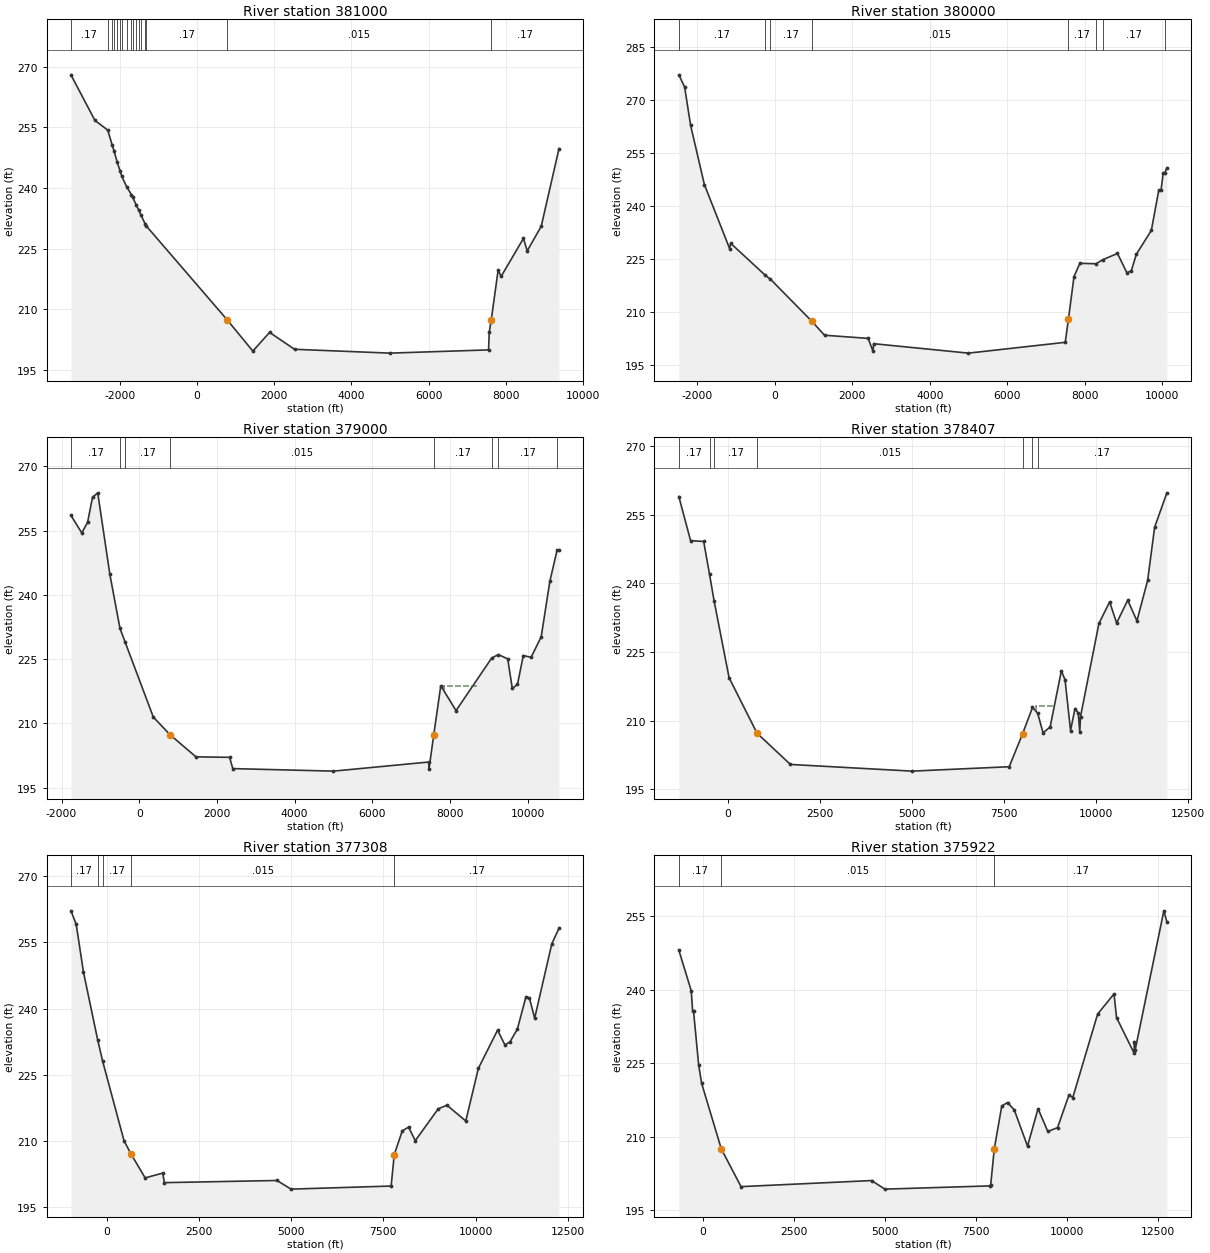
Type RM Length L Ch R = 1 ,381000  ,1000,1000,1000
BEGIN DESCRIPTION:
WFSJ Main 378.0
END DESCRIPTION:
XS GIS Cut Line= 4
      3794475.51     10182635.79      3788136.25     10177338.51
      3785686.41     10176555.03      3783902.75      10176802.4
#Sta/Elev= 30
 -3261.2  267.99 -2641.5  256.73 -2308.3  254.32 -2192.7   250.6 -2147.6  249.25
   -2068  246.53   -1987  244.15 -1943.4  242.87 -1818.8  240.33 -1694.1  238.32
 -1665.7  237.74 -1569.5  235.79   -1505  234.48 -1444.9  233.26 -1344.4  231.22
 -1320.3  230.73  783.44  207.41  1447.4  199.68  1880.8  204.31  2526.3  200.13
    4999  199.18  7549.6  199.98    7567  204.32 7619.97  207.41  7797.9  219.73
  7874.7  218.13  8453.6  227.56  8549.9  224.45  8913.3  230.54  9372.8  249.73
#Mann= 17 ,-1 , 0
 -3261.2     .17       0 -2308.3     .17       0 -2192.7     .11       0
 -2147.6     .17       0   -2068     .11       0   -1987     .17       0
 -1943.4     .11       0 -1818.8     .11       0 -1694.1     .17       0
 -1665.7     .11       0 -1569.5     .17       0   -1505     .11       0
 -1444.9     .17       0 -1344.4     .11       0 -1320.3     .17       0
  783.44    .015       0 7619.97     .17       0
Bank Sta=783.44,7619.97
XS Rating Curve= 0 ,0
Exp/Cntr=0.3,0.1

Type RM Length L Ch R = 1 ,380000  ,1000,1000,1000
BEGIN DESCRIPTION:
WFSJ Main 377.0
END DESCRIPTION:
XS GIS Cut Line= 4
      3794372.39     10181586.26      3788804.67     10176595.82
      3786117.21     10175805.03      3783955.79     10176651.37
#Sta/Elev= 30
 -2476.9  277.11 -2328.3  273.67 -2172.8  262.77 -1818.4  246.06 -1167.3  227.94
 -1138.9  229.42  -244.2  220.35  -112.3  219.25  954.55  207.37  1283.3   203.4
  2409.1   202.5    2537  198.83  2551.2     201    4999  198.33  7498.4  201.39
  7580.9  207.98  7724.7  220.01  7875.9  223.75  8294.8  223.63  8461.1  224.74
  8847.1  226.55  9088.7  221.09  9202.6  221.62  9335.6  226.35  9720.9  233.06
  9913.5  244.49  9973.2  244.62 10027.4  249.33 10060.9  249.21 10122.6  250.78
#Mann= 8 ,-1 , 0
 -2476.9     .17       0  -244.2     .11       0  -112.3     .17       0
  954.55    .015       0  7580.9     .17       0  8294.8     .11       0
  8461.1     .17       0 10060.9     .11       0
Bank Sta=954.55,7580.9
XS Rating Curve= 0 ,0
Exp/Cntr=0.3,0.1

Type RM Length L Ch R = 1 ,379000  ,593,593,593
BEGIN DESCRIPTION:
WFSJ Main 376.0
END DESCRIPTION:
XS GIS Cut Line= 4
      3794398.43     10180284.17      3789350.27     10175791.52
      3786638.05     10175193.05      3783942.75     10176573.25
#Sta/Elev= 30
 -1757.8  258.54 -1478.7  254.44 -1329.9   256.9 -1202.8  262.75 -1068.2   263.8
  -756.3  244.79  -495.5  232.18  -367.7   229.1   362.5  211.49  793.08  207.37
  1460.4  202.21    2325   202.1  2409.4  199.47    4999  198.88    7450     201
  7460.2  199.43  7583.1  207.42  7762.9   218.8  8155.6     213  9072.9  225.25
  9244.6  226.07  9485.4  225.06  9604.2  218.17  9737.5  219.12  9887.3  225.85
 10087.1  225.42   10348  230.21   10570  243.13 10756.9  250.43 10805.6  250.51
#Mann= 8 ,-1 , 0
 -1757.8     .17       0  -495.5     .11       0  -367.7     .17       0
  793.08    .015       0  7583.1     .17       0  9072.9     .11       0
  9244.6     .17       0 10756.9     .11       0
#XS Ineff= 1 ,-1
  7850.3    8700  218.82
Permanent Ineff=
       F
Bank Sta=793.08,7583.1
XS Rating Curve= 0 ,0
Exp/Cntr=0.3,0.1

Type RM Length L Ch R = 1 ,378407  ,1099,1099,1099
BEGIN DESCRIPTION:
WFSJ Main 375.0
END DESCRIPTION:
XS GIS Cut Line= 3
      3794721.42     10179344.99      3786665.82     10172900.52
       3783735.3     10172761.63
#Sta/Elev= 30
 -1330.8  258.94 -1012.4  249.32  -657.1  249.14  -498.4  241.98  -375.7  236.24
    32.9  219.39  792.05  207.28  1697.7  200.46    4999     199  7638.2  199.96
  8001.6  207.17  8270.1   212.9  8410.2  211.66    8557  207.36  8749.1  208.63
  9053.4  220.87  9153.6  218.96  9303.7  207.86  9423.9  212.65    9514  211.65
    9554  207.51    9574  210.92 10074.6  231.25 10364.9  235.95   10554  231.34
 10855.5  236.31 11105.7  231.81 11396.1  240.62 11586.3  252.25 11919.2  259.76
#Mann= 7 ,-1 , 0
 -1330.8     .17       0  -498.4     .11       0  -375.7     .17       0
  792.05    .015       0  8001.6     .17       0  8270.1     .11       0
  8410.2     .17       0
#XS Ineff= 2 ,-1
  9053.4    9865  220.87  8356.9    8875  213.12
Permanent Ineff=
       F       F
Bank Sta=792.05,8001.6
XS Rating Curve= 0 ,0
Exp/Cntr=0.3,0.1

Type RM Length L Ch R = 1 ,377308  ,1386,1386,1386
BEGIN DESCRIPTION:
WFSJ Main 374.0
END DESCRIPTION:
XS GIS Cut Line= 4
      3795026.95     10178622.75      3790929.71     10174831.07
      3786179.71     10172317.18       3783915.8     10172414.41
#Sta/Elev= 30
  -964.5  262.15  -822.4  259.12  -624.5  248.22  -236.8  232.76  -106.9  228.09
   472.6  210.04   656.3   207.1  1045.8  201.59  1519.8  202.67  1569.2  200.51
    4618     201    4999  199.04  7710.8  199.74    7795  206.87  8014.3  212.28
    8184  213.09  8364.6  210.03  8985.7  217.24  9222.1  218.08  9733.2  214.49
 10074.1  226.43 10594.6  235.09 10794.8  231.71 10934.9  232.49 11130.9  235.33
 11362.5  242.63 11455.4  242.43 11599.2   237.8 12062.5  254.63 12258.2  258.21
#Mann= 5 ,-1 , 0
  -964.5     .17       0  -236.8    .125       0  -106.9     .17       0
   656.3    .015       0    7795     .17       0
Bank Sta=656.3,7795
XS Rating Curve= 0 ,0
Exp/Cntr=0.3,0.1

Type RM Length L Ch R = 1 ,375922  ,922,922,922
BEGIN DESCRIPTION:
WFSJ Main 373.0
END DESCRIPTION:
XS GIS Cut Line= 6
      3796151.92     10176594.95      3795138.05     10176261.63
      3791763.05     10173706.07      3788040.82     10172761.63
      3785776.93      10172039.4      3783874.11     10172108.85
#Sta/Elev= 30
  -665.9  248.08  -324.8  239.78  -286.6  235.58  -261.6  235.57  -122.3   224.7
   -40.6  220.89     502  207.46  1043.8  199.76  4634.7     201    4999  199.25
  7879.6  199.91  7910.5  200.17  8009.1  207.52  8213.9  216.24  8372.6  216.95
  8557.9  215.45  8922.5  208.04  9212.3  215.69  9480.4  211.04  9748.4  211.82
   10063   218.5   10167  217.97 10851.2  235.04 11300.6  239.14 11370.6  234.31
   11851  227.08 11861.3  229.38   11881  227.63 12671.5  256.13 12755.3  253.87
#Mann= 3 , 0 , 0
  -665.9     .17       0     502    .015       0  8009.1     .17       0
#XS Ineff= 1 ,-1
  8372.6   10020  216.95
Permanent Ineff=
       F
Bank Sta=502,8009.1
XS Rating Curve= 0 ,0
Exp/Cntr=0.3,0.1

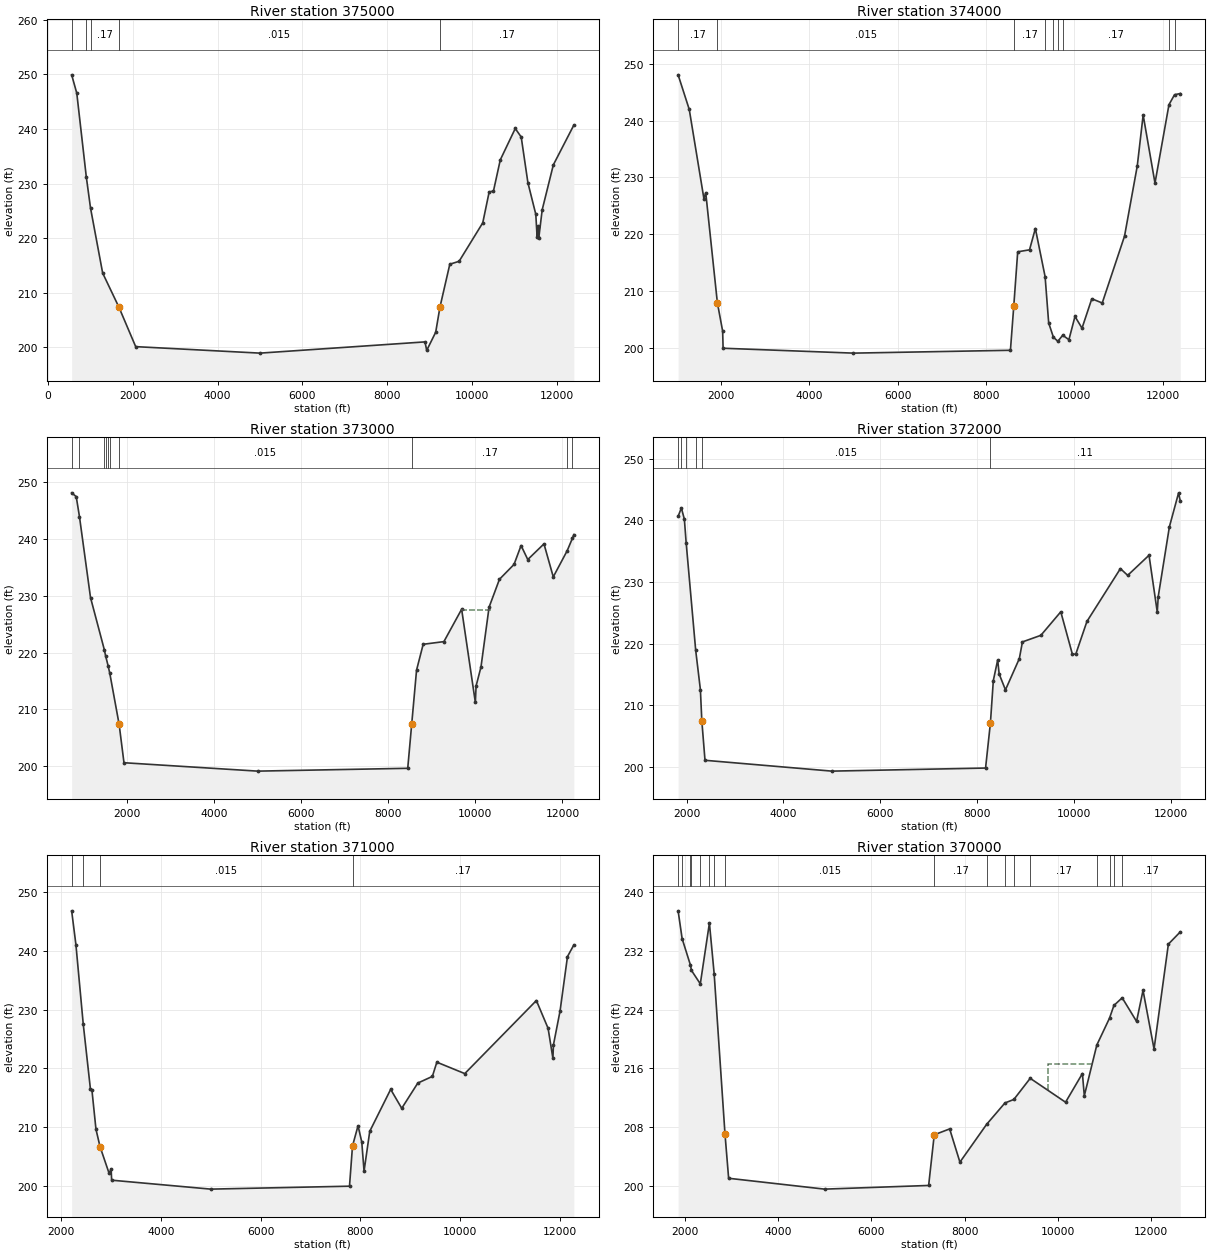
Type RM Length L Ch R = 1 ,375000  ,1000,1000,1000
BEGIN DESCRIPTION:
WFSJ Main 372.0
END DESCRIPTION:
XS GIS Cut Line= 3
       3795797.8     10173570.66      3791444.05     10172694.65
      3784108.65     10171735.83
#Sta/Elev= 30
     559  249.94     680  246.57     904  231.25  1003.9  225.51  1290.1  213.59
 1673.74  207.33  2068.6   200.1    4999  198.91    8889  200.97  8929.3  199.41
  9141.1  202.74    9242  207.37  9473.9  215.21  9693.1  215.75 10250.5   222.8
 10401.8  228.47 10502.6  228.62   10664  234.35   11017   240.1 11157.3  238.53
 11315.1  230.15   11501  224.37 11531.3  220.28 11546.8  222.04 11551.9  220.28
 11561.5  222.24 11571.6  220.04 11652.3  225.21 11914.5  233.43 12397.8  240.72
#Mann= 5 ,-1 , 0
     559     .17       0     904     .11       0  1003.9     .17       0
 1673.74    .015       0    9242     .17       0
Bank Sta=1673.74,9242
XS Rating Curve= 0 ,0
Exp/Cntr=0.3,0.1

Type RM Length L Ch R = 1 ,374000  ,1000,1000,1000
BEGIN DESCRIPTION:
WFSJ Main 371.0
END DESCRIPTION:
XS GIS Cut Line= 3
       3795417.9     10172211.08      3791482.34     10171695.39
      3784290.99     10169937.44
#Sta/Elev= 30
  1030.8  248.05    1283  241.96  1615.8  226.23  1656.1  227.33  1919.7  207.96
  2039.4  202.96  2049.5  199.96    4999   199.1  8556.2   199.6 8632.61  207.45
  8720.9  216.92  8988.6  217.27  9120.7  221.02  9341.4  212.55  9422.5   204.4
  9529.4   201.9  9630.1  201.18  9740.7  202.25  9880.6  201.46   10018  205.55
 10177.2  203.49 10398.9  208.66 10635.3  207.92 11140.1  219.68 11428.4  232.02
 11561.8  240.98 11829.8  229.01 12146.4   242.8 12272.1  244.55 12403.1  244.76
#Mann= 9 ,-1 , 0
  1030.8     .17       0  1919.7    .015       0 8632.61     .17       0
  9341.4     .11       0  9529.4     .15       0  9630.1     .11       0
  9740.7     .17       0 12146.4     .11       0 12272.1     .17       0
#XS Ineff= 1 ,-1
  9120.7   11300  221.02
Permanent Ineff=
       F
Bank Sta=1919.7,8632.61
XS Rating Curve= 0 ,0
Exp/Cntr=0.3,0.1

Type RM Length L Ch R = 1 ,373000  ,1000,1000,1000
BEGIN DESCRIPTION:
WFSJ Main 370.0
END DESCRIPTION:
XS GIS Cut Line= 3
      3795712.75     10171516.84      3791520.63     10170696.12
      3784351.33     10169548.32
#Sta/Elev= 30
   728.3  248.15   833.3  247.48   907.4  243.97  1161.3  229.69  1478.4   220.5
  1506.3  219.47  1567.3   217.6  1603.9  216.34  1818.7  207.33    1930  200.57
    4999  199.09  8446.1  199.59  8537.3  207.38  8648.7  216.89  8800.7  221.45
  9276.6  221.92    9684  227.63  9999.1   211.2 10015.9   214.1 10128.2  217.45
 10314.2  227.99 10552.6  232.91 10887.5  235.53 11048.8  238.86 11202.6  236.39
 11574.7  239.15 11788.1  233.33 12106.2  237.92 12229.6  240.16 12260.6  240.78
#Mann= 10 ,-1 , 0
   728.3     .11       0   907.4     .17       0  1478.4     .11       0
  1506.3     .17       0  1567.3     .11       0  1603.9     .17       0
  1818.7    .015       0  8537.3     .17       0 12106.2     .11       0
 12229.6     .17       0
#XS Ineff= 1 ,-1
  9678.9   10400  227.56
Permanent Ineff=
       F
Bank Sta=1818.7,8537.3
XS Rating Curve= 0 ,0
Exp/Cntr=0.3,0.1

Type RM Length L Ch R = 1 ,372000  ,1000,1000,1000
BEGIN DESCRIPTION:
WFSJ Main 369.0
END DESCRIPTION:
XS GIS Cut Line= 3
      3794776.94     10169888.36      3791606.71     10169703.71
      3784422.85     10169280.73
#Sta/Elev= 30
  1824.4  240.66  1891.5  242.02  1953.7  240.19  1990.2  236.39  2187.4  218.89
  2284.3  212.52  2314.3  207.41  2379.6  201.03    4999  199.27  8174.3  199.77
  8274.5   207.1  8334.6  213.99  8424.8  217.34  8454.8  215.06  8585.1  212.47
  8871.7  217.55  8935.7  220.26  9316.3  221.33  9727.8  225.15  9967.4  218.26
 10037.6  218.28   10268  223.59 10959.2  232.17 11109.4  231.07 11550.2  234.34
 11720.5  225.11 11740.5  227.63 11970.9  238.96 12161.2  244.48 12196.3  243.12
#Mann= 6 ,-1 , 0
  1824.4     .17       0  1891.5     .11       0  1990.2     .17       0
  2187.4     .11       0  2314.3    .015       0  8274.5     .11       0
#XS Ineff= 1 ,-1
  8424.8    8905  217.34
Permanent Ineff=
       F
Bank Sta=2314.3,8274.5
XS Rating Curve= 0 ,0
Exp/Cntr=0.3,0.1

Type RM Length L Ch R = 1 ,371000  ,1000,1000,1000
BEGIN DESCRIPTION:
WFSJ Main 368.0
END DESCRIPTION:
XS GIS Cut Line= 4
      3794517.84     10169211.07       3791768.3     10168719.71
      3788954.49     10168609.37      3784521.42     10169171.17
#Sta/Elev= 30
  2206.9  246.79  2292.7  241.03  2438.6  227.61  2582.8  216.56  2613.2  216.37
  2694.8  209.66  2775.8  206.72  2958.6  202.16  2999.2  202.92  3009.4     201
    4999  199.48  7782.6  199.98  7842.8  206.81  7953.8  210.25  8028.8  207.49
  8074.7  202.54    8189  209.31  8608.9  216.44  8830.7  213.22  9153.2  217.51
  9445.5  218.64  9535.4  221.06   10096  219.12 11532.6  231.54 11767.8  226.82
 11864.7  221.71 11874.8  223.98 12008.1  229.77 12157.1  239.02 12284.5  240.99
#Mann= 4 ,-1 , 0
  2206.9     .17       0  2438.6     .11       0  2775.8    .015       0
  7842.8     .17       0
#XS Ineff= 1 ,-1
  8608.9    9220  216.44
Permanent Ineff=
       F
Bank Sta=2775.8,7842.8
XS Rating Curve= 0 ,0
Exp/Cntr=0.3,0.1

Type RM Length L Ch R = 1 ,370000  ,1000,1000,1000
BEGIN DESCRIPTION:
WFSJ Main 367.0
END DESCRIPTION:
XS GIS Cut Line= 5
      3794910.61     10168478.64      3794704.02     10168186.97
      3791955.86     10167751.28      3787959.23       10167871.
      3784532.51      10169049.7
#Sta/Elev= 30
  1860.1  237.47    1946  233.68  2125.1  230.05  2145.9  229.35  2335.6  227.51
  2530.8   235.8  2632.3  228.91  2864.3  207.07  2942.6     201    4999  199.52
    7229  200.02  7349.1  206.93  7679.2  207.73  7899.3   203.2  8472.1  208.36
  8864.1  211.27  9055.4  211.75  9405.6  214.63 10163.1  211.37 10524.2  215.28
   10565  212.25 10833.1  219.17 11104.9  222.83 11199.9  224.57 11376.8  225.61
 11684.7  222.39 11823.4  226.62 12059.5  218.63 12366.6  232.93 12622.2   234.6
#Mann= 17 ,-1 , 0
  1860.1     .17       0    1946     .11       0  2125.1     .17       0
  2145.9     .11       0  2335.6     .17       0  2530.8     .11       0
  2632.3     .17       0  2864.3    .015       0  7349.1     .17       0
  8472.1     .11       0  8864.1     .17       0  9055.4     .11       0
  9405.6     .17       0 10833.1     .11       0 11104.9     .17       0
 11199.9     .11       0 11376.8     .17       0
#XS Ineff= 1 ,-1
  9779.9   10770  216.63
Permanent Ineff=
       F
Bank Sta=2864.3,7349.1
XS Rating Curve= 0 ,0
Exp/Cntr=0.3,0.1

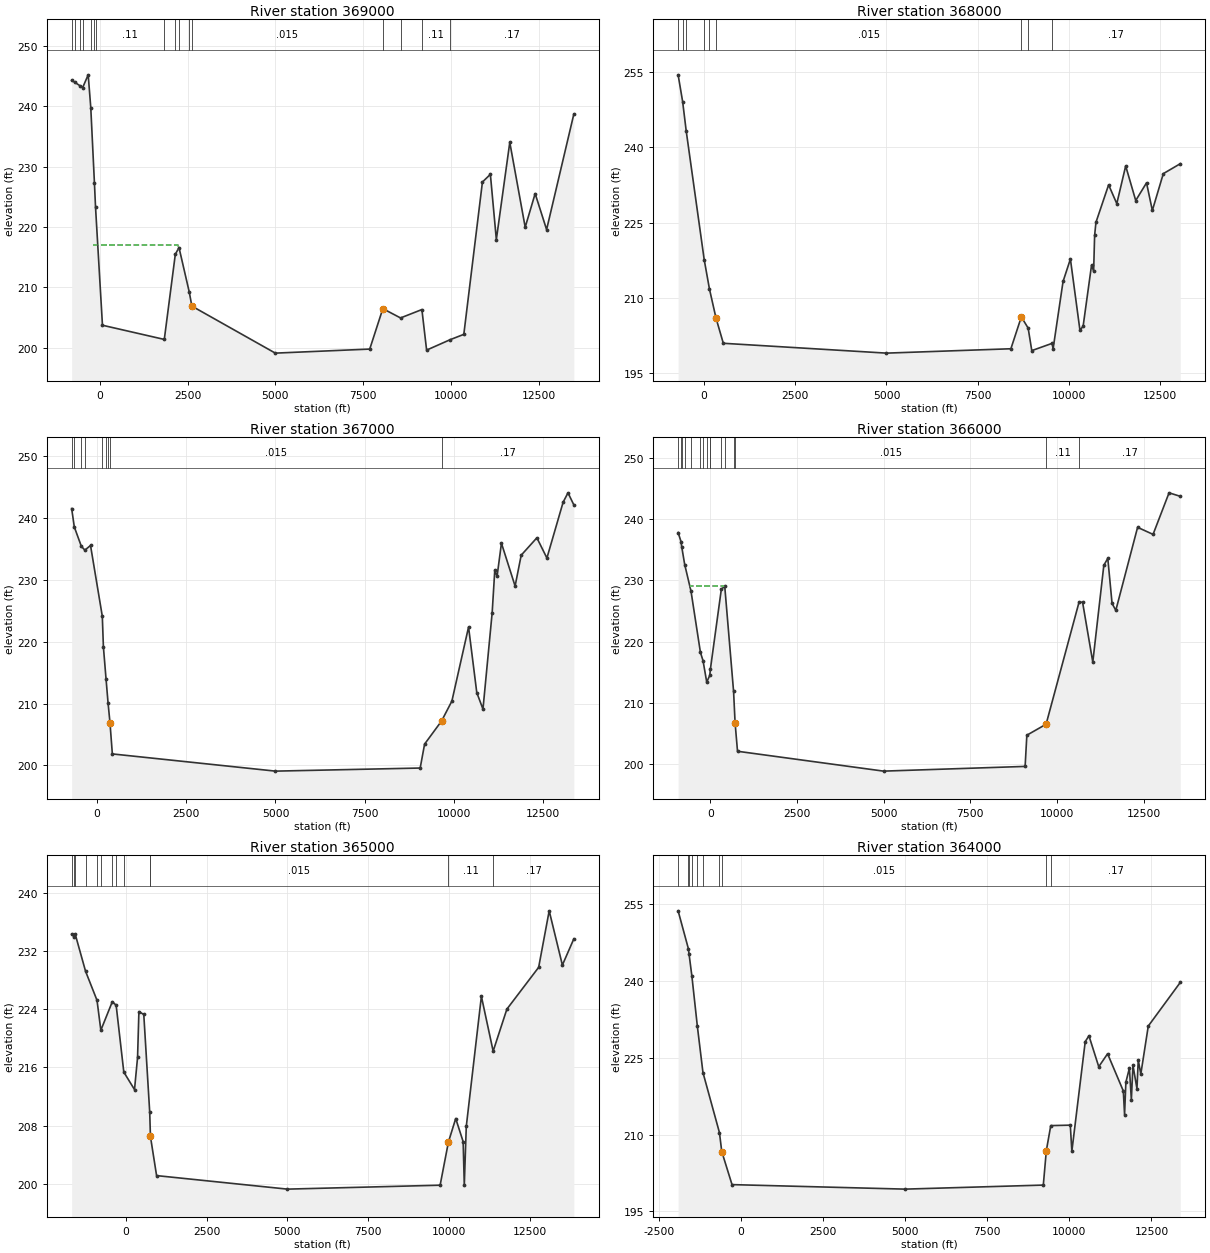
Type RM Length L Ch R = 1 ,369000  ,1000,1000,1000
BEGIN DESCRIPTION:
WFSJ Main 366.0
END DESCRIPTION:
XS GIS Cut Line= 6
      3797644.95     10165926.57       3794606.8     10166874.47
      3791994.16     10166752.01      3789065.13     10166777.25
      3786664.18     10166369.61      3784337.95     10168466.26
#Sta/Elev= 30
  -798.1  244.32  -706.8  243.98  -552.1  243.39  -483.6  243.13  -327.1  245.23
  -253.6  239.79    -149  227.23    -119  223.37    78.8  203.74    1839  201.39
  2152.9   215.5  2257.5  216.61    2549  209.25  2623.7  206.91    4999  199.12
  7686.4  199.79  8059.5  206.49  8563.7  204.95  9171.2  206.34  9305.5  199.62
  9976.6  201.35 10364.4  202.23 10894.1  227.47 11120.5  228.74 11290.2  217.94
 11672.8  234.04 12111.5  219.98 12394.8  225.55 12720.6  219.59 13496.1  238.73
#Mann= 16 ,-1 , 0
  -798.1     .11       0  -706.8     .17       0  -552.1     .11       0
  -483.6     .17       0  -253.6     .11       0    -149     .17       0
    -119     .11       0    1839     .17       0  2152.9     .11       0
  2257.5     .17       0    2549     .11       0  2623.7    .015       0
  8059.5     .17       0  8563.7     .15       0  9171.2     .11       0
  9976.6     .17       0
#XS Ineff= 1 ,-1
    -180  2221.5     217
Permanent Ineff=
       F
Bank Sta=2623.7,8059.5
XS Rating Curve= 0 ,0
Exp/Cntr=0.3,0.1

Type RM Length L Ch R = 1 ,368000  ,1000,1000,1000
BEGIN DESCRIPTION:
WFSJ Main 365.0
END DESCRIPTION:
XS GIS Cut Line= 5
      3797657.14     10165732.11       3791944.3     10165758.39
      3788250.89     10165963.02      3786877.63     10166145.31
       3784398.5     10167785.91
#Sta/Elev= 30
  -712.9  254.44  -589.3  249.13  -490.6  243.24     2.9  217.62   146.7  211.79
   326.4  206.01   526.4     201    4999  199.04  8411.7  199.91  8698.1  206.25
  8885.2  204.02  8984.6  199.54  9539.6  200.98  9569.7  199.92  9842.1   213.3
 10043.8  217.77 10304.6  203.63 10391.9  204.37 10623.6  216.56 10680.7  215.36
 10707.8  222.46 10743.9  225.07 11091.4  232.54 11315.6   228.8 11559.3   236.3
 11834.9  229.42   12131  232.94 12290.5  227.44 12591.3  234.77 13057.2  236.75
#Mann= 9 ,-1 , 0
  -712.9     .17       0  -589.3     .11       0  -490.6     .17       0
     2.9     .11       0   146.7     .17       0   326.4    .015       0
  8698.1     .15       0  8885.2     .11       0  9539.6     .17       0
#XS Ineff= 1 ,-1
 10043.8   10830  217.77
Permanent Ineff=
       F
Bank Sta=326.4,8698.1
XS Rating Curve= 0 ,0
Exp/Cntr=0.3,0.1

Type RM Length L Ch R = 1 ,367000  ,1000,1000,1000
BEGIN DESCRIPTION:
WFSJ Main 364.0
END DESCRIPTION:
XS GIS Cut Line= 4
       3797535.6     10165051.56      3791836.71     10164766.93
      3787761.12     10165196.46      3784252.75     10167603.56
#Sta/Elev= 30
    -706  241.52  -631.4  238.54  -434.2  235.41  -335.6   234.8  -177.6  235.55
   152.2  224.11   182.9  219.17   256.2  214.02   312.8  210.13  366.95  206.91
   433.2  201.86    4999  199.08  9051.2  199.58  9174.9  203.45  9649.7  207.18
  9938.9   210.4 10405.6  222.37 10635.8  211.77   10809   209.1 11066.8  224.71
 11139.5  231.53 11203.6  230.55 11326.1  235.92 11708.5  228.99 11879.3  233.98
 12318.2  236.79 12599.1  233.52 13053.2  242.55 13189.1  244.06 13352.9  242.11
#Mann= 9 ,-1 , 0
    -706     .11       0  -631.4     .17       0  -434.2     .11       0
  -335.6     .17       0   152.2    .125       0   256.2     .17       0
   312.8     .11       0  366.95    .015       0  9649.7     .17       0
#XS Ineff= 1 ,-1
 10405.6   11070  222.37
Permanent Ineff=
       F
Bank Sta=366.95,9649.7
XS Rating Curve= 0 ,0
Exp/Cntr=0.3,0.1

Type RM Length L Ch R = 1 ,366000  ,1000,1000,1000
BEGIN DESCRIPTION:
WFSJ Main 363.0
END DESCRIPTION:
XS GIS Cut Line= 5
      3797559.91     10164516.83      3796441.87     10164030.72
      3791739.15     10163790.47      3787779.59     10164937.78
      3784083.37     10167396.46
#Sta/Elev= 30
    -928  237.78  -843.8   236.3  -825.2   235.5    -738  232.56  -554.9  228.18
  -284.5  218.23  -208.7  216.87  -102.9  213.39   -14.2  214.48       3  215.48
   318.5  228.51   417.1  229.02   672.3  211.86  715.88  206.73   785.8   202.1
    4999  198.86  9084.1  199.63    9134  204.72    9689  206.51 10639.9  226.42
 10742.1  226.41 11036.7  216.64 11355.3  232.44 11469.6  233.57 11592.8  226.21
   11701  225.09 12329.2  238.63 12775.7  237.48   13237  244.26 13561.7  243.69
#Mann= 16 ,-1 , 0
    -928     .11       0  -843.8     .17       0  -825.2     .11       0
    -738     .17       0  -554.9     .11       0  -284.5     .17       0
  -208.7     .11       0  -102.9     .17       0   -14.2     .11       0
       3     .17       0   318.5     .11       0   417.1     .17       0
   672.3     .11       0  715.88    .015       0    9689     .11       0
 10639.9     .17       0
#XS Ineff= 1 ,-1
    -575   386.3  229.11
Permanent Ineff=
       F
Bank Sta=715.88,9689
XS Rating Curve= 0 ,0
Exp/Cntr=0.3,0.1

Type RM Length L Ch R = 1 ,365000  ,1000,1000,1000
BEGIN DESCRIPTION:
WFSJ Main 362.0
END DESCRIPTION:
XS GIS Cut Line= 5
      3797644.97      10164443.9      3795797.77     10163107.11
      3791400.61     10162887.71      3786148.46     10163447.39
      3782794.27     10164723.44
#Sta/Elev= 30
 -1682.8  234.34 -1608.3  233.99 -1575.7  234.38 -1252.7  229.24  -897.1  225.23
  -778.5  221.12  -422.9  225.05  -304.4  224.55   -67.3  215.36   264.1  212.96
   358.5  217.38   400.2  223.68     551  223.29   734.7  209.86   757.5  206.51
   947.7  201.13    4999  199.27  9729.4  199.81  9986.1  205.74 10212.1  208.98
 10442.3   205.8 10477.8  199.81 10539.3  207.89 11007.1  225.78 11371.7  218.24
 11796.7  224.02   12781  229.77 13107.1  237.54 13515.7  230.08 13870.6  233.69
#Mann= 13 ,-1 , 0
 -1682.8     .11       0 -1608.3     .17       0 -1575.7     .11       0
 -1252.7     .17       0  -897.1     .11       0  -778.5     .17       0
  -422.9     .11       0  -304.4     .17       0   -67.3     .11       0
   734.7    .125       0   757.5    .015       0  9986.1     .11       0
 11371.7     .17       0
#XS Ineff= 1 ,-1
    -315   400.2  223.68
Permanent Ineff=
       F
Bank Sta=757.5,9986.1
XS Rating Curve= 0 ,0
Exp/Cntr=0.3,0.1

Type RM Length L Ch R = 1 ,364000  ,1000,1000,1000
BEGIN DESCRIPTION:
WFSJ Main 361.0
END DESCRIPTION:
XS GIS Cut Line= 4
      3797167.87     10159511.07       3790767.3     10162120.38
      3785905.41     10163350.17      3782782.49     10164601.76
#Sta/Elev= 30
   -1912  253.65 -1600.2  246.28 -1580.2  245.28 -1491.9  240.87 -1325.9  231.11
 -1155.4   222.1  -653.8  210.39 -583.06  206.69  -270.5  200.24  4998.9  199.36
  9207.9  200.15  9300.3  206.89  9434.9  211.75 10029.7  211.84   10077  206.74
 10484.4  228.14 10597.5  229.27 10896.1  223.24 11165.2  225.77 11644.1  218.51
 11682.2  213.89 11722.2  220.22 11829.8  222.97   11889  216.78 11937.4  223.54
 12059.3  218.96 12098.9  224.54 12176.9   221.8   12404  231.17 13379.4  239.69
#Mann= 10 ,-1 , 0
   -1912     .17       0 -1600.2     .11       0 -1580.2     .17       0
 -1491.9     .11       0 -1325.9     .17       0 -1155.4     .11       0
  -653.8     .11       0 -583.06    .015       0  9300.3     .11       0
  9434.9     .17       0
Bank Sta=-583.06,9300.3
XS Rating Curve= 0 ,0
Exp/Cntr=0.3,0.1