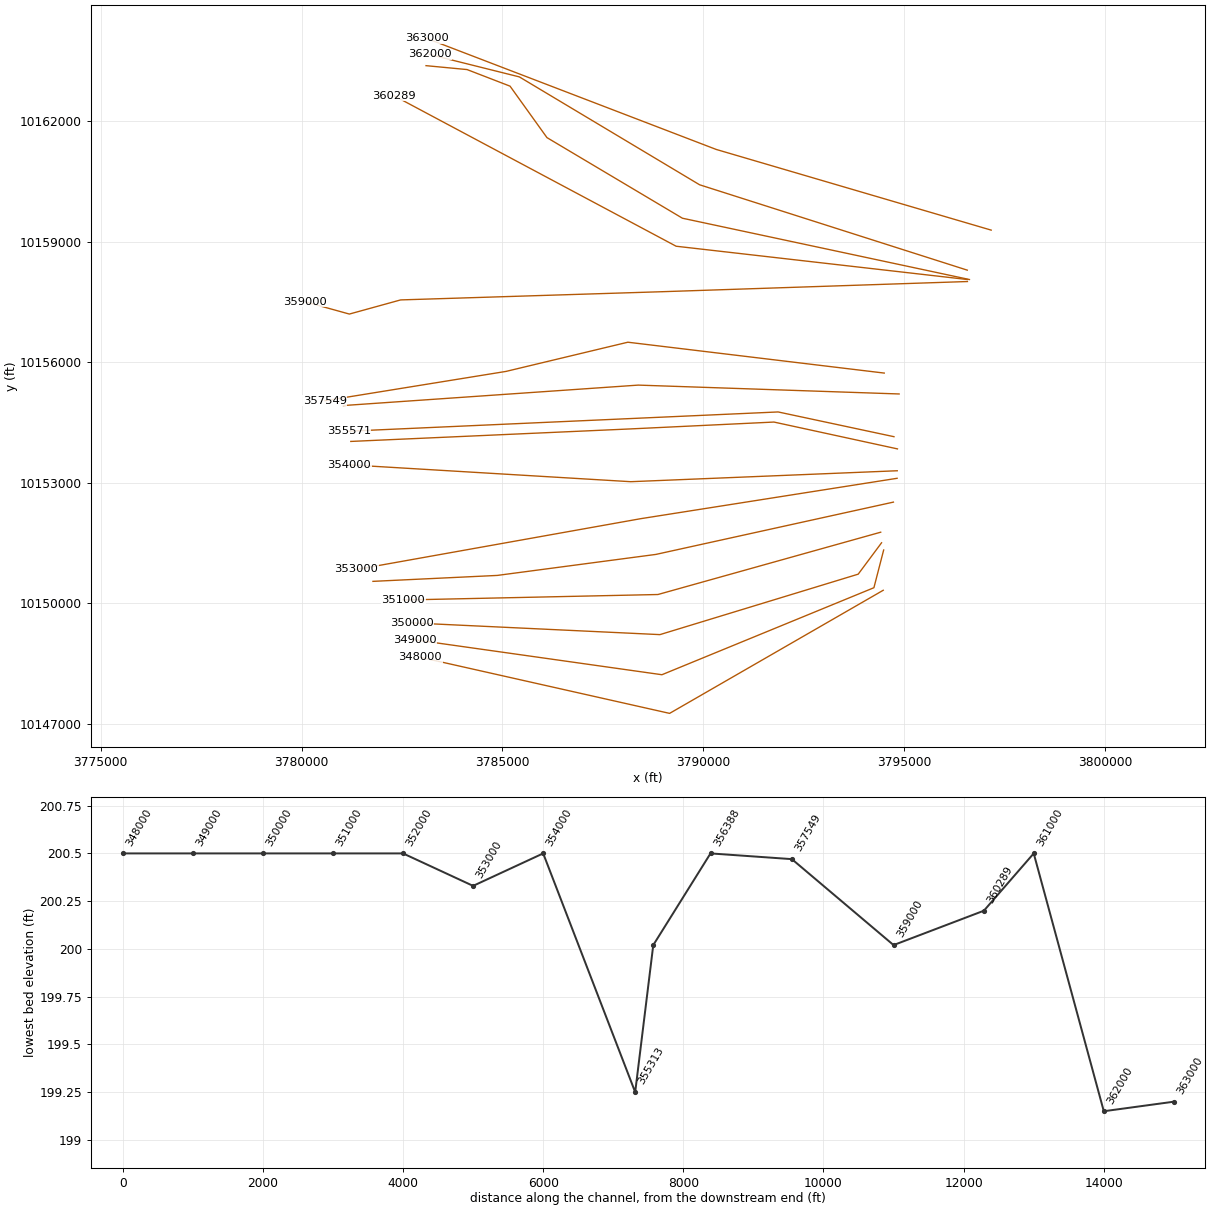
HEC-RAS study WFSJ Main.prj: WFSJ Main Base Level Engineering

--- WFSJ Main.g01 (geometry) --- (continued)

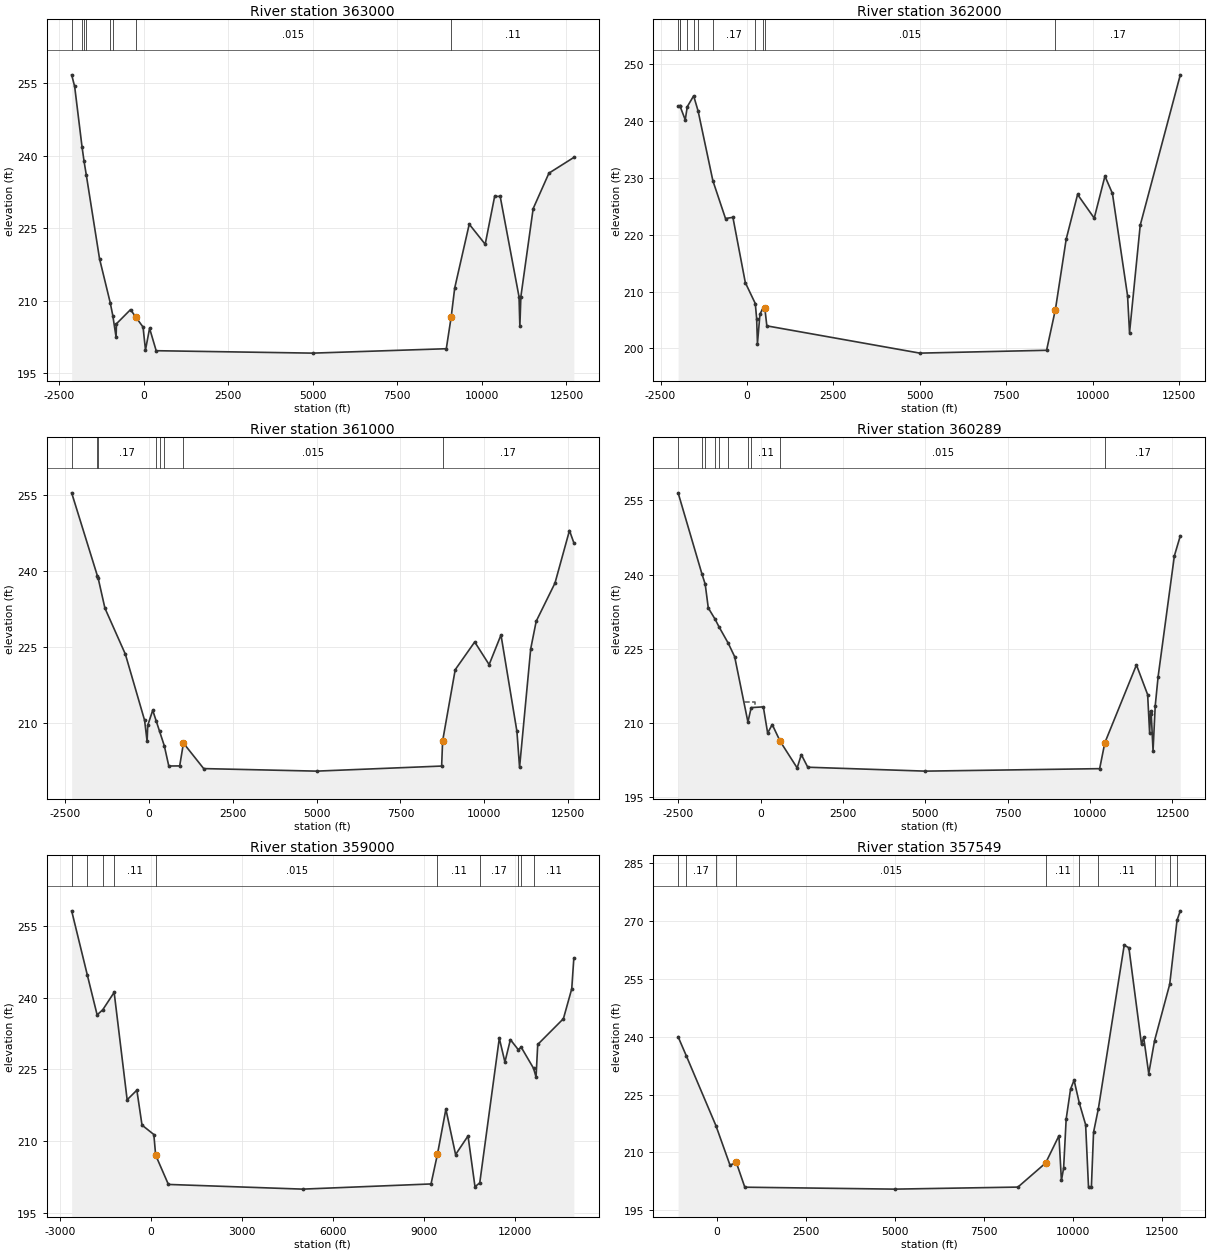
Type RM Length L Ch R = 1 ,363000  ,1000,1000,1000
BEGIN DESCRIPTION:
WFSJ Main 360.0
END DESCRIPTION:
XS GIS Cut Line= 3
      3797158.86     10159291.15      3790316.93     10161300.56
      3783110.24     10164067.19
#Sta/Elev= 30
 -2130.9  256.74 -2041.9  254.33   -1824  241.86 -1763.4  238.83 -1698.4  236.07
 -1306.5  218.72  -990.6  209.64  -913.5  206.94  -816.6  202.49  -806.2  205.27
  -389.3   208.2 -238.76  206.69   -19.5  204.59    52.5  199.85   173.5  204.33
   368.5   199.7  4998.9   199.2  8947.9  200.11  9092.6   206.7  9196.6  212.66
  9626.4  225.86 10098.3  221.71 10377.1  231.59 10541.1  231.61 11098.7  210.85
 11123.3  204.73 11153.3  210.88 11516.8  229.08   11983  236.41 12719.5  239.66
#Mann= 8 ,-1 , 0
 -2130.9     .11       0   -1824     .17       0 -1763.4     .11       0
 -1698.4     .17       0  -990.6     .11       0  -913.5     .11       0
 -238.76    .015       0  9092.6     .11       0
#XS Ineff= 1 ,-1
 10541.1   11825  231.61
Permanent Ineff=
       F
Bank Sta=-238.76,9092.6
XS Rating Curve= 0 ,0
Exp/Cntr=0.3,0.1

Type RM Length L Ch R = 1 ,362000  ,1000,1000,1000
BEGIN DESCRIPTION:
WFSJ Main 359.0
END DESCRIPTION:
XS GIS Cut Line= 4
       3796563.4     10158294.61       3789903.5      10160420.6
       3785419.3     10163107.11      3783183.29     10163666.12
#Sta/Elev= 30
   -1991  242.65 -1936.7  242.59 -1933.1   242.6 -1784.7  240.22 -1726.3  242.54
 -1541.8  244.45 -1412.1  241.76  -986.1  229.51  -620.5  222.85  -406.6  223.06
   -47.3  211.56     241  207.88   279.9  205.23   303.2  200.84   376.4  206.02
   450.8  206.92   515.7  207.13   574.8  203.95  4998.9  199.15  8664.9  199.65
 8919.86206.8153  9232.7  219.24  9561.3  227.08 10042.5  222.92 10352.6  230.31
   10569  227.27 11006.8  209.26 11063.8  202.75 11372.7  221.66 12532.2  248.15
#Mann= 11 ,-1 , 0
   -1991     .17       0 -1936.7     .11       0 -1933.1     .17       0
 -1726.3     .11       0 -1541.8     .17       0 -1412.1     .11       0
  -986.1     .17       0     241     .15       0   450.8     .11       0
   515.7    .015       0 8919.86     .17       0
#XS Ineff= 1 ,-1
 10352.6   11930  230.31
Permanent Ineff=
       F
Bank Sta=515.7,8919.86
XS Rating Curve= 0 ,0
Exp/Cntr=0.3,0.1

Type RM Length L Ch R = 1 ,361000  ,711,711,711
BEGIN DESCRIPTION:
WFSJ Main 358.0
END DESCRIPTION:
XS GIS Cut Line= 6
       3796617.9     10158061.06      3789476.66     10159587.73
      3786106.54     10161594.89      3785188.39     10162876.21
      3784118.95      10163289.4      3783098.13     10163386.63
#Sta/Elev= 30
 -2302.6  255.42 -1532.7  238.98 -1514.6  238.66 -1310.6  232.66  -701.2  223.58
  -127.8  210.53   -52.8  206.35     -34  209.52   114.5  212.51   215.1  210.47
   316.9   208.4   460.7  205.48   593.9  201.51   918.6  201.53  1031.1  206.03
  1634.4     201  4998.9   200.5  8729.2   201.5  8758.1  206.44    9134  220.52
    9715  225.99 10144.9  221.52 10498.8  227.37 10973.3  208.36 11052.5  201.24
 11385.1  224.64 11548.8  230.08 12108.5  237.61 12540.5  247.98 12670.8  245.56
#Mann= 8 ,-1 , 0
 -2302.6     .17       0 -1532.7     .11       0 -1514.6     .17       0
   215.1     .11       0   316.9     .17       0   460.7     .11       0
  1031.1    .015       0  8758.1     .17       0
#XS Ineff= 1 ,-1
 10498.8   11630  227.37
Permanent Ineff=
       F
Bank Sta=1031.1,8758.1
XS Rating Curve= 0 ,0
Exp/Cntr=0.3,0.1

Type RM Length L Ch R = 1 ,360289  ,1289,1289,1289
BEGIN DESCRIPTION:
WFSJ Main 357.0
END DESCRIPTION:
XS GIS Cut Line= 3
      3796567.81     10158061.08      3789320.34      10158890.1
      3782308.15     10162633.17
#Sta/Elev= 30
 -2503.9  256.54 -1781.9  240.14 -1682.1  238.05   -1588  233.23 -1382.8  230.97
 -1265.7  229.45  -983.8  226.11    -788  223.38  -385.2  210.15  -285.4  213.06
    82.8  213.21   213.7  207.91   352.7  209.63   596.1  206.21  1109.5  200.85
  1235.5  203.55  1431.6  200.99  4998.9   200.2 10291.4   200.7 10448.3  205.93
 11407.9   221.7 11747.8  215.69   11808  207.93 11835.6   212.4 11857.5  211.72
 11912.1  204.34 11977.9  213.39 12065.7  219.32 12559.3  243.78 12739.5  247.84
#Mann= 10 ,-1 , 0
 -2503.9     .17       0 -1781.9     .11       0 -1682.1     .17       0
 -1382.8     .11       0 -1265.7     .17       0  -983.8     .11       0
  -385.2     .17       0  -285.4     .11       0   596.1    .015       0
 10448.3     .17       0
#XS Ineff= 2 ,-1
 11407.9   12155   221.7    -515    -173  214.15
Permanent Ineff=
       F       F
Bank Sta=596.1,10448.3
XS Rating Curve= 0 ,0
Exp/Cntr=0.3,0.1

Type RM Length L Ch R = 1 ,359000  ,1451,1451,1451
BEGIN DESCRIPTION:
WFSJ Main 356.0
END DESCRIPTION:
XS GIS Cut Line= 5
      3796567.88     10158011.07      3788951.12     10157756.88
      3782466.17     10157553.29      3781190.13     10157200.86
       3780096.4     10157504.68
#Sta/Elev= 30
   -2621  258.12 -2106.4  244.78 -1780.5   236.4   -1595  237.46 -1218.9   241.1
    -790  218.67  -469.8  220.68  -299.7  213.39    90.5  211.42   150.6  207.11
   570.8     201  4998.8  200.02  9235.4   201.1  9445.5  207.25  9725.6  216.71
 10045.8  207.24   10456  211.12 10686.1  200.52 10843.1  201.33 11488.1  231.52
 11673.1  226.56   11854  231.23 12110.7  229.16   12212  229.63 12617.2  225.25
 12700.2  223.42   12756  230.22 13603.1   235.6 13877.9  241.84 13947.1  248.26
#Mann= 10 ,-1 , 0
   -2621     .17       0 -2106.4     .11       0   -1595     .17       0
 -1218.9     .11       0   150.6    .015       0  9445.5     .11       0
 10843.1     .17       0 12110.7     .11       0   12212     .17       0
 12617.2     .11       0
#XS Ineff= 1 ,-1
  9725.6   11300  216.71
Permanent Ineff=
       F
Bank Sta=150.6,9445.5
XS Rating Curve= 0 ,0
Exp/Cntr=0.3,0.1

Type RM Length L Ch R = 1 ,357549  ,1161,1161,1161
BEGIN DESCRIPTION:
WFSJ Main 355.0
END DESCRIPTION:
XS GIS Cut Line= 4
      3794497.82     10155731.25      3788118.95     10156499.91
      3785087.27     10155772.61      3780582.47     10155042.51
#Sta/Elev= 30
 -1082.2  239.97  -855.8  235.11   -20.9  216.94   376.2  206.66   550.4  207.43
   791.2  200.97  4998.8  200.47  8462.8     201 9240.45  207.23  9614.8   214.3
  9684.8  202.71  9746.5  205.91  9818.2  218.65  9941.5  226.41 10040.3  228.71
 10187.3  222.78 10364.5  217.18 10445.5     201 10526.5     201 10587.3  215.22
 10723.3  221.37 11448.4  263.72 11580.1  263.04 11934.4  237.99 11995.5   239.8
 12137.3  230.42 12300.5  238.95 12726.4  253.58 12932.8  270.21 13024.1  272.62
#Mann= 10 ,-1 , 0
 -1082.2     .11       0  -855.8     .17       0   -20.9     .11       0
   550.4    .015       0 9240.45     .11       0 10187.3    .125       0
 10723.3     .11       0 12300.5     .17       0 12726.4     .11       0
 12932.8     .17       0
#XS Ineff= 2 ,-1
  9614.8    9840   214.3 10040.3   10950  228.71
Permanent Ineff=
       F       F
Bank Sta=550.4,9240.45
XS Rating Curve= 0 ,0
Exp/Cntr=0.3,0.1

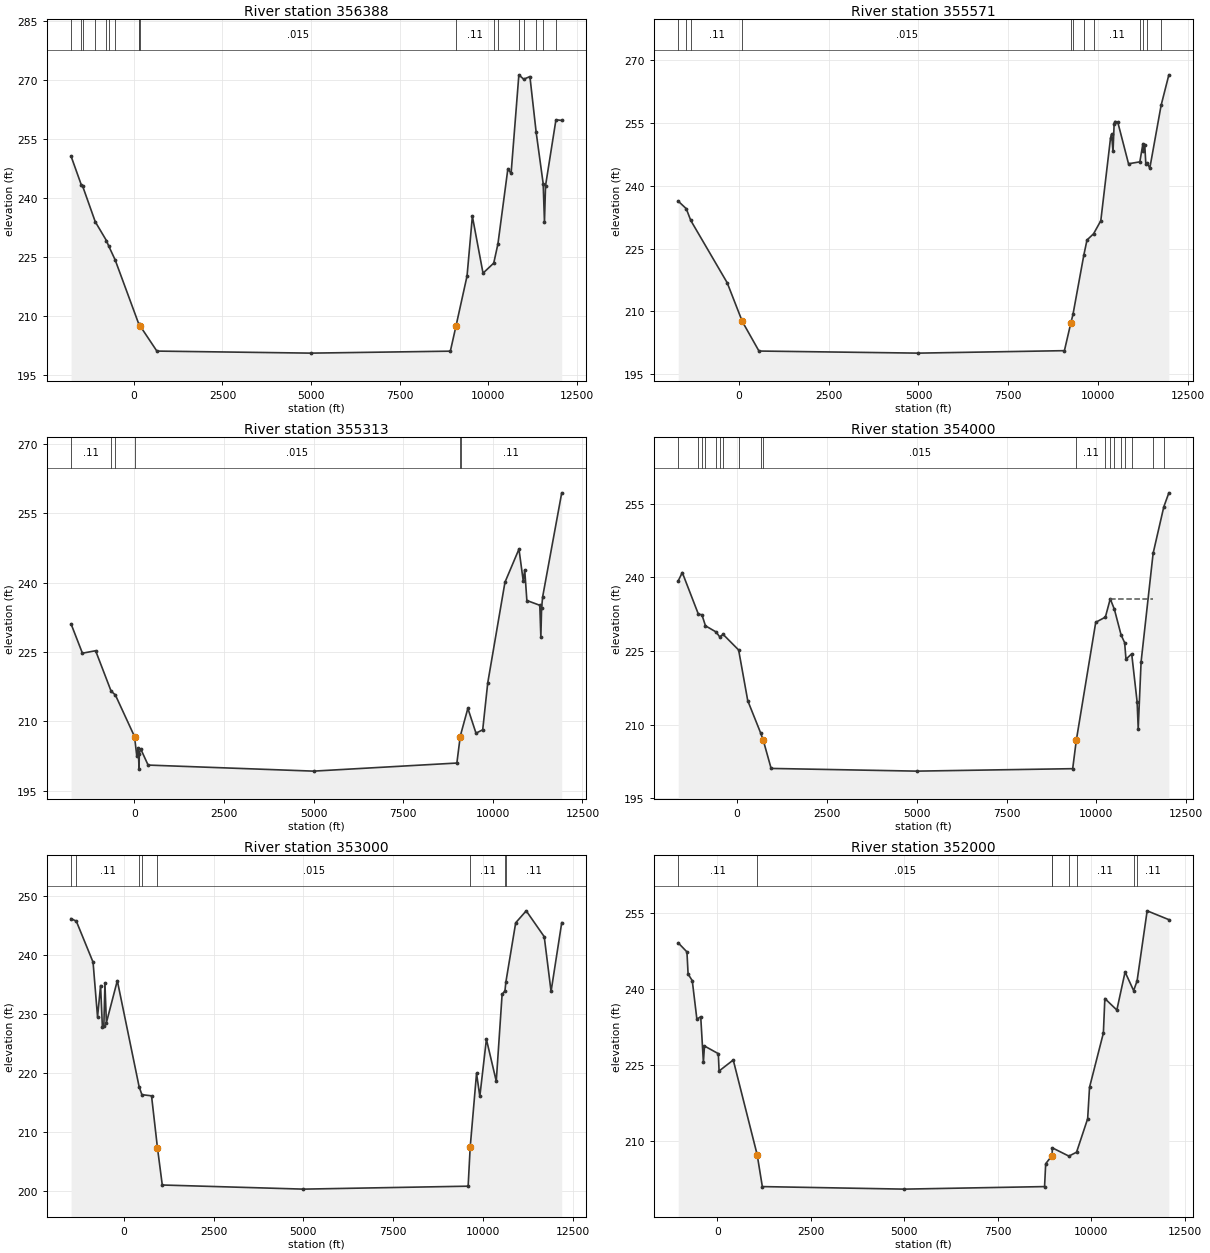
Type RM Length L Ch R = 1 ,356388  ,817,817,817
BEGIN DESCRIPTION:
WFSJ Main 354.0
END DESCRIPTION:
XS GIS Cut Line= 3
      3794867.88     10155211.07       3788378.5     10155431.77
      3781042.07     10154922.71
#Sta/Elev= 30
 -1772.8  250.66 -1485.6  243.39 -1443.2  242.95 -1090.1  233.96  -774.5  229.16
  -715.3  227.87  -529.7  224.27   142.4  207.81     149  207.61   168.4  207.52
   648.6  201.02  4998.8   200.5  8931.1     201 9089.37  207.36  9402.2  220.14
  9552.6  235.35  9853.3  220.87 10155.6  223.43 10273.9  228.32   10555  247.49
 10645.2  246.26 10864.8  271.39 11001.6  270.27 11176.5  270.95 11353.4  256.71
 11550.7  243.68 11587.4   233.9 11617.5  243.15 11911.6  259.95 12074.4  259.77
#Mann= 18 ,-1 , 0
 -1772.8     .11       0 -1485.6     .17       0 -1443.2     .11       0
 -1090.1     .17       0  -774.5     .11       0  -715.3     .17       0
  -529.7     .11       0   142.4     .17       0     149     .11       0
   168.4    .015       0 9089.37     .11       0 10155.6    .125       0
 10273.9     .11       0 10864.8    .125       0 11001.6     .11       0
 11353.4    .125       0 11550.7     .11       0 11911.6     .17       0
Bank Sta=168.4,9089.37
XS Rating Curve= 0 ,0
Exp/Cntr=0.3,0.1

Type RM Length L Ch R = 1 ,355571  ,258,258,258
BEGIN DESCRIPTION:
WFSJ Main 353.0
END DESCRIPTION:
XS GIS Cut Line= 3
      3794740.02     10154147.05       3791858.1     10154763.36
      3781177.93     10154284.19
#Sta/Elev= 30
 -1677.9  236.35 -1454.4  234.55 -1328.3  231.73  -315.6  216.83   103.7  207.58
   566.9  200.52  4998.8  200.02  9057.3  200.61  9236.6  207.27    9295  209.26
  9598.2  223.52    9685  227.06  9867.8  228.55 10068.3  231.66 10338.6  251.41
 10368.6  252.31 10408.6  248.23 10438.7  254.78 10458.7  255.38 10538.8  255.27
 10839.1  245.28 11153.4  245.74 11239.5  250.09 11252.1  248.24 11289.5  249.83
 11319.5  245.33 11364.8  245.44 11429.6  244.19 11745.1  259.26 11960.1  266.54
#Mann= 12 ,-1 , 0
 -1677.9     .11       0 -1454.4     .17       0 -1328.3     .11       0
   103.7    .015       0  9236.6    .125       0    9295     .11       0
  9598.2    .125       0  9867.8     .11       0 11153.4     .17       0
 11252.1     .11       0 11364.8     .17       0 11745.1     .11       0
Bank Sta=103.7,9236.6
XS Rating Curve= 0 ,0
Exp/Cntr=0.3,0.1

Type RM Length L Ch R = 1 ,355313  ,1313,1313,1313
BEGIN DESCRIPTION:
WFSJ Main 352.0
END DESCRIPTION:
XS GIS Cut Line= 4
      3794826.82     10153843.23      3791753.93     10154511.63
      3788125.46     10154338.02      3781226.54     10154028.99
#Sta/Elev= 30
 -1761.9   231.1 -1445.7  224.77 -1077.3   225.3    -646  216.57  -526.6  215.73
     7.5  206.74    68.9  202.62   109.8  204.24   134.4  199.75   140.5  203.04
   178.4  204.08   386.1  200.56  4998.8  199.25  8997.1     201  9087.1  206.53
  9102.2  207.12  9303.6  212.84  9530.4  207.46  9717.8   208.2  9857.9  218.34
 10338.4  240.12 10728.8   247.3 10848.9  240.34   10889  242.82   10949  236.17
 11309.4  235.14 11339.4  228.22 11359.4  234.48 11389.5  236.98 11921.3  259.47
#Mann= 6 ,-1 , 0
 -1761.9     .11       0    -646     .17       0  -526.6     .11       0
     7.5    .015       0  9087.1    .125       0  9102.2     .11       0
Bank Sta=7.5,9087.1
XS Rating Curve= 0 ,0
Exp/Cntr=0.3,0.1

Type RM Length L Ch R = 1 ,354000  ,1000,1000,1000
BEGIN DESCRIPTION:
WFSJ Main 351.0
END DESCRIPTION:
XS GIS Cut Line= 3
      3794821.32      10153298.9      3788191.22     10153026.34
      3781186.72     10153446.65
#Sta/Elev= 30
 -1635.7  239.27 -1522.1  240.98 -1074.5  232.49  -975.9  232.37  -877.3  230.12
  -581.5  228.86  -482.9  227.88  -384.3  228.36    45.9  225.19   299.4  214.86
   658.1  208.28   729.8  206.83   949.9  201.05  4998.8   200.5  9341.2     201
  9441.3  206.76  9982.3  230.83 10250.6  231.89 10386.5  235.61 10502.2  233.46
 10687.6  228.26 10786.7  226.68 10823.8  223.31 10983.1  224.41 11134.4  214.58
 11164.4  209.16 11244.6  222.77 11579.4   244.9 11876.7  254.37 12017.1  257.22
#Mann= 19 ,-1 , 0
 -1635.7     .11       0 -1074.5     .17       0  -975.9     .11       0
  -877.3     .17       0  -581.5     .11       0  -482.9     .17       0
  -384.3     .11       0    45.9     .15       0   658.1    .125       0
   729.8    .015       0  9441.3     .11       0 10250.6    .125       0
 10386.5     .11       0 10502.2    .125       0 10687.6     .11       0
 10786.7    .125       0 10983.1     .11       0 11579.4    .125       0
 11876.7     .11       0
#XS Ineff= 1 ,-1
   10383   11575  235.66
Permanent Ineff=
       F
Bank Sta=729.8,9441.3
XS Rating Curve= 0 ,0
Exp/Cntr=0.3,0.1

Type RM Length L Ch R = 1 ,353000  ,1000,1000,1000
BEGIN DESCRIPTION:
WFSJ Main 350.0
END DESCRIPTION:
XS GIS Cut Line= 3
      3794817.83     10153111.07      3788435.78     10152104.73
      3781366.11     10150840.03
#Sta/Elev= 30
 -1460.9  246.22 -1315.3   245.8  -849.7  238.84  -724.8  229.53  -640.9  234.88
  -589.7   227.8  -549.8  227.99  -519.4  235.23  -478.9  228.57  -175.2   235.7
   430.9  217.71   508.2  216.36   776.4  216.16  941.01207.3317    1075  201.03
  4998.8  200.33  9579.5  200.83 9636.36  207.42  9813.1  219.98  9904.6  216.07
 10087.4  225.76 10361.7  218.64 10524.3  233.39 10603.2  233.95 10627.4  235.41
 10901.8  245.52 11194.7  247.55 11695.5  243.16 11885.5  233.87 12181.9  245.54
#Mann= 8 ,-1 , 0
 -1460.9    .125       0 -1315.3     .11       0   430.9     .15       0
   508.2     .11       0  941.01    .015       0 9636.36     .11       0
 10603.2    .125       0 10627.4     .11       0
Bank Sta=941.01,9636.36
XS Rating Curve= 0 ,0
Exp/Cntr=0.3,0.1

Type RM Length L Ch R = 1 ,352000  ,1000,1000,1000
BEGIN DESCRIPTION:
WFSJ Main 349.0
END DESCRIPTION:
XS GIS Cut Line= 4
      3794726.28     10152517.97      3788817.29     10151215.67
      3784869.74     10150692.29      3781777.66     10150544.55
#Sta/Elev= 30
 -1050.8  249.06  -816.9  247.27  -786.2  242.91  -674.5   241.6  -550.7  233.99
  -448.3   234.5  -376.6  225.52    -348  228.72    22.2  227.21    43.3  223.79
   422.1  225.96 1061.36  207.31  1200.4     201  4998.8   200.5    8752     201
  8782.2  205.51 8952.84  207.12  8959.9  208.64  9402.9  207.01  9607.8  207.78
    9905  214.38  9955.3  220.58 10325.5  231.27 10365.1  238.08 10685.9  235.81
 10906.2  243.31 11135.2  239.64 11227.9  241.56 11496.8  255.37 12077.7  253.63
#Mann= 8 ,-1 , 0
 -1050.8     .11       0 1061.36    .015       0 8952.84    .125       0
  8959.9     .11       0  9402.9    .125       0  9607.8     .11       0
 11135.2    .125       0 11227.9     .11       0
Bank Sta=1061.36,8952.84
XS Rating Curve= 0 ,0
Exp/Cntr=0.3,0.1

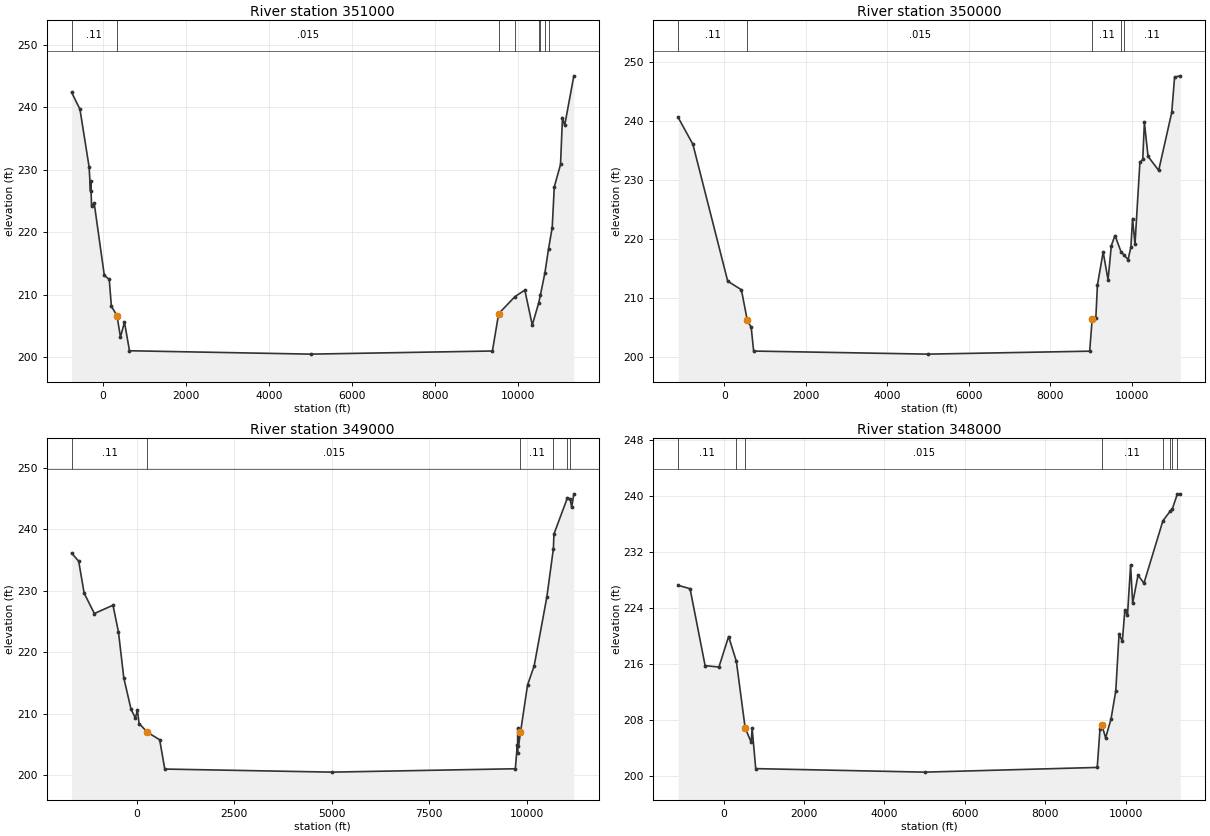
Type RM Length L Ch R = 1 ,351000  ,1000,1000,1000
BEGIN DESCRIPTION:
WFSJ Main 348.0
END DESCRIPTION:
XS GIS Cut Line= 3
      3794409.69      10151768.7      3788867.13     10150216.91
        3782527.     10150080.22
#Sta/Elev= 30
  -755.7   242.4  -555.9  239.71  -335.6   230.5  -301.5  226.61  -296.3  228.24
  -276.1  224.18  -213.8  224.72    31.6  213.09   149.7  212.48   201.6  208.16
   336.6  206.67   419.7  203.23   516.7  205.62   637.7  201.04  4998.8   200.5
  9380.3     201  9530.3  206.97  9922.5  209.71 10160.5  210.75 10340.5  205.16
 10494.7  208.69 10535.3  209.92 10644.2   213.5 10733.3   217.4 10820.6  220.76
 10870.6  227.28 11020.7  230.87 11067.8  238.38 11120.7  237.11 11341.6  245.06
#Mann= 8 ,-1 , 0
  -755.7     .11       0   336.6    .015       0  9530.3     .11       0
  9922.5     .11       0 10494.7    .125       0 10535.3     .11       0
 10644.2    .125       0 10733.3     .11       0
Bank Sta=336.6,9530.3
XS Rating Curve= 0 ,0
Exp/Cntr=0.3,0.1

Type RM Length L Ch R = 1 ,350000  ,1000,1000,1000
BEGIN DESCRIPTION:
WFSJ Main 347.0
END DESCRIPTION:
XS GIS Cut Line= 4
      3794430.81     10151504.86      3793850.41     10150723.95
      3788916.97     10149218.15      3782737.97     10149510.35
#Sta/Elev= 30
 -1131.1  240.64  -768.5  236.08      85  212.88   420.9  211.41     566  206.22
     661  205.06   721.4  201.02  4998.8   200.5  8963.5     201  9023.6  206.43
  9113.7   206.6  9153.8  212.24  9293.9  217.81    9414  213.08  9494.1   218.9
  9584.2  220.61  9731.3  217.87  9798.6  217.38  9904.6  216.51  9974.7  218.68
 10014.7  223.48 10074.8  219.15 10194.9  233.02   10265  233.51   10305  239.78
 10395.1  234.03 10655.4  231.65 10975.8  241.48 11045.9  247.48 11185.9  247.69
#Mann= 5 ,-1 , 0
 -1131.1     .11       0     566    .015       0  9023.6     .11       0
  9731.3    .125       0  9798.6     .11       0
Bank Sta=566,9023.6
XS Rating Curve= 0 ,0
Exp/Cntr=0.3,0.1

Type RM Length L Ch R = 1 ,349000  ,1000,1000,1000
BEGIN DESCRIPTION:
WFSJ Main 346.0
END DESCRIPTION:
XS GIS Cut Line= 4
      3794483.59     10151325.46      3794240.87     10150386.25
      3788966.81      10148219.4      3782822.63      10149088.2
#Sta/Elev= 30
 -1671.9  236.14 -1491.8  234.83 -1350.8  229.61   -1089  226.31  -612.1  227.66
  -471.5  223.31  -334.7  215.83  -150.7  210.78   -38.6  209.31      15  210.56
    57.3  208.41   270.6  206.99   585.3  205.77   715.9     201  4998.8   200.5
  9705.3  201.05  9755.8  204.95  9761.2  203.64  9766.3  207.63  9786.1  204.68
  9837.4  206.99 10018.4  214.68 10187.6  217.78 10513.3  229.01 10680.6  236.84
 10695.1  239.25 11042.3  245.16 11110.9  244.93 11149.5  243.61 11205.3  245.79
#Mann= 6 ,-1 , 0
 -1671.9     .11       0   270.6    .015       0  9837.4     .11       0
 10680.6    .125       0 11042.3     .11       0 11110.9    .125       0
Bank Sta=270.6,9837.4
XS Rating Curve= 0 ,0
Exp/Cntr=0.3,0.1

Type RM Length L Ch R = 1 ,348000  ,1000,1000,1000
BEGIN DESCRIPTION:
WFSJ Main 345.0
END DESCRIPTION:
XS GIS Cut Line= 3
      3794473.02     10150322.92      3789157.79     10147256.97
      3782951.01     10148655.12
#Sta/Elev= 30
 -1136.1  227.18    -839   226.7  -464.1  215.71  -120.9  215.51   120.4  219.87
   313.5  216.33   532.3  206.81   683.5  204.76   705.4  206.79   795.5     201
  4998.8   200.5  9294.9  201.17    9363  206.63  9411.4  207.21    9503  205.39
  9637.9  208.09  9756.2   212.1  9838.2  220.24  9920.2  219.18  9981.7  223.63
 10047.7  222.88 10125.2  230.06 10176.5  224.62 10309.7  228.63 10457.5  227.49
 10929.5   236.4 11117.5  237.83 11162.6  238.08 11289.9  240.25 11362.3  240.17
#Mann= 8 ,-1 , 0
 -1136.1     .11       0   313.5    .125       0   532.3    .015       0
  9411.4     .11       0 10929.5    .125       0 11117.5     .11       0
 11162.6    .125       0 11289.9     .11       0
Bank Sta=532.3,9411.4
XS Rating Curve= 0 ,0
Exp/Cntr=0.3,0.1