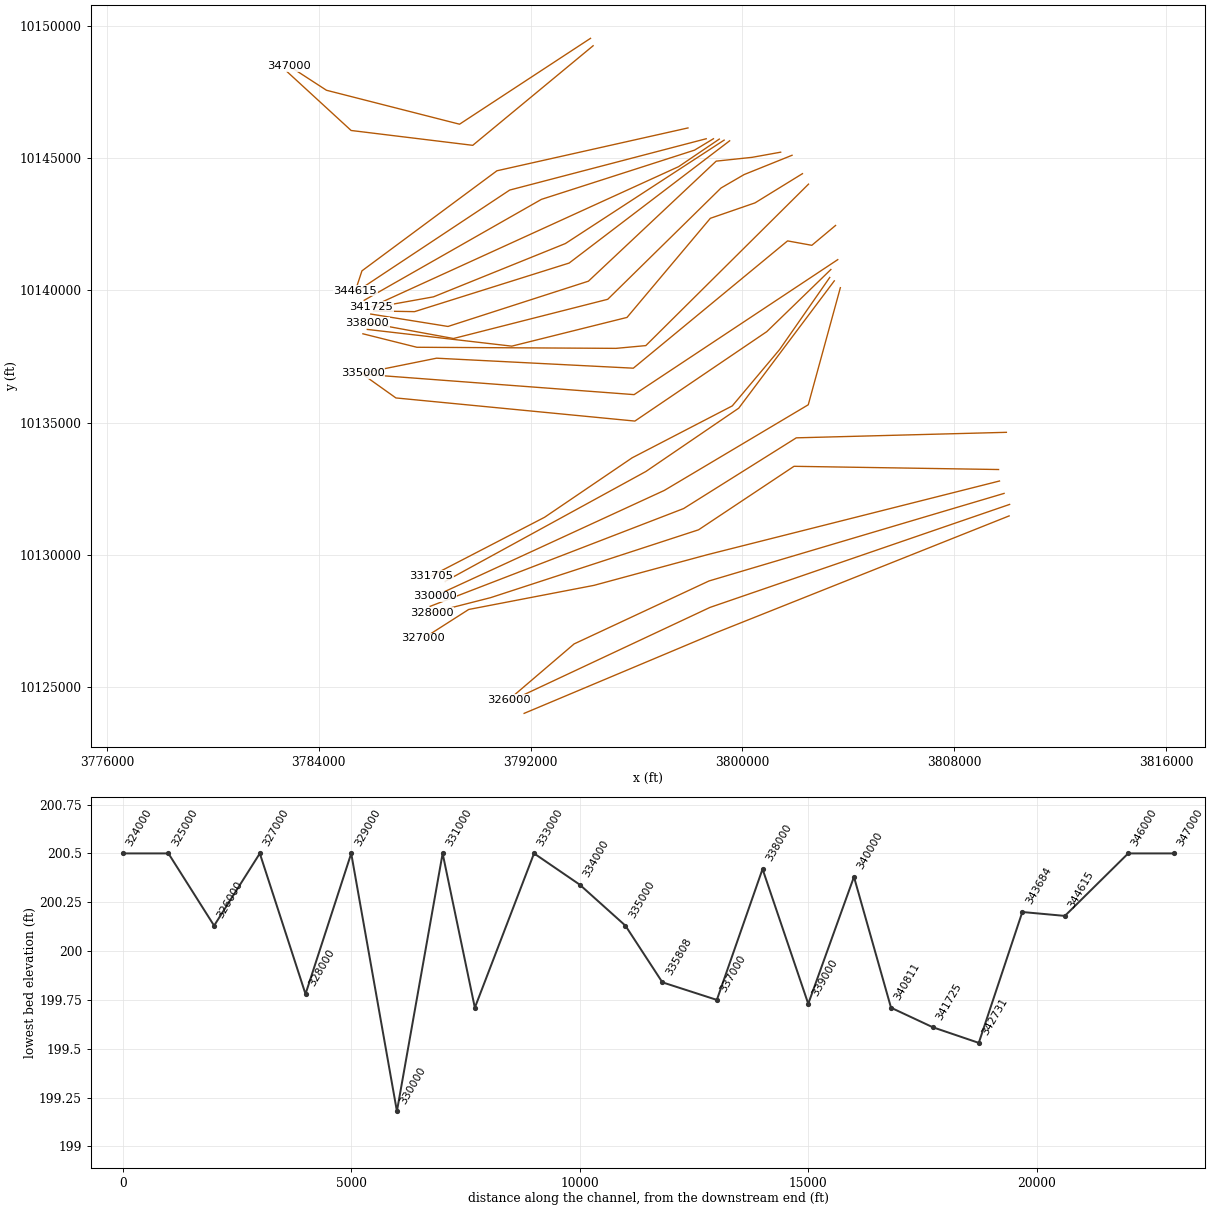
HEC-RAS study WFSJ Main.prj: WFSJ Main Base Level Engineering

--- WFSJ Main.g01 (geometry) --- (continued)

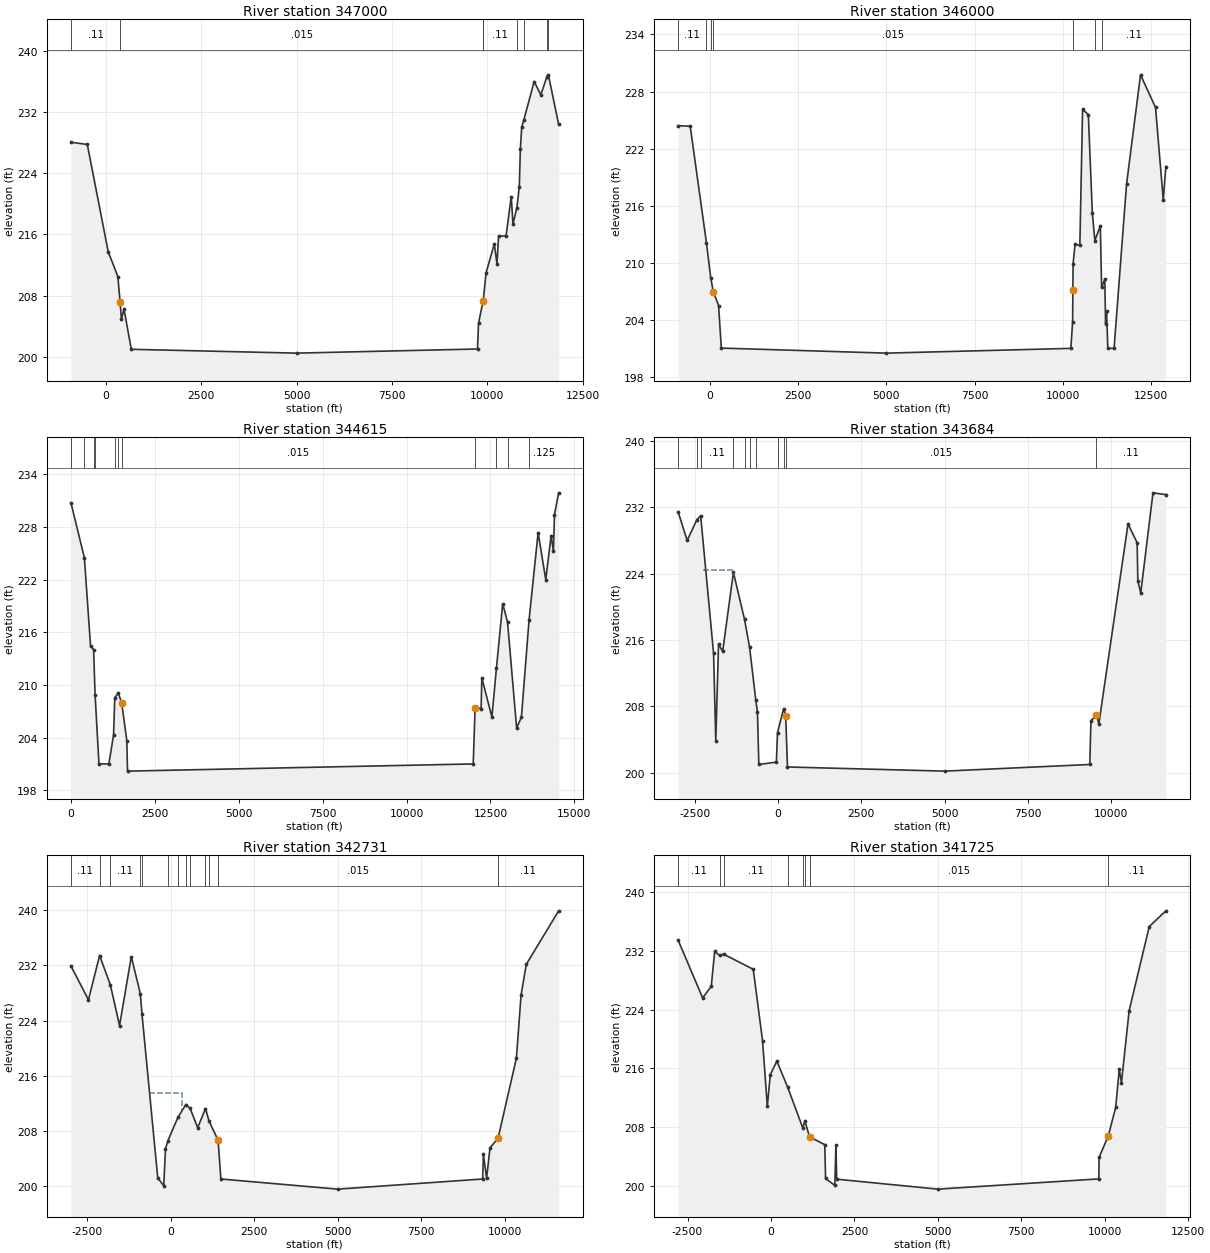
Type RM Length L Ch R = 1 ,347000  ,1000,1000,1000
BEGIN DESCRIPTION:
WFSJ Main 344.0
END DESCRIPTION:
XS GIS Cut Line= 5
        3794262.     10149531.47      3793955.94     10149330.95
      3789315.35     10146285.43      3784289.32     10147568.58
      3782875.68      10148486.4
#Sta/Elev= 30
  -916.6  228.05  -487.2  227.76    61.3  213.75   314.5  210.49   371.7  207.23
   407.9  204.92   474.3  206.27   667.1     201  4998.8   200.5    9745  201.04
  9771.8  204.39  9889.2  207.27  9896.5  207.41  9970.9  211.01 10185.4  214.76
 10255.3  212.16 10297.5  215.77 10493.9  215.82 10630.1  220.96 10675.2  217.35
 10778.1  219.51 10841.3  222.25 10868.6  227.12 10904.6  230.04 10958.7  230.94
 11230.8  235.98 11405.1  234.25 11565.5  236.62 11603.6  236.86 11872.7  230.38
#Mann= 8 ,-1 , 0
  -916.6     .11       0   371.7    .015       0  9889.2    .125       0
  9896.5     .11       0 10778.1    .125       0 10958.7     .11       0
 11565.5    .125       0 11603.6     .11       0
Bank Sta=371.7,9889.2
XS Rating Curve= 0 ,0
Exp/Cntr=0.3,0.1

Type RM Length L Ch R = 1 ,346000  ,1385,1385,1385
BEGIN DESCRIPTION:
WFSJ Main 343.0
END DESCRIPTION:
XS GIS Cut Line= 4
       3794360.6     10149251.13      3789813.75     10145486.77
        3785220.     10146048.04      3782798.16     10148274.57
#Sta/Elev= 30
  -902.9  224.41  -560.5  224.36  -101.9  212.13    22.3  208.38    93.4  206.97
   243.1   205.5     321  201.03  4998.8   200.5 10226.3     201 10275.6  203.79
   10283 207.128 10289.8  209.91 10346.5  211.95 10480.9  211.83 10558.6  226.12
 10721.4  225.58 10834.8  215.21 10906.9  212.34 11061.1  213.87 11097.7   207.4
 11188.7  208.27 11209.7   203.6   11238  204.91 11273.8     201 11450.7     201
 11804.2  218.26 12200.4  229.76 12625.2  226.33 12844.7  216.61 12917.7  220.12
#Mann= 7 ,-1 , 0
  -902.9     .11       0  -101.9    .125       0    22.3     .11       0
    93.4    .015       0   10283     .11       0 10906.9    .125       0
 11097.7     .11       0
#XS Ineff= 1 ,-1
 10721.4   12160  225.58
Permanent Ineff=
       F
Bank Sta=93.4,10283
XS Rating Curve= 0 ,0
Exp/Cntr=0.3,0.1

Type RM Length L Ch R = 1 ,344615  ,931,931,931
BEGIN DESCRIPTION:
WFSJ Main 341.0
END DESCRIPTION:
XS GIS Cut Line= 4
      3797943.17     10146144.12      3790727.81      10144524.6
      3785629.03     10140741.25      3785382.48     10139991.81
#Sta/Elev= 30
       0  230.75     401  224.48   584.6  214.45   676.4  214.01   719.7   208.9
   835.6     201  1130.2     201  1270.4   204.3    1307  208.53  1410.6  209.09
    1512  207.95  1665.8  203.65  1686.3  200.18   11987     201 12043.3  207.38
 12222.8  207.31 12243.7  210.79 12544.1  206.35 12679.7  211.94 12865.4  219.25
 13009.4  217.16 13280.7  205.11 13422.5   206.3   13652  217.45 13920.8  227.33
 14148.6  221.99 14307.6  226.99 14376.4  225.23 14408.2  229.39 14532.4  231.88
#Mann= 11 ,-1 , 0
       0     .11       0     401     .12       0   676.4    .125       0
   719.7     .11       0    1307    .125       0  1410.6     .11       0
    1512    .015       0 12043.3     .11       0 12679.7    .125       0
 13009.4     .11       0   13652    .125       0
#XS Ineff= 2 ,-1
 12865.4   13750  219.25 12243.7   12710  210.79
Permanent Ineff=
       F       F
Bank Sta=1512,12043.3
XS Rating Curve= 0 ,0
Exp/Cntr=0.3,0.1

Type RM Length L Ch R = 1 ,343684  ,953,953,953
BEGIN DESCRIPTION:
WFSJ Main 341.0
END DESCRIPTION:
XS GIS Cut Line= 3
      3798631.51     10145735.55      3791209.59     10143795.43
      3785401.78     10139942.02
#Sta/Elev= 30
 -2999.6  231.45 -2728.6     228 -2437.1  230.49 -2323.3  230.97 -1935.2  214.39
 -1869.2  203.82 -1786.5   215.5 -1662.5  214.63 -1339.8  224.15 -1006.9  218.49
  -855.1  215.14  -668.3  208.76  -618.5  207.34  -577.2     201   -50.1  201.29
   -16.4  204.83   167.9  207.73     229  206.85     283   200.7  4998.7   200.2
  9357.7     201  9393.8  206.29  9559.2  206.93  9631.4  205.92 10506.2  229.99
 10780.2  227.72 10801.2  223.11 10888.5  221.67 11255.4  233.74 11641.6  233.53
#Mann= 11 ,-1 , 0
 -2999.6     .11       0 -2437.1    .125       0 -2323.3     .11       0
 -1339.8    .125       0 -1006.9     .11       0  -855.1    .125       0
  -668.3     .11       0   -16.4    .125       0   167.9     .11       0
     229    .015       0  9559.2     .11       0
#XS Ineff= 1 ,-1
   -2250   -1311  224.38
Permanent Ineff=
       F
Bank Sta=229,9559.2
XS Rating Curve= 0 ,0
Exp/Cntr=0.3,0.1

Type RM Length L Ch R = 1 ,342731  ,1006,1006,1006
BEGIN DESCRIPTION:
WFSJ Main 340.0
END DESCRIPTION:
XS GIS Cut Line= 4
      3798904.89     10145735.53      3798189.34     10145304.01
       3792407.5     10143443.87       3785714.8     10139628.77
#Sta/Elev= 30
   -2993  231.92 -2468.2  227.01 -2133.6  233.43 -1809.6  229.14 -1536.1  223.26
 -1184.4  233.28  -912.2  227.86  -864.4  224.95    -391  201.15  -212.5  200.03
  -159.9  205.37   -88.4  206.55   212.9  209.94   450.9  211.81   578.5  211.25
   804.2  208.44  1038.2  211.22  1149.1  209.35  1415.8  206.64  1499.8     201
  4998.7  199.53  9343.4     201    9365  204.62  9461.5   201.1  9563.8  205.53
  9805.8  206.93 10354.7  218.53 10494.4  227.69 10649.6  232.14   11620  239.92
#Mann= 13 ,-1 , 0
   -2993     .11       0 -2133.6    .125       0 -1809.6     .11       0
  -912.2    .125       0  -864.4     .11       0   -88.4    .125       0
   212.9     .11       0   450.9    .125       0   578.5     .11       0
  1038.2    .125       0  1149.1     .11       0  1415.8    .015       0
  9805.8     .11       0
#XS Ineff= 1 ,-1
    -665   333.8  213.44
Permanent Ineff=
       F
Bank Sta=1415.8,9805.8
XS Rating Curve= 0 ,0
Exp/Cntr=0.3,0.1

Type RM Length L Ch R = 1 ,341725  ,914,914,914
BEGIN DESCRIPTION:
WFSJ Main 339.0
END DESCRIPTION:
XS GIS Cut Line= 4
      3799126.24     10145722.51      3797589.73     10144680.98
      3792772.09     10142480.33      3785988.21     10139381.36
#Sta/Elev= 30
 -2783.4  233.42 -2048.4  225.57 -1790.2  227.16 -1688.4  231.88 -1538.1  231.34
 -1421.8  231.52  -532.5  229.46  -254.5  219.77  -111.5  210.87   -21.5  215.17
   174.3  216.99     498  213.45   949.6  207.94  1015.1  208.85 1153.24  206.71
  1610.4  205.65  1633.4  201.07  1911.3  200.11  1943.8  205.59  1966.3  200.96
  4998.7  199.61  9820.1     201    9827  203.9210099.77  206.79 10325.6   210.7
 10431.7   215.9 10497.8  214.06 10728.1  223.84 11331.2  235.27 11827.5   237.4
#Mann= 8 ,-1 , 0
 -2783.4     .11       0 -1538.1    .125       0 -1421.8     .11       0
     498    .125       0   949.6     .11       0  1015.1     .11       0
 1153.24    .015       010099.77     .11       0
#XS Ineff= 1 ,-1
    -350   174.3  216.99
Permanent Ineff=
       F
Bank Sta=1153.24,10099.77
XS Rating Curve= 0 ,0
Exp/Cntr=0.3,0.1

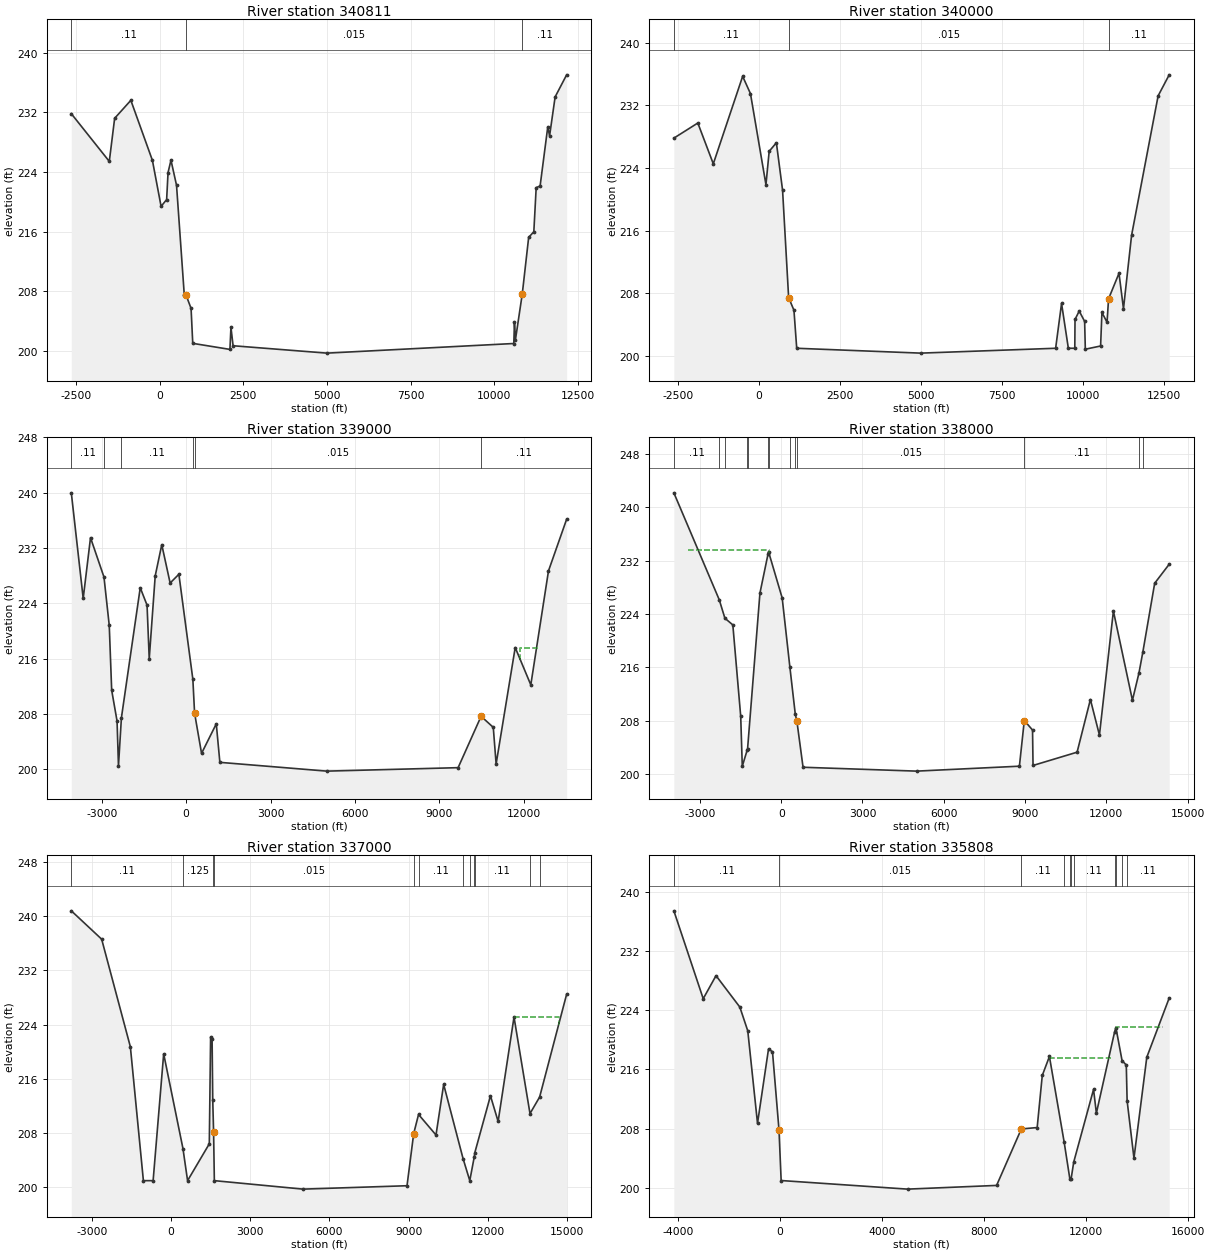
Type RM Length L Ch R = 1 ,340811  ,811,811,811
BEGIN DESCRIPTION:
WFSJ Main 338.0
END DESCRIPTION:
XS GIS Cut Line= 4
      3799308.55     10145683.46      3793312.71     10141773.37
      3788331.98     10139758.97      3786092.65     10139355.37
#Sta/Elev= 30
 -2641.9  231.82 -1506.3  225.42 -1346.3   231.2  -862.2  233.61  -217.7  225.56
    41.8  219.39   207.7   220.3   249.9  223.93   337.5  225.58   503.4  222.22
   735.8  207.46   785.3  207.52     938  205.71   988.2  201.02  2099.6  200.21
  2129.9  203.17    2194   200.7  4998.7  199.71 10585.5     201 10604.4  203.86
   10634   201.510838.82  207.67 11029.4  215.24 11183.5  215.98   11254   221.9
 11371.3  222.12 11600.9  230.07 11654.5  228.85 11820.4  234.07 12164.3  237.03
#Mann= 3 , 0 , 0
 -2641.9     .11       0   785.3    .015       010838.82     .11       0
Bank Sta=785.3,10838.82
XS Rating Curve= 0 ,0
Exp/Cntr=0.3,0.1

Type RM Length L Ch R = 1 ,340000  ,1000,1000,1000
BEGIN DESCRIPTION:
WFSJ Main 337.0
END DESCRIPTION:
XS GIS Cut Line= 4
      3799516.91     10145657.43      3793455.17     10141036.14
      3787615.84     10139199.08      3786066.35     10139225.12
#Sta/Elev= 30
 -2622.4  227.82 -1882.9  229.75 -1404.9  224.54  -498.6  235.71  -257.4   233.5
   220.7  221.88   320.5  226.14   542.8  227.23   734.1  221.17   921.1  207.47
  1085.3  205.85  1170.6     201  4998.7  200.38  9164.9     201  9347.7  206.72
  9557.4     201  9756.6     201  9763.6  204.68  9892.8  205.75 10060.3  204.43
 10081.5  200.88 10553.3  201.29 10594.2  205.57 10752.5  204.32   10799  207.31
 11121.5  210.57 11259.5  206.05 11509.5  215.41 12329.6  233.22 12671.2   235.9
#Mann= 3 ,-1 , 0
 -2622.4     .11       0   921.1    .015       0   10799     .11       0
Bank Sta=921.1,10799
XS Rating Curve= 0 ,0
Exp/Cntr=0.3,0.1

Type RM Length L Ch R = 1 ,339000  ,1000,1000,1000
BEGIN DESCRIPTION:
WFSJ Main 336.0
END DESCRIPTION:
XS GIS Cut Line= 6
      3801443.97     10145227.72      3800363.23     10145032.41
      3799009.06     10144889.18      3794183.58     10140350.99
      3788878.86     10138639.18      3785962.56     10139107.87
#Sta/Elev= 30
 -4084.2  239.99 -3661.3  224.71 -3401.2   233.5 -2922.5   227.8 -2734.9   220.8
 -2648.7  211.43 -2457.6  206.98 -2407.4  200.48 -2302.3  207.46 -1633.1  226.26
 -1391.1  223.74 -1313.4  215.99   -1101  227.97  -867.6  232.49  -570.6  226.94
  -259.4  228.21   237.8  213.01   299.3  208.11   546.9   202.3  1070.5  206.57
    1198     201  4998.7  199.73  9669.3  200.23 10486.2  207.66 10919.5  206.06
 11020.7  200.76 11699.3  217.61 12253.7  212.21 12882.8   228.7 13527.8  236.17
#Mann= 6 ,-1 , 0
 -4084.2     .11       0 -2922.5     .17       0 -2302.3     .11       0
   237.8    .125       0   299.3    .015       0 10486.2     .11       0
#XS Ineff= 2 ,-1
   -3900  -867.6  232.49 11877.3   12570  217.57
Permanent Ineff=
       F       F
Bank Sta=299.3,10486.2
XS Rating Curve= 0 ,0
Exp/Cntr=0.3,0.1

Type RM Length L Ch R = 1 ,338000  ,1000,1000,1000
BEGIN DESCRIPTION:
WFSJ Main 335.0
END DESCRIPTION:
XS GIS Cut Line= 6
      3801873.67     10145110.54      3800063.75     10144381.37
      3799191.36     10143873.56      3794911.98     10139665.84
      3789087.19     10138183.45      3785832.39     10138782.34
#Sta/Elev= 30
 -3962.2  242.16   -2288  226.13 -2078.5  223.35 -1785.9  222.35   -1495  208.64
 -1437.1  201.15 -1249.7  203.66 -1241.5  203.77  -785.2  227.12  -488.3  232.95
    -468  233.32    35.2   226.4   317.6  216.09   518.3  208.99  579.98  207.87
   805.9     201  4998.7  200.42  8791.2  201.16  8972.2  208.01  9276.2  206.58
  9294.3  201.27 10920.4  203.26 11411.6  211.16 11745.1  205.83 12260.4  224.43
 12963.1  211.05 13204.3  215.14 13349.9  218.34 13784.2   228.6 14319.9  231.45
#Mann= 13 ,-1 , 0
 -3962.2     .11       0   -2288    .125       0 -2078.5     .11       0
 -1249.7    .125       0 -1241.5     .11       0  -488.3    .125       0
    -468     .11       0   317.6    .125       0   518.3     .11       0
  579.98    .015       0  8972.2     .11       0 13204.3    .125       0
 13349.9     .11       0
#XS Ineff= 2 ,-1
   -3433  -452.7   233.6 12260.4   13850  224.43
Permanent Ineff=
       F       F
Bank Sta=579.98,8972.2
XS Rating Curve= 0 ,0
Exp/Cntr=0.3,0.1

Type RM Length L Ch R = 1 ,337000  ,1192,1192,1192
BEGIN DESCRIPTION:
WFSJ Main 334.0
END DESCRIPTION:
XS GIS Cut Line= 6
      3802266.87     10144415.22      3800475.21     10143311.06
      3798787.71     10142727.72      3795640.38     10138980.69
      3791287.71     10137894.39      3785832.03     10138526.69
#Sta/Elev= 30
 -3783.5  240.79 -2633.5  236.61 -1545.4  220.74 -1051.8     201    -683     201
  -283.1   219.7   447.3  205.74   622.6     201    1446  206.43  1495.4  222.18
  1551.8  221.84  1576.2  212.93  1608.6  208.15  1637.2     201  4998.7  199.75
  8938.5  200.25 9191.18  207.93  9375.4  210.76 10037.1  207.73 10327.2  215.19
 11061.8  204.26   11317     201 11486.5   204.5 11509.6  205.15 12100.9  213.51
 12391.5  209.73 12993.3  225.12   13599  210.89 13963.8  213.33 14987.5  228.49
#Mann= 12 ,-1 , 0
 -3783.5     .11       0   447.3    .125       0  1576.2     .15       0
  1608.6    .015       0 9191.18     .17       0  9375.4     .11       0
 11061.8    .125       0   11317     .11       0 11486.5    .125       0
 11509.6     .11       0   13599    .125       0 13963.8     .11       0
#XS Ineff= 3 ,-1
   -2000  1495.4  222.18 10327.2   12890  215.19 12993.3   14680  225.12
Permanent Ineff=
       F       F       F
Bank Sta=1608.6,9191.18
XS Rating Curve= 0 ,0
Exp/Cntr=0.3,0.1

Type RM Length L Ch R = 1 ,335808  ,808,808,808
BEGIN DESCRIPTION:
WFSJ Main 333.0
END DESCRIPTION:
XS GIS Cut Line= 5
      3802496.03     10144019.37      3796350.21     10137915.22
      3795225.21     10137811.06      3787703.26     10137852.35
      3785666.02     10138361.66
#Sta/Elev= 30
   -4159   237.4 -3008.9  225.54 -2506.9  228.65 -1573.5  224.41 -1262.3   221.2
  -880.5  208.72  -449.2  218.75  -293.6  218.38  -37.94  207.81    45.8     201
  4998.7  199.84  8490.3  200.34  9459.5  207.96 10080.3  208.15 10280.3  215.18
 10560.3  217.74 11137.4   206.2 11361.5  201.21   11411  201.23 11512.8  203.49
 12290.4   213.3 12400.4  210.09 13113.9  221.04 13166.3  221.64 13407.6  217.19
 13572.8  216.59 13605.9  211.76 13874.1  204.02 14376.9  217.64 15254.9  225.63
#Mann= 11 ,-1 , 0
   -4159     .11       0  -37.94    .015       0  9459.5     .11       0
 11137.4    .125       0 11361.5     .11       0   11411    .125       0
 11512.8     .11       0 13113.9    .125       0 13166.3     .15       0
 13407.6    .125       0 13605.9     .11       0
#XS Ineff= 3 ,-1
   -1250  -449.2  218.75 10540.3   12990  217.57   13155   15020  221.67
Permanent Ineff=
       F       F       F
Bank Sta=-37.94,9459.5
XS Rating Curve= 0 ,0
Exp/Cntr=0.3,0.1

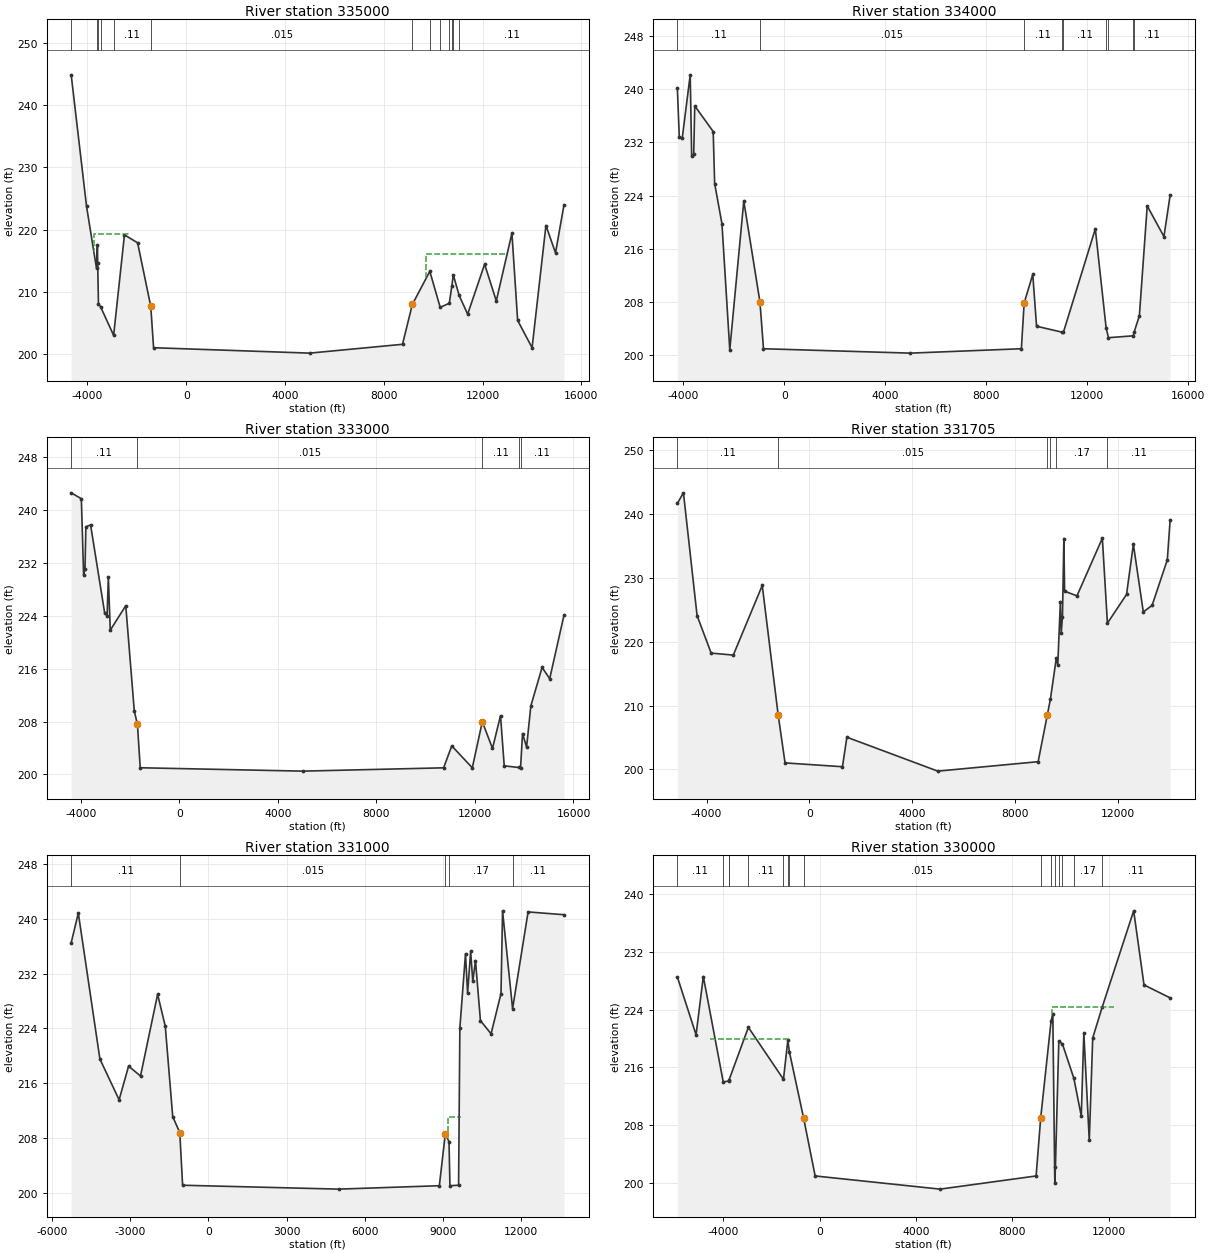
Type RM Length L Ch R = 1 ,335000  ,1000,1000,1000
BEGIN DESCRIPTION:
WFSJ Main 332.0
END DESCRIPTION:
XS GIS Cut Line= 6
       3803516.9     10142456.91      3802621.04     10141706.89
      3801704.38     10141873.56      3795879.05     10137061.46
      3788446.56      10137439.4      3785652.57      10136875.1
#Sta/Elev= 30
 -4655.9  244.91 -4034.6  223.75 -3629.9  213.76   -3593  217.56 -3583.2  214.58
 -3551.8  208.07   -3464  207.57 -2937.3  202.99 -2499.5  219.16 -1966.7  217.88
 -1433.8  207.64 -1320.5     201  4998.7  200.13    8756  201.55 9153.91  207.96
  9861.3  213.29 10281.5   207.5 10650.6  208.15 10752.3   210.9 10812.7  212.72
 11049.3  209.41 11393.2   206.4 12080.3  214.43   12553  208.53 13185.5  219.42
 13416.9  205.39 14001.7     201 14562.8  220.66 14950.4  216.26 15292.5  223.98
#Mann= 13 ,-1 , 0
 -4655.9     .11       0   -3593     .15       0 -3583.2     .11       0
   -3464     .15       0 -2937.3     .11       0 -1433.8    .015       0
 9153.91     .11       0  9861.3    .125       0 10281.5     .11       0
 10650.6    .125       0 10752.3     .11       0 10812.7    .125       0
 11049.3     .11       0
#XS Ineff= 3 ,-1
   -3725 -2371.8  219.26  9727.3   13000  216.02 13185.5   14565  219.42
Permanent Ineff=
       F       F       F
Bank Sta=-1433.8,9153.91
XS Rating Curve= 0 ,0
Exp/Cntr=0.3,0.1

Type RM Length L Ch R = 1 ,334000  ,1000,1000,1000
BEGIN DESCRIPTION:
WFSJ Main 331.0
END DESCRIPTION:
XS GIS Cut Line= 3
       3803600.2     10141165.22      3795908.29     10136061.89
      3785652.59     10136833.73
#Sta/Elev= 30
 -4230.9  240.18 -4155.1  232.89 -4037.8  232.63   -3722  242.16   -3664  229.94
 -3583.7  230.19 -3541.6  237.49   -2812  233.64 -2753.6  225.82 -2464.9  219.79
 -2155.1  200.84 -1599.9   223.2 -959.61  208.02  -819.9     201  4998.7  200.34
  9392.8     201  9503.1  207.88  9844.1  212.17  9994.5  204.38 10991.6   203.5
 11055.1  203.44 12321.1  219.01 12749.2  204.13 12841.4  202.66 13819.7  202.94
   13860  203.52   14066  205.96 14376.9  222.46 15038.7  217.85 15284.7  224.09
#Mann= 9 ,-1 , 0
 -4230.9     .11       0 -959.61    .015       0  9503.1     .11       0
 10991.6     .17       0 11055.1     .11       0 12749.2    .125       0
 12841.4     .11       0 13819.7    .125       0   13860     .11       0
#XS Ineff= 3 ,-1
   -2800 -1599.9   223.2 12321.1   14418  219.01  9844.1   12040  212.17
Permanent Ineff=
       F       F       F
Bank Sta=-959.61,9503.1
XS Rating Curve= 0 ,0
Exp/Cntr=0.3,0.1

Type RM Length L Ch R = 1 ,333000  ,1295,1295,1295
BEGIN DESCRIPTION:
WFSJ Main 330.0
END DESCRIPTION:
XS GIS Cut Line= 5
      3803340.31      10140792.2      3800919.74     10138443.25
      3795937.53     10135062.32      3786911.93     10135936.74
      3785652.57     10136833.55
#Sta/Elev= 30
   -4394   242.6 -3981.3  241.71 -3889.3  230.16 -3832.9   231.1 -3797.4  237.46
 -3606.5  237.75 -3033.7  224.41 -2934.7  224.03 -2885.3  229.85 -2807.3  221.82
 -2177.9  225.53 -1831.4  209.59 -1704.1  207.58 -1590.9  201.01  4998.7   200.5
 10726.4     201 11058.3  204.32 11891.8     201 12298.4  207.98 12711.7  203.93
 13037.1  208.89 13187.8   201.3 13772.4  201.05 13851.8  201.02 13931.3  206.18
 14096.2  204.14 14268.4  210.36 14725.7  216.19 15034.3  214.48 15613.9  224.09
#Mann= 5 ,-1 , 0
   -4394     .11       0 -1704.1    .015       0 12298.4     .11       0
 13772.4    .125       0 13851.8     .11       0
Bank Sta=-1704.1,12298.4
XS Rating Curve= 0 ,0
Exp/Cntr=0.3,0.1

Type RM Length L Ch R = 1 ,331705  ,705,705,705
BEGIN DESCRIPTION:
WFSJ Main 329.0
END DESCRIPTION:
XS GIS Cut Line= 6
      3803297.34     10140491.42      3801406.72     10137770.07
      3799616.36     10135635.96      3795835.11     10133673.72
      3792526.51     10131425.02        3788245.     10129205.51
#Sta/Elev= 30
 -5137.8   241.7   -4901  243.36 -4370.2  224.11 -3822.3  218.22 -2960.2  217.91
 -1833.2  228.83 -1214.9  208.57  -945.6     201  1289.5   200.4  1460.9  205.03
  4998.7  199.71    8906  201.19  9261.5  208.48  9384.9  211.03  9615.6  217.48
  9670.7  216.42  9772.4  226.31  9803.5  221.31  9853.4  223.96  9907.6  236.19
  9936.2  227.93 10417.4   227.2 11405.7  236.24 11602.6  222.91 12347.4  227.42
 12612.9  235.28   13000  224.68 13342.7  225.71 13934.6  232.86 14044.6  239.13
#Mann= 6 ,-1 , 0
 -5137.8     .11       0 -1214.9    .015       0  9261.5    .125       0
  9384.9     .11       0  9615.6     .17       0 11602.6     .11       0
Bank Sta=-1214.9,9261.5
XS Rating Curve= 0 ,0
Exp/Cntr=0.3,0.1

Type RM Length L Ch R = 1 ,331000  ,1000,1000,1000
BEGIN DESCRIPTION:
WFSJ Main 328.0
END DESCRIPTION:
XS GIS Cut Line= 4
       3803469.2      10140362.5      3799859.85     10135550.02
      3796351.86     10133155.52      3788775.41     10129005.27
#Sta/Elev= 30
 -5262.9  236.52   -4989  240.85 -4161.1  219.52 -3424.4  213.56 -3061.1  218.48
 -2603.6  217.04 -1947.3  228.99 -1653.6   224.3 -1368.2   211.1 -1097.3  208.76
    -989  201.07  4998.7   200.5  8858.5     201  9086.5  208.57  9229.4  207.43
  9264.6     201  9596.4  201.07  9645.7  224.09  9861.8  234.92  9941.7  229.12
 10059.1  235.25 10140.7  230.87   10244  233.91 10434.6  225.14 10842.3  223.21
 11223.4   229.1 11283.2  241.19 11667.6  226.87 12262.6  241.03 13638.7  240.62
#Mann= 5 ,-1 , 0
 -5262.9     .11       0 -1097.3    .015       0  9086.5     .11       0
  9229.4     .17       0 11667.6     .11       0
#XS Ineff= 2 ,-1
  9189.1    9670  211.09   -4620 -1947.3  228.99
Permanent Ineff=
       F       F
Bank Sta=-1097.3,9086.5
XS Rating Curve= 0 ,0
Exp/Cntr=0.3,0.1

Type RM Length L Ch R = 1 ,330000  ,1000,1000,1000
BEGIN DESCRIPTION:
WFSJ Main 327.0
END DESCRIPTION:
XS GIS Cut Line= 4
      3803698.38     10140104.66      3802486.15     10135678.49
      3797050.42     10132440.96      3788371.13     10128439.71
#Sta/Elev= 30
   -5916   228.5 -5138.9  220.51 -4837.1  228.56 -4010.5     214 -3789.9  214.11
 -3775.9   214.2 -2965.8  221.54 -1507.6  214.36 -1326.2  219.77 -1262.4  218.16
  -672.5  209.03  -191.3     201  4998.7  199.18    8989     201  9179.8  209.06
  9610.6  222.41  9682.7  223.43  9765.1  200.09  9791.3  202.25  9931.5  219.67
 10082.9  219.23 10557.4  214.49   10865  209.28 10971.1  220.75 11197.4  205.92
 11340.6  220.08 11729.9  224.29   13042  237.64 13471.7   227.4 14557.2  225.61
#Mann= 16 ,-1 , 0
   -5916     .11       0 -4010.5     .17       0 -3789.9     .11       0
 -3775.9     .17       0 -2965.8     .11       0 -1507.6    .125       0
 -1326.2    .125       0 -1262.4     .11       0  -672.5    .015       0
  9179.8     .11       0  9610.6     .17       0  9791.3     .11       0
  9931.5    .125       0 10082.9     .11       0 10557.4     .17       0
 11729.9     .11       0
#XS Ineff= 2 ,-1
   -4540 -1326.8  219.92  9667.8   12218   224.3
Permanent Ineff=
       F       F
Bank Sta=-672.5,9179.8
XS Rating Curve= 0 ,0
Exp/Cntr=0.3,0.1

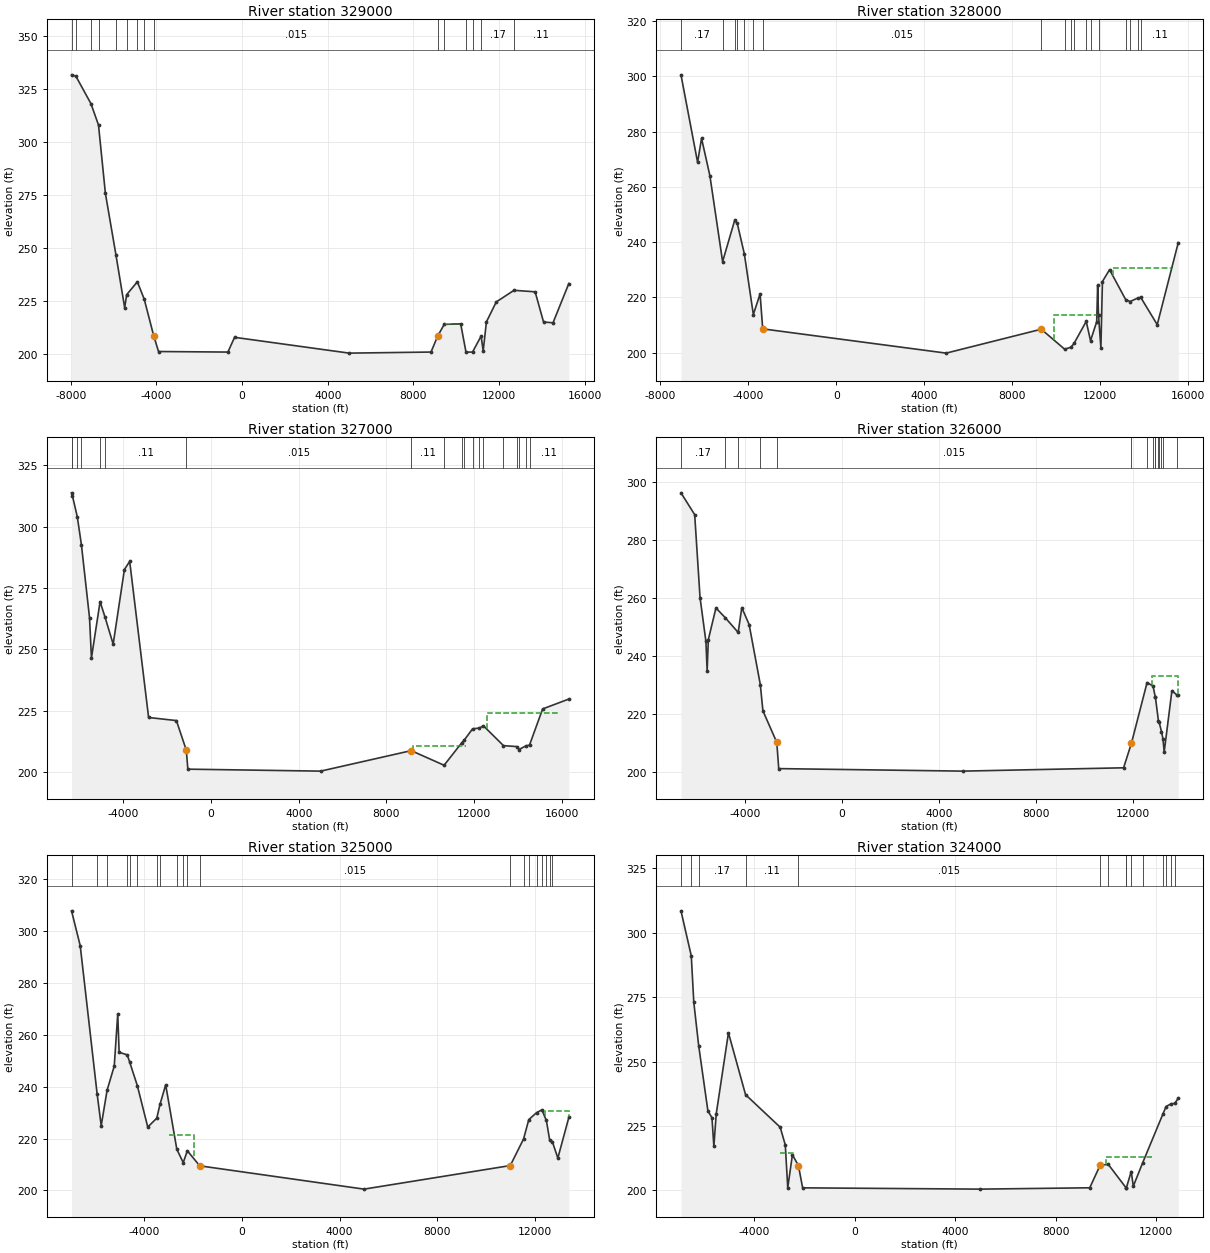
Type RM Length L Ch R = 1 ,329000  ,1000,1000,1000
BEGIN DESCRIPTION:
WFSJ Main 326.0
END DESCRIPTION:
XS GIS Cut Line= 4
      3809968.75     10134636.82      3802034.76     10134428.49
      3797777.11     10131753.99      3788206.68     10128059.15
#Sta/Elev= 30
 -7964.7  331.84 -7761.8   331.2 -7055.5  318.19 -6705.2  308.14 -6383.3  275.89
 -5888.9  246.77 -5482.9  221.89 -5390.3  228.08 -4890.3  234.17 -4569.6  225.96
 -4126.9  208.68 -3902.4  201.26  -661.3     201  -351.2  207.96  4998.7   200.5
  8823.3  201.01 9131.88   208.5  9440.5  214.07 10208.8  214.32 10456.6     201
 10761.9     201 11164.9  208.57 11259.3  201.51 11411.4  215.28 11870.3  224.66
 12700.5  230.15   13686  229.43 14078.7  215.19 14520.6  214.82 15258.9  233.34
#Mann= 15 ,-1 , 0
 -7964.7     .17       0 -7761.8     .11       0 -7055.5     .15       0
 -6705.2     .17       0 -5888.9     .11       0 -5390.3    .125       0
 -4890.3     .11       0 -4569.6     .11       0 -4126.9    .015       0
 9131.88    .125       0  9440.5     .11       0 10456.6     .17       0
 10761.9     .11       0 11164.9     .17       0 12700.5     .11       0
#XS Ineff= 2 ,-1
  9479.9 10208.7  214.16 10208.8   11450  214.32
Permanent Ineff=
       F       F
Bank Sta=-4126.9,9131.88
XS Rating Curve= 0 ,0
Exp/Cntr=0.3,0.1

Type RM Length L Ch R = 1 ,328000  ,1000,1000,1000
BEGIN DESCRIPTION:
WFSJ Main 325.0
END DESCRIPTION:
XS GIS Cut Line= 5
      3809673.61     10133230.58      3801947.95      10133352.1
      3798343.15      10130951.7      3790489.62     10128386.83
      3788272.33     10127820.57
#Sta/Elev= 30
 -7057.5  300.57 -6301.6  268.88 -6121.6  277.56 -5741.6  263.98 -5165.2  232.92
 -4615.3  247.89 -4497.4  246.73 -4175.1  235.67 -3767.3  213.76 -3461.3  221.23
 -3341.3  208.57  4998.7  199.78 9321.72  208.44 10383.8  201.21 10675.6  201.92
 10813.5  203.33 11366.5  211.29 11561.5  204.28 11842.5  211.16 11885.5  224.38
 11924.1  213.72 12032.8  201.59 12102.9  225.71   12427  230.01 13157.6   219.2
 13357.6  218.47 13724.7  219.78 13845.2  219.95 14594.1  210.09 15550.2  239.79
#Mann= 18 ,-1 , 0
 -7057.5     .17       0 -5165.2     .11       0 -4615.3     .17       0
 -4497.4     .11       0 -4175.1     .17       0 -3767.3     .11       0
 -3341.3    .015       0 9321.72     .11       0 10383.8     .17       0
 10675.6     .17       0 10813.5     .11       0 11366.5     .17       0
 11561.5     .11       0 11924.1     .17       0 13157.6     .11       0
 13357.6     .11       0 13724.7    .125       0 13845.2     .11       0
#XS Ineff= 3 ,-1
  9913.6   11881  213.57 11885.5   12372  224.38 12586.4   15300  230.51
Permanent Ineff=
       F       F       F
Bank Sta=-3341.3,9321.72
XS Rating Curve= 0 ,0
Exp/Cntr=0.3,0.1

Type RM Length L Ch R = 1 ,327000  ,1000,1000,1000
BEGIN DESCRIPTION:
WFSJ Main 324.0
END DESCRIPTION:
XS GIS Cut Line= 5
       3809708.4     10132796.55        3798696.     10130016.04
      3794391.53     10128851.23      3789660.63     10127939.78
      3787946.26     10126843.88
#Sta/Elev= 30
   -6358  313.76 -6320.7  312.67 -6095.5  304.03 -5906.7  292.56 -5538.3  262.96
 -5449.8  246.58 -5056.1  269.47   -4830  263.14 -4459.7  252.17 -3947.6  282.54
 -3706.8  285.86 -2844.3  222.33 -1576.9  221.07-1124.79  208.99 -1056.1   201.3
  4998.7   200.5 9126.55  208.84 10626.4  202.89 11438.6  212.13 11538.4  213.08
 11924.1   217.7 12236.6  218.05   12420  218.94 13333.9  210.87 13932.3   210.5
 14039.3   209.3 14349.8  210.74 14519.6   211.1 15118.4  225.81 16311.9  229.83
#Mann= 19 ,-1 , 0
   -6358     .11       0 -6320.7     .17       0 -6095.5     .11       0
 -5906.7     .17       0 -5056.1     .11       0   -4830     .11       0
-1124.79    .015       0 9126.55     .11       0 10626.4    .125       0
 11438.6    .125       0 11538.4     .11       0 11924.1     .17       0
 12236.6     .11       0   12420     .17       0 13333.9     .15       0
 13932.3    .125       0 14039.3     .11       0 14349.8    .125       0
 14519.6     .11       0
#XS Ineff= 2 ,-1
  9210.2   11625  210.85 12569.1   15820  224.04
Permanent Ineff=
       F       F
Bank Sta=-1124.79,9126.55
XS Rating Curve= 0 ,0
Exp/Cntr=0.3,0.1

Type RM Length L Ch R = 1 ,326000  ,1000,1000,1000
BEGIN DESCRIPTION:
WFSJ Main 323.0
END DESCRIPTION:
XS GIS Cut Line= 4
      3809882.02     10132327.81      3798735.55     10129016.91
      3793642.83     10126637.69      3791168.91     10124521.84
#Sta/Elev= 30
 -6627.8  296.29 -6062.6  288.76 -5841.1  260.07 -5599.6  244.96   -5549  234.88
   -5500  245.56 -5185.4  256.51 -4804.3  253.17 -4268.4  248.04 -4119.8  256.61
 -3817.3  250.78 -3355.7     230 -3249.5  220.97-2677.47  210.07 -2596.8     201
  4998.7  200.13 11622.4  201.2811947.09  209.81 12590.8  230.74 12836.7  229.49
 12929.3  225.73 12933.7  225.69 13059.4  217.43 13087.7  217.02 13185.1  213.79
   13246  211.27 13296.4  206.76 13614.8  227.93 13811.6  226.49 13876.4  226.59
#Mann= 15 ,-1 , 0
 -6627.8     .17       0 -4804.3     .11       0 -4268.4     .17       0
 -3355.7     .11       0-2677.47    .015       011947.09     .11       0
 12590.8    .125       0 12836.7     .11       0 12929.3    .125       0
 12933.7     .11       0 13059.4    .125       0 13087.7     .11       0
 13185.1    .125       0   13246     .11       0 13811.6    .125       0
#XS Ineff= 1 ,-1
 12813.4 13876.4  233.15
Permanent Ineff=
       F
Bank Sta=-2677.47,11947.09
XS Rating Curve= 0 ,0
Exp/Cntr=0.3,0.1

Type RM Length L Ch R = 1 ,325000  ,1000,1000,1000
BEGIN DESCRIPTION:
WFSJ Main 322.0
END DESCRIPTION:
XS GIS Cut Line= 3
      3810090.27     10131911.12      3798773.83     10128017.64
      3791191.67     10124457.22
#Sta/Elev= 30
 -6967.5  307.87 -6612.3  294.43 -5921.4  237.33 -5753.7  224.95 -5512.1  238.68
   -5220  247.96 -5077.1   268.1   -5020   253.3 -4688.2  252.29 -4585.2  249.42
 -4276.2  240.43   -3849  224.45   -3481  227.87 -3349.2  233.17 -3115.5  240.75
 -2660.6  215.91 -2397.7  210.72 -2230.3   215.3-1722.17  209.49  4998.6   200.5
10981.02  209.59 11524.7  219.85 11738.9  227.32 12060.1  230.02 12274.3   231.1
   12458  226.98 12595.5  219.32 12702.6  218.82 12927.2  212.48 13376.5  228.15
#Mann= 20 ,-1 , 0
 -6967.5     .17       0 -5921.4     .11       0 -5512.1     .17       0
 -4688.2     .11       0 -4585.2     .17       0 -4276.2     .17       0
   -3481     .17       0 -3349.2     .11       0 -2660.6     .11       0
 -2397.7    .125       0 -2230.3     .11       0-1722.17    .015       0
10981.02     .11       0 11524.7     .11       0 11738.9     .15       0
 12060.1    .125       0 12274.3    .125       0   12458     .11       0
 12595.5    .125       0 12702.6     .11       0
#XS Ineff= 2 ,-1
   -2990 -1970.3  221.37   12386 13376.5  230.58
Permanent Ineff=
       F       F
Bank Sta=-1722.17,10981.02
XS Rating Curve= 0 ,0
Exp/Cntr=0.3,0.1

Type RM Length L Ch R = 1 ,324000  ,689,689,689
BEGIN DESCRIPTION:
WFSJ Main 321.0
END DESCRIPTION:
XS GIS Cut Line= 3
        3810073.     10131477.12      3799016.19     10127066.92
      3791754.81     10124011.82
#Sta/Elev= 30
 -6903.9  308.54 -6493.7  291.05   -6393  272.96 -6200.1  256.24 -5832.5  230.86
   -5671  228.22 -5595.7  217.09 -5500.8  229.72 -5015.7  261.19 -4334.9  237.17
 -2956.4  224.53 -2753.4  217.62 -2656.5     201 -2471.3  213.84 -2231.4  209.65
 -2064.3     201  4998.6   200.5  9357.1  201.02 9771.11   209.8 10095.8  210.08
 10796.3  201.08 10814.6  201.05   11007  207.34 11088.8  201.64 11464.1  210.78
 12271.2  229.75 12394.3  232.56 12587.2  233.61 12740.8  233.77 12877.9  235.86
#Mann= 15 ,-1 , 0
 -6903.9     .17       0 -6493.7     .11       0 -6200.1     .17       0
 -4334.9     .11       0 -2231.4    .015       0 9771.11     .11       0
 10095.8     .11       0 10796.3    .125       0 10814.6     .15       0
   11007    .125       0 11464.1     .11       0 12271.2     .15       0
 12394.3     .11       0 12587.2    .125       0 12740.8     .11       0
#XS Ineff= 2 ,-1
  9988.8   11845  213.16   -2950 -2441.2  214.45
Permanent Ineff=
       F       F
Bank Sta=-2231.4,9771.11
XS Rating Curve= 0 ,0
Exp/Cntr=0.3,0.1