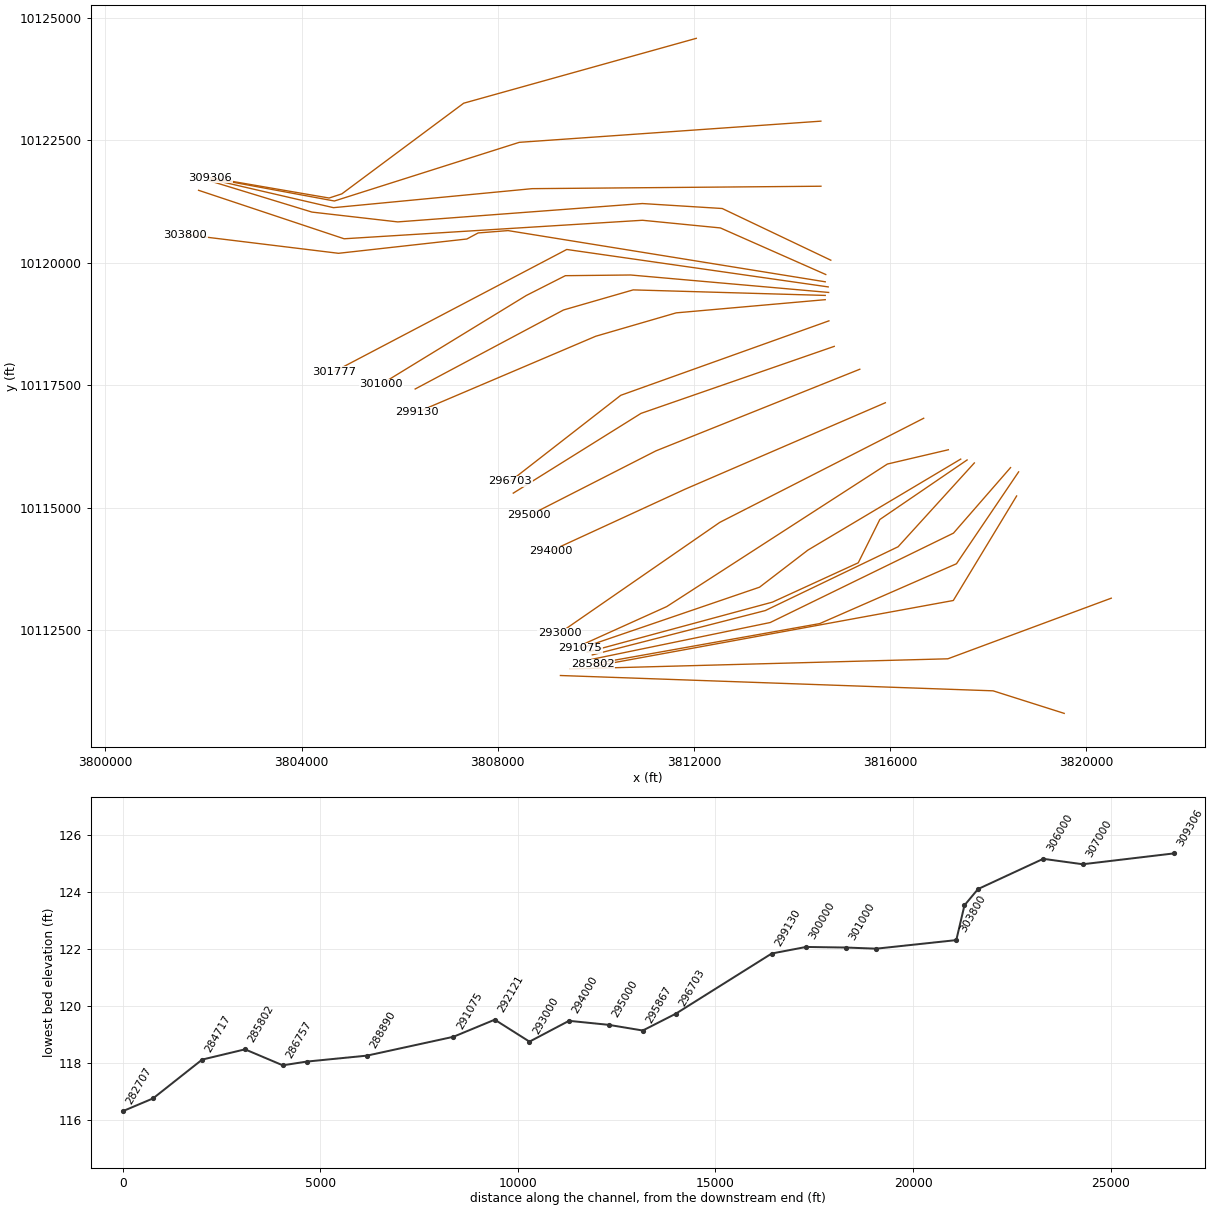
HEC-RAS study WFSJ Main.prj: WFSJ Main Base Level Engineering

--- WFSJ Main.g01 (geometry) --- (continued)

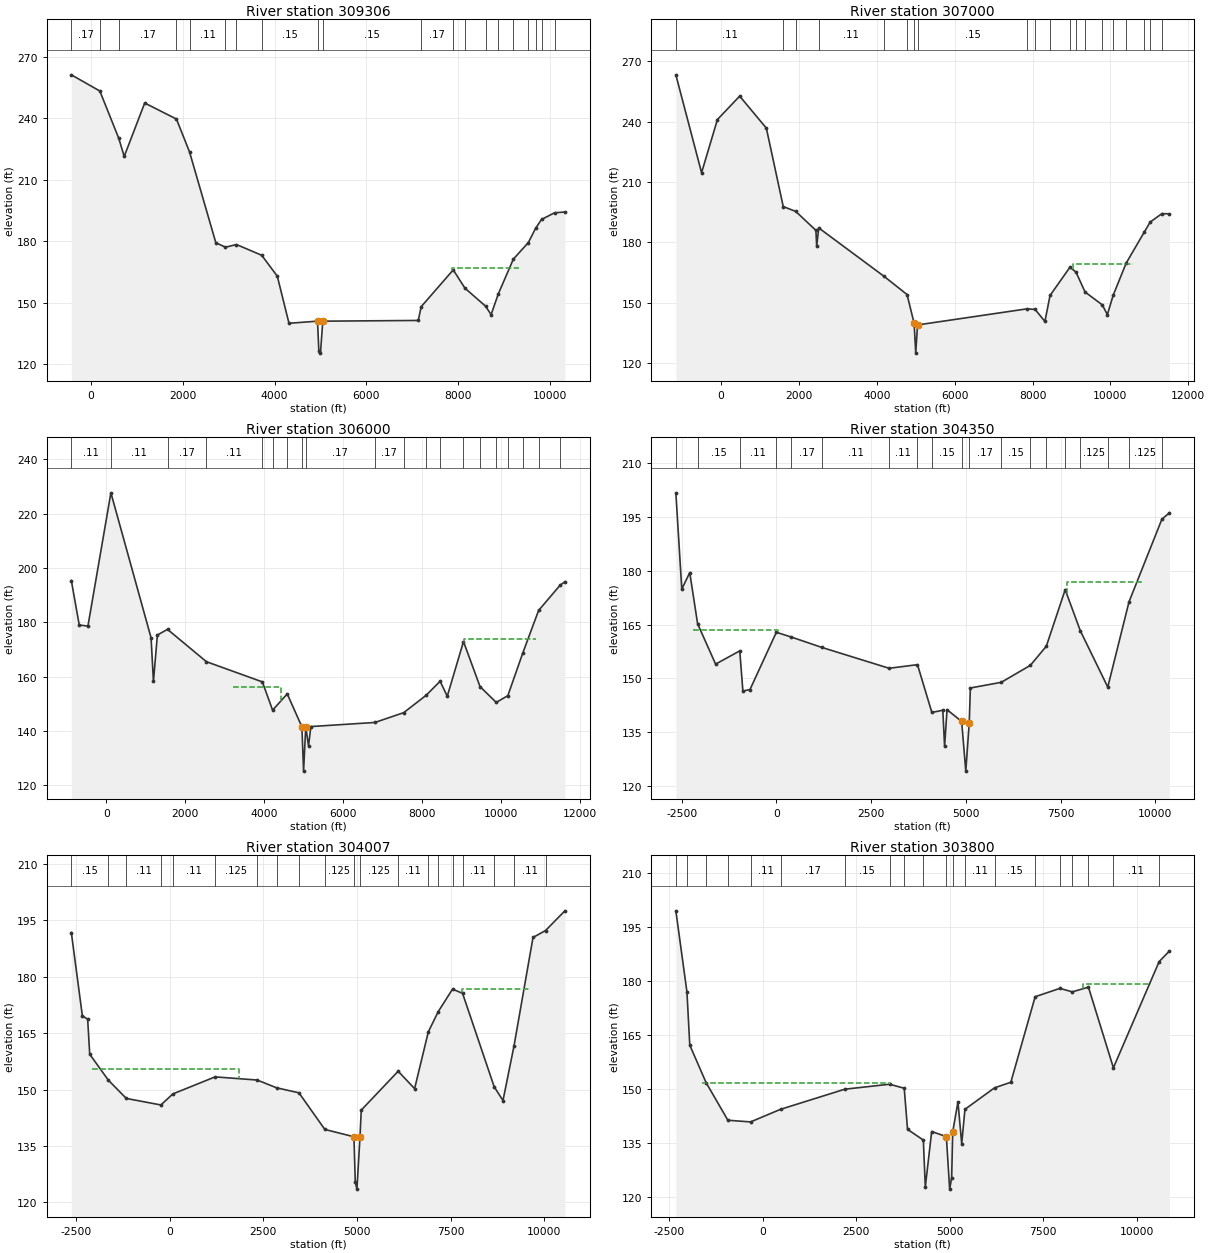
Type RM Length L Ch R = 1 ,309306  ,2306,2306,2306
BEGIN DESCRIPTION:
WFSJ Main 307.0
END DESCRIPTION:
XS GIS Cut Line= 5
      3812046.89     10124581.13      3807305.16     10123257.35
      3804821.62     10121407.48      3804561.76     10121322.58
      3802141.32       10121739.
#Sta/Elev= 30
  -427.2  261.29   193.2  253.39   605.6  230.28   724.2  221.44  1170.7  247.53
  1862.1  239.68  2146.8  223.62  2719.2   179.3  2929.9  177.07  3168.5   178.4
    3719  173.15  4058.3  162.94    4313  139.93  4934.2  140.97  4963.4  126.49
  4998.6  125.35  5048.9  140.96    7128  141.31  7193.3  148.06  7890.4  166.02
  8143.6  157.12  8596.8  148.24  8714.8  144.14  8873.3  154.36  9199.7  171.28
  9526.9  179.36  9684.2  186.32  9812.9  190.64 10096.8   193.9   10322  194.29
#Mann= 20 ,-1 , 0
  -427.2     .17       0   193.2     .17       0   605.6     .17       0
  1862.1     .11       0  2146.8     .11       0  2929.9     .17       0
  3168.5     .11       0    3719     .15       0  4934.2     .09       0
  5048.9     .15       0  7193.3     .17       0  7890.4    .125       0
  8143.6     .11       0  8596.8     .15       0  8873.3     .11       0
  9199.7    .125       0  9526.9     .11       0  9684.2    .125       0
  9812.9     .15       0 10096.8    .125       0
#XS Ineff= 1 ,-1
  7859.8    9315  167.13
Permanent Ineff=
       F
Bank Sta=4934.2,5048.9
XS Rating Curve= 0 ,0
Exp/Cntr=0.3,0.1

Type RM Length L Ch R = 1 ,307000  ,1000,1000,1000
BEGIN DESCRIPTION:
WFSJ Main 305.0
END DESCRIPTION:
XS GIS Cut Line= 4
      3814586.82     10122891.16       3808438.1     10122458.86
      3804669.28     10121261.93      3802151.31     10121728.22
#Sta/Elev= 30
 -1163.9  263.31  -503.3  214.65   -95.3   241.1   475.6  252.72  1160.8  236.82
  1594.8  197.82  1914.6  195.43  2433.9  186.01    2454  178.14  2506.5  187.22
  4183.5  163.16  4775.4  154.09  4957.2  139.82  4998.6  124.97  5044.9  138.98
  7862.5     147  8067.2  146.67    8317  140.71  8449.2  153.63  8960.5  167.68
  9116.6  165.21  9348.7  155.35  9791.9  148.94  9921.9  144.12 10072.2  153.81
 10405.4  169.75 10875.2  185.31 11021.7  190.12 11323.3  194.32 11515.1  194.21
#Mann= 20 ,-1 , 0
 -1163.9     .11       0  1594.8     .11       0  1914.6     .17       0
  2506.5     .11       0  4183.5     .15       0  4775.4     .15       0
  4957.2     .09       0  5044.9     .15       0  7862.5     .17       0
  8067.2     .15       0  8449.2     .17       0  8960.5     .11       0
  9116.6    .125       0  9348.7     .11       0  9791.9     .15       0
 10072.2     .11       0 10405.4    .125       0 10875.2    .125       0
 11021.7     .15       0 11323.3    .125       0
#XS Ineff= 1 ,-1
  9026.9   10570  169.34
Permanent Ineff=
       F
Bank Sta=4957.2,5044.9
XS Rating Curve= 0 ,0
Exp/Cntr=0.3,0.1

Type RM Length L Ch R = 1 ,306000  ,1650,1650,1650
BEGIN DESCRIPTION:
WFSJ Main 304.0
END DESCRIPTION:
XS GIS Cut Line= 4
      3814588.34     10121563.33      3808701.34     10121513.82
      3804650.82     10121125.83      3802164.73     10121702.21
#Sta/Elev= 30
  -887.2  195.31  -686.7  178.95  -466.7  178.57   115.4  227.63  1133.4  174.25
  1193.4  158.17  1293.4  175.27  1550.1  177.36  2536.4  165.45  3953.7  158.02
  4213.3  147.61  4584.7   153.6 4955.59  141.48  4998.6  125.16  5053.7  141.59
  5124.1  134.37  5182.7  141.57  6806.9  143.08  7536.3  146.69  8102.4  153.05
  8458.9  158.25  8640.1  152.73  9051.4  172.88  9470.5  156.28  9881.4  150.46
 10174.9  152.94 10554.5  168.67 10954.6  184.31 11500.1  193.62 11621.1  194.88
#Mann= 20 ,-1 , 0
  -887.2     .11       0   115.4     .11       0  1550.1     .17       0
  2536.4     .11       0  3953.7     .17       0  4213.3     .11       0
  4584.7     .17       0 4955.59     .09       0  5053.7     .17       0
  6806.9     .17       0  7536.3     .15       0  8102.4     .11       0
  8458.9     .17       0  9051.4     .11       0  9470.5     .11       0
  9881.4     .15       0 10174.9     .11       0 10554.5    .125       0
 10954.6    .125       0 11500.1    .125       0
#XS Ineff= 2 ,-1
  9069.1   10895  173.67    3200  4423.5  156.12
Permanent Ineff=
       F       F
Bank Sta=4955.59,5053.7
XS Rating Curve= 0 ,0
Exp/Cntr=0.3,0.1

Type RM Length L Ch R = 1 ,304350  ,343,343,343
BEGIN DESCRIPTION:
WFSJ Main 303.0
END DESCRIPTION:
XS GIS Cut Line= 6
       3814789.1     10120054.11      3812575.56      10121108.8
      3810947.59     10121209.99      3805960.97     10120835.36
      3804213.32     10121035.55      3802123.02     10121674.44
#Sta/Elev= 30
   -2656  201.79 -2499.5  174.92 -2289.1  179.52 -2081.7  165.25 -1606.5  153.97
  -968.5  157.67  -886.2  146.45    -699  146.87    -3.3  162.86   389.7  161.54
  1196.5  158.64  2974.3  152.81  3722.8  153.82  4102.8  140.48  4391.9   141.1
  4438.8  131.02  4503.2  141.25  4889.4  137.97  4998.6   124.1  5089.6   137.6
  5119.6  147.31  5934.3  148.89  6703.2  153.63  7124.4  158.97    7623  174.75
  8020.5  163.32  8746.8  147.56  9307.6  171.36 10175.3  194.42 10373.8  196.22
#Mann= 19 ,-1 , 0
   -2656     .11       0 -2081.7     .15       0  -968.5     .11       0
    -3.3     .11       0   389.7     .17       0  1196.5     .11       0
  2974.3     .11       0  3722.8     .11       0  4102.8     .15       0
  4889.4     .09       0  5089.6     .17       0  5934.3     .15       0
  6703.2     .11       0  7124.4     .17       0    7623     .11       0
  8020.5    .125       0  8746.8     .11       0  9307.6    .125       0
 10175.3    .125       0
#XS Ineff= 2 ,-1
   -2200    44.2  163.47  7663.5    9640  176.95
Permanent Ineff=
       F       F
Bank Sta=4889.4,5089.6
XS Rating Curve= 0 ,0
Exp/Cntr=0.3,0.1

Type RM Length L Ch R = 1 ,304007  ,207,207,207
BEGIN DESCRIPTION:
WFSJ Main 302.0
END DESCRIPTION:
XS GIS Cut Line= 5
      3814686.14     10119761.97      3812537.68     10120712.51
      3810949.14     10120868.76      3804868.41     10120491.15
       3801901.3     10121480.19
#Sta/Elev= 30
 -2619.3  191.77 -2325.9  169.65 -2183.7  168.72 -2129.1  159.41 -1631.3  152.51
 -1152.6  147.65    -231  145.92    87.9  148.85  1215.1  153.39  2336.7  152.55
  2860.4  150.47  3452.2  149.15  4142.5  139.41  4919.3  137.46  4954.5   125.4
  4998.6  123.53  5080.1  137.33  5114.8  144.55  6098.3  154.89  6537.6  150.27
    6904  165.38  7167.1  170.74  7549.8  176.74    7817   175.6  8659.8  150.77
    8895   147.1  9186.5  161.48  9696.1  190.48 10029.3  192.31 10546.3  197.56
#Mann= 20 ,-1 , 0
 -2619.3     .15       0 -1631.3    .125       0 -1152.6     .11       0
    -231     .15       0    87.9     .11       0  1215.1    .125       0
  2336.7     .11       0  2860.4     .15       0  3452.2     .11       0
  4142.5    .125       0  4919.3     .09       0  5080.1    .125       0
  6098.3     .11       0    6904    .125       0  7167.1    .125       0
  7549.8    .125       0    7817     .11       0  8659.8     .15       0
  9186.5     .11       0 10029.3     .11       0
#XS Ineff= 2 ,-1
   -2065  1853.6   155.5  7808.9    9610  176.86
Permanent Ineff=
       F       F
Bank Sta=4919.3,5080.1
XS Rating Curve= 0 ,0
Exp/Cntr=0.3,0.1

Type RM Length L Ch R = 1 ,303800  ,2023,2023,2023
BEGIN DESCRIPTION:
WFSJ Main 301.0
END DESCRIPTION:
XS GIS Cut Line= 6
      3814675.68     10119613.13      3808210.48     10120658.05
      3807600.68     10120610.31      3807370.64     10120486.61
      3804753.81     10120194.73      3801630.85     10120576.38
#Sta/Elev= 30
 -2325.1  199.49 -2028.9  177.04 -1952.5  162.24 -1516.9  151.86  -933.4  141.41
  -327.1  140.95   474.6  144.44  2192.9  150.02  3391.1   151.4  3783.4  150.29
  3872.1  138.89  4294.8  135.91    4347  122.91  4517.5  138.29  4910.3  136.87
  4998.6  122.31  5052.3  125.44  5079.9  138.14  5220.4  146.51    5321  134.88
  5407.2  144.44  6198.1   150.4  6634.7  151.95  7285.5  175.67  7946.5  177.98
  8279.6  177.02    8711  178.32  9378.2  155.96 10601.7  185.41 10876.1  188.33
#Mann= 20 ,-1 , 0
 -2325.1     .11       0 -2028.9     .15       0 -1516.9     .11       0
  -933.4     .15       0  -327.1     .11       0   474.6     .17       0
  2192.9     .15       0  3391.1     .11       0  3783.4     .15       0
  4294.8    .125       0  4910.3     .09       0  5079.9     .15       0
  5407.2     .11       0  6198.1     .15       0  7285.5     .17       0
  7946.5    .125       0  8279.6     .11       0    8711     .17       0
  9378.2     .11       0 10601.7     .17       0
#XS Ineff= 2 ,-1
   -1615  3393.9  151.73  8561.2   10375  179.33
Permanent Ineff=
       F       F
Bank Sta=4910.3,5079.9
XS Rating Curve= 0 ,0
Exp/Cntr=0.3,0.1

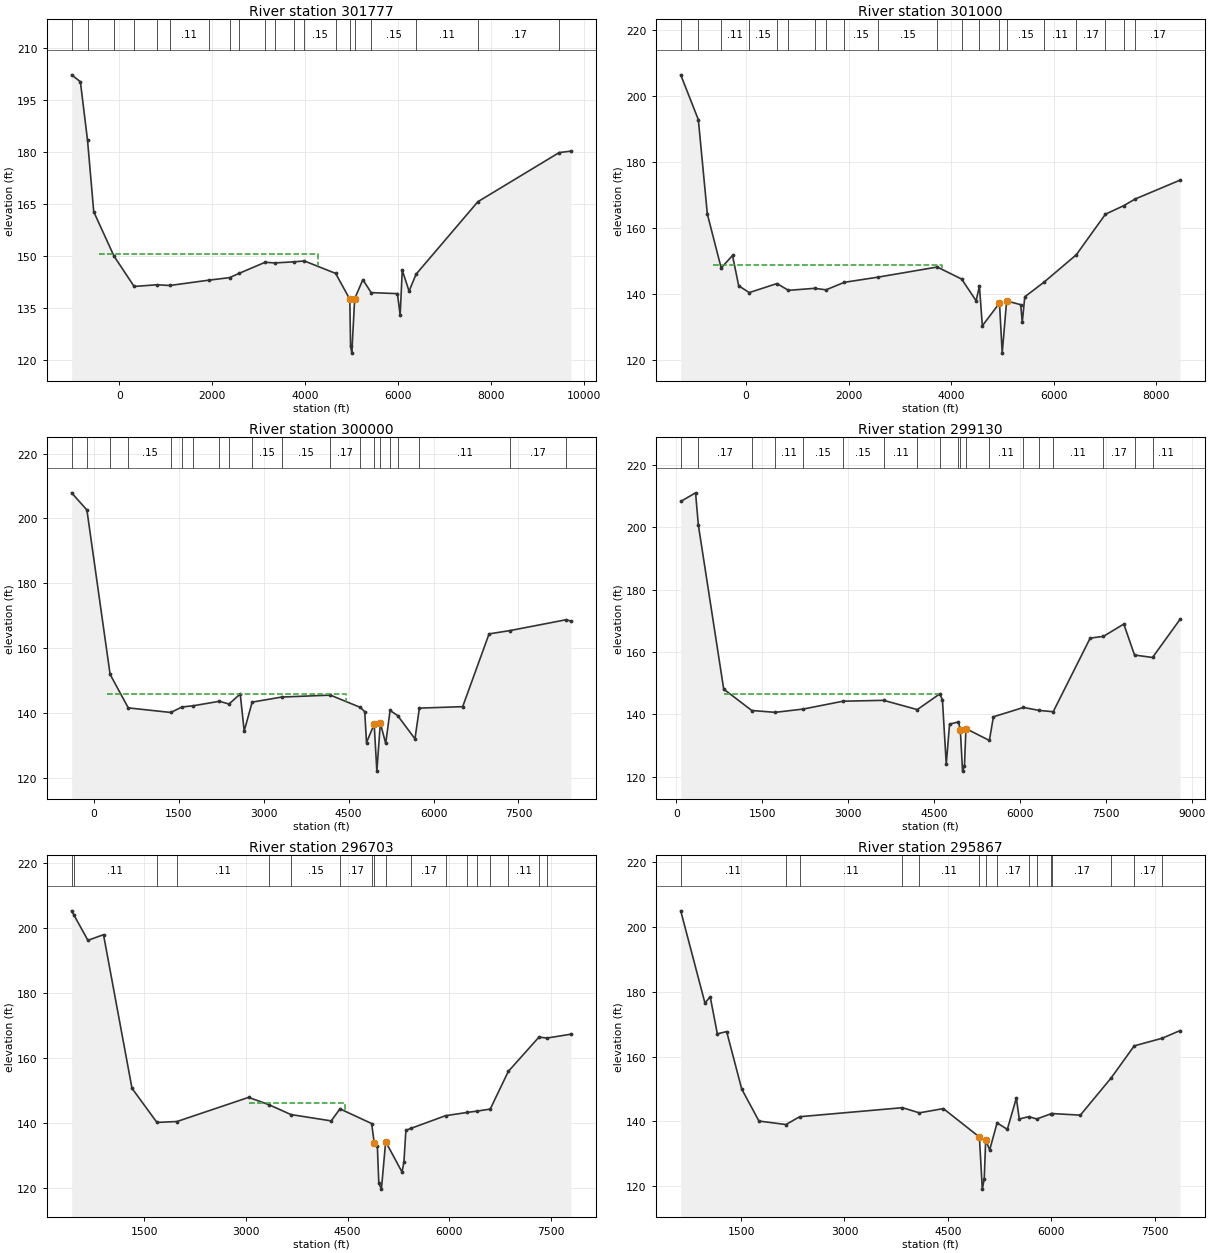
Type RM Length L Ch R = 1 ,301777  ,777,777,777
BEGIN DESCRIPTION:
WFSJ Main 300.0
END DESCRIPTION:
XS GIS Cut Line= 3
      3814736.46     10119508.96      3809406.59     10120272.85
      3804667.01     10117781.53
#Sta/Elev= 30
 -1027.7  202.16  -839.4  200.16  -685.5  183.29    -552  162.72  -116.2  149.95
   316.7  141.21   811.9   141.7  1082.7  141.49  1920.3  143.02  2368.7  143.75
  2580.5  145.02    3134  148.17  3343.8  147.99  3753.7   148.3  3977.5  148.56
  4650.7  144.97  4955.6  137.53  4971.9  123.98  4998.6  122.01  5060.1  137.68
  5236.5  143.16  5415.6  139.44  5979.8  139.14  6038.5  132.96  6083.7  145.89
  6230.6  139.86  6380.9  144.74  7710.2  165.62  9458.5  179.77  9711.1  180.18
#Mann= 20 ,-1 , 0
 -1027.7     .11       0  -685.5     .15       0  -116.2     .11       0
   316.7     .15       0   811.9     .15       0  1082.7     .11       0
  1920.3     .17       0  2368.7     .15       0  2580.5     .17       0
    3134     .17       0  3343.8     .11       0  3753.7    .125       0
  3977.5     .15       0  4650.7     .11       0  4955.6     .09       0
  5060.1     .15       0  5415.6     .15       0  6380.9     .11       0
  7710.2     .17       0  9458.5     .11       0
#XS Ineff= 1 ,-1
    -440  4264.4  150.49
Permanent Ineff=
       F
Bank Sta=4955.6,5060.1
XS Rating Curve= 0 ,0
Exp/Cntr=0.3,0.1

Type RM Length L Ch R = 1 ,301000  ,1000,1000,1000
BEGIN DESCRIPTION:
WFSJ Main 299.0
END DESCRIPTION:
XS GIS Cut Line= 5
       3814745.1     10119396.12      3810708.68     10119752.02
      3809378.19     10119738.13      3808580.87     10119333.42
      3805622.37     10117521.42
#Sta/Elev= 30
 -1276.8  206.36  -933.1  192.78  -757.5  164.21  -487.2  147.85  -265.6  151.64
  -145.2  142.45    60.7  140.39   602.6  143.13   825.6  141.07  1335.7  141.68
  1560.6  141.23  1916.4   143.5    2570  145.06  3730.7  148.14  4207.2  144.48
  4489.6  137.91    4554  142.37  4610.9  130.33  4945.8  137.22  4998.6  122.05
  5085.2  137.87  5359.9  136.72  5390.5  131.37  5439.3  139.11  5821.2  143.63
  6444.6  151.84    7014  164.14  7369.4  166.71  7595.5  168.75  8469.3  174.45
#Mann= 20 ,-1 , 0
 -1276.8     .11       0  -933.1     .15       0  -487.2     .11       0
    60.7     .15       0   602.6     .15       0   825.6     .17       0
  1335.7     .15       0  1560.6     .17       0  1916.4     .15       0
    2570     .15       0  3730.7     .11       0  4207.2     .11       0
    4554     .15       0  4945.8     .09       0  5085.2     .15       0
  5821.2     .11       0  6444.6     .17       0    7014     .11       0
  7369.4     .11       0  7595.5     .17       0
#XS Ineff= 1 ,-1
    -655  3816.2  148.62
Permanent Ineff=
       F
Bank Sta=4945.8,5085.2
XS Rating Curve= 0 ,0
Exp/Cntr=0.3,0.1

Type RM Length L Ch R = 1 ,300000  ,870,870,870
BEGIN DESCRIPTION:
WFSJ Main 298.0
END DESCRIPTION:
XS GIS Cut Line= 4
      3814675.67     10119335.35      3810760.76      10119448.2
      3809340.79     10119038.23      3806316.69     10117425.83
#Sta/Elev= 30
  -394.5  207.89  -124.6   202.6   285.1  151.92   606.4  141.57  1357.6  140.16
  1555.2  141.85  1752.9  142.22  2217.2  143.61  2386.2  142.76  2584.6  145.87
  2654.6  134.43  2795.4  143.35  3316.2  144.91  4176.9  145.51  4706.5  141.73
  4784.5  140.38  4815.7  130.88    4951  136.54  4998.6  122.07    5060  136.89
  5154.8  130.62  5232.4  140.78  5365.8   139.2    5672  132.03  5749.7   141.5
  6514.9  141.95  6981.1  164.39  7349.9  165.41  8347.2  168.77  8427.1  168.32
#Mann= 20 ,-1 , 0
  -394.5     .11       0  -124.6     .15       0   285.1     .11       0
   606.4     .15       0  1357.6     .11       0  1555.2     .15       0
  1752.9     .17       0  2217.2     .15       0  2386.2     .17       0
  2795.4     .15       0  3316.2     .15       0  4176.9     .17       0
  4706.5     .15       0    4951     .09       0    5060     .15       0
  5232.4     .11       0  5365.8     .15       0  5749.7     .11       0
  7349.9     .17       0  8347.2     .17       0
#XS Ineff= 1 ,-1
     235  4461.8  145.96
Permanent Ineff=
       F
Bank Sta=4951,5060
XS Rating Curve= 0 ,0
Exp/Cntr=0.3,0.1

Type RM Length L Ch R = 1 ,299130  ,2427,2427,2427
BEGIN DESCRIPTION:
WFSJ Main 297.0
END DESCRIPTION:
XS GIS Cut Line= 4
      3814675.64     10119248.54       3811637.5     10118979.45
      3809996.87     10118502.02      3806352.64     10116950.21
#Sta/Elev= 30
    76.7  208.32   335.9  211.08   383.9  200.83   827.4  148.14  1318.4  141.28
    1725  140.69  2218.6  141.75  2909.6  144.26  3620.4  144.54  4208.3  141.57
  4598.1  146.58  4647.1  144.75  4714.1   124.1  4771.9   136.9    4927  137.62
 4959.74  135.15  4998.6  121.84  5032.3  123.56 5057.59  135.48  5467.2  131.68
  5537.6  139.26    6063  142.26  6338.8   141.3  6581.9  140.89  7227.6  164.49
  7459.6  165.06  7814.6     169    8002  159.08  8316.2  158.28  8796.3  170.49
#Mann= 19 ,-1 , 0
    76.7     .11       0   383.9     .17       0  1318.4     .15       0
    1725     .11       0  2218.6     .15       0  2909.6     .15       0
  3620.4     .11       0  4208.3     .17       0  4598.1     .15       0
    4927     .12       0 4959.74     .09       0 5057.59     .15       0
  5467.2     .11       0    6063     .11       0  6338.8     .11       0
  6581.9     .11       0  7459.6     .17       0    8002     .17       0
  8316.2     .11       0
#XS Ineff= 1 ,-1
     830  4594.9  146.69
Permanent Ineff=
       F
Bank Sta=4959.74,5057.59
XS Rating Curve= 0 ,0
Exp/Cntr=0.3,0.1

Type RM Length L Ch R = 1 ,296703  ,836,836,836
BEGIN DESCRIPTION:
WFSJ Main 296.0
END DESCRIPTION:
XS GIS Cut Line= 3
      3814750.76      10118816.4      3810508.19     10117297.32
      3808252.07     10115540.15
#Sta/Elev= 30
   428.1  205.26   458.2  204.12   668.3  196.19   898.5  197.93  1318.6  150.73
  1686.5  140.23  1982.3  140.51  3039.2  147.93  3340.2  145.67  3663.1  142.65
  4258.1   140.7  4386.8   144.4 4854.69139.8827  4892.3  133.93  4938.8  132.84
  4960.2  121.51  4998.6  119.73    5061  134.32  5302.4  124.99  5330.6  128.09
  5359.5  137.81  5439.3  138.44  5944.1   142.3  6265.2   143.3    6414  143.72
  6604.2  144.34  6870.3   155.9  7323.2  166.46  7442.9  166.16  7794.1  167.35
#Mann= 18 ,-1 , 0
   428.1     .17       0   458.2     .11       0  1686.5     .15       0
  1982.3     .11       0  3340.2     .17       0  3663.1     .15       0
  4386.8     .17       0 4854.69     .15       0  4892.3     .09       0
    5061     .15       0  5439.3     .17       0  5944.1     .15       0
  6265.2     .17       0    6414     .15       0  6604.2     .17       0
  6870.3     .11       0  7323.2     .17       0  7442.9     .11       0
#XS Ineff= 2 ,-1
    1370  3039.2  147.93    3040  4462.8  146.17
Permanent Ineff=
       F       F
Bank Sta=4892.3,5061
XS Rating Curve= 0 ,0
Exp/Cntr=0.3,0.1

Type RM Length L Ch R = 1 ,295867  ,867,867,867
BEGIN DESCRIPTION:
WFSJ Main 295.0
END DESCRIPTION:
XS GIS Cut Line= 3
      3814859.31     10118295.58      3810920.51     10116928.39
      3808316.34     10115300.78
#Sta/Elev= 30
   625.2  204.88   976.1   176.5    1053  178.39    1156  166.99  1291.5  167.68
  1509.3     150  1759.4  140.12  2151.2  139.04  2349.8  141.45    3840  144.23
  4085.3  142.64  4433.9  143.95 4956.46  135.19  4998.6  119.14  5026.5  122.26
  5047.7  134.31  5105.5  131.21  5212.8  139.54  5361.4  137.57  5492.3  147.19
  5534.7  140.76  5673.9  141.47  5787.6  140.75  5997.4  142.37  6014.8  142.42
  6420.3  141.93  6867.1   153.4  7201.9  163.28  7605.7  165.62  7865.5  167.98
#Mann= 15 ,-1 , 0
   625.2     .11       0  2151.2     .15       0  2349.8     .11       0
    3840     .15       0  4085.3     .11       0 4956.46     .07       0
  5047.7     .11       0  5212.8     .17       0  5673.9     .15       0
  5787.6     .17       0  5997.4     .15       0  6014.8     .17       0
  6867.1     .11       0  7201.9     .17       0  7605.7     .11       0
#XS Ineff= 1 ,-1
  5492.3    6715  147.19
Permanent Ineff=
       F
Bank Sta=4956.46,5047.7
XS Rating Curve= 0 ,0
Exp/Cntr=0.3,0.1

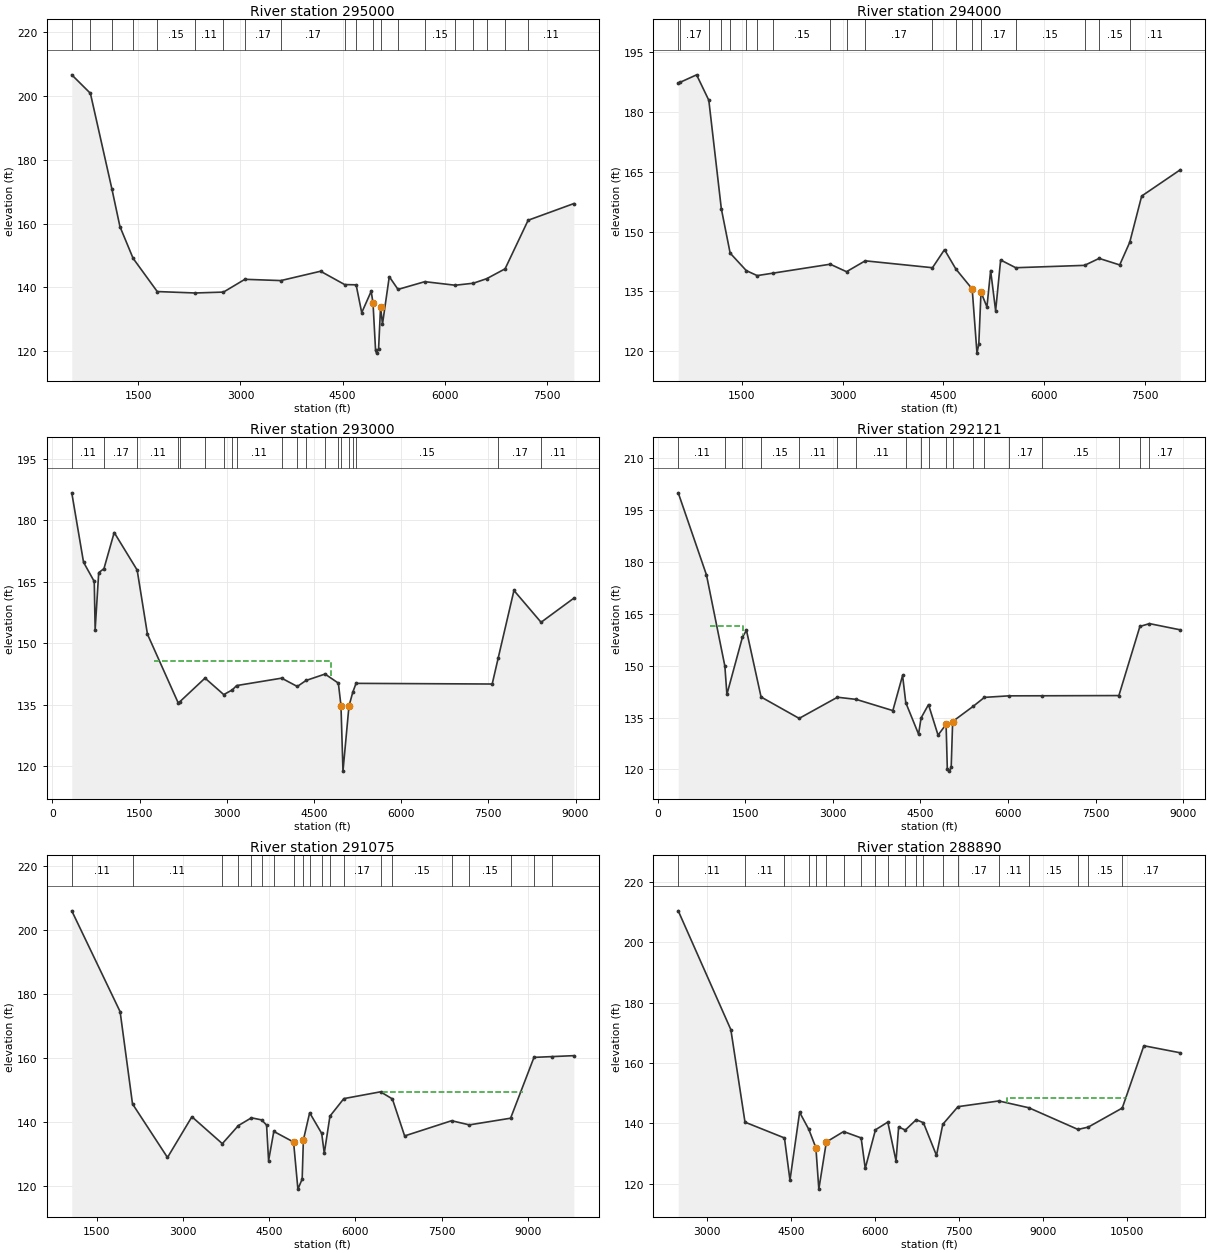
Type RM Length L Ch R = 1 ,295000  ,1000,1000,1000
BEGIN DESCRIPTION:
WFSJ Main 294.0
END DESCRIPTION:
XS GIS Cut Line= 3
      3815380.13     10117828.99      3811223.65     10116163.09
      3808643.35     10114845.81
#Sta/Elev= 30
   522.1  206.65   795.6  200.85  1112.4  170.77  1229.5  159.05  1422.5   149.1
  1777.5  138.66    2332  138.21  2750.7  138.49  3064.8   142.5  3593.3   142.1
  4176.7  145.03  4530.4  140.85    4699  140.77  4781.2  132.04  4920.1  138.73
 4946.85  135.12  4984.7   120.2  4998.6  119.34    5029  120.74  5058.2  133.88
  5086.1  128.43    5186  143.32  5314.4  139.33  5707.9  141.76    6154  140.64
  6420.4  141.27  6617.5   142.7  6887.2  145.79  7225.6  161.03  7897.1  166.26
#Mann= 20 ,-1 , 0
   522.1     .11       0   795.6     .17       0  1112.4     .11       0
  1422.5     .17       0  1777.5     .15       0    2332     .11       0
  2750.7     .15       0  3064.8     .17       0  3593.3     .17       0
  4530.4     .11       0    4699     .15       0 4946.85     .09       0
  5058.2     .15       0  5314.4     .17       0  5707.9     .15       0
    6154     .15       0  6420.4     .11       0  6617.5     .15       0
  6887.2     .17       0  7225.6     .11       0
Bank Sta=4946.85,5058.2
XS Rating Curve= 0 ,0
Exp/Cntr=0.3,0.1

Type RM Length L Ch R = 1 ,294000  ,1000,1000,1000
BEGIN DESCRIPTION:
WFSJ Main 293.0
END DESCRIPTION:
XS GIS Cut Line= 3
      3815900.97      10117145.4      3811821.22     10115382.62
      3809075.86     10114118.05
#Sta/Elev= 30
   555.7  187.28   577.9  187.42   828.7  189.34  1010.5  182.95  1196.5  155.73
  1327.7  144.59  1568.2  140.19  1730.1  138.94  1962.1  139.55  2815.9   141.8
  3058.2  139.92  3336.7  142.65  4336.9  140.92  4515.6  145.46    4684  140.61
  4927.4  135.59  4998.6  119.48  5025.7  121.74  5058.4  134.77  5146.8  131.07
  5201.6  140.22    5276  130.12  5350.4  142.86    5575  140.92  6597.9  141.51
  6815.9  143.26  7121.1  141.62  7270.4   147.3  7447.9  158.91  8022.6  165.51
#Mann= 19 ,-1 , 0
   555.7     .15       0   577.9     .17       0  1010.5     .11       0
  1196.5    .125       0  1327.7     .15       0  1568.2     .11       0
  1730.1     .15       0  1962.1     .15       0  2815.9     .11       0
  3058.2     .15       0  3336.7     .17       0  4336.9     .11       0
    4684     .17       0  4927.4     .07       0  5058.4     .17       0
    5575     .15       0  6597.9     .17       0  6815.9     .15       0
  7270.4     .11       0
#XS Ineff= 1 ,-1
    1270  4515.6  145.46
Permanent Ineff=
       F
Bank Sta=4927.4,5058.4
XS Rating Curve= 0 ,0
Exp/Cntr=0.3,0.1

Type RM Length L Ch R = 1 ,293000  ,879,879,879
BEGIN DESCRIPTION:
WFSJ Main 292.0
END DESCRIPTION:
XS GIS Cut Line= 3
      3816682.26     10116828.58      3812525.91     10114704.16
      3809260.37     10112444.89
#Sta/Elev= 30
   332.2  186.64   534.6  169.71     719  165.01   734.5  153.27   795.6  167.16
   886.2  168.15  1062.2  176.96  1457.2   167.8  1634.2  152.16  2160.5  135.49
  2188.4  135.64    2625  141.44  2947.1  137.42  3094.6  138.57  3168.5  139.62
  3943.2  141.43  4212.6   139.4    4364  140.87  4690.1  142.43  4919.2  140.22
  4964.1  134.72  4998.6  118.75  5101.6  134.61  5167.1  137.99  5223.5  140.16
  7566.1     140  7670.1  146.39  7940.4  162.82  8406.9  155.06  8970.9  160.94
#Mann= 20 ,-1 , 0
   332.2     .11       0   886.2     .17       0  1457.2     .11       0
  2160.5     .15       0  2188.4     .11       0    2625     .15       0
  2947.1     .11       0  3094.6     .15       0  3168.5     .11       0
  3943.2     .17       0  4212.6     .11       0    4364     .17       0
  4690.1     .11       0  4919.2     .17       0  4964.1     .09       0
  5101.6     .17       0  5167.1     .15       0  5223.5     .15       0
  7670.1     .17       0  8406.9     .11       0
#XS Ineff= 1 ,-1
    1740  4799.7  145.55
Permanent Ineff=
       F
Bank Sta=4964.1,5101.6
XS Rating Curve= 0 ,0
Exp/Cntr=0.3,0.1

Type RM Length L Ch R = 1 ,292121  ,1046,1046,1046
BEGIN DESCRIPTION:
WFSJ Main 291.0
END DESCRIPTION:
XS GIS Cut Line= 4
      3817185.72     10116186.21      3815942.42     10115894.47
      3811444.61     10112986.02      3809652.22     10112176.34
#Sta/Elev= 30
   352.6  199.89   836.5  176.16  1151.3  149.85  1186.2  141.68  1452.6  158.22
  1521.4  160.17  1771.5  140.93    2424  134.75  3079.3  140.86  3400.8  140.24
  4028.7     137  4195.4  147.14  4250.3  139.29  4469.3  130.19  4511.9  134.86
  4639.4  138.74  4802.8  129.92  4940.7  133.02  4961.8  120.17  4998.6  119.52
  5028.4  120.75 5053.14  133.85  5405.1  138.24  5597.5  140.82  6015.2  141.26
  6582.2  141.28  7900.4  141.34  8260.4   161.3  8423.9  162.12  8952.7  160.32
#Mann= 19 ,-1 , 0
   352.6     .11       0  1151.3     .11       0  1452.6     .17       0
  1771.5     .15       0    2424     .11       0  3079.3     .15       0
  3400.8     .11       0  4250.3     .15       0  4511.9     .15       0
  4639.4     .17       0  4940.7     .09       0 5053.14     .15       0
  5405.1     .11       0  5597.5     .15       0  6015.2     .17       0
  6582.2     .15       0  7900.4     .17       0  8260.4     .11       0
  8423.9     .17       0
#XS Ineff= 2 ,-1
     905    1470  161.48    1615  4195.4  147.14
Permanent Ineff=
       F       F
Bank Sta=4940.7,5053.14
XS Rating Curve= 0 ,0
Exp/Cntr=0.3,0.1

Type RM Length L Ch R = 1 ,291075  ,2185,2185,2185
BEGIN DESCRIPTION:
WFSJ Main 290.0
END DESCRIPTION:
XS GIS Cut Line= 4
      3817437.47     10115995.25      3814322.86     10114138.75
      3813336.75     10113381.81      3809683.98     10112131.81
#Sta/Elev= 30
  1066.7  206.03  1907.6  174.45  2122.7   145.6    2731  128.82  3155.4  141.57
  3684.6  133.15  3964.1  138.82  4190.2  141.24  4366.8  140.59    4454  138.97
  4488.9  127.83  4579.7  136.98  4923.3  133.66  4998.6  118.92  5072.8  122.07
  5093.6  134.28  5202.9  142.82  5412.2  136.37  5457.1  130.14  5555.7  141.76
  5797.3  147.25  6435.4  149.38  6641.3  147.15  6854.3  135.57    7671  140.33
  7979.4  139.03  8696.8  141.12  9103.4  160.16  9415.2   160.4  9796.5   160.7
#Mann= 20 ,-1 , 0
  1066.7     .11       0  2122.7     .11       0  3684.6     .11       0
  3964.1     .15       0  4190.2     .11       0  4366.8     .15       0
  4579.7     .11       0  4923.3     .09       0  5093.6     .15       0
  5202.9     .17       0  5412.2     .15       0  5555.7     .11       0
  5797.3     .17       0  6435.4     .11       0  6641.3     .15       0
    7671     .17       0  7979.4     .15       0  8696.8     .17       0
  9103.4     .11       0  9415.2     .17       0
#XS Ineff= 1 ,-1
  6478.7    8915  149.39
Permanent Ineff=
       F
Bank Sta=4923.3,5093.6
XS Rating Curve= 0 ,0
Exp/Cntr=0.3,0.1

Type RM Length L Ch R = 1 ,288890  ,1531,1531,1531
BEGIN DESCRIPTION:
WFSJ Main 288.0
END DESCRIPTION:
XS GIS Cut Line= 5
      3817567.63     10115977.86      3815788.14     10114762.59
      3815348.96     10113879.71      3813600.17     10113077.26
      3809824.07     10112055.74
#Sta/Elev= 30
  2484.7  210.39  3425.3  171.06  3678.3  140.43  4383.8   135.2  4482.5  121.22
  4654.7   143.7    4820  138.01  4945.9  131.95  4998.6  118.26  5132.7  133.86
  5441.7  137.32  5754.8  135.21  5828.3  125.14    6011   137.9  6231.7  140.45
  6379.1  127.58  6425.1  138.83  6544.8  137.82  6739.6  141.23  6868.3  140.25
  7101.9  129.42  7214.8  139.72  7486.4  145.56  8216.3  147.45  8752.6   145.2
  9631.9  138.02  9816.4   138.8 10423.4   145.1 10809.8  165.73 11461.6  163.39
#Mann= 20 ,-1 , 0
  2484.7     .11       0  3678.3     .11       0  4383.8     .11       0
    4820     .15       0  4945.9     .09       0  5132.7     .15       0
  5441.7     .11       0  5754.8     .15       0    6011     .17       0
  6231.7     .17       0  6544.8     .17       0  6739.6     .11       0
  6868.3     .17       0  7214.8     .15       0  7486.4     .17       0
  8216.3     .11       0  8752.6     .15       0  9631.9     .11       0
  9816.4     .15       0 10423.4     .17       0
#XS Ineff= 1 ,-1
  8370.6   10500  148.59
Permanent Ineff=
       F
Bank Sta=4945.9,5132.7
XS Rating Curve= 0 ,0
Exp/Cntr=0.3,0.1

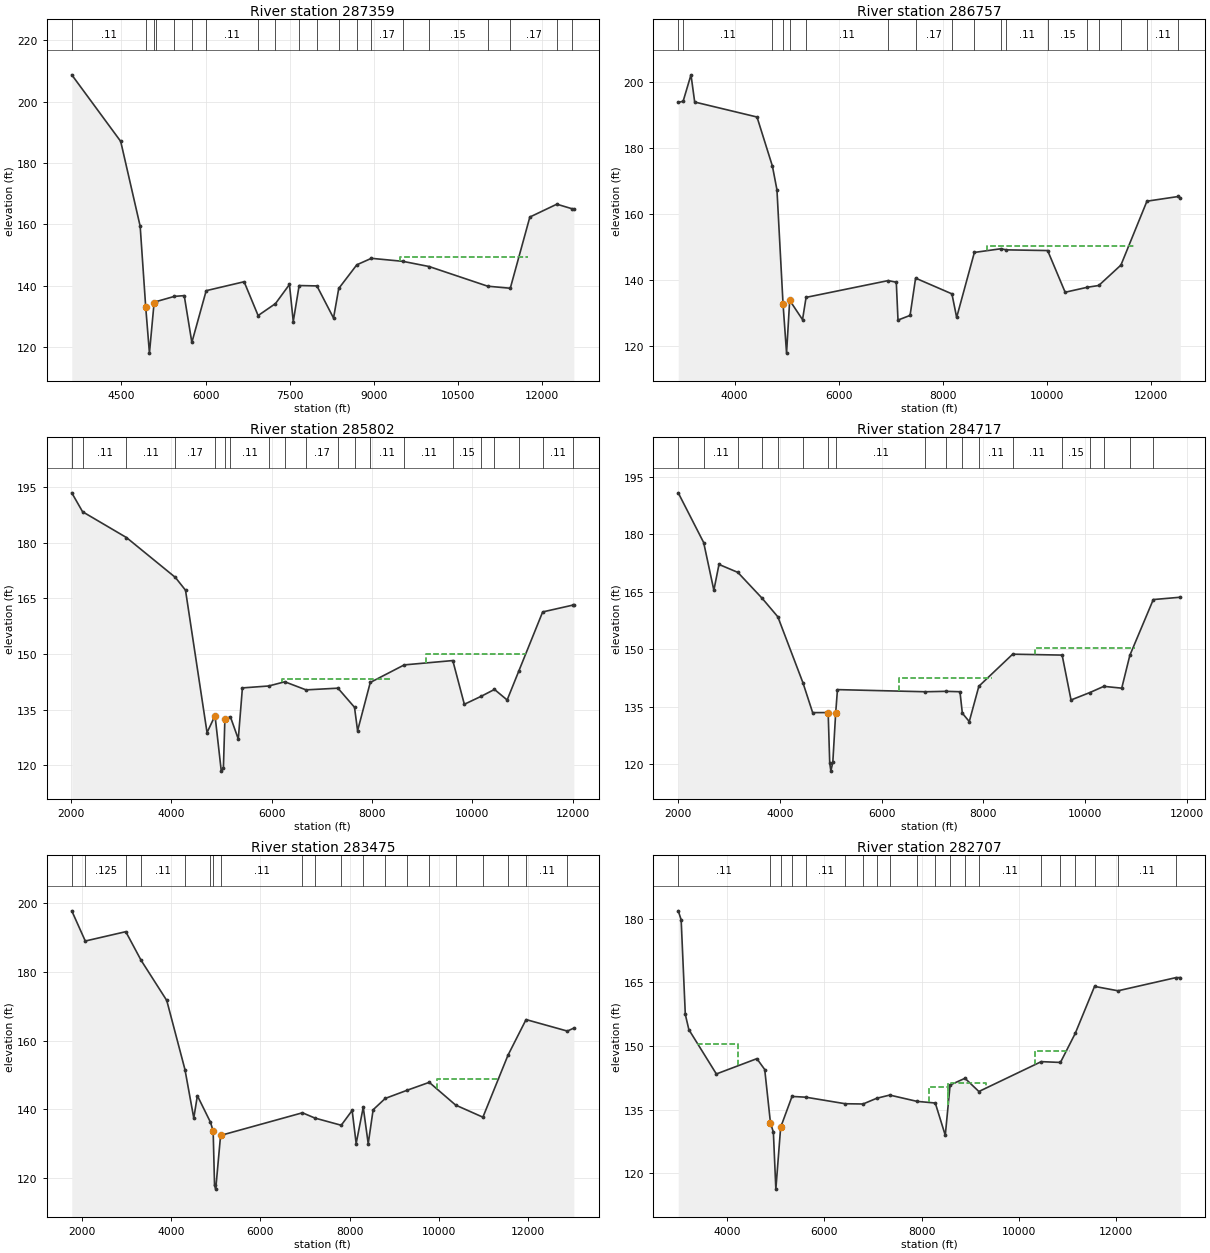
Type RM Length L Ch R = 1 ,287359  ,602,602,602
BEGIN DESCRIPTION:
WFSJ Main 287.0
END DESCRIPTION:
XS GIS Cut Line= 4
      3817715.23     10115917.12       3816161.4     10114207.04
      3813453.81      10112904.7      3809927.02     10111999.86
#Sta/Elev= 30
  3613.2  208.73  4486.1  187.04  4833.4  159.39    4932  133.11  4998.6  118.05
  5080.7  134.28  5118.5  134.84  5444.1  136.54  5619.3  136.79  5755.3  121.53
  6011.1   138.4  6687.6  141.31  6937.3  130.29    7247  134.19  7496.3  140.42
  7564.2  128.34    7669  140.07  7986.2  139.95  8282.5  129.48  8375.3  139.11
  8697.8  146.83  8957.8  148.94    9519  147.96  9986.7  146.27   11032  139.86
 11435.5  139.19 11784.4  162.39 12265.7  166.58   12545  165.05 12569.3  164.93
#Mann= 20 ,-1 , 0
  3613.2     .11       0    4932     .07       0  5080.7     .11       0
  5118.5     .15       0  5444.1     .17       0  5755.3     .15       0
  6011.1     .11       0  6937.3     .15       0    7247     .17       0
    7669     .17       0  7986.2     .17       0  8375.3     .15       0
  8697.8     .17       0  8957.8     .17       0    9519     .11       0
  9986.7     .15       0   11032     .15       0 11435.5     .17       0
 12265.7     .11       0   12545     .17       0
#XS Ineff= 1 ,-1
    9461   11750  149.23
Permanent Ineff=
       F
Bank Sta=4932,5080.7
XS Rating Curve= 0 ,0
Exp/Cntr=0.3,0.1

Type RM Length L Ch R = 1 ,286757  ,955,955,955
BEGIN DESCRIPTION:
WFSJ Main 286.0
END DESCRIPTION:
XS GIS Cut Line= 4
      3818453.07     10115821.62      3817289.87     10114484.82
      3813554.94     10112660.89      3809913.14     10111909.59
#Sta/Elev= 30
  2917.3  193.67  3011.7  194.06  3162.3  202.03  3233.5  193.81  4430.8  189.28
  4726.9  174.43    4814  167.28 4930.76  132.85  4998.6  117.92  5058.8  133.88
  5305.5  128.04  5373.6  134.77  6951.3  139.84  7107.1  139.35  7139.9  127.91
  7371.8  129.32  7477.9  140.58  8176.1  135.83  8266.9  128.71  8607.2  148.35
  9113.9  149.46  9224.3  149.13 10015.1  148.92 10351.7  136.32 10779.2  137.83
 10997.2  138.36 11423.2  144.53   11923  163.84 12527.3  165.26 12564.3  164.79
#Mann= 18 ,-1 , 0
  2917.3    .125       0  3011.7     .11       0  4726.9     .17       0
 4930.76     .09       0  5058.8     .15       0  5373.6     .11       0
  6951.3     .15       0  7477.9     .17       0  8176.1     .15       0
  8607.2     .11       0  9113.9     .17       0  9224.3     .11       0
 10015.1     .15       0 10779.2     .17       0 10997.2     .15       0
 11423.2     .17       0   11923     .11       0 12527.3     .17       0
#XS Ineff= 1 ,-1
  8845.8   11690  150.26
Permanent Ineff=
       F
Bank Sta=4930.76,5058.8
XS Rating Curve= 0 ,0
Exp/Cntr=0.3,0.1

Type RM Length L Ch R = 1 ,285802  ,1085,1085,1085
BEGIN DESCRIPTION:
WFSJ Main 285.0
END DESCRIPTION:
XS GIS Cut Line= 4
      3818617.98     10115734.79      3817350.64     10113859.82
      3814562.83     10112638.85        3809934.     10111812.37
#Sta/Elev= 30
  2018.1  193.46  2233.8  188.36  3108.7  181.41  4083.3  170.67  4285.5  167.22
  4714.9  128.86  4873.8  133.44  4998.6  118.48  5040.7  119.25  5070.3  132.46
    5180  133.13  5337.6  127.13  5419.6   140.9  5944.5  141.42  6264.6  142.55
  6688.3  140.37    7324  140.83  7654.3  135.68  7715.7  129.36  7968.6  142.37
  8645.5   147.1  9613.5  148.27  9843.8  136.49 10182.4  138.66 10444.5  140.49
 10697.1  137.65 10933.1  145.57 11405.3  161.37 12016.8  163.24 12026.7  163.21
#Mann= 20 ,-1 , 0
  2018.1     .11       0  2233.8     .11       0  3108.7     .11       0
  4083.3     .17       0  4873.8     .09       0  5070.3     .15       0
    5180     .11       0  5944.5     .17       0  6264.6     .17       0
  6688.3     .17       0    7324     .15       0  7654.3     .15       0
  7968.6     .11       0  8645.5     .11       0  9613.5     .15       0
 10182.4     .17       0 10444.5     .15       0 10933.1     .17       0
 11405.3     .11       0 12016.8     .17       0
#XS Ineff= 2 ,-1
  6210.5    8400  143.18  9076.9   11080  150.02
Permanent Ineff=
       F       F
Bank Sta=4873.8,5070.3
XS Rating Curve= 0 ,0
Exp/Cntr=0.3,0.1

Type RM Length L Ch R = 1 ,284717  ,1242,1242,1242
BEGIN DESCRIPTION:
WFSJ Main 284.0
END DESCRIPTION:
XS GIS Cut Line= 3
      3818577.22     10115242.96      3817286.49     10113110.18
      3810024.66     10111779.37
#Sta/Elev= 30
  1996.6  190.84  2497.1  177.84  2697.3  165.39  2798.2  172.13  3169.1  170.05
  3649.4  163.25  3955.9  158.44  4450.4  141.18  4640.6  133.41  4945.6  133.42
  4976.1  120.34  4998.6  118.12  5037.1  120.43 5093.46  133.31  5128.6  139.42
  6858.4  138.86  7256.8  138.97  7538.1  138.87  7584.8  133.26  7721.1  131.07
  7909.7   140.3  8574.9  148.68  9547.8  148.44  9722.9  136.71 10094.1  138.66
 10367.9  140.27 10720.2   139.8 10879.9  148.39 11340.7  162.95 11872.3  163.56
#Mann= 18 ,-1 , 0
  1996.6     .11       0  2497.1     .11       0  3169.1     .17       0
  3649.4     .11       0  3955.9     .11       0  4450.4     .17       0
  4945.6     .07       0 5093.46     .11       0  6858.4     .17       0
  7256.8     .15       0  7584.8     .15       0  7909.7     .11       0
  8574.9     .11       0  9547.8     .15       0 10094.1     .17       0
 10367.9     .15       0 10879.9     .17       0 11340.7     .11       0
#XS Ineff= 2 ,-1
  6338.2    8160  142.53  9012.3   10980  150.22
Permanent Ineff=
       F       F
Bank Sta=4945.6,5093.46
XS Rating Curve= 0 ,0
Exp/Cntr=0.3,0.1

Type RM Length L Ch R = 1 ,283475  ,768,768,768
BEGIN DESCRIPTION:
WFSJ Main 283.0
END DESCRIPTION:
XS GIS Cut Line= 3
      3820506.45     10113157.41      3817175.29     10111920.43
      3809482.47     10111714.28
#Sta/Elev= 30
  1773.4  197.76  2076.2  188.97  2983.5  191.69  3326.7  183.36  3901.5  171.67
  4309.2  151.57  4507.2  137.44  4587.6  143.96  4880.6  136.24  4941.3  133.68
  4972.1  117.86  4998.6  116.76  5107.5  132.39    6942  138.98  7219.3  137.45
  7810.9  135.35  8055.2  139.66  8145.3  130.03  8303.8   140.6  8415.4  129.96
  8525.4  139.86  8796.8  143.16  9289.8  145.55  9782.8  147.84 10374.4  141.22
 10984.8   137.7 11546.6  155.73 11951.9  166.11 12876.6  162.76 13022.4  163.63
#Mann= 20 ,-1 , 0
  1773.4     .17       0  2076.2    .125       0  2983.5    .125       0
  3326.7     .11       0  4309.2     .17       0  4880.6     .12       0
  4941.3     .07       0  5107.5     .11       0    6942     .17       0
  7219.3     .11       0  7810.9     .17       0  8303.8     .15       0
  8796.8     .17       0  9289.8     .11       0  9782.8     .17       0
 10374.4     .15       0 10984.8     .11       0 11546.6     .17       0
 11951.9     .11       0 12876.6    .125       0
#XS Ineff= 3 ,-1
  8303.8    8650   140.6  9965.1   11370  148.69    4400  4587.6  143.96
Permanent Ineff=
       F       F       F
Bank Sta=4941.3,5107.5
XS Rating Curve= 0 ,0
Exp/Cntr=0.3,0.1

Type RM Length L Ch R = 1 ,282707  ,415,415,415
BEGIN DESCRIPTION:
WFSJ Main 282.0
END DESCRIPTION:
XS GIS Cut Line= 3
      3819546.82     10110806.86      3818097.16     10111266.93
      3809277.71     10111579.43
#Sta/Elev= 30
  2987.1  181.82  3047.2  179.72  3132.9  157.44  3206.3  153.85  3772.8  143.42
  4607.4  147.02  4769.3  144.46  4887.6   131.9  4947.6  129.72  4998.6  116.31
  5097.7  130.86  5331.9  138.13  5616.8  137.95  6428.4  136.41  6795.1  136.35
  7075.2  137.69  7345.4  138.45  7905.6  136.97  8283.9  136.58  8489.8  128.98
  8589.3  140.82    8896   142.4  9182.5  139.29 10467.6  146.32   10863  146.13
 11167.1  152.95 11565.9  164.03 12049.3     163 13235.6  166.08   13333  166.11
#Mann= 20 ,-1 , 0
  2987.1     .11       0  4887.6     .06       0  5097.7     .11       0
  5331.9     .17       0  5616.8     .11       0  6428.4     .15       0
  6795.1     .11       0  7075.2     .17       0  7345.4     .15       0
  7905.6     .17       0  8283.9     .15       0  8589.3     .11       0
    8896     .17       0  9182.5     .11       0 10467.6     .15       0
   10863    .125       0 11167.1     .11       0 11565.9     .17       0
 12049.3     .11       0 13235.6     .11       0
#XS Ineff= 4 ,-1
    3370  4213.5  150.42  8159.7  8549.8  140.26  8549.9    9338   141.4
   10341   11050  148.94
Permanent Ineff=
       F       F       F       F
Bank Sta=4887.6,5097.7
XS Rating Curve= 0 ,0
Exp/Cntr=0.3,0.1