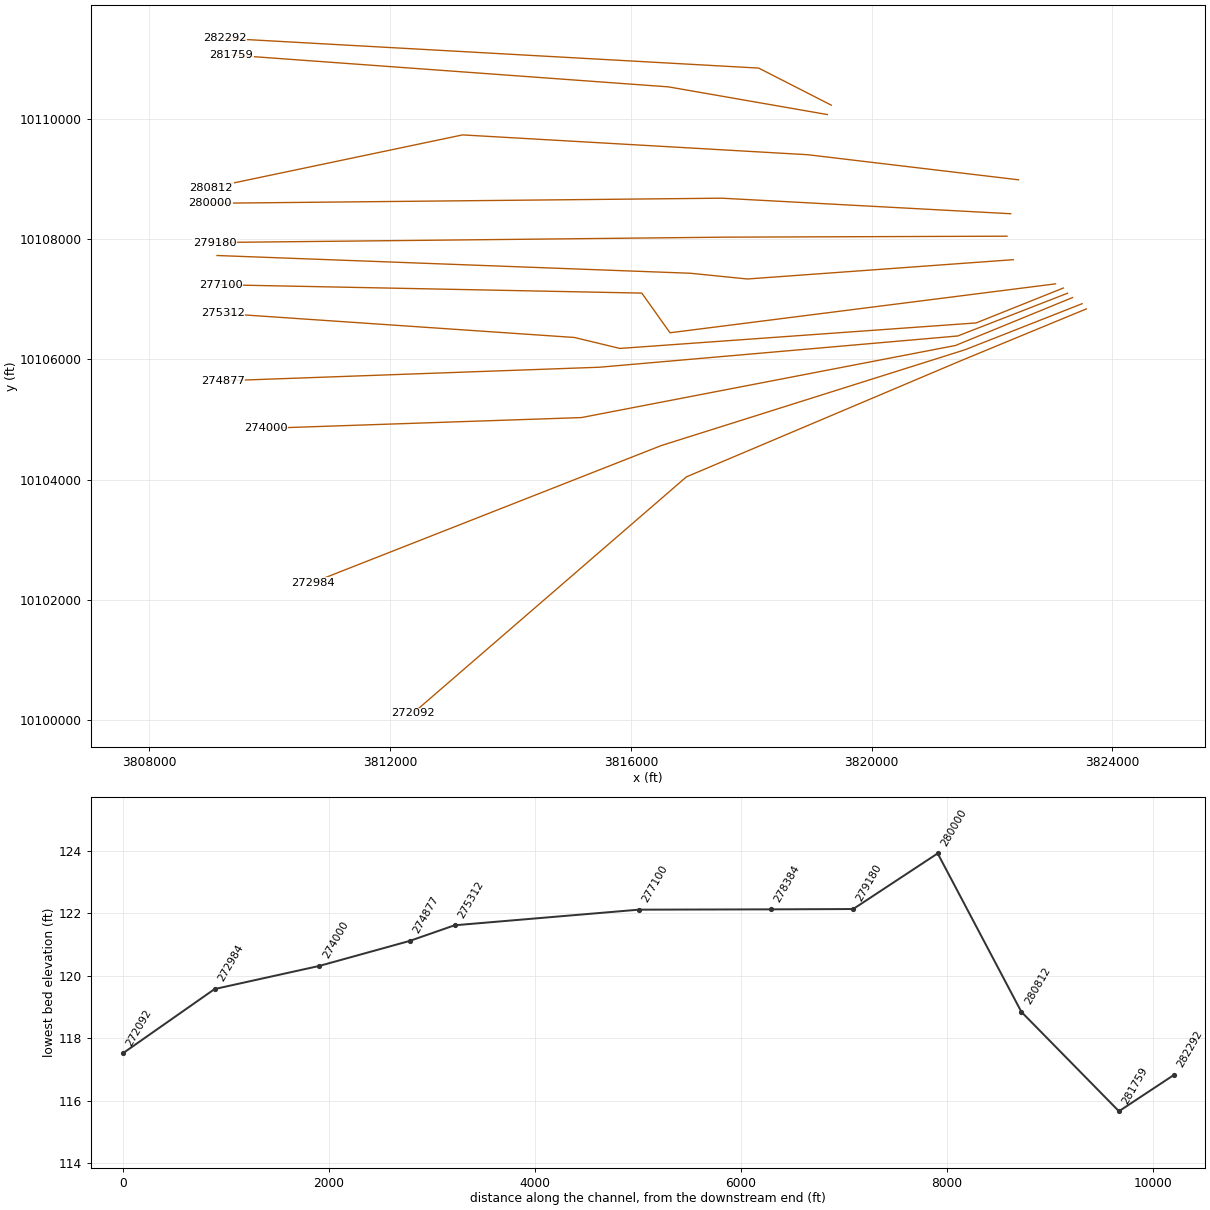
HEC-RAS study WFSJ Main.prj: WFSJ Main Base Level Engineering

--- WFSJ Main.g01 (geometry) --- (continued)

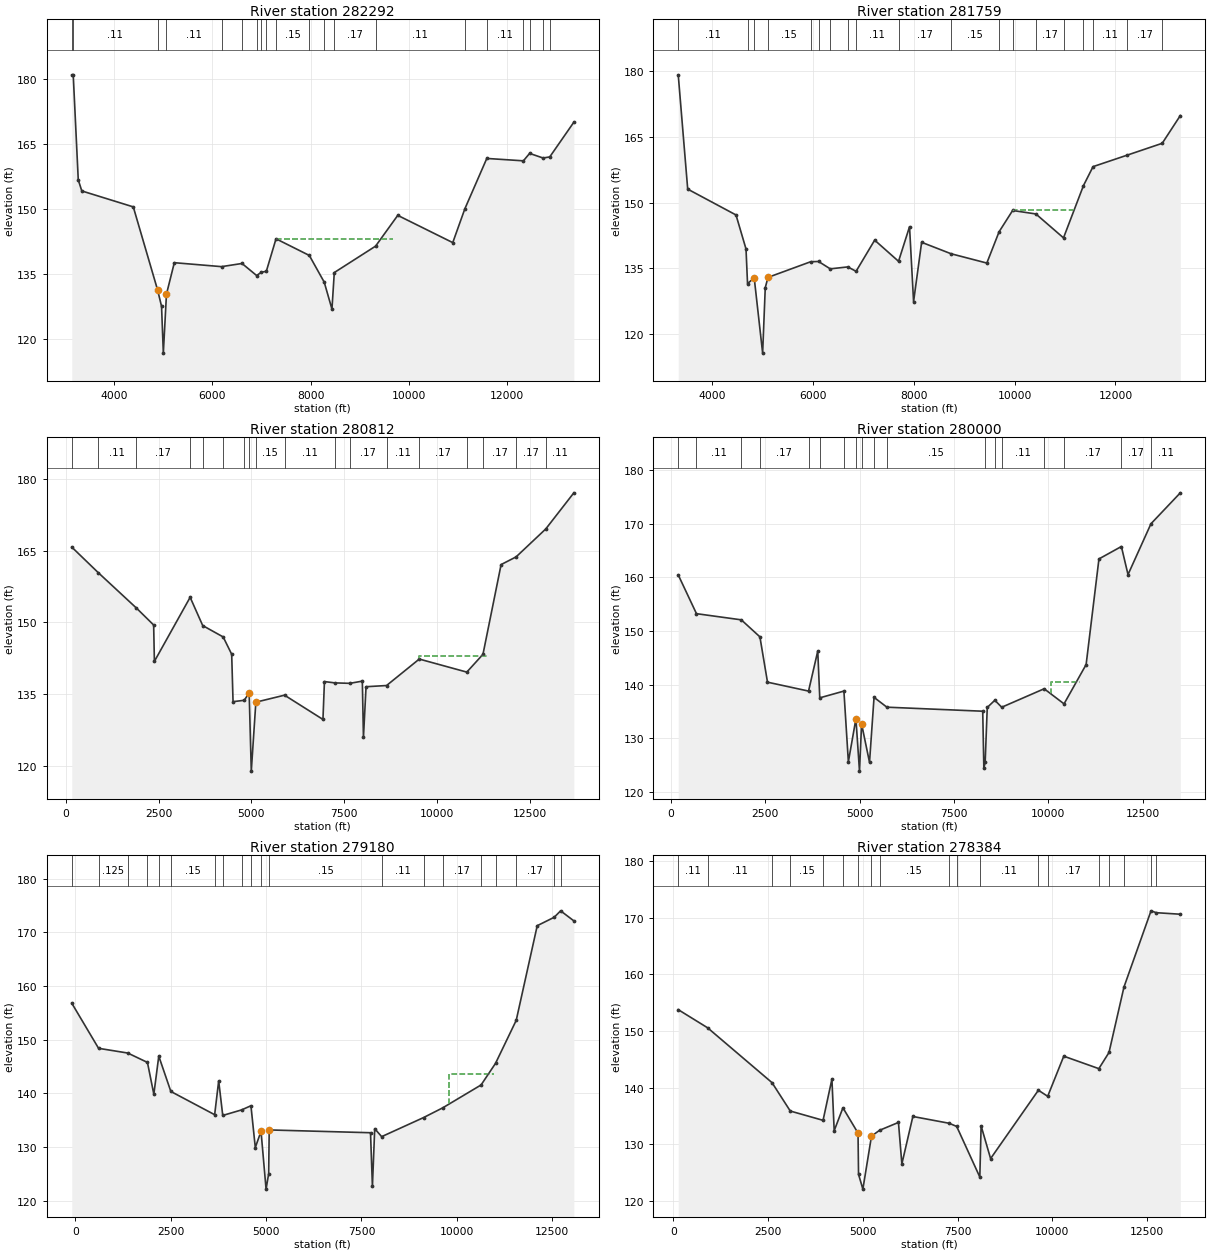
Type RM Length L Ch R = 1 ,282292  ,533,533,533
BEGIN DESCRIPTION:
WFSJ Main 281.0
END DESCRIPTION:
XS GIS Cut Line= 3
      3819329.83     10110225.25      3818123.21     10110841.59
      3809252.22     10111336.35
#Sta/Elev= 30
  3131.1  180.81  3160.8  180.86  3263.6  156.67  3335.9  154.14  4385.7  150.47
    4882  131.33  4962.1  127.59  4998.6  116.82  5062.3  130.38  5222.5  137.63
  6185.4  136.72  6603.6  137.45  6900.7  134.68  6999.7  135.44  7098.7  135.64
  7296.8  143.13  7975.6   139.3    8280  133.15  8437.5  126.95  8485.1  135.36
  9327.3  141.44  9779.6  148.52 10901.3  142.25 11147.6  150.02 11595.5  161.62
 12341.7  161.07 12468.7  162.78 12743.2  161.72 12879.3  161.97 13370.8  169.96
#Mann= 20 ,-1 , 0
  3131.1     .15       0  3160.8     .11       0    4882     .07       0
  5062.3     .11       0  6185.4     .11       0  6603.6     .15       0
  6900.7     .11       0  6999.7     .15       0  7098.7     .11       0
  7296.8     .15       0  7975.6     .17       0    8280     .11       0
  8485.1     .17       0  9327.3     .11       0 11147.6     .17       0
 11595.5     .11       0 12341.7     .17       0 12468.7     .11       0
 12743.2     .17       0 12879.3     .11       0
#XS Ineff= 2 ,-1
  7295.7    9687  143.14  9779.6   11125  148.52
Permanent Ineff=
       F       F
Bank Sta=4882,5062.3
XS Rating Curve= 0 ,0
Exp/Cntr=0.3,0.1

Type RM Length L Ch R = 1 ,281759  ,947,947,947
BEGIN DESCRIPTION:
WFSJ Main 280.0
END DESCRIPTION:
XS GIS Cut Line= 3
        3819263.      10110069.3      3816624.07     10110529.38
      3809358.47     10111058.89
#Sta/Elev= 30
  3323.6  179.19  3511.5   153.1    4470   147.2  4668.7  139.43  4698.8  131.52
  4831.1  132.86  4998.6  115.66  5050.5   130.6  5104.9  132.95  5951.2  136.52
  6108.3  136.58  6339.8   134.9  6687.9  135.34  6853.1  134.34  7221.8  141.45
  7695.5  136.62  7913.6  144.52  7993.8  127.42  8153.7  140.96  8739.2  138.34
  9447.7  136.22  9690.7  143.36  9959.5  148.22 10420.9  147.43 10969.1  141.97
 11365.9  153.92 11555.3  158.23 12226.5  160.83 12928.2  163.56 13287.2  169.89
#Mann= 19 ,-1 , 0
  3323.6     .11       0  4698.8     .15       0  4831.1     .07       0
  5104.9     .15       0  5951.2     .15       0  6108.3     .11       0
  6339.8     .11       0  6687.9     .15       0  6853.1     .11       0
  7695.5     .17       0  8739.2     .15       0  9690.7     .11       0
  9959.5     .17       0 10420.9     .17       0 10969.1     .11       0
 11365.9     .17       0 11555.3     .11       0 12226.5     .17       0
 12928.2     .11       0
#XS Ineff= 3 ,-1
  7221.8  7913.5  141.45  7913.6    9885  144.52    9959   11196  148.23
Permanent Ineff=
       F       F       F
Bank Sta=4831.1,5104.9
XS Rating Curve= 0 ,0
Exp/Cntr=0.3,0.1

Type RM Length L Ch R = 1 ,280812  ,812,812,812
BEGIN DESCRIPTION:
Mapping XS e11f3f2d
END DESCRIPTION:
XS GIS Cut Line= 4
      3822440.03     10108984.24      3818941.78      10109400.9
      3813203.93     10109730.76      3809028.58     10108854.03
#Sta/Elev= 30
   158.5  165.74     871   160.4  1897.1  153.01  2366.2  149.43  2386.3  141.82
    3350  155.23    3689  149.31  4240.5  146.93  4470.1  143.31  4506.8  133.38
  4807.6  133.67 4941.43135.2123  4998.6  118.84 5121.68133.2735    5895  134.74
  6930.8  129.66  6970.8  137.59    7253  137.31  7655.3  137.22  7992.5  137.68
  8022.6  125.88  8092.7  136.51  8645.7  136.76  9527.7   142.3 10809.1  139.57
 11244.9  143.29 11733.9  162.08 12138.4  163.69   12938  169.54 13695.2   177.1
#Mann= 18 ,-1 , 0
   158.5     .17       0     871     .11       0  1897.1     .17       0
    3350    .125       0    3689     .17       0  4240.5     .11       0
  4807.6     .15       0 4941.43     .09       0 5121.68     .15       0
    5895     .11       0    7253     .15       0  7655.3     .17       0
  8645.7     .11       0  9527.7     .17       0 10809.1     .17       0
 11244.9     .17       0 12138.4     .17       0   12938     .11       0
#XS Ineff= 1 ,-1
  9516.8   11345  143.03
Permanent Ineff=
       F
Bank Sta=4941.43,5121.68
XS Rating Curve= 0 ,0
Exp/Cntr=0.3,0.1

Type RM Length L Ch R = 1 ,280000  ,820,820,820
BEGIN DESCRIPTION:
WFSJ Main 279.0
END DESCRIPTION:
XS GIS Cut Line= 3
      3822309.81       10108420.      3817511.87     10108678.52
        3809012.     10108593.62
#Sta/Elev= 30
   195.1  160.46   678.3  153.24  1866.4  152.09  2359.6  148.92  2560.5  140.48
  3648.5  138.82  3892.4  146.27  3945.6  137.56  4585.6  138.82  4703.6  125.64
  4903.9  133.67  4998.6  123.91    5054  132.71    5264  125.55    5384  137.65
  5724.9  135.82  8264.2  135.07  8294.2  124.41  8329.1  125.63  8384.2  135.77
  8585.1  137.11  8767.3  135.81  9892.4  139.25   10419  136.44 11004.3  143.76
 11344.3  163.44 11938.5  165.75 12114.4  160.52 12722.7  169.99 13500.3  175.75
#Mann= 18 ,-1 , 0
   195.1     .11       0   678.3     .11       0  1866.4     .15       0
  2359.6     .17       0  3648.5    .125       0  3945.6     .17       0
  4585.6     .12       0  4903.9     .09       0    5054     .12       0
    5384     .17       0  5724.9     .15       0  8329.1     .11       0
  8585.1     .17       0  8767.3     .11       0  9892.4     .17       0
   10419     .17       0 11938.5     .17       0 12722.7     .11       0
#XS Ineff= 2 ,-1
    2365  3892.4  146.27 10074.3   10840  140.52
Permanent Ineff=
       F       F
Bank Sta=4903.9,5054
XS Rating Curve= 0 ,0
Exp/Cntr=0.3,0.1

Type RM Length L Ch R = 1 ,279180  ,796,796,796
BEGIN DESCRIPTION:
WFSJ Main 278.0
END DESCRIPTION:
XS GIS Cut Line= 3
      3822249.09     10108046.74      3817561.84     10108030.57
      3809087.99     10107941.63
#Sta/Elev= 30
     -95  156.78   607.5  148.37  1372.4  147.49  1888.9  145.74  2056.3  139.81
  2185.8  146.91  2502.3  140.33  3650.5     136  3756.3  142.31  3862.8  135.86
  4356.1  136.89  4601.9  137.67  4716.3  129.88  4866.3  132.91  4998.6  122.13
  5066.3     125 5080.74  133.16  7736.4  132.64  7786.4  122.63  7846.4  133.39
  8028.9  131.91  9125.7  135.46  9632.5  137.29 10634.3  141.54 11012.9  145.56
 11555.8  153.58 12106.7  171.22 12549.9  172.78 12719.8  173.99 13066.6  172.12
#Mann= 20 ,-1 , 0
     -95     .11       0   607.5    .125       0  1372.4    .125       0
  1888.9    .125       0  2185.8     .17       0  2502.3     .15       0
  3650.5     .11       0  3862.8     .17       0  4356.1     .11       0
  4601.9     .17       0  4866.3     .09       0 5080.74     .15       0
  8028.9     .11       0  9125.7     .15       0  9632.5     .17       0
 10634.3     .15       0 11012.9     .17       0 11555.8     .17       0
 12549.9     .11       0 12719.8     .17       0
#XS Ineff= 3 ,-1
    1485  2185.8  146.91    2186  3756.3  142.31  9783.2   10980  143.56
Permanent Ineff=
       F       F       F
Bank Sta=4866.3,5080.74
XS Rating Curve= 0 ,0
Exp/Cntr=0.3,0.1

Type RM Length L Ch R = 1 ,278384  ,1284,1284,1284
BEGIN DESCRIPTION:
WFSJ Main 277.0
END DESCRIPTION:
XS GIS Cut Line= 4
      3822353.26     10107656.11      3817934.84     10107334.93
      3816988.66     10107430.42      3809124.06     10107725.56
#Sta/Elev= 30
   125.5  153.79   900.6  150.59  2600.7  140.91  3082.7   135.9    3948  134.26
  4181.6  141.53  4241.7  132.43  4472.1  136.47 4870.68  132.01  4884.2  124.73
  4998.6  122.12    5226  131.47  5438.3   132.5  5937.7  133.89  6027.7  126.57
  6317.9  134.94  7277.4  133.74  7474.9  133.18  8085.3  124.25  8119.2  133.28
  8369.4  127.51  9630.9  139.57  9876.5   138.5 10300.7  145.58 11226.5  143.38
 11494.5  146.23   11890  157.79 12603.6  171.23   12742   170.9 13376.7  170.63
#Mann= 19 ,-1 , 0
   125.5     .11       0   900.6     .11       0  2600.7     .17       0
  3082.7     .15       0    3948     .11       0  4472.1     .17       0
 4870.68     .09       0    5226     .17       0  5438.3     .15       0
  7277.4     .11       0  7474.9     .15       0  8085.3     .11       0
  9630.9     .17       0  9876.5     .17       0 11226.5     .15       0
 11494.5     .17       0   11890     .17       0 12603.6     .11       0
   12742     .17       0
#XS Ineff= 1 ,-1
 2387.99  4181.6  141.53
Permanent Ineff=
       F
Bank Sta=4870.68,5226
XS Rating Curve= 0 ,0
Exp/Cntr=0.3,0.1

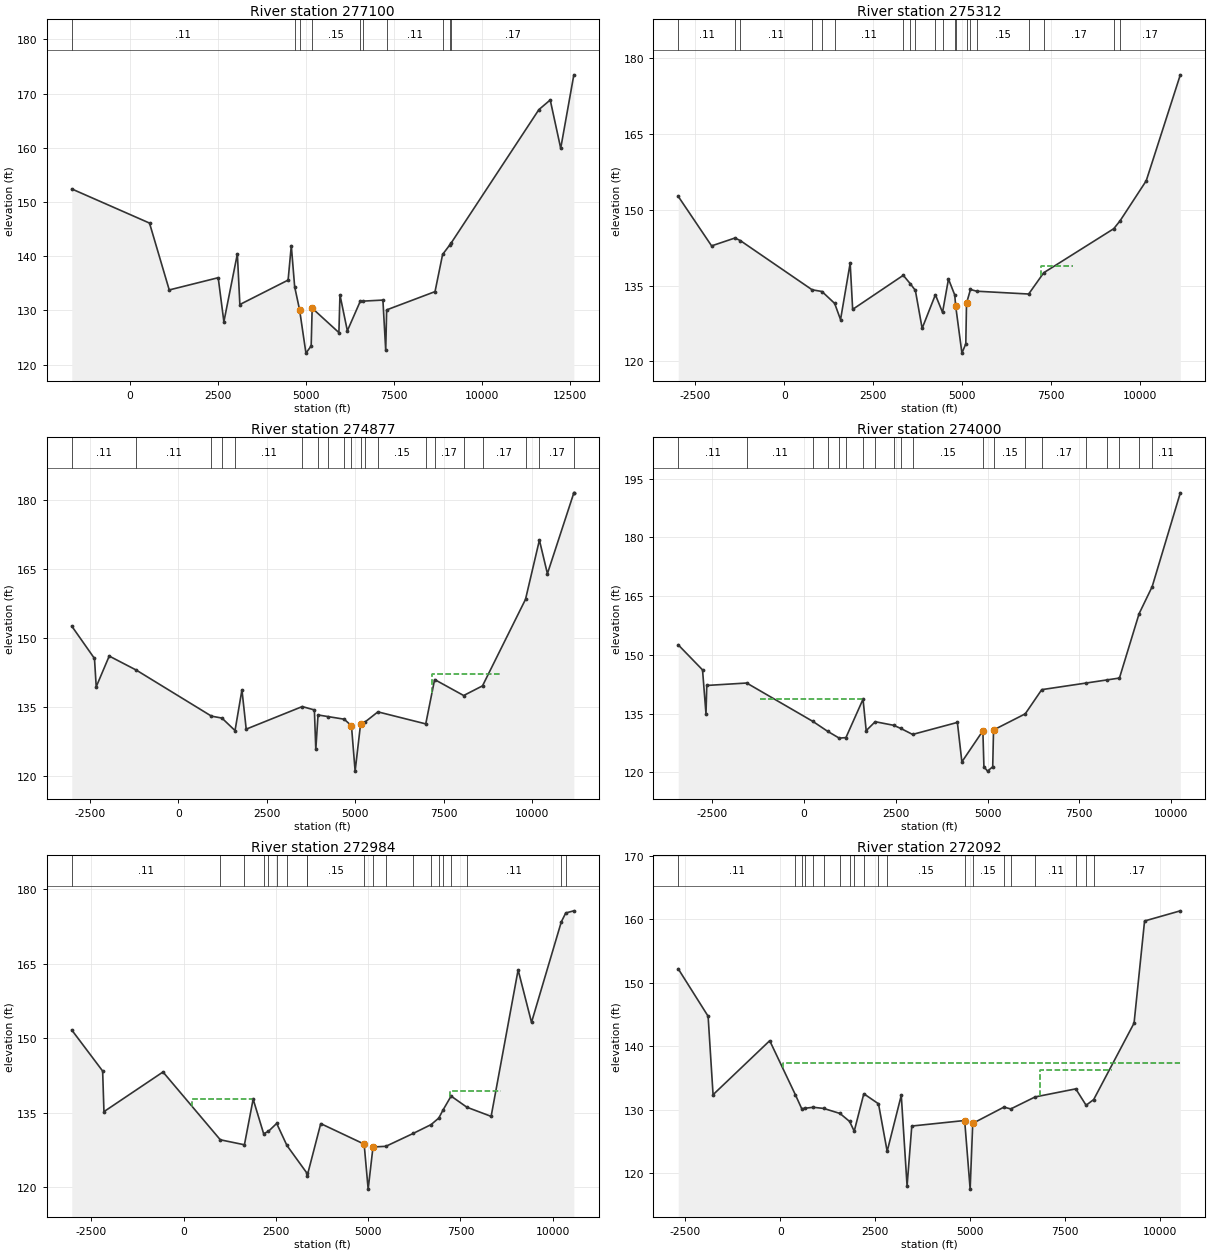
Type RM Length L Ch R = 1 ,277100  ,1788,1788,1788
BEGIN DESCRIPTION:
WFSJ Main 276.0
END DESCRIPTION:
XS GIS Cut Line= 4
      3823054.64      10107254.2      3816650.11     10106440.83
      3816181.36     10107100.56      3809184.81     10107239.45
#Sta/Elev= 30
 -1653.7  152.41   554.8  146.11  1115.2  133.77  2506.2  136.03  2667.5   127.9
  3050.6  140.43  3121.1  131.08  4492.1  135.59  4582.8  141.95  4678.4  134.35
  4817.9  130.12  4998.6  122.11  5147.5  123.44  5175.5  130.41  5935.1   125.9
  5965.1  132.86  6175.2  126.23  6541.7  131.68    6631  131.71  7185.4   131.9
  7265.4  122.61  7291.4  130.09  8665.7  133.46  8881.1  140.32    9093  142.15
  9117.1  142.36 11616.3  167.05 11938.5  168.83 12236.4  159.91 12609.5  173.47
#Mann= 10 ,-1 , 0
 -1653.7     .11       0  4678.4     .15       0  4817.9     .09       0
  5175.5     .15       0  6541.7     .11       0    6631     .15       0
  7291.4     .11       0  8881.1     .17       0    9093     .15       0
  9117.1     .17       0
#XS Ineff= 1 ,-1
     680  4582.8  141.95
Permanent Ineff=
       F
Bank Sta=4817.9,5175.5
XS Rating Curve= 0 ,0
Exp/Cntr=0.3,0.1

Type RM Length L Ch R = 1 ,275312  ,435,435,435
BEGIN DESCRIPTION:
WFSJ Main 275.0
END DESCRIPTION:
XS GIS Cut Line= 5
      3823184.87     10107184.77      3821735.72     10106604.41
      3815816.78     10106180.42      3815061.57     10106362.71
      3809221.25      10106761.9
#Sta/Elev= 30
   -2983  152.67 -2044.4  142.86 -1386.5  144.42 -1234.5   143.9   783.6  134.16
  1061.1  133.82  1417.9  131.46  1583.6  128.25  1854.3  139.44  1924.5  130.28
  3348.3  137.03  3545.6  135.36  3688.5  134.04  3879.5  126.52    4252  133.18
  4453.2  129.68  4620.3  136.29  4796.6  133.13 4823.73   130.9  4998.6  121.61
  5107.7  123.46    5128   131.5  5239.2  134.22  5411.4  133.88  6876.3  133.32
  7300.9  137.54  9269.9  146.26  9448.5  147.83 10184.2  155.76   11143  176.75
#Mann= 20 ,-1 , 0
   -2983     .11       0 -1386.5    .125       0 -1234.5     .11       0
   783.6     .17       0  1061.1     .11       0  1417.9     .11       0
  3348.3     .15       0  3545.6     .11       0  3688.5     .15       0
    4252     .17       0  4453.2     .15       0  4796.6     .15       0
 4823.73     .09       0    5128     .15       0  5239.2     .11       0
  5411.4     .15       0  6876.3     .11       0  7300.9     .17       0
  9269.9     .15       0  9448.5     .17       0
#XS Ineff= 2 ,-1
    -455  1854.3  139.44  7237.3    8125  138.79
Permanent Ineff=
       F       F
Bank Sta=4823.73,5128
XS Rating Curve= 0 ,0
Exp/Cntr=0.3,0.1

Type RM Length L Ch R = 1 ,274877  ,877,877,877
BEGIN DESCRIPTION:
WFSJ Main 274.0
END DESCRIPTION:
XS GIS Cut Line= 4
      3823254.26     10107097.95      3821431.22     10106387.76
      3815478.24     10105867.92      3809221.23     10105642.28
#Sta/Elev= 30
 -3011.5   152.6 -2369.4  145.57 -2320.4  139.43 -1952.9   146.1 -1189.5  143.06
   937.7  133.05  1233.9  132.63  1603.6  129.92  1799.2  138.76  1919.6  130.23
  3504.1  135.13  3846.9   134.4  3887.1  125.82  3950.2  133.31  4236.5  132.95
  4688.5  132.39 4895.09  130.96  4998.6  121.11  5151.2  131.24  5290.7  131.85
  5642.5  133.98  6995.1  131.37  7245.9     141  8067.2  137.53  8599.6  139.63
  9815.4  158.42 10208.3  171.28 10434.6  163.99 11176.4  181.42 11181.7  181.55
#Mann= 20 ,-1 , 0
 -3011.5     .11       0 -1189.5     .11       0   937.7     .11       0
  1233.9     .17       0  1603.6     .11       0  3504.1     .11       0
  3950.2     .11       0  4236.5     .17       0  4688.5     .17       0
 4895.09     .09       0  5151.2     .15       0  5290.7     .11       0
  5642.5     .15       0  6995.1     .11       0  7245.9     .17       0
  8067.2     .15       0  8599.6     .17       0  9815.4     .11       0
 10208.3     .17       0 11176.4     .11       0
#XS Ineff= 2 ,-1
    -405  1799.2  138.76  7172.5    9120  142.23
Permanent Ineff=
       F       F
Bank Sta=4895.09,5151.2
XS Rating Curve= 0 ,0
Exp/Cntr=0.3,0.1

Type RM Length L Ch R = 1 ,274000  ,1016,1016,1016
BEGIN DESCRIPTION:
WFSJ Main 273.0
END DESCRIPTION:
XS GIS Cut Line= 4
      3823337.62     10107026.41      3821394.94     10106230.04
      3815178.32     10105030.85      3809931.66     10104852.33
#Sta/Elev= 30
 -3430.8  152.56 -2768.6  146.16 -2674.5  134.92 -2652.9  142.19 -1565.3  142.81
   240.7  132.99   639.7  130.48   955.2  128.74  1138.4  128.87  1604.6  138.68
  1690.6  130.65  1936.4  132.93  2435.1  132.02  2634.6  131.21  2954.8  129.68
  4175.5  132.75  4297.8  122.67    4870  130.61  4898.6  121.41  4998.6  120.31
  5138.1  121.43  5160.6  130.82  6024.4  134.94    6474  141.12  7671.8  142.79
  8263.6  143.62  8591.2  144.08  9126.7  160.52  9482.4  167.41 10249.7  191.38
#Mann= 20 ,-1 , 0
 -3430.8     .11       0 -1565.3     .11       0   240.7     .17       0
   639.7     .17       0   955.2     .15       0  1138.4     .11       0
  1604.6    .125       0  1936.4     .11       0  2435.1     .17       0
  2634.6     .11       0  2954.8     .15       0    4870     .09       0
  5160.6     .15       0  6024.4     .11       0    6474     .17       0
  7671.8     .15       0  8263.6     .17       0  8591.2     .17       0
  9126.7     .17       0  9482.4     .11       0
#XS Ineff= 1 ,-1
   -1215  1598.9   138.8
Permanent Ineff=
       F
Bank Sta=4870,5160.6
XS Rating Curve= 0 ,0
Exp/Cntr=0.3,0.1

Type RM Length L Ch R = 1 ,272984  ,892,892,892
BEGIN DESCRIPTION:
WFSJ Main 272.0
END DESCRIPTION:
XS GIS Cut Line= 4
       3823497.3     10106924.33      3821553.33     10106159.05
      3816506.02     10104565.83       3810712.3      10102287.4
#Sta/Elev= 30
 -3034.4  151.65 -2197.5  143.38 -2162.3  135.19    -562  143.19   990.8  129.52
    1645  128.51  1881.4  137.71  2165.6  130.75  2294.1  131.21  2519.2  132.82
  2797.3  128.37  3337.6  122.81  3344.4  122.19  3713.4  132.78  4889.6128.6489
  4998.6  119.57    5130  128.07  5477.7   128.2  6216.7  130.79    6704  132.58
  6912.9   133.9  7030.7  135.56  7246.5  138.33    7675  136.08  8331.5  134.24
  9062.9  163.77    9426  153.19 10234.2  173.47 10353.8  175.25 10573.2  175.68
#Mann= 20 ,-1 , 0
 -3034.4     .11       0   990.8     .15       0    1645     .11       0
  2165.6    .125       0  2294.1     .11       0  2519.2     .17       0
  2797.3     .15       0  3337.6     .11       0  3344.4     .15       0
  4889.6     .09       0    5130     .15       0  5477.7     .11       0
  6216.7     .15       0    6704     .11       0  6912.9     .17       0
  7030.7     .15       0  7246.5     .17       0    7675     .11       0
 10234.2     .15       0 10353.8     .17       0
#XS Ineff= 3 ,-1
   -2350    -562  143.19     230  1881.4  137.71  7225.4    8590  139.32
Permanent Ineff=
       F       F       F
Bank Sta=4889.6,5130
XS Rating Curve= 0 ,0
Exp/Cntr=0.3,0.1

Type RM Length L Ch R = 1 ,272092  ,1443,1443,1443
BEGIN DESCRIPTION:
WFSJ Main 271.0
END DESCRIPTION:
XS GIS Cut Line= 4
      3823566.81     10106837.55      3821501.89     10105984.28
      3816922.68       10104045.      3812378.43     10100112.73
#Sta/Elev= 30
 -2685.6  152.18 -1899.2  144.72 -1768.8  132.37  -277.5  140.87   397.4  132.37
     564  130.18     663  130.25   870.7  130.39  1142.8  130.21  1572.1  129.42
  1825.7  128.16  1947.2  126.63  2199.5  132.52  2585.9  130.94  2814.3  123.46
  3185.5  132.27  3338.5  118.01  3462.3  127.44  4854.1  128.31  4998.6  117.51
  5066.8  127.86  5888.7  130.42  6067.8  130.13  6708.7  132.02  7779.3  133.29
  8050.8  130.71    8251  131.61  9313.6  143.64    9590  159.71   10531  161.31
#Mann= 20 ,-1 , 0
 -2685.6     .11       0   397.4     .17       0     564     .15       0
     663     .17       0   870.7     .15       0  1142.8     .15       0
  1572.1     .17       0  1825.7     .17       0  1947.2     .11       0
  2199.5     .15       0  2585.9     .11       0  2814.3     .15       0
  4854.1     .09       0  5066.8     .15       0  5888.7     .11       0
  6067.8     .15       0  6708.7     .11       0  7779.3     .17       0
  8050.8     .15       0    8251     .17       0
#XS Ineff= 3 ,-1
   -2050  -277.5  140.87      65 -2162.3  137.42  6845.8    8736  136.22
Permanent Ineff=
       F       F       F
Bank Sta=4854.1,5066.8
XS Rating Curve= 0 ,0
Exp/Cntr=0.3,0.1