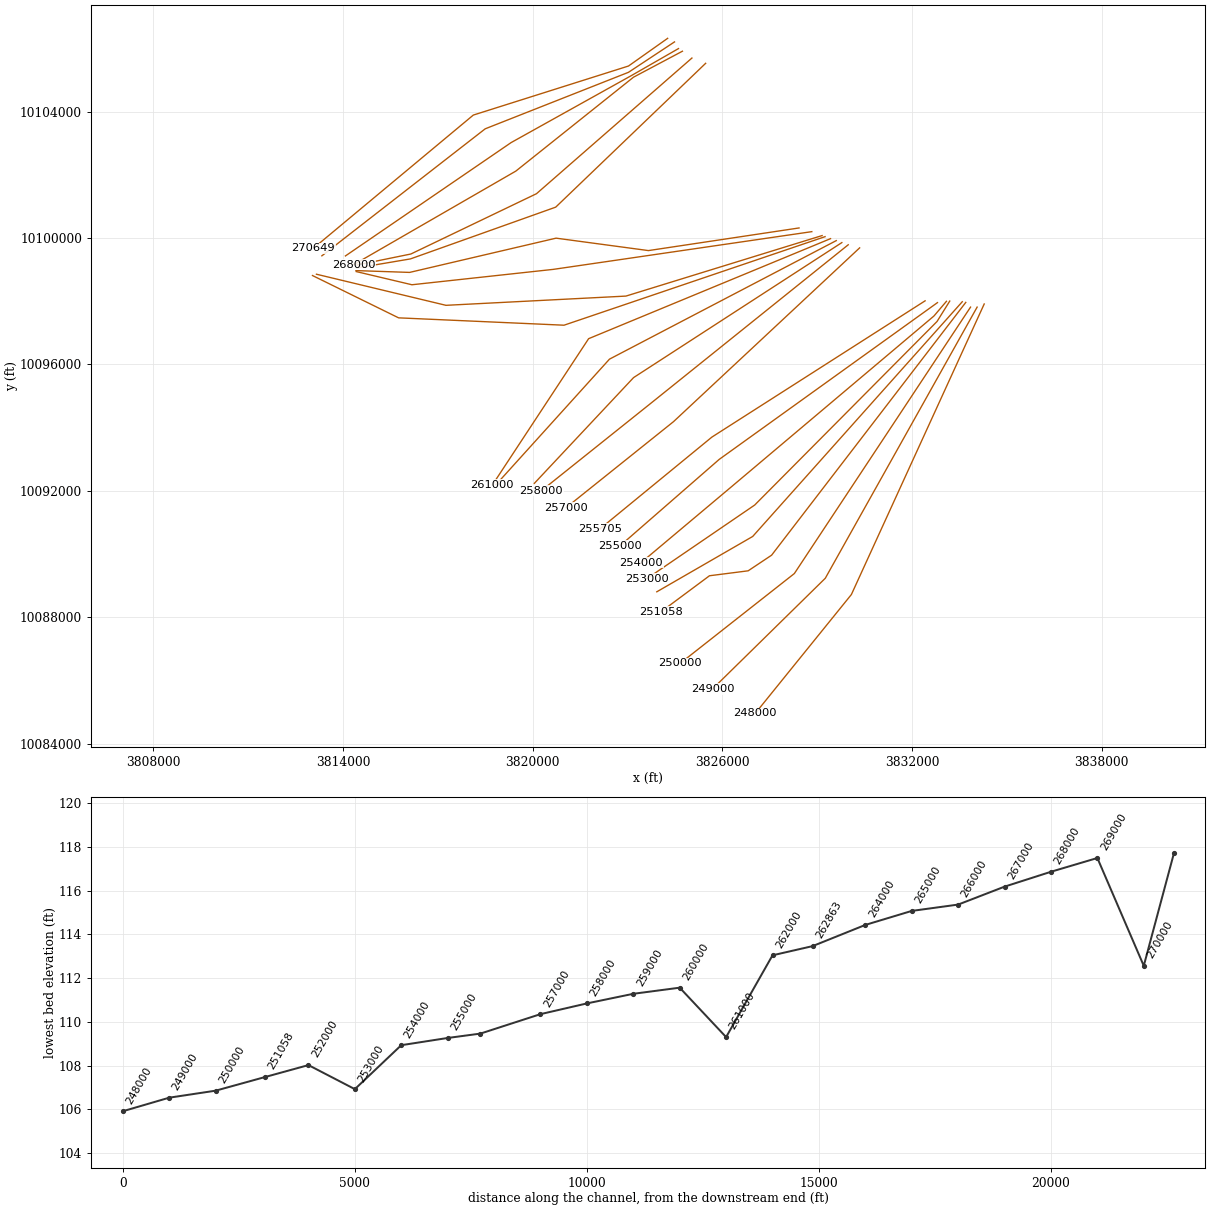
HEC-RAS study WFSJ Main.prj: WFSJ Main Base Level Engineering

--- WFSJ Main.g01 (geometry) --- (continued)

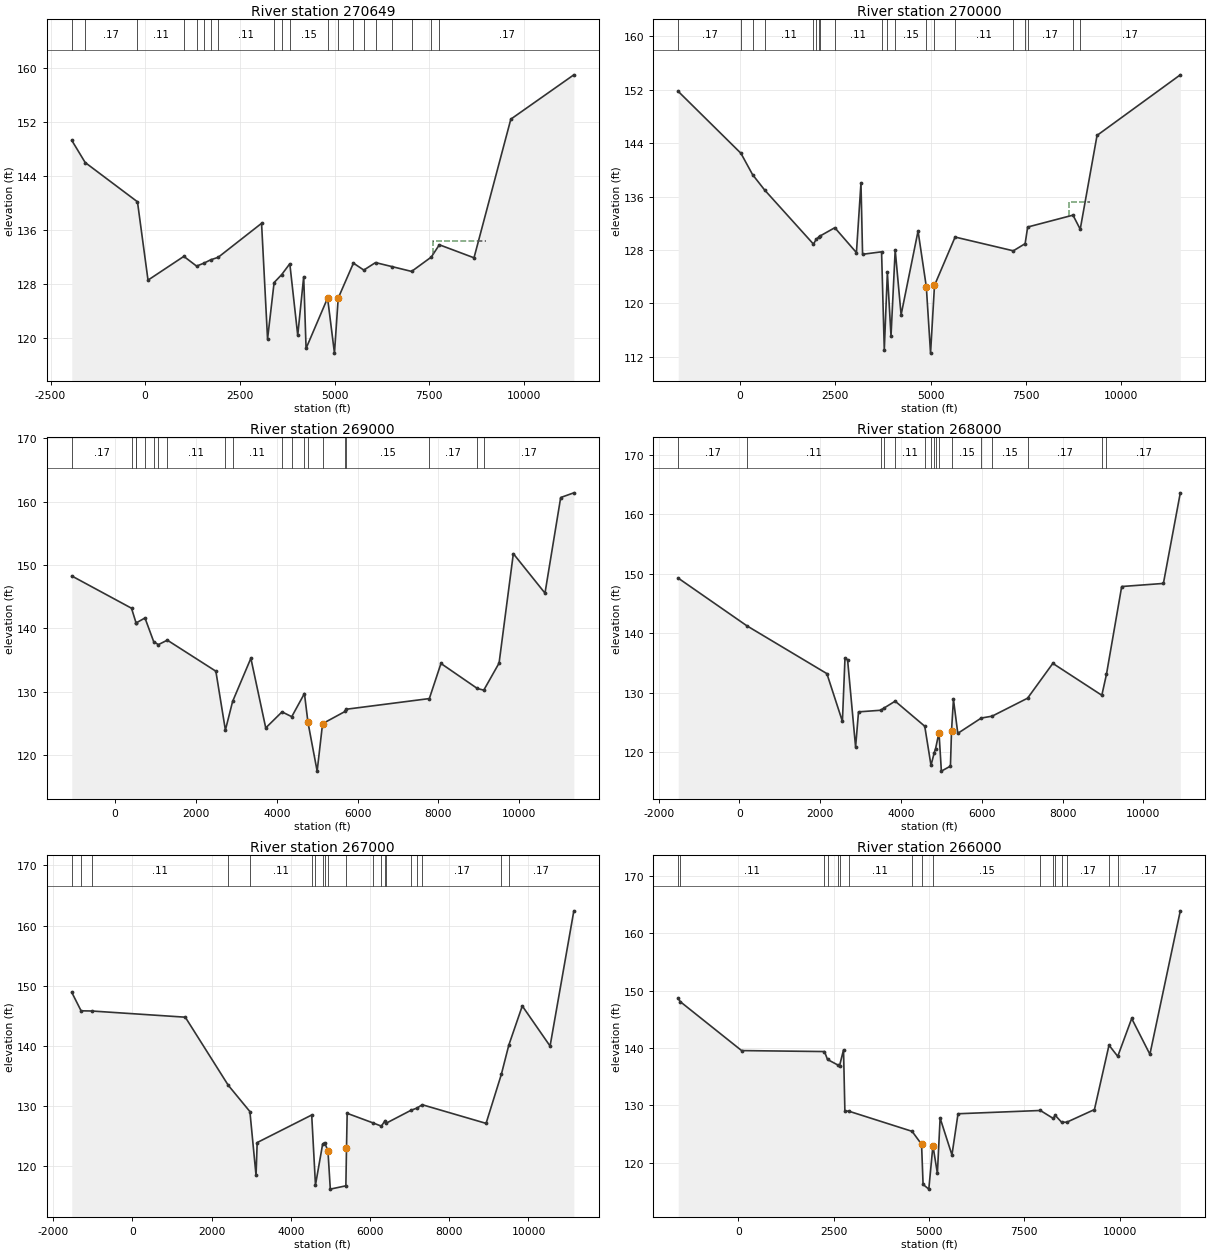
Type RM Length L Ch R = 1 ,270649  ,649,649,649
BEGIN DESCRIPTION:
WFSJ Main 270.0
END DESCRIPTION:
XS GIS Cut Line= 4
      3824269.88     10106316.69      3823031.08     10105440.77
       3818120.6     10103888.75       3813055.5       10099670.
#Sta/Elev= 30
 -1938.7  149.24 -1584.4  145.95  -203.7  140.13    74.8  128.52  1020.8  132.04
  1357.6   130.6  1556.7  131.05  1729.4  131.53  1927.1   131.9  3073.6  136.94
  3231.6  119.79  3404.7  128.16    3605  129.34  3819.5  130.95  4028.6  120.34
  4185.9  129.03  4248.9   118.4 4816.98  125.86  4998.6   117.7  5097.4  125.85
  5499.3  131.04  5773.6  130.01  6082.7  131.12  6521.3  130.52  7035.4  129.81
  7555.6  131.94  7768.4  133.76  8683.8  131.83  9656.2  152.38 11320.3  158.95
#Mann= 20 ,-1 , 0
 -1938.7     .17       0 -1584.4     .17       0  -203.7     .11       0
  1020.8     .15       0  1357.6     .17       0  1556.7     .15       0
  1729.4     .17       0  1927.1     .11       0  3404.7     .17       0
    3605     .11       0  3819.5     .15       0 4816.98     .09       0
  5097.4     .15       0  5499.3     .15       0  5773.6     .11       0
  6082.7     .15       0  6521.3     .11       0  7035.4     .15       0
  7555.6     .11       0  7768.4     .17       0
#XS Ineff= 2 ,-1
    -135  3073.6  136.94  7604.6    8990  134.29
Permanent Ineff=
       F       F
Bank Sta=4816.98,5097.4
XS Rating Curve= 0 ,0
Exp/Cntr=0.3,0.1

Type RM Length L Ch R = 1 ,270000  ,1000,1000,1000
BEGIN DESCRIPTION:
WFSJ Main 269.0
END DESCRIPTION:
XS GIS Cut Line= 4
      3824486.94     10106203.87      3823031.33     10105242.03
      3818498.32     10103454.82      3813329.26     10099435.88
#Sta/Elev= 30
 -1617.3  151.75      27  142.48   332.6  139.28     646     137  1928.7  128.88
  2004.2  129.64  2062.8  129.91  2108.7  130.12  2487.9  131.34  3054.9  127.61
  3174.2  138.03  3216.1  127.36  3714.4  127.73  3785.8  113.06  3866.6  124.66
  3961.9  115.12  4071.5  128.01  4226.6  118.29    4671  130.84  4887.6   122.5
  4998.6  112.56    5102   122.7  5642.5  129.94  7168.6  127.88  7478.6  128.95
  7545.1  131.44  8733.2  133.22  8923.1  131.11  9364.3  145.16 11547.6  154.23
#Mann= 20 ,-1 , 0
 -1617.3     .17       0      27     .11       0   332.6     .17       0
     646     .11       0  1928.7     .15       0  2004.2     .17       0
  2062.8     .15       0  2108.7     .17       0  2487.9     .11       0
  3714.4     .17       0  3866.6     .11       0  4071.5     .15       0
  4887.6     .09       0    5102     .15       0  5642.5     .11       0
  7168.6     .15       0  7478.6     .11       0  7545.1     .17       0
  8733.2     .15       0  8923.1     .17       0
#XS Ineff= 2 ,-1
     265  3174.2  138.03  8623.3    9180  135.21
Permanent Ineff=
       F       F
Bank Sta=4887.6,5102
XS Rating Curve= 0 ,0
Exp/Cntr=0.3,0.1

Type RM Length L Ch R = 1 ,269000  ,1000,1000,1000
BEGIN DESCRIPTION:
WFSJ Main 268.0
END DESCRIPTION:
XS GIS Cut Line= 4
      3824612.78     10105992.62      3823125.22     10105139.66
      3819316.75     10103018.26      3814074.36     10099432.15
#Sta/Elev= 30
 -1074.2  148.29   404.2   143.2   515.5  140.91   522.5  140.89   737.4  141.66
   953.5  137.92  1069.2  137.45  1290.3  138.16  2491.8  133.26  2727.9  123.97
    2906  128.48  3358.3   135.3  3726.4  124.31  4129.6  126.84  4369.9  126.08
  4684.1  129.74 4771.22  125.19  4998.6  117.49  5132.9  124.98  5696.2  126.93
  5724.5  127.26  7775.3  128.94    8063  134.48  8963.2  130.53  9122.5  130.27
  9501.2  134.54    9854  151.81 10637.4  145.58 11026.1  160.67 11351.6  161.41
#Mann= 20 ,-1 , 0
 -1074.2     .17       0   404.2     .11       0   515.5     .17       0
   522.5     .11       0   737.4     .17       0   953.5     .11       0
  1069.2     .17       0  1290.3     .11       0  2727.9     .17       0
    2906     .11       0  4129.6    .125       0  4369.9     .17       0
  4684.1     .15       0 4771.22     .09       0  5132.9     .15       0
  5696.2     .11       0  5724.5     .15       0  7775.3     .17       0
  8963.2     .11       0  9122.5     .17       0
#XS Ineff= 2 ,-1
    1750  3358.3   135.3    8063    9550  134.48
Permanent Ineff=
       F       F
Bank Sta=4771.22,5132.9
XS Rating Curve= 0 ,0
Exp/Cntr=0.3,0.1

Type RM Length L Ch R = 1 ,268000  ,1000,1000,1000
BEGIN DESCRIPTION:
WFSJ Main 267.0
END DESCRIPTION:
XS GIS Cut Line= 4
      3824737.79      10105909.3      3823189.68     10105087.46
      3819467.24     10102116.85      3814345.18     10099161.31
#Sta/Elev= 30
 -1515.2   149.3   183.8  141.29  2164.5  133.25  2548.8  125.22  2612.8  135.88
  2676.9  135.58  2875.4   120.9  2947.5  126.82  3491.8  127.09  3586.3  127.49
  3854.6  128.62    4587  124.41  4742.1  117.83  4822.8  119.98  4854.7  120.63
 4939.82  123.35  4998.6  116.86    5223   117.7 5250.04  123.64  5297.7  128.91
  5405.4  123.21  5985.4  125.78    6255   126.1  7132.8  129.12  7757.8  134.97
  8970.7  129.61    9085  133.12  9462.5  147.89 10494.9  148.41 10913.6  163.64
#Mann= 16 ,-1 , 0
 -1515.2     .17       0   183.8     .11       0  3491.8     .15       0
  3586.3    .125       0  3854.6     .11       0    4587     .17       0
  4742.1     .15       0  4822.8     .17       0  4854.7     .15       0
 4939.82     .09       0 5250.04     .15       0  5985.4     .11       0
    6255     .15       0  7132.8     .17       0  8970.7     .11       0
    9085     .17       0
#XS Ineff= 2 ,-1
    1390  2612.8  135.88  7757.8    9230  134.97
Permanent Ineff=
       F       F
Bank Sta=4939.82,5250.04
XS Rating Curve= 0 ,0
Exp/Cntr=0.3,0.1

Type RM Length L Ch R = 1 ,267000  ,1000,1000,1000
BEGIN DESCRIPTION:
WFSJ Main 266.0
END DESCRIPTION:
XS GIS Cut Line= 4
      3825038.01     10105693.31      3820120.68     10101401.89
      3816145.51     10099493.62      3814445.08     10099145.87
#Sta/Elev= 30
 -1526.6  148.89 -1291.5  145.82 -1026.8  145.79  1338.7  144.76  2422.3  133.45
  2969.3  129.07  3124.3  118.45  3152.8  123.92    4529   128.5  4624.2  116.86
  4803.6  123.62  4853.5  123.91  4938.4  122.58  4998.6  116.18  5391.4  116.73
  5407.1  122.95  5424.2  128.78  6083.9  127.17  6286.9  126.65  6381.7  127.57
  6394.4  127.09  7036.3  129.29  7188.1  129.66  7318.1  130.21  8929.9  127.11
  9314.9  135.25  9503.7  140.12  9843.7  146.63 10545.2  139.96 11145.1  162.44
#Mann= 20 ,-1 , 0
 -1526.6     .17       0 -1291.5     .15       0 -1026.8     .11       0
  2422.3     .15       0  2969.3     .11       0    4529     .17       0
  4624.2     .15       0  4803.6     .17       0  4853.5     .15       0
  4938.4     .09       0  5407.1     .15       0  6083.9     .11       0
  6286.9     .17       0  6381.7     .11       0  6394.4     .15       0
  7036.3     .17       0  7188.1     .15       0  7318.1     .17       0
  9314.9     .11       0  9503.7     .17       0
Bank Sta=4938.4,5407.1
XS Rating Curve= 0 ,0
Exp/Cntr=0.3,0.1

Type RM Length L Ch R = 1 ,266000  ,1000,1000,1000
BEGIN DESCRIPTION:
WFSJ Main 265.0
END DESCRIPTION:
XS GIS Cut Line= 4
      3825472.05     10105526.22      3820728.36     10100976.16
      3816131.62     10099338.38      3814440.85     10099052.25
#Sta/Elev= 30
 -1573.1  148.66 -1522.9  148.08    88.5  139.53  2262.4  139.36  2341.6  137.98
  2622.3  136.98  2656.9  136.86  2761.9  139.66  2797.5  128.96    2895  128.97
  4560.8  125.44 4808.65123.1817  4848.3  116.18  4998.6  115.36  5106.7  122.95
  5223.5  118.11  5295.3  127.75  5605.6  121.32  5764.9  128.51  7924.8  129.08
  8257.6  127.71  8316.5  128.21    8480  127.04  8615.2  127.03  9342.4  129.24
  9724.4  140.47  9953.6  138.52 10319.7  145.13   10797  138.88 11594.6  163.91
#Mann= 17 ,-1 , 0
 -1573.1     .15       0 -1522.9     .11       0  2262.4     .17       0
  2341.6     .15       0  2622.3     .11       0  2656.9     .15       0
    2895     .11       0  4560.8     .15       0 4808.65     .09       0
  5106.7     .15       0  7924.8     .17       0  8257.6     .15       0
  8316.5     .17       0    8480     .15       0  8615.2     .17       0
  9724.4     .11       0  9953.6     .17       0
Bank Sta=4808.65,5106.7
XS Rating Curve= 0 ,0
Exp/Cntr=0.3,0.1

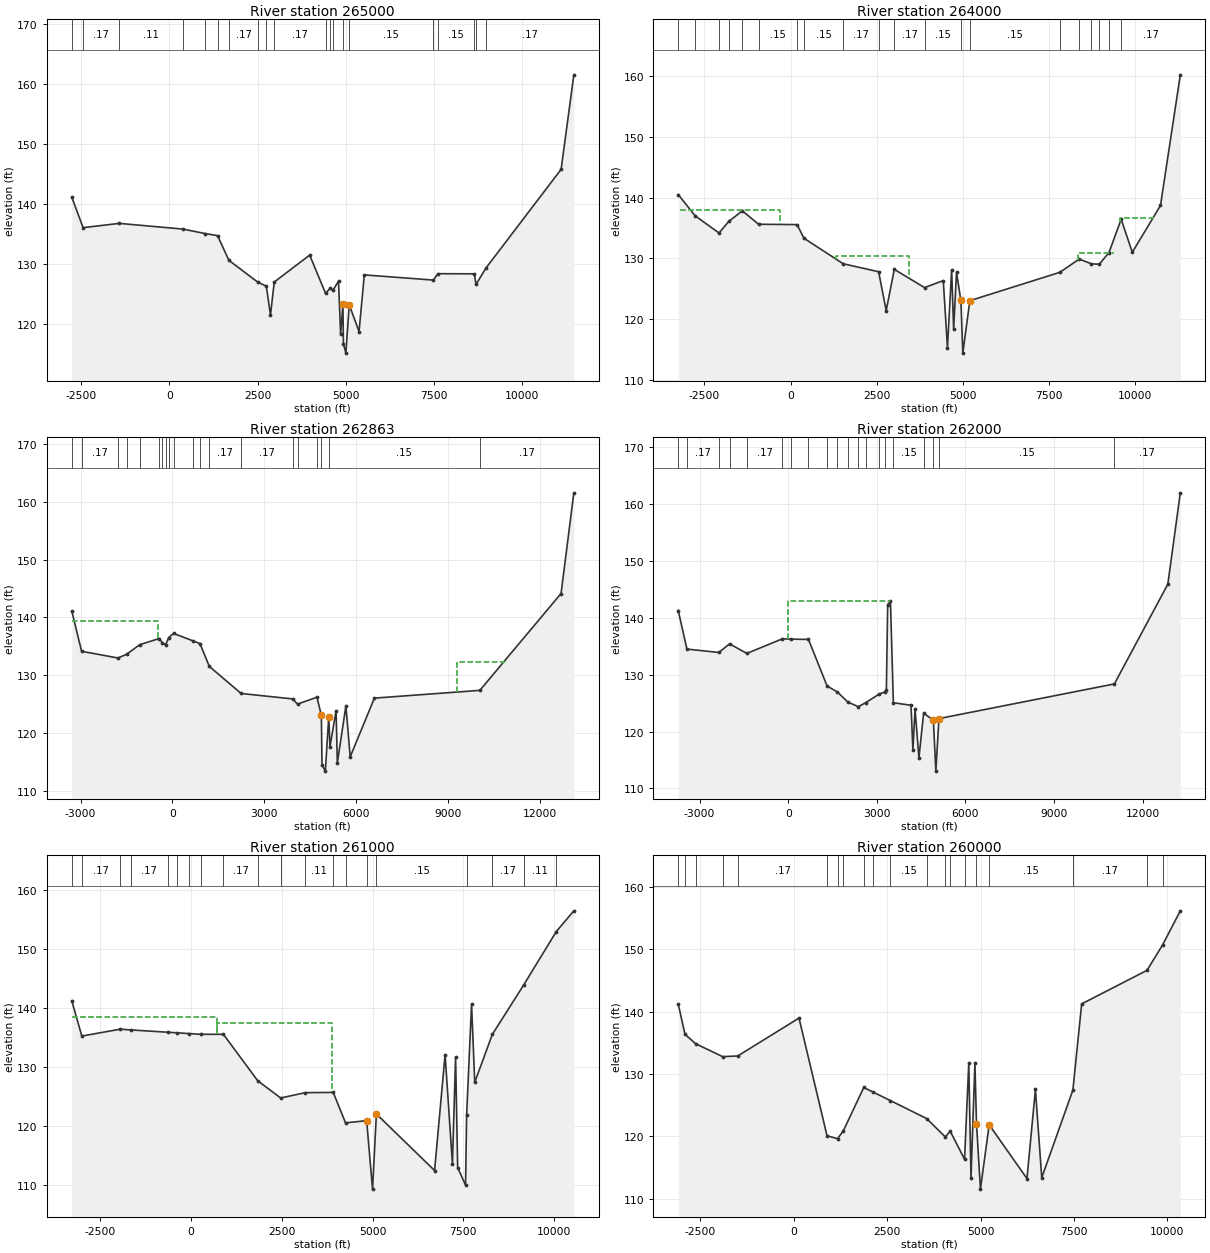
Type RM Length L Ch R = 1 ,265000  ,1000,1000,1000
BEGIN DESCRIPTION:
WFSJ Main 264.0
END DESCRIPTION:
XS GIS Cut Line= 5
      3828427.78     10100317.86      3823662.12     10099601.71
      3820740.02     10099994.91      3816105.58      10098911.3
      3814407.68     10098968.59
#Sta/Elev= 30
 -2767.6  141.08   -2447     136 -1421.3  136.71   382.6  135.76  1013.9  135.01
  1362.3  134.67  1685.7  130.54  2504.8   126.9  2744.8  126.24  2863.1  121.41
  2969.6  126.93    3973  131.42  4423.2  125.04    4555   125.9  4636.2  125.59
  4790.3  127.07  4850.8  118.19 4915.05  123.26  4930.1  116.64  4998.6  115.07
  5094.7  123.12  5371.9  118.67  5521.4  128.12  7481.2  127.25    7606  128.32
  8638.7   128.3  8686.2  126.52  8971.3  129.29 11097.9  145.73 11458.3  161.49
#Mann= 20 ,-1 , 0
 -2767.6     .11       0   -2447     .17       0 -1421.3     .11       0
   382.6     .15       0  1013.9     .17       0  1362.3     .15       0
  1685.7     .17       0  2504.8     .15       0  2744.8     .15       0
  2969.6     .17       0  4423.2     .15       0    4555     .11       0
  4636.2     .15       0 4915.05     .09       0  5094.7     .15       0
  7481.2     .17       0    7606     .15       0  8638.7     .17       0
  8686.2     .15       0  8971.3     .17       0
#XS Ineff= 1 ,-1
    1325    3973  131.42
Permanent Ineff=
       F
Bank Sta=4915.05,5094.7
XS Rating Curve= 0 ,0
Exp/Cntr=0.3,0.1

Type RM Length L Ch R = 1 ,264000  ,1137,1137,1137
BEGIN DESCRIPTION:
WFSJ Main 263.0
END DESCRIPTION:
XS GIS Cut Line= 4
      3828831.42     10100200.68      3820655.76     10099007.95
      3816178.49     10098520.67      3814418.04     10098937.35
#Sta/Elev= 30
 -3262.2  140.51 -2771.8  137.02 -2077.7  134.19 -1794.4  136.11 -1402.4  137.83
  -928.4  135.63   188.6  135.57   386.9  133.33  1526.9  129.13  2554.4  127.82
  2774.6  121.44  3010.3  128.21  3887.9  125.21    4432  126.36  4553.2  115.33
  4674.5  128.13    4733  118.37    4816  127.71    4943  123.11  4998.6  114.43
  5203.2  123.06  7815.5  127.72  8379.5  129.91  8734.1  129.11  8960.9  129.06
  9243.3  130.98  9595.8  136.45  9919.2  131.02 10737.5  138.72 11312.8  160.21
#Mann= 20 ,-1 , 0
 -3262.2     .11       0 -2771.8     .17       0 -2077.7     .15       0
 -1794.4     .17       0 -1402.4     .11       0  -928.4     .15       0
   188.6     .11       0   386.9     .15       0  1526.9     .17       0
  2554.4     .15       0  3010.3     .17       0  3887.9     .15       0
    4943     .09       0  5203.2     .15       0  7815.5     .17       0
  8379.5     .15       0  8734.1     .17       0  8960.9     .15       0
  9243.3     .17       0  9595.8     .17       0
#XS Ineff= 4 ,-1
    1315  3441.6  130.45   -3215  -307.7  137.91  8337.5    9390  130.96
  9570.9   10560  136.61
Permanent Ineff=
       F       F       F       F
Bank Sta=4943,5203.2
XS Rating Curve= 0 ,0
Exp/Cntr=0.3,0.1

Type RM Length L Ch R = 1 ,262863  ,863,863,863
BEGIN DESCRIPTION:
WFSJ Main 262.0
END DESCRIPTION:
XS GIS Cut Line= 4
      3829156.83     10100076.65      3822949.89     10098162.08
      3817255.87     10097869.94      3813157.69       10098854.
#Sta/Elev= 30
 -3290.1  141.12 -2969.4  134.16 -1778.7     133 -1496.6  133.65 -1067.2   135.3
  -432.7  136.36  -325.3  135.62  -223.3  135.27  -121.3  136.53    38.7  137.24
     682  135.94   899.2   135.5  1205.3  131.55  2247.5  126.87  3934.8  125.93
  4088.6  125.03    4724  126.23 4867.98   123.1  4889.7  114.54  4998.6  113.46
    5110  122.85    5150   117.7  5350.3  123.91  5390.3  114.87  5670.7  124.74
  5810.9  115.93  6601.9  126.07 10048.9  127.41 12703.5  144.14 13121.6  161.53
#Mann= 20 ,-1 , 0
 -3290.1     .11       0 -2969.4     .17       0 -1778.7     .11       0
 -1496.6     .17       0 -1067.2     .17       0  -432.7     .11       0
  -325.3    .125       0  -223.3     .11       0  -121.3    .125       0
    38.7     .11       0     682     .11       0   899.2    .125       0
  1205.3     .17       0  2247.5     .17       0  3934.8     .17       0
  4088.6     .15       0    4724     .17       0 4867.98     .09       0
    5110     .15       0 10048.9     .17       0
#XS Ineff= 2 ,-1
   -3300  -471.5   139.4  9314.9   10890  132.35
Permanent Ineff=
       F       F
Bank Sta=4867.98,5110
XS Rating Curve= 0 ,0
Exp/Cntr=0.3,0.1

Type RM Length L Ch R = 1 ,262000  ,1000,1000,1000
BEGIN DESCRIPTION:
WFSJ Main 261.0
END DESCRIPTION:
XS GIS Cut Line= 4
       3829250.6     10100041.93      3820990.47     10097240.99
      3815756.62      10097473.8      3813032.74      10098812.3
#Sta/Elev= 30
 -3722.1  141.27 -3427.8  134.49 -2347.2   133.9 -1983.8  135.41 -1398.9  133.73
    -196   136.3     100  136.24   686.7  136.19  1316.3  128.01    1662  126.96
    2021  125.18  2377.6  124.36  2631.3   125.1  3070.9  126.55  3270.3  126.96
  3323.8  127.34  3368.1  142.32  3462.4  142.86  3560.4  125.06    4158  124.62
  4221.4  116.79  4294.6  123.95  4425.5  115.38  4584.7  123.22 4914.86  121.99
  4998.5  113.04 5103.11122.2745 11041.7  128.37 12851.1  145.89   13274  161.96
#Mann= 20 ,-1 , 0
 -3722.1     .11       0 -3427.8     .17       0 -2347.2     .11       0
 -1983.8     .17       0 -1398.9     .17       0    -196     .11       0
     100    .125       0   686.7     .11       0  1316.3     .17       0
    1662     .15       0    2021     .17       0  2377.6     .15       0
  2631.3     .17       0  3070.9     .15       0  3270.3     .17       0
  3560.4     .15       0  4584.7     .17       0 4914.86     .09       0
 5103.11     .15       0 11041.7     .17       0
#XS Ineff= 2 , 0
       0  3462.4  142.86               0
Permanent Ineff=
       F       F
Bank Sta=4914.86,5103.11
XS Rating Curve= 0 ,0
Exp/Cntr=0.3,0.1

Type RM Length L Ch R = 1 ,261000  ,1000,1000,1000
BEGIN DESCRIPTION:
WFSJ Main 260.0
END DESCRIPTION:
XS GIS Cut Line= 3
      3829424.24     10099979.44       3821769.4     10096814.55
      3818723.41     10092185.28
#Sta/Elev= 30
 -3283.3  141.19 -3006.7  135.21 -1953.6  136.37 -1656.2  136.25  -642.1  135.86
  -377.1  135.76   -53.9  135.63   263.1  135.51   891.9  135.51  1837.8  127.64
  2468.4  124.73  3149.3  125.63  3916.1  125.67    4255  120.52  4836.5  120.89
  4998.5   109.3  5104.4  122.02  6706.9  112.45  6996.1  132.08  7197.9  113.63
  7285.3  131.63  7342.5  112.96  7559.4  109.96  7588.8  121.77  7725.1  140.62
  7812.4  127.38  8296.8  135.49  9167.2  143.93 10058.9  152.91 10541.5  156.41
#Mann= 20 ,-1 , 0
 -3283.3     .11       0 -3006.7     .17       0 -1953.6     .11       0
 -1656.2     .17       0  -642.1     .11       0  -377.1     .17       0
   -53.9     .15       0   263.1     .17       0   891.9     .17       0
  1837.8     .11       0  2468.4     .17       0  3149.3     .11       0
  3916.1     .11       0    4255     .15       0  4836.5     .09       0
  5104.4     .15       0  7588.8     .11       0  8296.8     .17       0
  9167.2     .11       0 10058.9     .17       0
#XS Ineff= 4 ,-1
     717  3876.3  137.34   -3265   716.6  138.49  6996.1    7694  132.08
  7725.1    9075  140.62
Permanent Ineff=
       F       F       F       F
Bank Sta=4836.5,5104.4
XS Rating Curve= 0 ,0
Exp/Cntr=0.3,0.1

Type RM Length L Ch R = 1 ,260000  ,1000,1000,1000
BEGIN DESCRIPTION:
WFSJ Main 259.0
END DESCRIPTION:
XS GIS Cut Line= 3
      3829604.77     10099916.93      3822429.18     10096167.12
      3818839.96     10092197.33
#Sta/Elev= 30
 -3096.3   141.2 -2915.3  136.36 -2629.8  134.85 -1905.6  132.78   -1502  132.89
   138.5  138.96   889.1  120.11  1170.6  119.63  1327.4  120.92  1873.1  127.84
  2128.3  127.09  2586.4  125.74  3556.7  122.87  4055.8  119.93  4189.8  120.83
  4572.8  116.34  4685.6  131.75  4745.4  113.42  4850.2   131.7 4892.36  122.07
  4998.5  111.56  5231.8  121.87  6244.4  113.25  6470.8  127.52  6640.4   113.4
  7474.4  127.43  7709.7  141.23  9460.2  146.61  9880.2  150.71 10351.8  156.14
#Mann= 20 ,-1 , 0
 -3096.3     .11       0 -2915.3     .17       0 -2629.8     .17       0
 -1905.6     .11       0   -1502     .17       0   889.1     .17       0
  1170.6     .15       0  1327.4     .17       0  1873.1     .11       0
  2128.3     .11       0  2586.4     .15       0  3556.7     .11       0
  4055.8     .15       0  4189.8     .11       0  4572.8     .17       0
 4892.36     .09       0  5231.8     .15       0  7474.4     .17       0
  9460.2     .11       0  9880.2     .17       0
#XS Ineff= 3 ,-1
                           -3085   138.5  138.96 7709.78    9035  141.23
Permanent Ineff=
       F       F       F
Bank Sta=4892.36,5231.8
XS Rating Curve= 0 ,0
Exp/Cntr=0.3,0.1

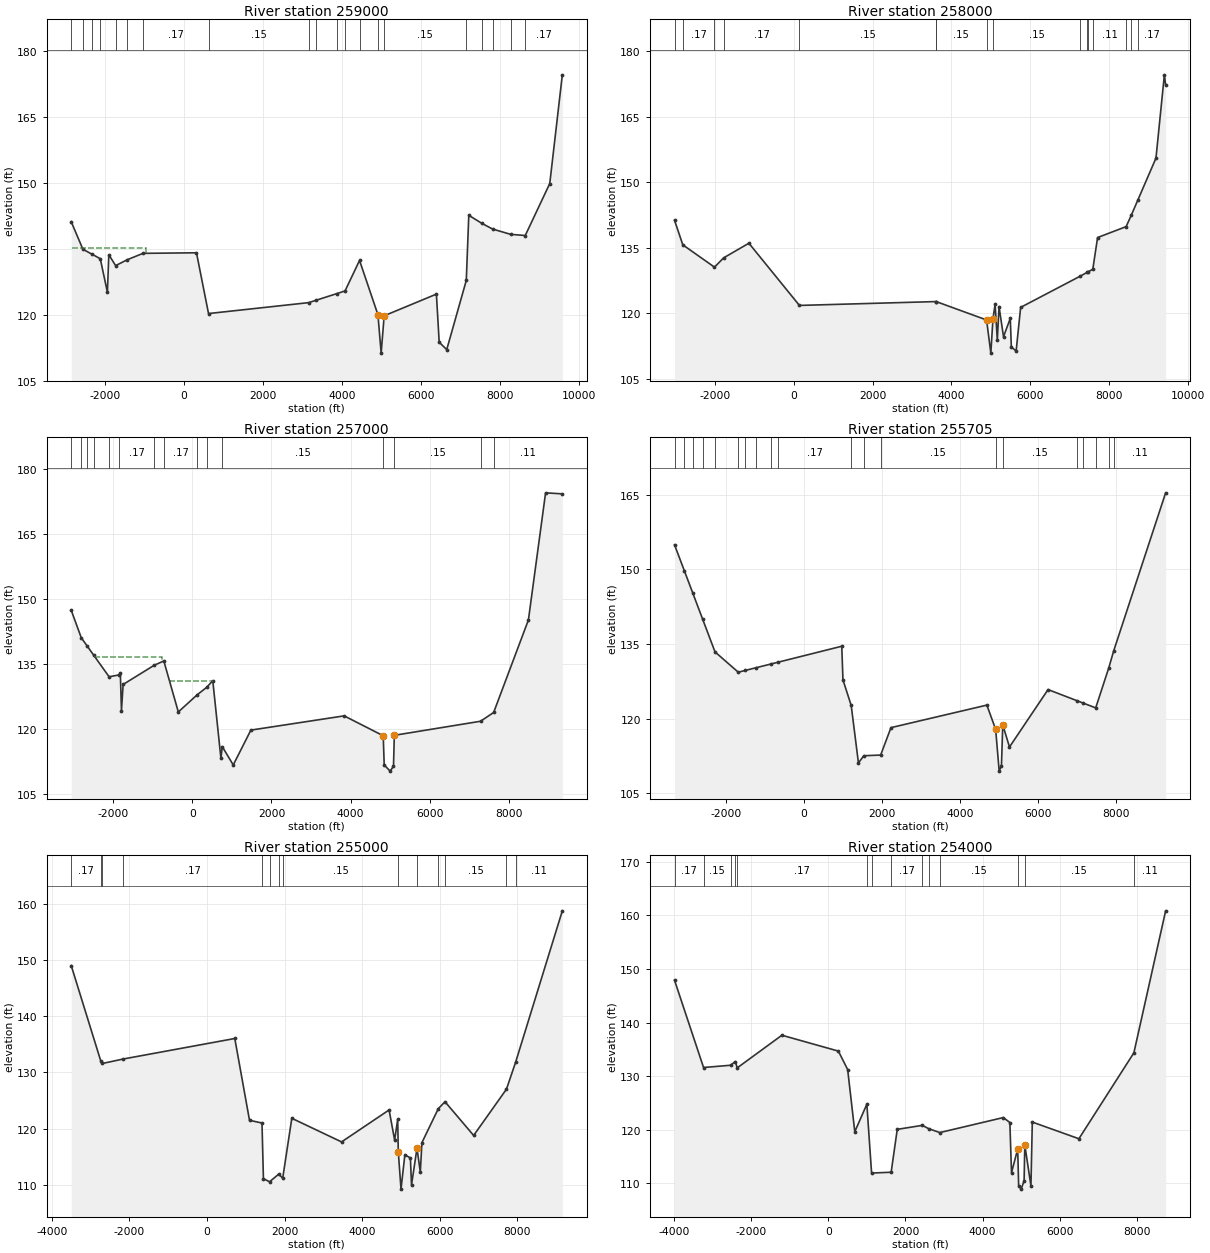
Type RM Length L Ch R = 1 ,259000  ,1000,1000,1000
BEGIN DESCRIPTION:
WFSJ Main 258.0
END DESCRIPTION:
XS GIS Cut Line= 3
      3829781.84     10099854.42      3823191.56     10095583.11
      3820051.84     10092237.41
#Sta/Elev= 30
 -2853.4  141.16 -2557.6   134.9 -2334.1  133.81 -2117.1  132.75 -1937.1  125.12
 -1900.8  133.66 -1728.6  131.18 -1433.4  132.52 -1035.4  133.97   319.8   134.1
   624.9  120.28  3160.1  122.76  3352.7  123.31  3876.8  124.82  4083.1  125.42
  4450.9  132.36 4916.68  120.01  4998.5  111.28  5074.7  119.77  6397.9   124.7
  6468.7  113.76  6659.7  112.08  7155.1  127.81  7218.5  142.63  7549.5  140.79
  7821.2   139.5  8279.4  138.29  8649.1  138.03  9269.9  149.85  9588.2  174.57
#Mann= 20 ,-1 , 0
 -2853.4     .11       0 -2557.6     .17       0 -2334.1     .15       0
 -2117.1     .17       0 -1728.6     .11       0 -1433.4     .15       0
 -1035.4     .17       0   624.9     .15       0  3160.1     .17       0
  3352.7     .15       0  3876.8     .15       0  4083.1     .11       0
  4450.9     .15       0 4916.68     .09       0  5074.7     .15       0
  7155.1     .17       0  7549.5     .17       0  7821.2     .11       0
  8279.4     .11       0  8649.1     .17       0
#XS Ineff= 1 ,-1
   -2830  -953.9  135.15
Permanent Ineff=
       F
Bank Sta=4916.68,5074.7
XS Rating Curve= 0 ,0
Exp/Cntr=0.3,0.1

Type RM Length L Ch R = 1 ,258000  ,1000,1000,1000
BEGIN DESCRIPTION:
WFSJ Main 257.0
END DESCRIPTION:
XS GIS Cut Line= 3
      3829983.28     10099785.01      3823731.89     10094765.81
      3820272.53     10092002.24
#Sta/Elev= 30
   -3017  141.25 -2807.2  135.63 -2004.3  130.52 -1772.8  132.65 -1132.6     136
   147.7  121.76  3599.2  122.64  3612.5  122.64  4890.3  118.43  4998.5  110.84
 5051.64  118.68  5106.4  121.98  5162.5  113.83  5205.7  121.51  5319.4   114.6
  5490.7  118.78  5517.9  112.22  5639.6  111.34  5753.3  121.31  7267.8  128.48
  7433.3   129.3  7450.1  129.38  7581.9  130.04  7703.3   137.3  8426.1   139.8
  8554.7  142.36  8720.8  145.83  9182.7  155.48  9395.6  174.55  9427.7  172.27
#Mann= 16 ,-1 , 0
   -3017     .11       0 -2807.2     .17       0 -2004.3     .11       0
 -1772.8     .17       0   147.7     .15       0  3599.2     .17       0
  3612.5     .15       0  4890.3     .09       0 5051.64     .15       0
  7267.8     .17       0  7433.3     .15       0  7450.1     .17       0
  7581.9     .11       0  8426.1     .17       0  8554.7     .11       0
  8720.8     .17       0
#XS Ineff= 1 ,-1
   -3000 -1132.6     136
Permanent Ineff=
       F
Bank Sta=4890.3,5051.64
XS Rating Curve= 0 ,0
Exp/Cntr=0.3,0.1

Type RM Length L Ch R = 1 ,257000  ,1295,1295,1295
BEGIN DESCRIPTION:
WFSJ Main 256.0
END DESCRIPTION:
XS GIS Cut Line= 3
      3830344.71     10099687.76      3824455.36      10094189.5
      3821061.88     10091472.44
#Sta/Elev= 30
   -3057  147.41 -2803.4  141.08 -2648.9   139.1 -2487.2  137.03 -2099.8  132.08
 -1858.6   132.5 -1816.4  132.84 -1788.2  124.31 -1745.7  130.32  -962.5  134.73
  -718.3  135.73    -352  123.98   128.7  127.97   361.6  129.63   518.6  131.18
   723.8  113.33   758.6  115.99    1035  111.77  1480.7   119.8  3836.7  123.08
 4823.13   118.5  4848.4  111.77  4998.2  110.35  5082.8  111.48  5103.6   118.6
  7281.1  121.84  7612.4  123.86  8490.5  145.17  8924.3  174.46  9347.2  174.22
#Mann= 15 ,-1 , 0
   -3057     .11       0 -2803.4     .17       0 -2648.9     .15       0
 -2487.2     .17       0 -2099.8     .11       0 -1858.6     .17       0
  -962.5     .11       0  -718.3     .17       0   128.7     .11       0
   361.6     .17       0   758.6     .15       0 4823.13     .09       0
  5103.6     .15       0  7281.1     .17       0  7612.4     .11       0
#XS Ineff= 2 ,-1
   -2490  -769.2  136.55    -570   518.6  131.18
Permanent Ineff=
       F       F
Bank Sta=4823.13,5103.6
XS Rating Curve= 0 ,0
Exp/Cntr=0.3,0.1

Type RM Length L Ch R = 1 ,255705  ,705,705,705
BEGIN DESCRIPTION:
WFSJ Main 255.0
END DESCRIPTION:
XS GIS Cut Line= 3
      3832416.05     10098012.06      3825671.29     10093702.18
      3822129.61     10090798.53
#Sta/Elev= 30
 -3320.4  154.95 -3067.6   149.7 -2848.6  145.16 -2601.2  140.02   -2283  133.42
 -1686.9  129.34 -1505.2   129.7 -1221.8  130.26  -854.3  130.98  -662.2  131.36
   964.8  134.56   995.3  127.81    1207  122.65    1392   111.1  1528.6  112.55
  1961.5  112.69  2225.3   118.2  4682.9  122.73  4907.9  117.85  4998.2  109.46
  5056.5  110.56 5090.16118.7531  5262.5  114.31  6250.7  125.85  6983.4  123.64
  7146.1  123.15  7471.5  122.17  7808.1  130.25  7931.8  133.61  9263.6  165.39
#Mann= 20 ,-1 , 0
 -3320.4     .11       0 -3067.6     .17       0 -2848.6     .11       0
 -2601.2     .15       0   -2283     .17       0 -1686.9     .15       0
 -1505.2     .17       0 -1221.8     .17       0  -854.3     .11       0
  -662.2     .17       0    1207     .15       0  1528.6     .11       0
  1961.5     .15       0  4907.9     .09       0 5090.16     .15       0
  6983.4     .17       0  7146.1     .15       0  7471.5     .11       0
  7808.1     .17       0  7931.8     .11       0
Bank Sta=4907.9,5090.16
XS Rating Curve= 0 ,0
Exp/Cntr=0.3,0.1

Type RM Length L Ch R = 1 ,255000  ,1000,1000,1000
BEGIN DESCRIPTION:
WFSJ Main 254.0
END DESCRIPTION:
XS GIS Cut Line= 3
       3832806.9      10097955.5       3825901.6     10092995.91
      3822768.46      10090265.4
#Sta/Elev= 30
 -3501.8  148.99 -2743.6  132.11 -2699.4  131.59 -2157.7  132.39     714  136.03
  1093.4  121.49  1415.1  121.01    1452  111.13  1609.3  110.56  1845.8  111.92
  1949.2  111.21  2183.7  121.85  3465.6  117.65  4690.9  123.33  4833.4  117.98
  4913.1  121.68  4927.9  115.92  4998.2  109.26  5097.8  115.38  5240.2  114.79
  5268.7     110  5410.1  116.53  5495.6  112.29  5537.3  117.53  5959.4  123.56
  6132.3  124.79  6870.3   118.8  7715.7  127.02  7953.3  131.84    9156  158.72
#Mann= 14 ,-1 , 0
 -3501.8     .17       0 -2743.6     .11       0 -2699.4     .15       0
 -2157.7     .17       0  1415.1     .11       0  1609.3     .15       0
  1845.8     .11       0  1949.2     .15       0  4927.9     .09       0
  5410.1     .15       0  5959.4     .11       0  6132.3     .15       0
  7715.7     .17       0  7953.3     .11       0
Bank Sta=4927.9,5410.1
XS Rating Curve= 0 ,0
Exp/Cntr=0.3,0.1

Type RM Length L Ch R = 1 ,254000  ,1000,1000,1000
BEGIN DESCRIPTION:
WFSJ Main 253.0
END DESCRIPTION:
XS GIS Cut Line= 4
      3833091.59     10097997.14      3832695.77     10097531.87
       3826296.2     10092136.21       3823432.3     10089731.33
#Sta/Elev= 30
 -3981.5   147.9 -3229.8  131.62 -2529.9  132.04 -2406.2  132.74 -2357.7  131.55
 -1200.4  137.64   262.4  134.68   503.1  131.24   687.7  119.64  1000.1  124.77
  1122.8  111.93  1629.6  112.08  1787.8  120.08  2438.2  120.83    2598  120.22
    2890  119.48  4534.2  122.28  4704.5  121.36  4747.4     112  4908.1  116.42
  4908.1  116.43    4932   109.6  4998.2  108.93  5073.8  110.51 5091.32  117.19
  5250.7  109.54  5285.9  121.44    6493  118.33    7917  134.36  8739.7  160.85
#Mann= 14 ,-1 , 0
 -3981.5     .17       0 -3229.8     .15       0 -2529.9     .17       0
 -2406.2     .15       0 -2357.7     .17       0  1000.1     .15       0
  1122.8     .11       0  1629.6     .17       0  2438.2     .15       0
    2598     .17       0    2890     .15       0  4908.1     .09       0
 5091.32     .15       0    7917     .11       0
Bank Sta=4908.1,5091.32
XS Rating Curve= 0 ,0
Exp/Cntr=0.3,0.1

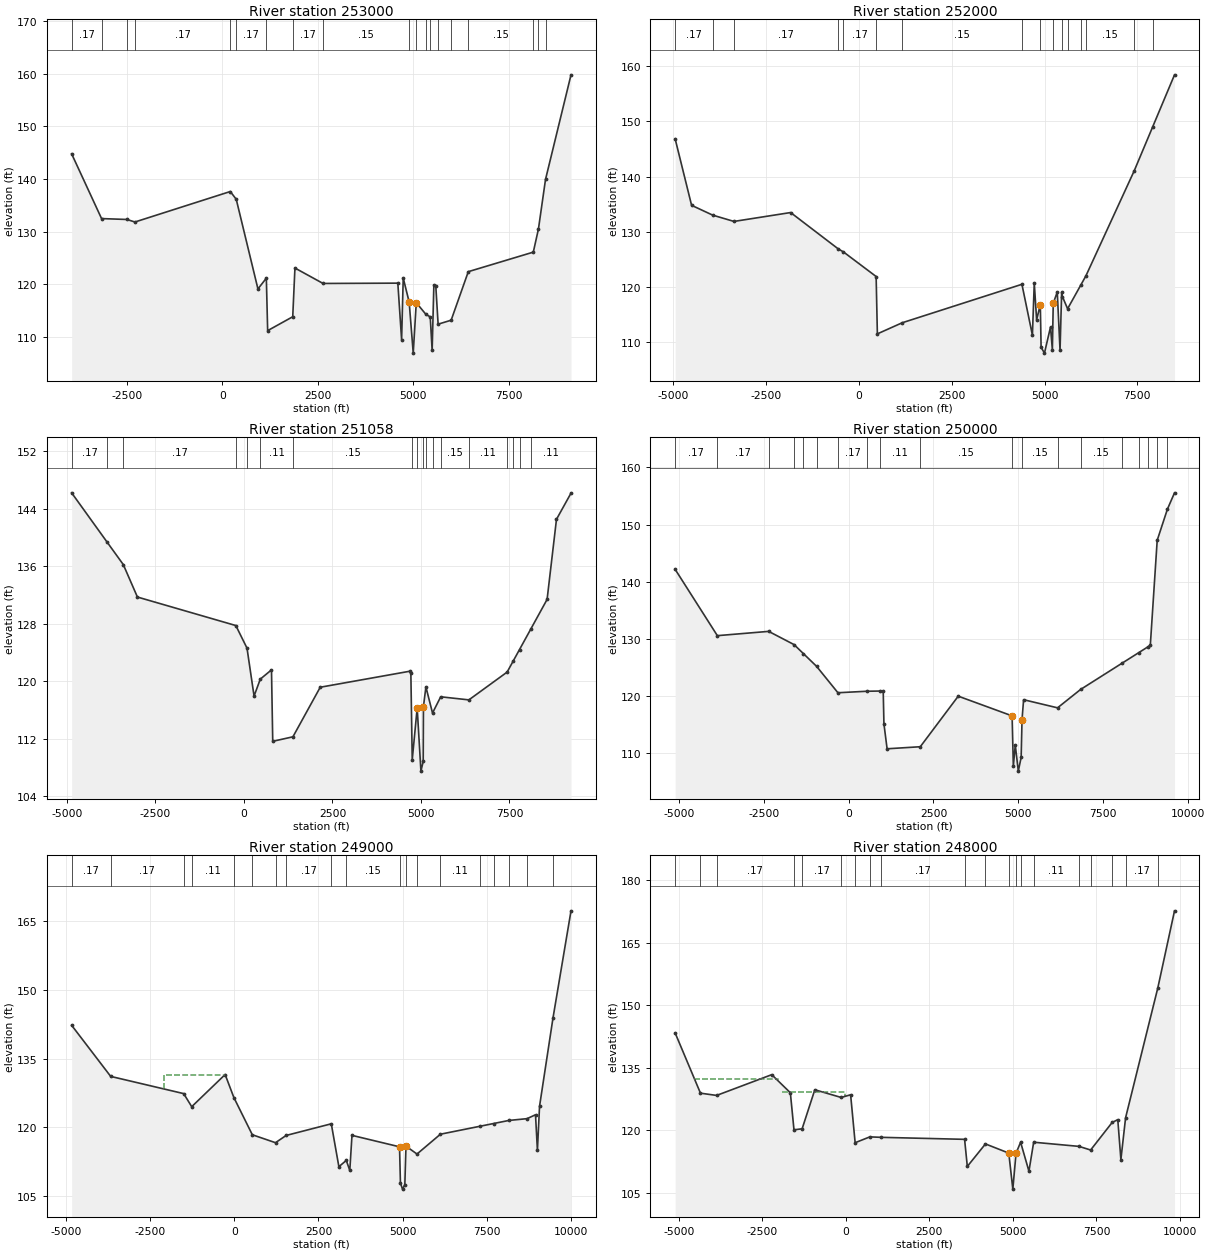
Type RM Length L Ch R = 1 ,253000  ,1000,1000,1000
BEGIN DESCRIPTION:
WFSJ Main 252.0
END DESCRIPTION:
XS GIS Cut Line= 4
      3833195.77      10098004.1      3832792.99     10097358.26
      3827024.34      10091551.7      3823613.96     10089222.99
#Sta/Elev= 30
 -3946.1  144.77 -3162.6  132.47 -2497.3   132.3 -2289.1  131.82   208.1  137.61
   363.8  136.14   932.1  119.11    1152  121.16  1186.6  111.19  1843.2  113.83
  1900.8  123.08  2637.3  120.15  4594.9  120.21  4693.9  109.48  4736.3  121.18
  4891.9  116.61  4998.2  106.92  5077.7   116.5  5331.3  114.27  5443.2  113.81
  5493.5  107.42  5538.3  119.87  5589.1  119.66  5649.8  112.42  5990.9  113.17
  6440.1  122.39  8142.1   126.1  8276.7  130.49  8461.8   139.9  9129.6  159.77
#Mann= 19 ,-1 , 0
 -3946.1     .17       0 -3162.6     .15       0 -2497.3     .17       0
 -2289.1     .17       0   208.1     .11       0   363.8     .17       0
    1152     .11       0  1843.2     .17       0  2637.3     .15       0
  4891.9     .07       0  5077.7     .15       0  5331.3     .15       0
  5443.2     .17       0  5649.8     .15       0  5990.9     .11       0
  6440.1     .15       0  8142.1     .11       0  8276.7     .17       0
  8461.8     .11       0
Bank Sta=4891.9,5077.7
XS Rating Curve= 0 ,0
Exp/Cntr=0.3,0.1

Type RM Length L Ch R = 1 ,252000  ,942,942,942
BEGIN DESCRIPTION:
WFSJ Main 251.0
END DESCRIPTION:
XS GIS Cut Line= 3
      3833591.57     10097983.23      3826960.74     10090557.33
      3823926.51     10088806.36
#Sta/Elev= 30
 -4955.5  146.85   -4512   134.8 -3943.2  133.02 -3370.3  131.88 -1842.3  133.49
  -558.8   126.9  -420.4  126.36   461.5   121.9   494.9  111.51  1163.6  113.52
  4390.6  120.49  4673.2  111.28  4723.4  120.73  4786.9  114.05  4886.4  116.81
  4907.3  109.08  4998.2  108.02  5160.9  112.75  5211.2  108.63 5234.87  117.04
  5343.3   119.1  5417.9  108.52    5461  119.01  5482.2  118.26  5621.5  116.06
  5980.5  120.39  6116.6  122.04  7418.3  141.07    7910  148.94  8503.2  158.44
#Mann= 16 ,-1 , 0
 -4955.5     .17       0 -3943.2     .15       0 -3370.3     .17       0
  -558.8     .11       0  -420.4     .17       0   461.5     .11       0
  1163.6     .15       0  4390.6     .11       0  4886.4     .06       0
 5234.87     .11       0  5482.2     .17       0  5621.5     .15       0
  5980.5     .11       0  6116.6     .15       0  7418.3     .17       0
    7910     .11       0
Bank Sta=4886.4,5234.87
XS Rating Curve= 0 ,0
Exp/Cntr=0.3,0.1

Type RM Length L Ch R = 1 ,251058  ,1058,1058,1058
BEGIN DESCRIPTION:
WFSJ Main 250.0
END DESCRIPTION:
XS GIS Cut Line= 5
      3833702.72     10097962.45      3827559.31     10089965.21
      3826817.12     10089470.41      3825593.16     10089314.16
       3824071.3     10088182.52
#Sta/Elev= 30
 -4868.9  146.22 -3864.7  139.34 -3409.7  136.23 -3010.7  131.71  -230.2  127.74
    85.4  124.59   284.6  117.92   460.6  120.28   776.8  121.57   812.1  111.62
  1382.4  112.25  2153.4  119.15  4684.7  121.38  4713.7  121.13  4752.6  109.04
  4892.3  116.27  4998.2  107.47  5062.6  108.82 5069.26  116.46    5139   119.2
  5325.5  115.56  5556.7  117.82  6352.8  117.39  7433.3  121.26  7611.6  122.86
  7783.3   124.4  8109.4  127.32  8562.4  131.38  8827.3  142.53    9238  146.18
#Mann= 18 ,-1 , 0
 -4868.9     .17       0 -3864.7     .15       0 -3409.7     .17       0
  -230.2     .11       0    85.4     .17       0   460.6     .11       0
  1382.4     .15       0  4752.6     .15       0  4892.3     .09       0
 5069.26     .15       0    5139     .11       0  5325.5     .17       0
  5556.7     .15       0  6352.8     .11       0  7433.3     .15       0
  7611.6     .11       0  7783.3     .17       0  8109.4     .11       0
Bank Sta=4892.3,5069.26
XS Rating Curve= 0 ,0
Exp/Cntr=0.3,0.1

Type RM Length L Ch R = 1 ,250000  ,1000,1000,1000
BEGIN DESCRIPTION:
WFSJ Main 249.0
END DESCRIPTION:
XS GIS Cut Line= 3
      3833853.76     10097813.48      3828279.41     10089384.85
      3824666.23     10086542.62
#Sta/Elev= 30
 -5105.2  142.17 -3862.3  130.56 -2351.5  131.31 -1602.4  128.99 -1330.9  127.43
  -940.7  125.19  -312.7  120.57   540.7  120.83   928.8  120.87  1020.9  120.88
    1042  115.12  1135.3  110.76  2112.2  111.12  3229.7  119.97  4815.6  116.52
  4851.7  107.72  4908.9  111.43  4998.2  106.85  5081.8  109.26 5107.68115.8818
    5154  119.35  6153.5  117.93  6830.9  121.14  8049.5  125.73  8536.9  127.56
    8818  128.62  8884.4  128.87  9087.2  147.25    9388   152.7  9597.1  155.56
#Mann= 19 ,-1 , 0
 -5105.2     .17       0 -3862.3     .17       0 -2351.5     .17       0
 -1602.4     .15       0 -1330.9     .11       0  -940.7     .17       0
  -312.7     .17       0   540.7     .17       0   928.8     .11       0
  2112.2     .15       0  4815.6     .09       0 5107.68     .15       0
  6153.5     .11       0  6830.9     .15       0  8049.5     .17       0
  8536.9     .15       0    8818     .11       0  9087.2     .17       0
    9388     .11       0
Bank Sta=4815.6,5107.68
XS Rating Curve= 0 ,0
Exp/Cntr=0.3,0.1

Type RM Length L Ch R = 1 ,249000  ,1000,1000,1000
BEGIN DESCRIPTION:
WFSJ Main 248.0
END DESCRIPTION:
XS GIS Cut Line= 3
      3834062.08     10097813.45       3829257.4     10089234.81
      3825687.08     10085730.13
#Sta/Elev= 30
 -4832.5  142.24 -3672.4   131.1 -1503.9  127.35 -1265.1   124.5  -272.2  131.51
   -13.3   126.5   535.2  118.38  1223.9  116.65  1540.1  118.23  2881.3  120.77
  3106.7  111.42  3327.1  112.79  3430.9   110.6    3496  118.25 4908.69115.7532
  4935.5  107.83  4998.2  106.53    5066  107.51 5100.22 115.895  5427.7  114.18
  6123.1   118.5  7289.8  120.22  7702.9  120.83  8157.2   121.5  8697.2  121.89
  8948.2  122.74  9004.8     115  9068.3  124.61  9467.4  143.82   10003  167.19
#Mann= 19 ,-1 , 0
 -4832.5     .17       0 -3672.4     .17       0 -1503.9     .15       0
 -1265.1     .11       0   -13.3     .11       0   535.2     .15       0
  1223.9     .11       0  1540.1     .17       0  2881.3     .11       0
  3327.1     .15       0 4908.69     .09       0 5100.22     .15       0
  5427.7     .11       0  6123.1     .11       0  7289.8     .15       0
  7702.9     .17       0  8157.2     .15       0  8697.2     .15       0
  9467.4     .11       0
#XS Ineff= 1 ,-1
   -2100  -272.2  131.51
Permanent Ineff=
       F
Bank Sta=4908.69,5100.22
XS Rating Curve= 0 ,0
Exp/Cntr=0.3,0.1

Type RM Length L Ch R = 1 ,248000  ,997,997,997
BEGIN DESCRIPTION:
WFSJ Main 247.0
END DESCRIPTION:
XS GIS Cut Line= 3
      3834286.04     10097912.41      3830083.59     10088720.52
      3827042.02     10084960.25
#Sta/Elev= 30
   -5107  143.37 -4348.9  128.92 -3865.5  128.38 -2216.2  133.36 -1659.3  129.02
 -1550.7  120.13   -1307  120.38  -927.2  129.74  -137.1  127.89   144.2  128.54
   279.4  117.04   718.9  118.44    1066  118.33  3554.7  117.85  3636.2  111.35
  4178.9  116.75 4876.59  114.55  4998.2  105.91 5094.29114.5215  5230.8  117.16
  5479.9  110.21  5621.5  117.16  6979.4  116.16  7326.1  115.29  7970.7   121.9
  8138.8  122.57  8231.6     113  8372.6  123.04  9336.5  154.16  9836.4  172.65
#Mann= 20 ,-1 , 0
   -5107     .17       0 -4348.9     .15       0 -3865.5     .17       0
 -1550.7     .15       0   -1307     .17       0  -137.1     .17       0
   279.4     .15       0   718.9     .17       0    1066     .17       0
  3554.7     .15       0  4178.9     .15       0 4876.59     .09       0
 5094.29     .15       0  5230.8     .17       0  5621.5     .11       0
  6979.4     .11       0  7326.1     .15       0  7970.7     .17       0
  8372.6     .17       0  9336.5     .11       0
#XS Ineff= 2 ,-1
   -1900   -22.4  129.16   -4550 -2037.8  132.37
Permanent Ineff=
       F       F
Bank Sta=4876.59,5094.29
XS Rating Curve= 0 ,0
Exp/Cntr=0.3,0.1