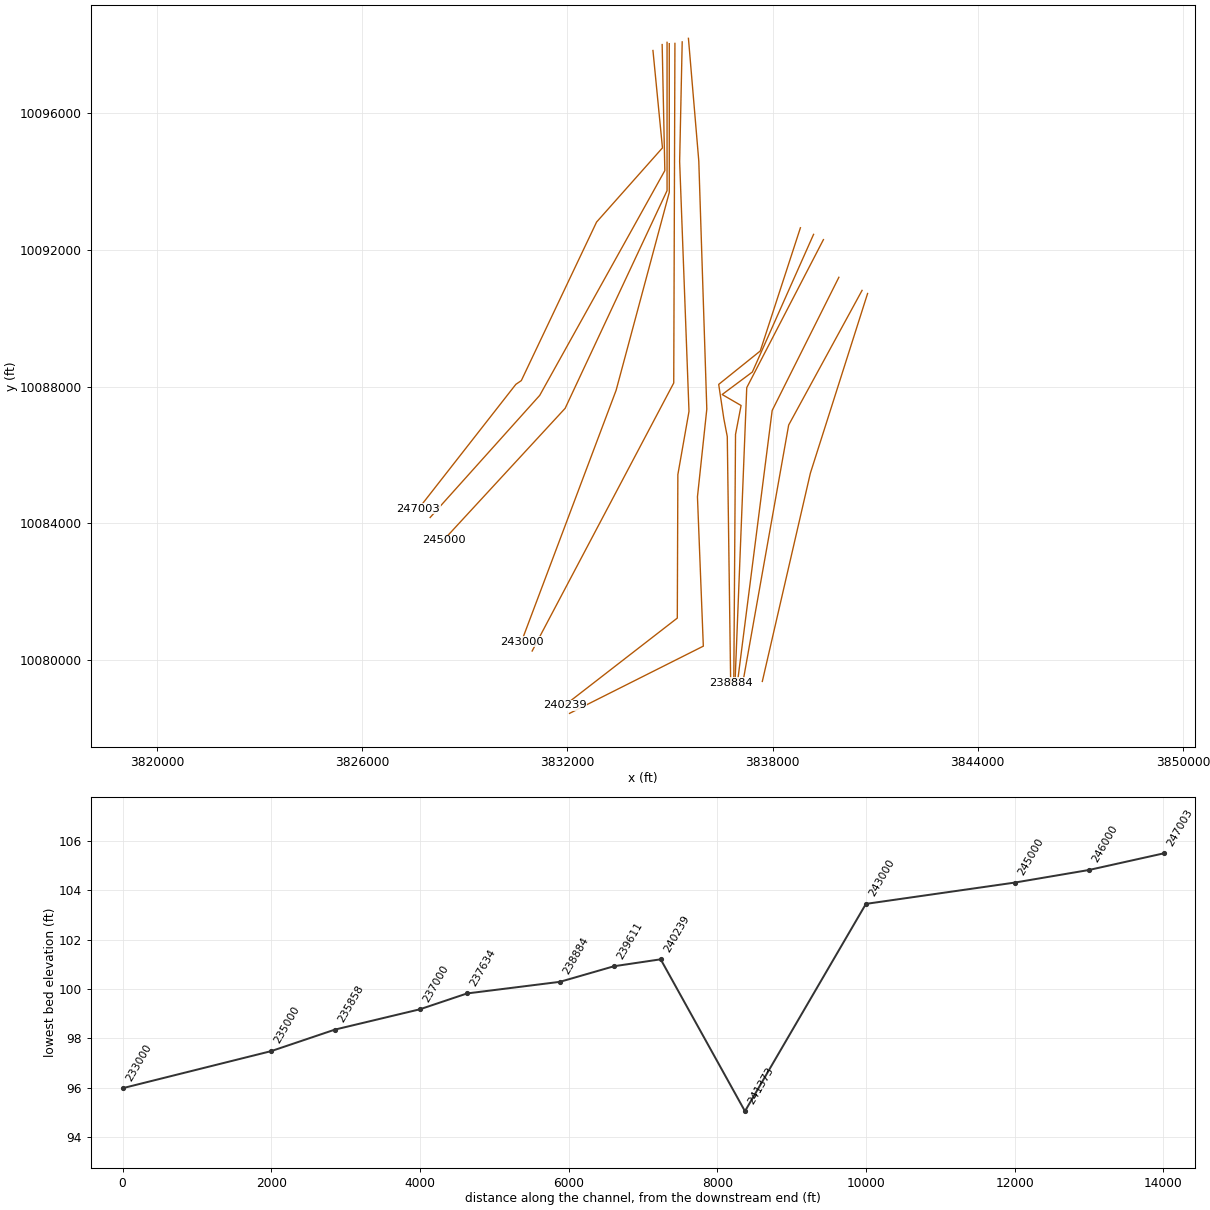
HEC-RAS study WFSJ Main.prj: WFSJ Main Base Level Engineering

--- WFSJ Main.g01 (geometry) --- (continued)

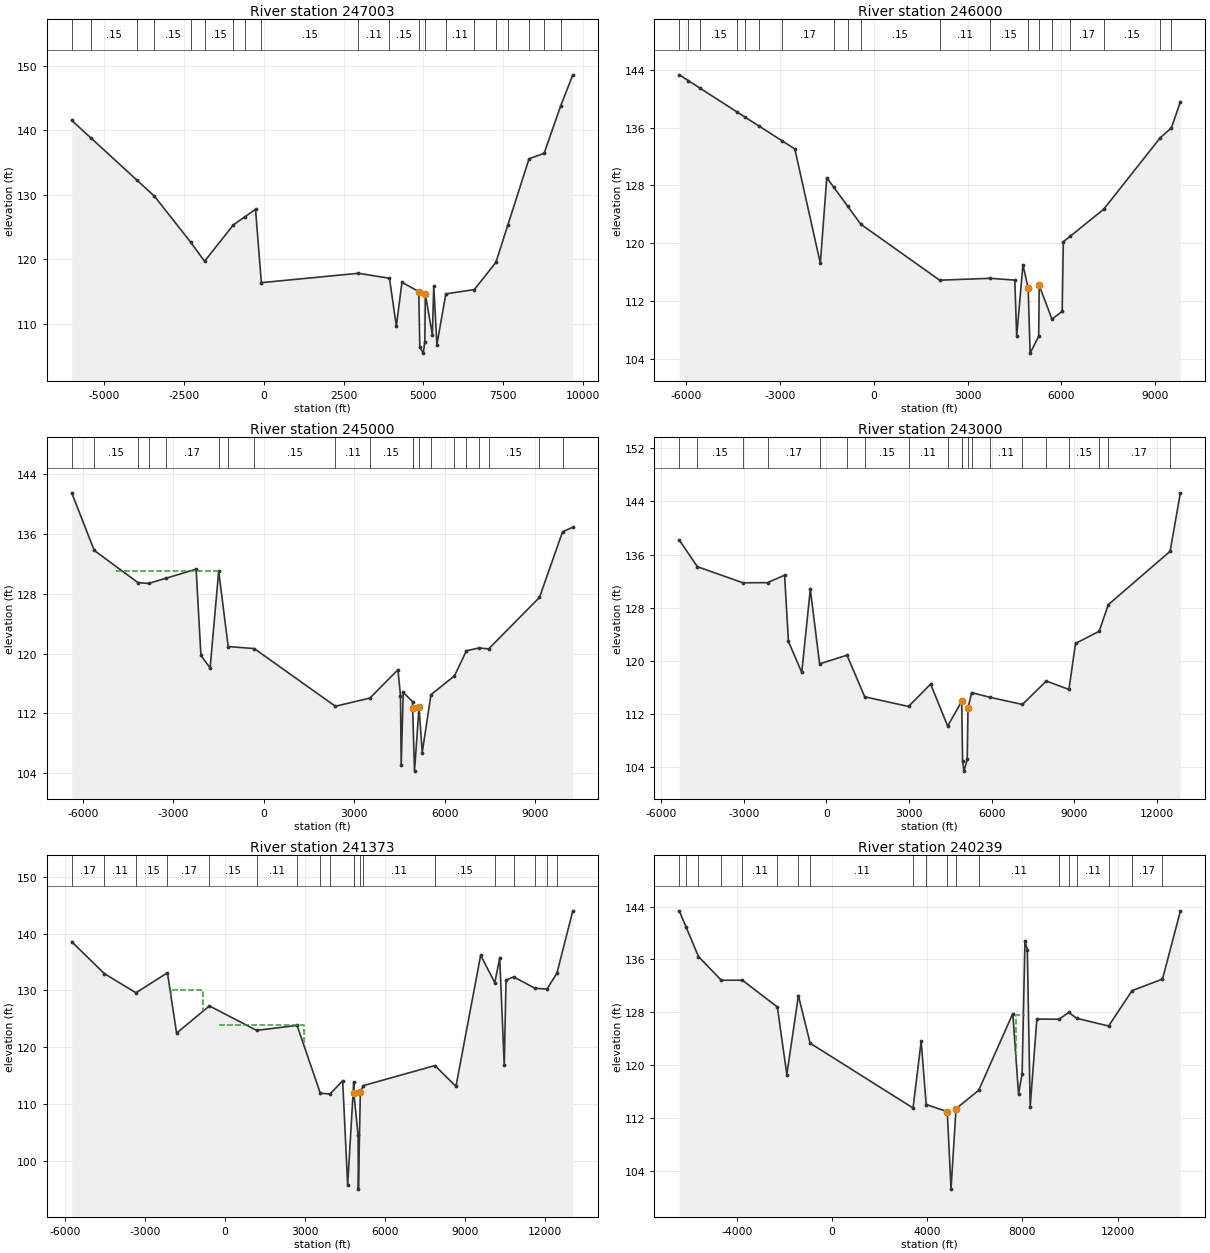
Type RM Length L Ch R = 1 ,247003  ,1003,1003,1003
BEGIN DESCRIPTION:
WFSJ Main 246.0
END DESCRIPTION:
XS GIS Cut Line= 6
      3834503.06     10097825.62      3834780.84      10094978.4
      3832853.75     10092808.26      3830653.48      10088172.6
      3830493.98     10088064.09      3827645.45     10084422.88
#Sta/Elev= 30
 -6023.7  141.54 -5424.3  138.83 -3992.1  132.34 -3434.7  129.82 -2295.3  122.68
 -1859.3  119.71  -954.5  125.36  -587.1  126.63  -260.7  127.76   -78.5   116.4
  2966.5  117.85  3938.7  117.08  4153.8  109.67  4329.9  116.46  4858.1  115.02
  4889.5  106.43  4998.2  105.48  5047.5  107.27  5061.8  114.66  5283.2   108.3
  5326.4  115.92  5425.8   106.8  5705.3  114.66  6598.6  115.33  7276.3  119.55
  7653.1  125.37    8315   135.6  8786.5  136.43  9301.3  143.73  9686.6   148.6
#Mann= 20 ,-1 , 0
 -6023.7     .17       0 -5424.3     .15       0 -3992.1     .17       0
 -3434.7     .15       0 -2295.3     .15       0 -1859.3     .15       0
  -954.5     .17       0  -587.1     .11       0   -78.5     .15       0
  2966.5     .11       0  3938.7     .15       0  4858.1     .09       0
  5061.8     .15       0  5705.3     .11       0  6598.6     .15       0
  7276.3     .17       0  7653.1     .15       0    8315     .11       0
  8786.5     .11       0  9301.3     .17       0
#XS Ineff= 1 ,-1
   -3290  -260.7  127.76
Permanent Ineff=
       F
Bank Sta=4858.1,5061.8
XS Rating Curve= 0 ,0
Exp/Cntr=0.3,0.1

Type RM Length L Ch R = 1 ,246000  ,1000,1000,1000
BEGIN DESCRIPTION:
WFSJ Main 245.0
END DESCRIPTION:
XS GIS Cut Line= 4
      3834772.15     10097999.26      3834850.28     10094314.34
      3831192.11     10087741.51       3827988.3     10084171.11
#Sta/Elev= 30
   -6208  143.31 -5919.6  142.51 -5538.9  141.45 -4357.9  138.16 -4114.6  137.48
 -3656.3  136.21 -2935.3  134.21 -2517.5  133.06 -1702.6  117.24 -1496.8  129.08
 -1280.9   127.8  -830.4  125.14    -408  122.64  2108.7   114.9  3731.2  115.16
  4509.5  114.91    4569  107.18  4769.1  117.04  4937.2  113.76  4998.2  104.81
  5272.2  107.13 5288.46  114.19  5696.4  109.51  6022.7  110.59  6058.6  120.21
    6286     121  7346.9  124.71  9155.8  134.61  9511.9  135.98  9797.1  139.58
#Mann= 19 ,-1 , 0
   -6208     .17       0 -5919.6     .17       0 -5538.9     .15       0
 -4357.9     .15       0 -4114.6     .17       0 -3656.3     .15       0
 -2935.3     .17       0 -1280.9     .15       0  -830.4     .17       0
    -408     .15       0  2108.7     .11       0  3731.2     .15       0
  4937.2     .07       0 5288.46     .15       0  5696.4     .11       0
    6286     .17       0  7346.9     .15       0  9155.8     .17       0
  9511.9     .17       0
#XS Ineff= 1 ,-1
   -2450 -1496.8  129.08
Permanent Ineff=
       F
Bank Sta=4937.2,5288.46
XS Rating Curve= 0 ,0
Exp/Cntr=0.3,0.1

Type RM Length L Ch R = 1 ,245000  ,2000,2000,2000
BEGIN DESCRIPTION:
WFSJ Main 244.0
END DESCRIPTION:
XS GIS Cut Line= 4
      3834915.38     10098064.32      3834915.38      10093728.4
       3831935.4      10087362.6       3828378.9     10083507.02
#Sta/Elev= 30
 -6364.7  141.45 -5619.7  133.77 -4170.7  129.47 -3817.2  129.35 -3238.3  130.05
 -2241.4  131.26 -2081.4  119.74 -1777.8  118.07 -1492.7  130.99 -1178.7  120.93
  -313.6  120.66  2374.4  112.96  3519.4  114.05  4449.6  117.83  4533.4  114.38
  4556.2  105.16  4624.7  114.81  4932.6  113.58 4935.87  112.74  4998.2   104.3
  5148.1  112.84  5254.1  106.78  5543.3   114.5  6322.6  117.02    6719  120.37
  7138.2  120.74  7456.2  120.62  9140.1  127.49  9907.1  136.26 10245.4  136.86
#Mann= 20 ,-1 , 0
 -6364.7     .17       0 -5619.7     .15       0 -4170.7     .17       0
 -3817.2     .15       0 -3238.3     .17       0 -1492.7     .17       0
 -1178.7     .15       0  -313.6     .15       0  2374.4     .11       0
  3519.4     .15       0  4932.6     .12       0 4935.87     .09       0
  5148.1     .15       0  5543.3     .15       0  6322.6     .11       0
    6719     .17       0  7138.2     .17       0  7456.2     .15       0
  9140.1     .17       0  9907.1     .17       0
#XS Ineff= 1 ,-1
   -4900 -1490.7  131.03
Permanent Ineff=
       F
Bank Sta=4935.87,5148.1
XS Rating Curve= 0 ,0
Exp/Cntr=0.3,0.1

Type RM Length L Ch R = 1 ,243000  ,1627,1627,1627
BEGIN DESCRIPTION:
WFSJ Main 242.0
END DESCRIPTION:
XS GIS Cut Line= 4
      3834980.49      10098025.3      3834980.49     10093676.32
        3833426.     10087890.59      3830657.58     10080538.33
#Sta/Elev= 30
 -5339.9  138.18 -4682.8  134.17 -3030.5  131.75 -2134.5  131.77 -1515.7  132.89
 -1375.7  122.94  -892.3  118.27  -581.7  130.79  -244.2  119.56   749.7  120.87
  1394.5  114.61  2985.2  113.16    3788  116.53  4405.9  110.21 4911.79113.8956
  4916.7  114.03  4947.7  104.99  4998.2  103.44    5117  105.19 5144.79112.9325
  5277.5  115.24  5926.1  114.55  7119.4  113.46  7987.8  116.98  8809.3  115.72
  9049.3  122.64  9906.8  124.45   10241  128.47 12483.5  136.48 12856.2  145.27
#Mann= 20 ,-1 , 0
 -5339.9     .17       0 -4682.8     .15       0 -3030.5     .15       0
 -2134.5     .17       0  -244.2     .15       0   749.7     .17       0
  1394.5     .15       0  2985.2     .11       0  4405.9     .15       0
 4911.79     .12       0  4916.7     .09       0 5144.79     .17       0
  5277.5     .11       0  5926.1     .11       0  7119.4     .15       0
  7987.8     .15       0  8809.3     .15       0  9906.8    .125       0
   10241     .17       0 12483.5     .11       0
#XS Ineff= 1 ,-1
   -1700  -581.7  130.79
Permanent Ineff=
       F
Bank Sta=4916.7,5144.79
XS Rating Curve= 0 ,0
Exp/Cntr=0.3,0.1

Type RM Length L Ch R = 1 ,241373  ,1134,1134,1134
BEGIN DESCRIPTION:
WFSJ Main 240.0
END DESCRIPTION:
XS GIS Cut Line= 3
      3835145.42     10098033.98       3835110.7      10088103.4
       3830970.4     10080265.48
#Sta/Elev= 30
 -5751.5  138.57 -4528.6  132.96 -3341.1  129.59 -2160.9  133.11 -1818.6  122.49
  -587.4  127.28  1182.9  122.98  2701.5  123.85  3573.5  111.92  3936.7   111.8
  4411.8  114.11  4598.6   95.75  4826.4  113.88 4832.48111.8833  4989.3   104.5
  5001.9   95.06  5074.3  112.06  5176.1  113.25    7872  116.79  8660.3  113.12
  9586.6  136.19 10117.8  131.37 10301.8  135.71 10472.2  116.83 10538.3  131.81
 10823.1  132.39 11620.6  130.39 12071.7  130.23 12445.2     133 13043.4     144
#Mann= 19 ,-1 , 0
 -5751.5     .17       0 -4528.6     .11       0 -3341.1     .15       0
 -2160.9     .17       0  -587.4     .15       0  1182.9     .11       0
  2701.5     .11       0  3573.5     .17       0  3936.7     .15       0
  4826.4     .12       0 4832.48     .09       0  5074.3     .15       0
  5176.1     .11       0    7872     .15       0 10117.8    .125       0
 10823.1     .11       0 11620.6     .17       0 12071.7     .17       0
 12445.2     .11       0
#XS Ineff= 3 ,-1
    -227  2951.5  123.88   -2025  -818.6  130.07  9586.6   12805  136.19
Permanent Ineff=
       F       F       F
Bank Sta=4832.48,5074.3
XS Rating Curve= 0 ,0
Exp/Cntr=0.3,0.1

Type RM Length L Ch R = 1 ,240239  ,628,628,628
BEGIN DESCRIPTION:
WFSJ Main 239.0
END DESCRIPTION:
XS GIS Cut Line= 6
      3835358.09     10098077.31      3835283.44     10094579.09
      3835556.88     10087274.41      3835231.36     10085425.45
      3835214.86      10081228.4      3831921.76     10078677.22
#Sta/Elev= 30
 -6417.1  143.36 -6134.8  140.94 -5610.1  136.43 -4654.4  132.85 -3764.8  132.85
 -2296.9  128.79 -1899.3  118.56 -1412.6  130.52  -921.3  123.31    3403  113.49
  3744.5  123.62  3954.2  114.02 4840.72  112.94  4998.2   101.2  5207.4  113.39
  6160.5  116.17  7593.5   127.8  7833.5  115.67  7983.5  118.63  8103.5   138.8
  8203.5  137.43  8323.5  113.65  8603.5  126.96    9540  126.94  9940.8  127.97
 10278.3  127.08 11616.9  125.91 12603.2  131.27 13881.3  133.02 14631.9  143.32
#Mann= 19 ,-1 , 0
 -6417.1    .125       0 -6134.8    .125       0 -5610.1     .15       0
 -4654.4    .125       0 -3764.8     .11       0 -2296.9    .125       0
 -1412.6    .125       0  -921.3     .11       0    3403    .125       0
  3954.2     .12       0 4840.72     .08       0  5207.4     .12       0
  6160.5     .11       0    9540     .15       0  9940.8    .125       0
 10278.3     .11       0 11616.9     .15       0 12603.2     .17       0
 13881.3     .17       0
#XS Ineff= 4 ,-1
  8103.5   14505   138.8  7723.5    8103  127.53   -1175  3744.5  123.62
   -3100 -1412.6  130.52
Permanent Ineff=
       F       F       F       F
Bank Sta=4840.72,5207.4
XS Rating Curve= 0 ,0
Exp/Cntr=0.3,0.1

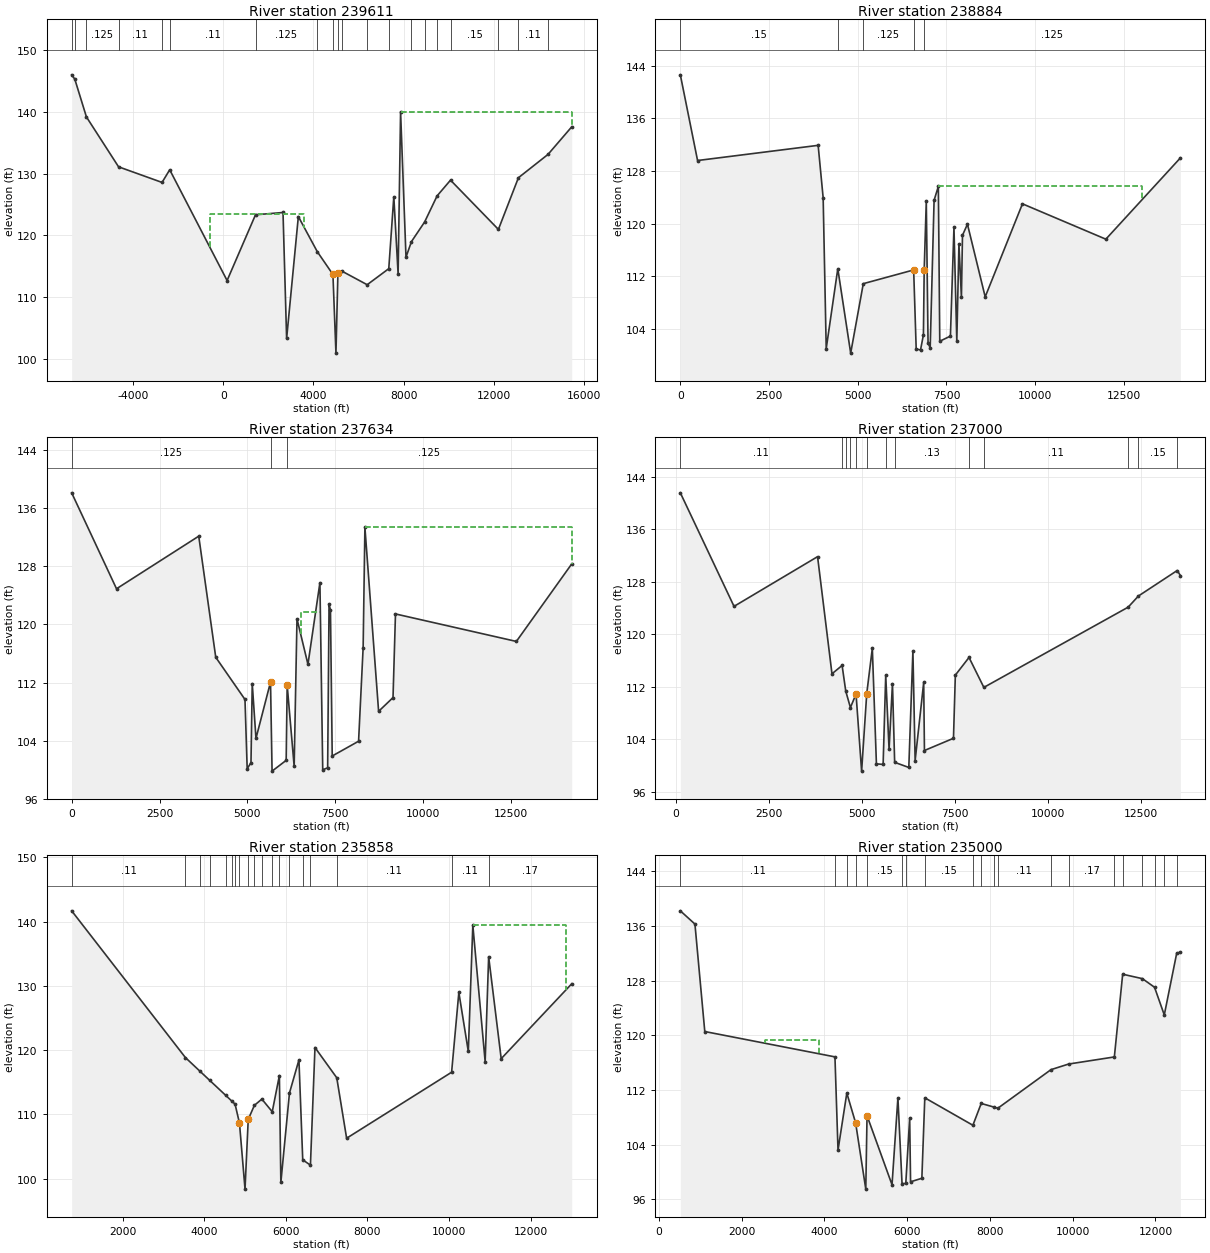
Type RM Length L Ch R = 1 ,239611  ,727,727,727
BEGIN DESCRIPTION:
WFSJ Main 238.0
END DESCRIPTION:
XS GIS Cut Line= 6
      3835540.39     10098181.51      3835843.34     10094592.12
      3836077.71     10087339.51      3835804.27     10084774.41
      3835975.84      10080407.8      3832063.86     10078441.96
#Sta/Elev= 30
 -6726.8     146 -6588.2   145.3 -6072.1  139.18 -4646.8   131.1 -2717.1  128.57
 -2377.2  130.62   168.8  112.68  1429.6  123.33  2649.7   123.7  2809.8  103.29
    3330  123.04  4170.8  117.35  4864.4  113.66  4998.2  100.92  5085.7  113.89
    5263   114.2  6383.6     112  7341.7   114.6  7565.5  126.26  7755.6  113.77
  7865.7  140.02  8105.9  116.46  8347.2  118.98  8933.2  122.17  9485.7  126.39
 10081.2  128.94 12205.4  120.96 13093.4  129.33 14406.7  133.11 15459.6  137.58
#Mann= 20 ,-1 , 0
 -6726.8    .125       0 -6588.2     .15       0 -6072.1    .125       0
 -4646.8     .11       0 -2717.1    .125       0 -2377.2     .11       0
  1429.6    .125       0  4170.8     .11       0  4864.4     .07       0
  5085.7     .11       0    5263     .11       0  6383.6     .11       0
  7341.7     .15       0  8347.2     .11       0  8933.2    .125       0
  9485.7     .15       0 10081.2     .15       0 12205.4     .11       0
 13093.4     .11       0 14406.7     .17       0
#XS Ineff= 3 ,-1
    -600  3600.9  123.47  7565.5    7865  126.26  7865.7 15459.6  140.02
Permanent Ineff=
       F       F       F
Bank Sta=4864.4,5085.7
XS Rating Curve= 0 ,0
Exp/Cntr=0.3,0.1

Type RM Length L Ch R = 1 ,238884  ,1250,1250,1250
XS GIS Cut Line= 6
      3838815.12     10092642.79      3837640.86     10089039.06
      3836425.58      10088062.5      3836574.72     10087064.54
       3836676.3     10086534.86      3836775.19     10079339.84
#Sta/Elev= 30
       0  142.64   485.6   129.6  3883.9  131.91    4025  123.93  4111.3  100.98
  4437.7  113.14  4800.9  100.29  5156.1  110.86  6575.6  112.95  6646.9  100.94
  6768.6  100.76  6850.6  103.07 6872.65  112.99  6931.4   123.4  6981.4  101.84
  7041.4  101.09  7151.4  123.55  7271.4  125.66  7311.4   102.1  7611.5  102.88
  7711.5  119.43  7791.5  102.07  7851.5   116.9  7921.5  108.78  7951.5  118.22
  8091.5  119.91  8591.6  108.85  9641.7  123.01 11991.9  117.63 14093.3     130
#Mann= 5 ,-1 , 0
       0     .15       0  4437.7    .125       0  5156.1    .125       0
  6575.6     .08       0 6872.65    .125       0
#XS Ineff= 2 ,-1
  6931.4  7271.3   123.4  7271.4   13005  125.66
Permanent Ineff=
       F       F
Bank Sta=6575.6,6872.65
XS Rating Curve= 0 ,0
Exp/Cntr=0.3,0.1

Type RM Length L Ch R = 1 ,237634  ,634,634,634
XS GIS Cut Line= 6
      3839199.79     10092449.24      3837409.43     10088423.63
      3836526.81     10087766.08      3837079.82     10087445.14
      3836917.49     10086599.22      3836866.89       10079385.
#Sta/Elev= 30
       0  138.08  1276.1  124.89  3615.7  132.12  4099.7  115.47  4931.5  109.67
    4994  100.15  5102.4  100.98  5137.9  111.86  5244.2  104.32  5658.1  112.06
  5702.2   99.82  6103.7   101.3  6132.1  111.62    6331  100.48  6411.4  120.75
  6723.2   114.5  7063.8  125.73  7143.8     100  7283.8  100.28  7323.8  122.77
  7363.8  121.96  7413.8   101.9  8163.8  103.93  8293.8  116.81  8343.8  133.33
  8733.9  108.04  9143.9  109.93  9213.9  121.43 12653.9  117.65 14229.5  128.31
#Mann= 3 , 0 , 0
       0    .125       0  5658.1     .08       0  6132.1    .125       0
#XS Ineff= 3 ,-1
  8343.8 14229.5  133.33  7063.8  8343.7  125.73  6517.2  7063.7  121.72
Permanent Ineff=
       F       F       F
Bank Sta=5658.1,6132.1
XS Rating Curve= 0 ,0
Exp/Cntr=0.3,0.1

Type RM Length L Ch R = 1 ,237000  ,1142,1142,1142
BEGIN DESCRIPTION:
WFSJ Main 236.0
END DESCRIPTION:
XS GIS Cut Line= 3
      3839487.86     10092295.55      3837245.54     10087966.86
      3836905.42     10079405.51
#Sta/Elev= 30
     125  141.56  1568.4  124.27  3814.2  131.84  4201.4     114  4473.7  115.27
    4572  111.36    4697  108.86  4848.4  110.92  4998.2   99.18  5135.9  110.98
    5286  117.89  5396.1  100.29  5576.4   100.2  5646.3  113.76  5736.4  102.49
  5827.5   112.5  5886.4  100.52  6266.8   99.74  6376.9  117.48  6436.9  100.79
  6667.1  112.68  6687.1  102.32  7467.7  104.18  7517.8   113.8  7885.2  116.49
    8284  111.93 12163.9  124.15 12439.8  125.85 13481.8  129.73 13568.1  128.97
#Mann= 13 ,-1 , 0
     125     .11       0  4473.7     .11       0    4572     .14       0
    4697     .15       0  4848.4    .085       0  5135.9     .15       0
  5646.3     .13       0  5886.4     .13       0  7885.2     .15       0
    8284     .11       0 12163.9    .125       0 12439.8     .15       0
 13481.8     .17       0
Bank Sta=4848.4,5135.9
XS Rating Curve= 0 ,0
Exp/Cntr=0.3,0.1

Type RM Length L Ch R = 1 ,235858  ,858,858,858
BEGIN DESCRIPTION:
WFSJ Main 235.0
END DESCRIPTION:
XS GIS Cut Line= 3
      3839939.26     10091193.69      3837988.66     10087297.74
      3836988.05     10079454.69
#Sta/Elev= 30
     747  141.67  3535.6  118.84    3896  116.69  4129.7   115.3  4526.8  112.94
  4680.8  112.02  4753.6  111.59 4861.89  108.64  4998.2   98.36 5076.92  109.21
  5227.8   111.4 5411.12  112.37  5665.9   110.4  5840.8  116.04  5876.9    99.4
  6088.2  113.32  6320.4  118.47  6413.6  102.92  6602.3  102.09  6713.6   120.4
  7247.9  115.69  7489.8  106.28 10064.4  116.55   10242  128.97 10473.8  119.79
 10584.7  139.43 10887.1  118.19 10972.8  134.54 11280.3  118.66 13010.6  130.32
#Mann= 19 ,-1 , 0
     747     .11       0  3535.6     .11       0    3896     .17       0
  4129.7     .15       0  4526.8     .15       0  4680.8     .15       0
  4753.6     .15       0 4861.89     .09       0 5076.92     .15       0
  5227.8     .15       0 5411.12     .13       0  5665.9     .11       0
  5840.8     .15       0  6088.2     .11       0  6413.6     .11       0
  6602.3     .15       0  7247.9     .11       0 10064.4     .11       0
 10972.8     .17       0
#XS Ineff= 1 ,-1
 10584.7 12873.1  139.43
Permanent Ineff=
       F
Bank Sta=4861.89,5076.92
XS Rating Curve= 0 ,0
Exp/Cntr=0.3,0.1

Type RM Length L Ch R = 1 ,235000  ,2000,2000,2000
BEGIN DESCRIPTION:
WFSJ Main 234.0
END DESCRIPTION:
XS GIS Cut Line= 3
      3840617.85     10090811.07      3838471.48     10086873.58
      3837139.78     10079388.11
#Sta/Elev= 30
   515.5  138.23   868.6  136.29  1106.5  120.56  4252.8  116.85  4326.9   103.2
  4539.5  111.55  4752.3  107.19  4998.2   97.49 5028.24  108.24  5632.3   98.13
  5774.5  110.86  5874.4    98.3  5964.9   98.32  6058.9  107.86  6080.6   98.56
  6353.4   99.08  6424.5  110.86    7587  106.84  7788.2  110.03  8089.9  109.51
  8189.7  109.33  9474.4  114.98  9900.1   115.8 11006.3  116.84 11207.5  128.95
 11684.3   128.3 11977.6  127.04 12213.2  122.99 12514.9  132.07   12603  132.14
#Mann= 20 ,-1 , 0
   515.5     .11       0  4252.8     .15       0  4539.5     .15       0
  4752.3     .09       0 5028.24     .15       0  5874.4     .11       0
  5964.9     .15       0  6424.5     .15       0    7587     .11       0
  7788.2     .17       0  8089.9     .15       0  8189.7     .11       0
  9474.4     .15       0  9900.1     .17       0 11006.3     .11       0
 11207.5     .17       0 11684.3     .11       0 11977.6    .125       0
 12213.2     .11       0 12514.9     .17       0
#XS Ineff= 1 ,-1
    2550  3869.3  119.37
Permanent Ineff=
       F
Bank Sta=4752.3,5028.24
XS Rating Curve= 0 ,0
Exp/Cntr=0.3,0.1

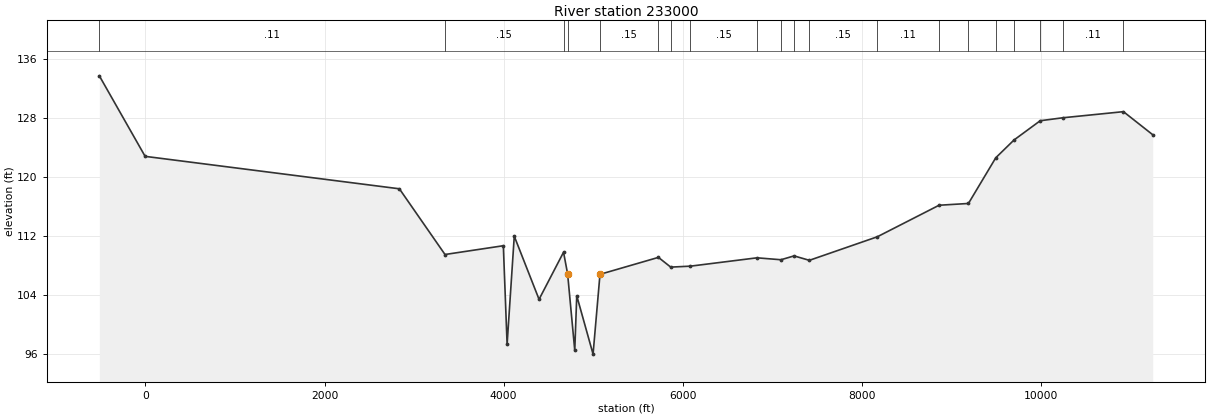
Type RM Length L Ch R = 1 ,233000  ,1000,1000,1000
BEGIN DESCRIPTION:
WFSJ Main 232.0
END DESCRIPTION:
XS GIS Cut Line= 3
      3840779.09       10090720.      3839105.77     10085464.67
      3837700.98     10079376.33
#Sta/Elev= 30
  -515.3  133.73    -3.9  122.81  2835.4  118.41  3344.8   109.5  3996.3  110.69
  4038.3   97.32  4118.3  111.98  4395.1  103.42  4668.6  109.81  4714.1  106.87
  4793.9   96.49    4816  103.91  4998.2   95.99  5075.5  106.81  5728.2  109.11
  5865.4  107.79  6086.1  107.92  6828.8  109.05  7096.2  108.79  7243.1  109.31
  7413.6  108.71  8171.9   111.9  8862.1  116.18  9190.1  116.42  9495.5  122.62
  9699.2  125.03  9991.8  127.64 10242.7  128.04 10921.1  128.87 11248.3  125.74
#Mann= 20 ,-1 , 0
  -515.3     .11       0  3344.8     .15       0  4668.6     .17       0
  4714.1     .09       0  5075.5     .15       0  5728.2     .15       0
  5865.4     .11       0  6086.1     .15       0  6828.8     .11       0
  7096.2     .15       0  7243.1     .11       0  7413.6     .15       0
  8171.9     .11       0  8862.1     .17       0  9190.1     .17       0
  9495.5     .11       0  9699.2     .17       0  9991.8     .17       0
 10242.7     .11       0 10921.1    .125       0
#XS Ineff= 1 ,-1
    1595  2835.4  118.41
Permanent Ineff=
       F
Bank Sta=4714.1,5075.5
XS Rating Curve= 0 ,0
Exp/Cntr=0.3,0.1