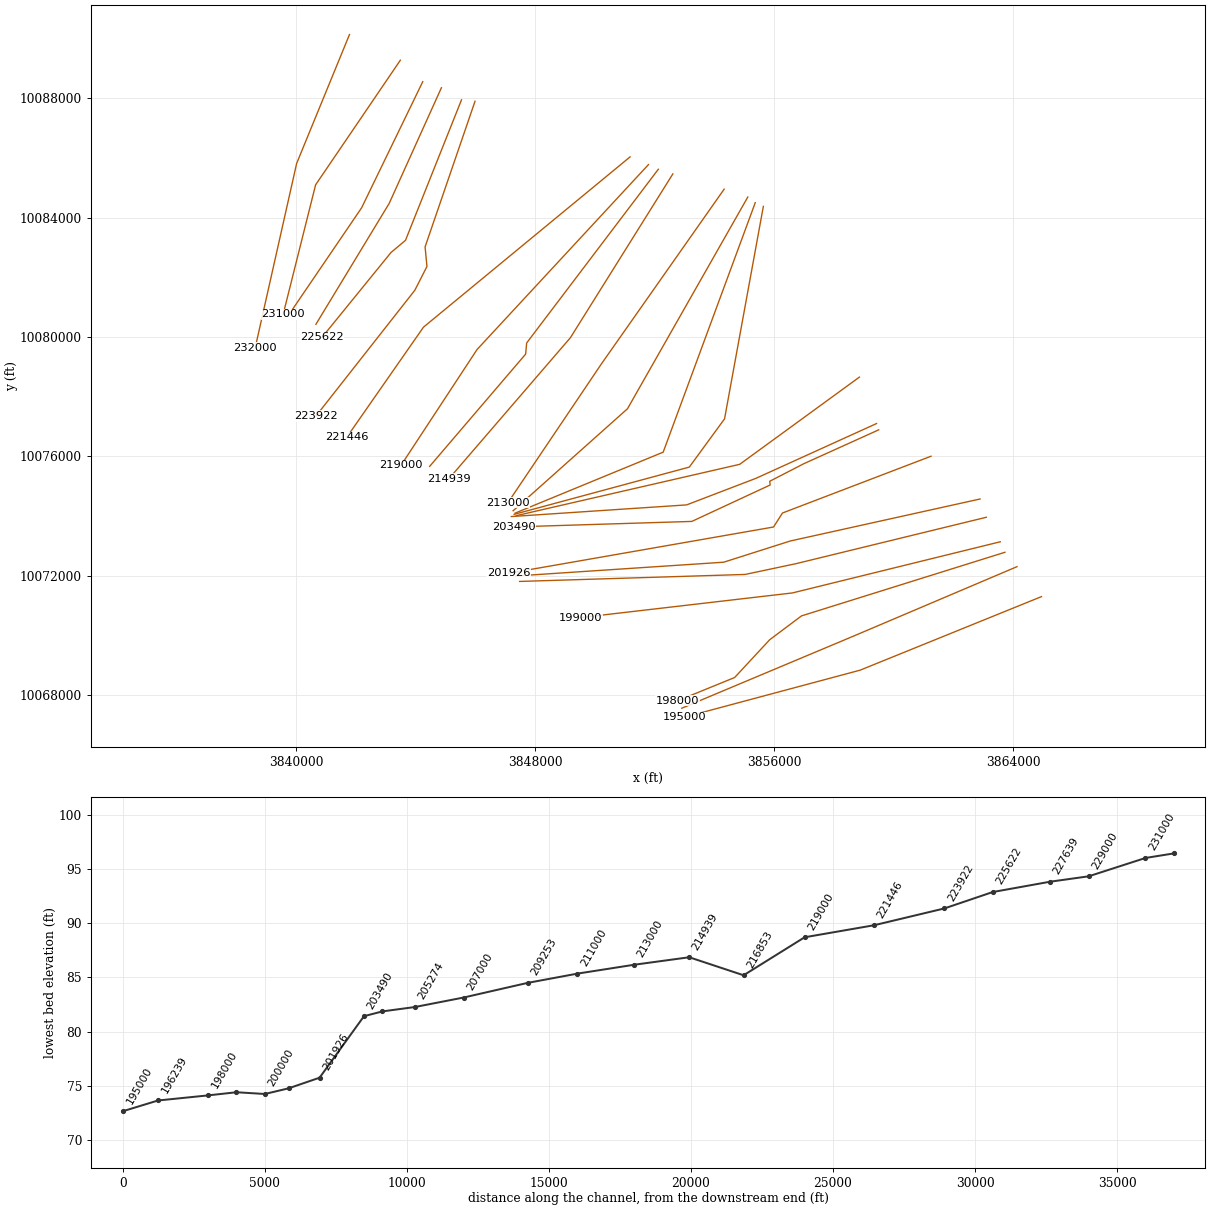
HEC-RAS study WFSJ Main.prj: WFSJ Main Base Level Engineering

--- WFSJ Main.g01 (geometry) --- (continued)

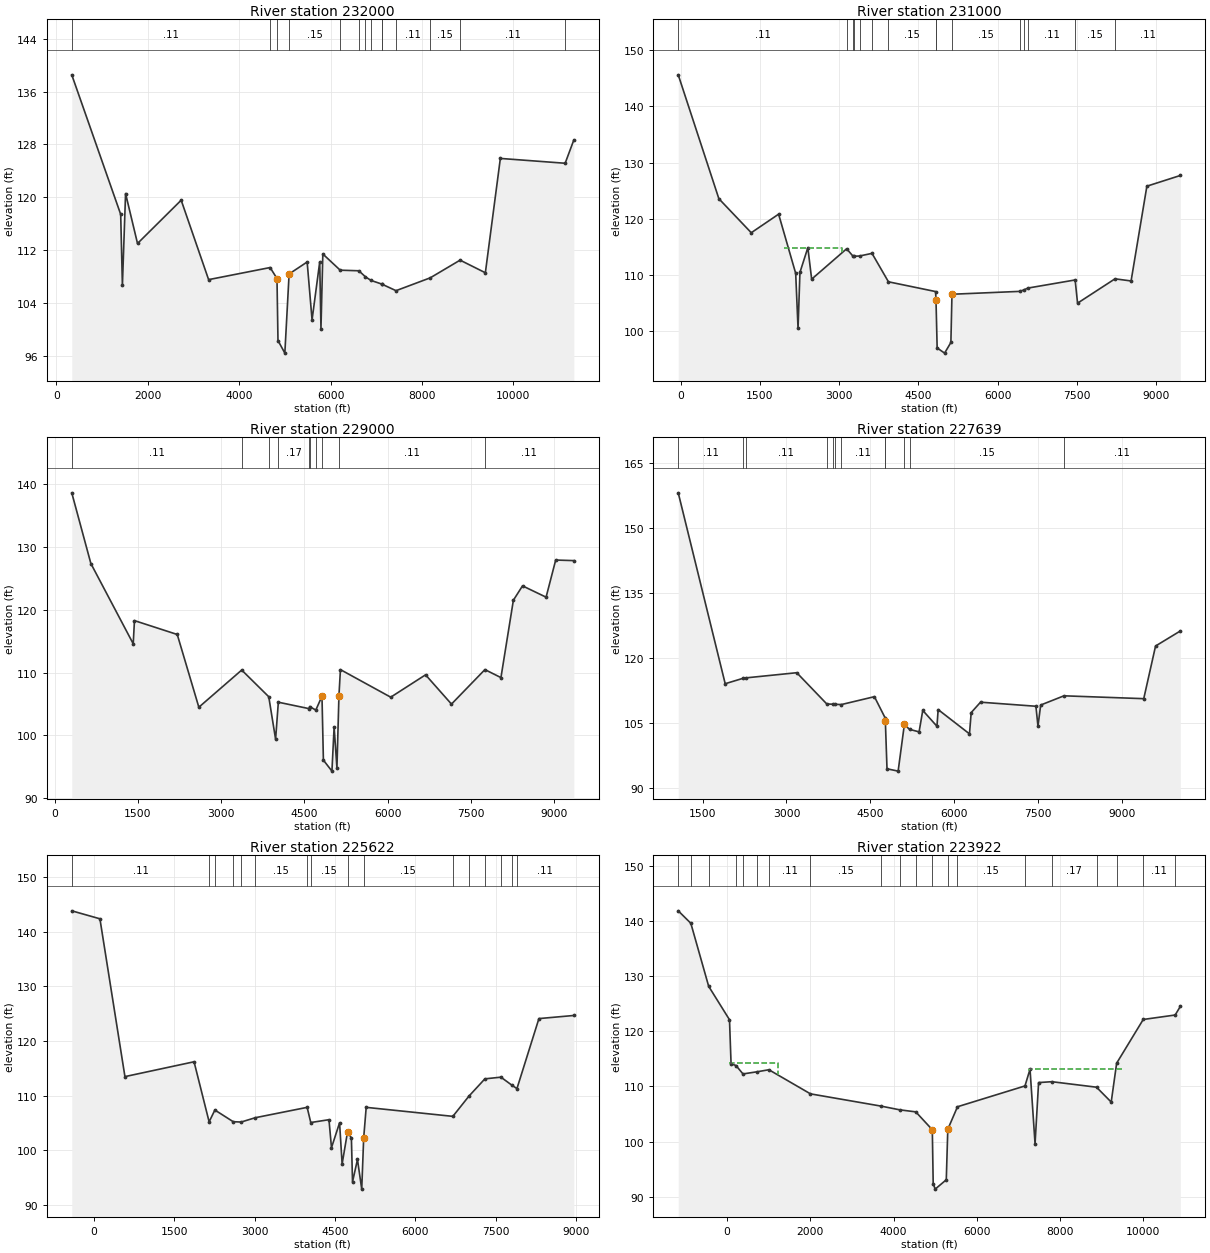
Type RM Length L Ch R = 1 ,232000  ,1000,1000,1000
BEGIN DESCRIPTION:
WFSJ Main 231.0
END DESCRIPTION:
XS GIS Cut Line= 3
      3841779.09     10090126.27      3840009.62     10085810.43
      3838622.84     10079641.89
#Sta/Elev= 30
   335.5  138.54    1406  117.43  1443.5  106.67  1512.8  120.58  1774.3  113.02
  2729.7  119.57  3330.1  107.55  4675.9  109.38  4826.4  107.72    4848   98.34
  4998.2   96.43  5091.6  108.41  5486.5  110.22  5593.8  101.46  5761.6  110.24
  5788.6  100.15  5829.6  111.43  6209.7  108.98  6617.8  108.89  6761.4  107.98
    6884  107.43  7115.3  106.89  7121.2  106.87  7431.2  105.88  8179.2  107.82
  8833.4   110.5  9386.2  108.59  9714.2  125.89 11132.3  125.16 11322.5  128.69
#Mann= 14 ,-1 , 0
   335.5     .11       0  4675.9     .15       0  4826.4     .09       0
  5091.6     .15       0  6209.7     .11       0  6617.8     .15       0
  6761.4     .11       0    6884     .15       0  7115.3     .11       0
  7121.2     .15       0  7431.2     .11       0  8179.2     .15       0
  8833.4     .11       0 11132.3    .125       0
#XS Ineff= 1 ,-1
     830  2729.7  119.57
Permanent Ineff=
       F
Bank Sta=4826.4,5091.6
XS Rating Curve= 0 ,0
Exp/Cntr=0.3,0.1

Type RM Length L Ch R = 1 ,231000  ,2000,2000,2000
BEGIN DESCRIPTION:
WFSJ Main 230.0
END DESCRIPTION:
XS GIS Cut Line= 3
      3843482.23     10089266.93      3840644.78     10085094.76
      3839560.36     10080766.96
#Sta/Elev= 30
   -45.6  145.64   723.7  123.55  1337.2  117.48  1855.1  120.79  2178.4  110.24
    2223  100.44  2259.1  110.41  2408.8  114.82  2480.7   109.2  3143.4  114.62
  3265.5  113.28  3291.4  113.29  3387.6  113.33  3623.6   113.8  3934.8  108.73
  4827.4  106.99  4835.2  105.54  4857.2   96.93  4998.2   96.01  5117.2   97.91
  5137.8  106.51  6416.7  107.02  6493.5  107.26  6575.1  107.61  7470.1  109.06
  7515.9  104.92  8224.8  109.26  8529.5  108.88  8828.5  125.78  9461.6  127.69
#Mann= 15 ,-1 , 0
   -45.6     .11       0  3143.4    .125       0  3265.5     .11       0
  3291.4    .125       0  3387.6     .11       0  3623.6     .17       0
  3934.8     .15       0  4827.4     .12       0  4835.2     .09       0
  5137.8     .15       0  6416.7     .11       0  6493.5     .15       0
  6575.1     .11       0  7470.1     .15       0  8224.8     .11       0
#XS Ineff= 1 ,-1
    1960  3049.4  114.81
Permanent Ineff=
       F
Bank Sta=4835.2,5137.8
XS Rating Curve= 0 ,0
Exp/Cntr=0.3,0.1

Type RM Length L Ch R = 1 ,229000  ,1361,1361,1361
BEGIN DESCRIPTION:
WFSJ Main 228.0
END DESCRIPTION:
XS GIS Cut Line= 3
      3844232.23     10088548.18      3842185.14      10084325.3
      3839732.55     10080720.52
#Sta/Elev= 30
   307.1  138.62   651.7  127.36  1415.2  114.59  1437.4  118.28  2209.1  116.07
  2598.4  104.49  3371.2  110.41  3859.1  106.16  3982.3    99.4  4031.8  105.29
  4589.1  104.26  4595.4   104.6  4707.3  104.04  4818.7  106.25  4844.2   96.07
  4998.2   94.32  5037.5  101.35  5088.3   94.82 5124.27  106.29  5151.3  110.48
  6058.2  106.09  6686.3  109.65  7153.5  104.99  7756.5  110.48  8045.5  109.21
  8269.9  121.53  8434.6  123.81  8859.5  122.01  9032.8  127.92    9360  127.83
#Mann= 10 ,-1 , 0
   307.1     .11       0  3371.2     .17       0  3859.1     .15       0
  4031.8     .17       0  4589.1     .15       0  4595.4     .17       0
  4707.3     .11       0  4818.7     .07       0 5124.27     .11       0
  7756.5     .11       0
Bank Sta=4818.7,5124.27
XS Rating Curve= 0 ,0
Exp/Cntr=0.3,0.1

Type RM Length L Ch R = 1 ,227639  ,2017,2017,2017
BEGIN DESCRIPTION:
WFSJ Main 227.0
END DESCRIPTION:
XS GIS Cut Line= 3
      3844857.23     10088345.05      3843107.22     10084470.05
      3840654.97     10080424.61
#Sta/Elev= 30
    1064  158.04  1904.2  113.99  2231.5  115.27  2275.7  115.34  3184.5  116.53
  3722.3  109.31  3832.1  109.26  3864.7  109.24  3982.2  109.18  4573.7     111
 4764.04106.1414  4769.6  105.32    4799   94.36  4998.2   93.82  5109.8  104.59
  5201.6  103.46  5373.1  102.88  5438.7  107.83  5692.8  104.17  5714.1  108.02
  6274.5  102.42  6305.4  107.33  6472.3  109.73    7463  108.79  7499.9  104.18
  7548.4  109.07  7965.1   111.2  9392.3  110.54  9603.7  122.69 10046.5  126.16
#Mann= 12 ,-1 , 0
    1064     .11       0  2231.5     .15       0  2275.7     .11       0
  3722.3     .15       0  3832.1     .11       0  3864.7     .15       0
  3982.2     .11       0 4764.04     .08       0  4769.6     .06       0
  5109.8     .11       0  5201.6     .15       0  7965.1     .11       0
Bank Sta=4769.6,5109.8
XS Rating Curve= 0 ,0
Exp/Cntr=0.3,0.1

Type RM Length L Ch R = 1 ,225622  ,1700,1700,1700
BEGIN DESCRIPTION:
WFSJ Main 225.0
END DESCRIPTION:
XS GIS Cut Line= 4
      3845529.12     10087938.83       3843654.1     10083235.67
      3843169.72     10082829.42      3840857.38     10079985.86
#Sta/Elev= 30
  -407.7  143.85   117.1  142.39   583.5  113.48  1872.1   116.2    2153   105.2
  2260.5  107.36  2602.5  105.22  2750.3  105.16    3013  105.95  3980.5  107.85
    4048  105.07  4387.3  105.59  4434.3  100.46    4585  105.02  4632.6   97.48
    4734  103.39  4805.5  102.23  4826.4   94.19  4918.7    98.3  4998.2   92.87
 5034.53  102.25  5081.4  107.85  6696.8   106.2  6995.5  109.89  7294.2  113.07
    7593  113.38  7790.8  111.96  7891.7  111.28  8301.5  124.11  8952.7  124.68
#Mann= 16 ,-1 , 0
  -407.7     .11       0    2153     .15       0  2260.5     .11       0
  2602.5     .15       0  2750.3     .11       0    3013     .15       0
  3980.5     .11       0    4048     .15       0    4734     .07       0
 5034.53     .15       0  6696.8     .17       0  6995.5     .11       0
  7294.2     .17       0    7593     .11       0  7790.8     .17       0
  7891.7     .11       0
#XS Ineff= 1 ,-1
     400  1872.1   116.2
Permanent Ineff=
       F
Bank Sta=4734,5034.53
XS Rating Curve= 0 ,0
Exp/Cntr=0.3,0.1

Type RM Length L Ch R = 1 ,223922  ,2476,2476,2476
BEGIN DESCRIPTION:
WFSJ Main 223.0
END DESCRIPTION:
XS GIS Cut Line= 5
      3845982.23     10087891.95      3844310.35     10083016.92
      3844372.85     10082360.67       3843966.6      10081563.8
       3840655.5       10077352.
#Sta/Elev= 30
 -1176.1   141.9  -873.5  139.64  -444.5  128.19    55.7  122.12    93.4  114.12
   211.1  113.81   379.9  112.28   727.1  112.68  1002.4  113.04  2001.8  108.66
  3701.7  106.43  4146.3  105.76  4532.4  105.39 4929.31  102.14  4950.7   92.36
  4998.2   91.36    5265   93.06 5301.55102.2279  5534.4  106.32  7156.2   110.1
  7277.4  113.14  7398.2   99.59  7483.2  110.71    7801  110.87  8874.9  109.87
  9228.3  107.17  9358.9  114.23  9997.9  122.17 10765.6  122.98 10888.8  124.54
#Mann= 20 ,-1 , 0
 -1176.1     .11       0  -873.5     .17       0  -444.5     .11       0
   211.1     .17       0   379.9     .17       0   727.1     .11       0
  1002.4     .11       0  2001.8     .15       0  3701.7     .11       0
  4146.3     .15       0  4532.4     .11       0 4929.31     .06       0
 5301.55     .11       0  5534.4     .15       0  7156.2     .11       0
    7801     .17       0  8874.9     .15       0  9358.9     .11       0
  9997.9     .11       0 10765.6     .11       0
#XS Ineff= 2 ,-1
  7263.5    9530  113.16      52  1228.2   114.3
Permanent Ineff=
       F       F
Bank Sta=4929.31,5301.55
XS Rating Curve= 0 ,0
Exp/Cntr=0.3,0.1

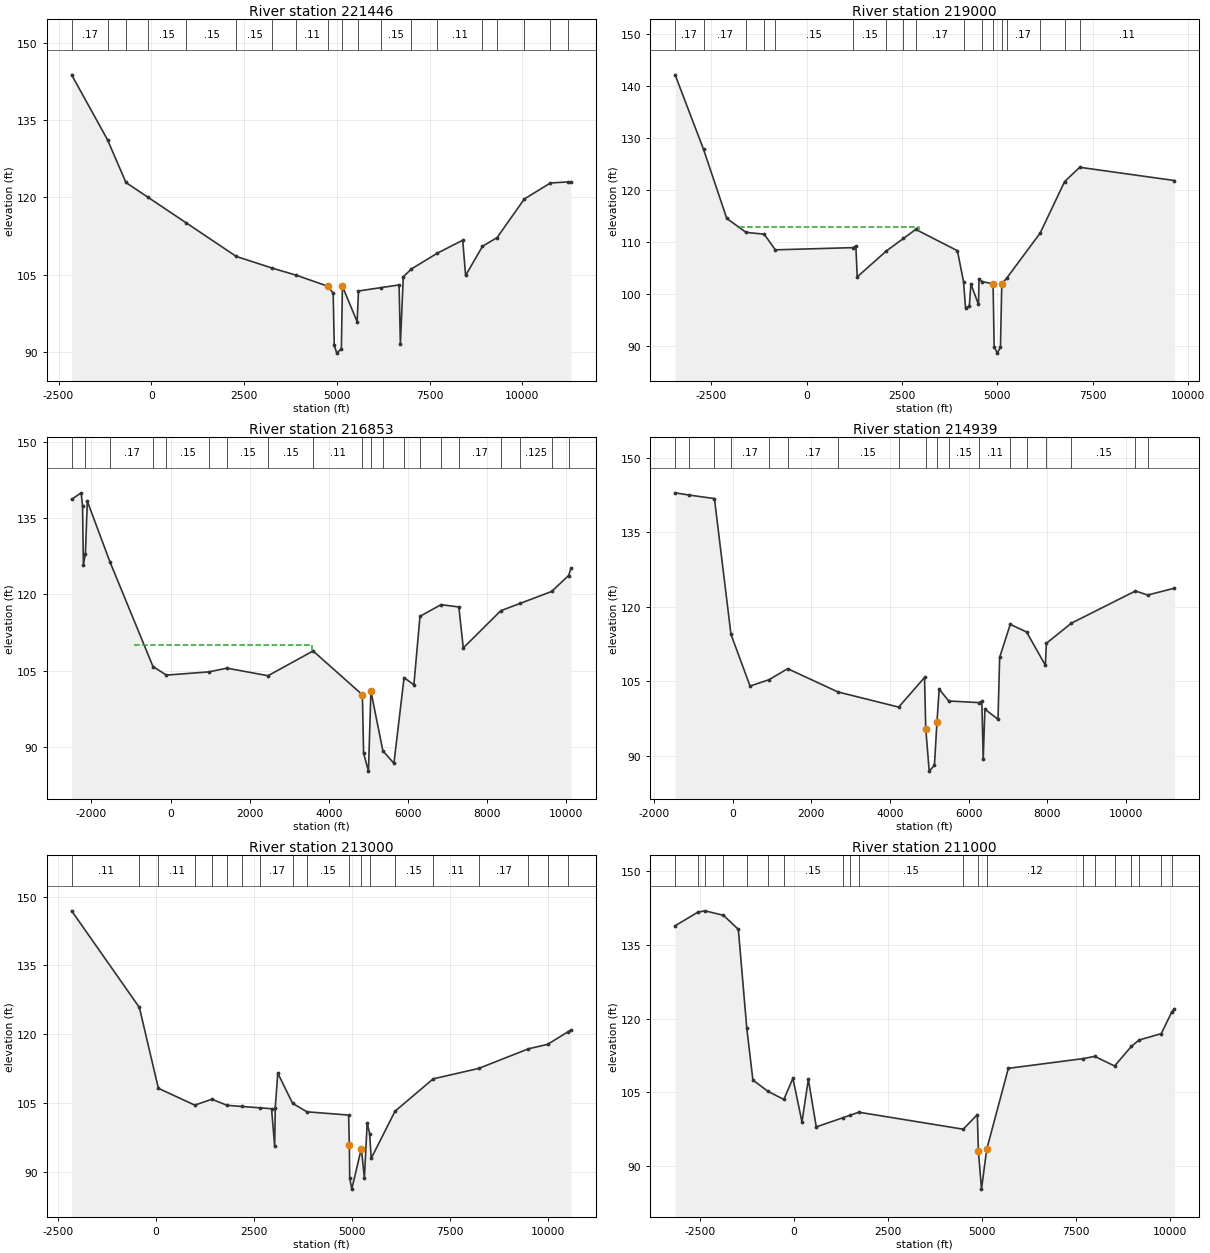
Type RM Length L Ch R = 1 ,221446  ,2446,2446,2446
BEGIN DESCRIPTION:
WFSJ Main 221.0
END DESCRIPTION:
XS GIS Cut Line= 3
      3851173.23      10086029.2      3844256.05     10080328.07
      3841685.61     10076640.22
#Sta/Elev= 30
 -2146.4  143.77 -1179.4  131.18  -683.6   122.9  -100.8  120.09   949.2  115.03
  2291.2  108.56  3266.7  106.28  3902.5  104.93 4752.45   102.8    4903  101.45
  4931.7   91.35  4998.2   89.81  5123.2   90.66  5151.9  102.77  5549.3    95.9
  5584.8  101.86  6190.2  102.51    6679  103.03  6714.2   91.54  6792.4   104.6
  7011.2  106.13  7712.2   109.2  8394.6   111.7  8472.3  104.87  8926.8  110.52
  9321.3  112.22 10055.3   119.7 10758.9   122.8 11232.3  123.01 11312.7  122.95
#Mann= 19 ,-1 , 0
 -2146.4     .17       0 -1179.4     .17       0  -683.6     .11       0
  -100.8     .15       0   949.2     .15       0  2291.2     .15       0
  3266.7     .17       0  3902.5     .11       0 4752.45     .09       0
  5151.9     .15       0  5584.8     .17       0  6190.2     .15       0
  7011.2     .17       0  7712.2     .11       0  8926.8     .17       0
  9321.3     .15       0 10055.3     .11       0 10758.9    .125       0
 11232.3    .125       0
Bank Sta=4752.45,5151.9
XS Rating Curve= 0 ,0
Exp/Cntr=0.3,0.1

Type RM Length L Ch R = 1 ,219000  ,2147,2147,2147
BEGIN DESCRIPTION:
WFSJ Main 219.0
END DESCRIPTION:
XS GIS Cut Line= 3
      3851789.73     10085772.11      3846049.65     10079579.71
      3843503.47     10075700.37
#Sta/Elev= 30
 -3443.6  142.15 -2698.3  127.83 -2090.2  114.57 -1586.3   111.9 -1110.2  111.54
  -817.3  108.54    1211  108.96  1292.3  109.23    1328  103.34  2092.7  108.33
  2539.5  110.73  2861.7  112.46    3953  108.37  4112.8  102.45  4165.6   97.43
  4264.2   97.66  4306.7  101.97  4505.2   98.04  4519.3  102.98    4599  102.44
  4887.3  102.01  4915.6   89.91  4998.2    88.7  5080.7   89.82 5115.74102.0369
  5240.8  103.06  6121.2  111.76  6762.9  121.66  7157.9  124.39  9640.3  121.85
#Mann= 17 ,-1 , 0
 -3443.6     .17       0 -2698.3     .17       0 -1586.3     .15       0
 -1110.2     .11       0  -817.3     .15       0    1211     .15       0
  2092.7     .17       0  2539.5     .11       0  2861.7     .17       0
  4112.8     .15       0    4599     .11       0  4887.3     .07       0
 5115.74     .11       0  5240.8     .17       0  6121.2     .11       0
  6762.9    .125       0  7157.9     .11       0
#XS Ineff= 1 ,-1
   -1750  2948.3  112.92
Permanent Ineff=
       F
Bank Sta=4887.3,5115.74
XS Rating Curve= 0 ,0
Exp/Cntr=0.3,0.1

Type RM Length L Ch R = 1 ,216853  ,1914,1914,1914
BEGIN DESCRIPTION:
WFSJ Main 217.0
END DESCRIPTION:
XS GIS Cut Line= 4
       3852119.6     10085615.87      3847711.62     10079799.91
       3847676.9     10079426.64      3844463.35     10075667.95
#Sta/Elev= 30
 -2501.7   138.7 -2261.1  139.98 -2225.8  137.42 -2204.9  125.77   -2154     128
 -2105.1  138.32 -1530.2  126.33    -446  105.79  -107.1   104.1   971.2  104.74
  1422.7  105.47  2459.7  103.98  3599.8  108.85    4845  100.23  4875.1   88.74
  4998.2    85.2 5060.66  100.93  5362.1   89.21    5642   86.73  5898.1   103.6
  6145.9   102.2  6300.5  115.68  6833.3  117.97  7282.5  117.51    7394  109.44
  8340.7  116.77  8839.5  118.24  9626.2  120.56 10055.6   123.7   10116  125.13
#Mann= 20 ,-1 , 0
 -2501.7     .11       0   -2154     .11       0 -1530.2     .17       0
    -446     .17       0  -107.1     .15       0   971.2     .15       0
  1422.7     .15       0  2459.7     .15       0  3599.8     .11       0
    4845     .07       0 5060.66     .15       0  5362.1     .11       0
  5898.1     .11       0  6300.5     .17       0  6833.3     .15       0
  7282.5     .17       0  8340.7     .11       0  8839.5    .125       0
  9626.2     .11       0 10055.6     .11       0
#XS Ineff= 1 ,-1
    -930  3577.4  110.03
Permanent Ineff=
       F
Bank Sta=4845,5060.66
XS Rating Curve= 0 ,0
Exp/Cntr=0.3,0.1

Type RM Length L Ch R = 1 ,214939  ,1939,1939,1939
BEGIN DESCRIPTION:
WFSJ Main 215.0
END DESCRIPTION:
XS GIS Cut Line= 3
      3852605.72     10085459.63      3849176.86     10079977.41
      3845105.73     10075251.31
#Sta/Elev= 30
 -1466.2  142.93 -1109.3  142.48  -465.7  141.77   -45.1  114.42   440.4     104
   926.8  105.29    1397   107.5  2676.9  102.81  4221.6   99.76  4879.6  105.73
  4910.2   95.38  4998.2   86.86  5131.2   88.03  5194.5   96.68  5251.9  103.37
  5495.8  100.99  6259.4  100.67    6337   100.9  6372.1   89.31  6414.9   99.34
  6748.4   97.31  6790.2  109.78  7059.8  116.43    7476  114.89  7953.1  108.19
  7979.9  112.62  8615.8  116.67 10244.2  123.15 10556.7  122.34 11237.8  123.72
#Mann= 18 ,-1 , 0
 -1466.2     .17       0 -1109.3     .17       0  -465.7     .11       0
   -45.1     .17       0   926.8     .11       0    1397     .17       0
  2676.9     .15       0  4221.6     .17       0  4910.2     .07       0
  5194.5     .17       0  5495.8     .15       0  6259.4     .11       0
  7059.8     .15       0    7476     .17       0  7979.9     .17       0
  8615.8     .15       0 10244.2    .125       0 10556.7    .125       0
Bank Sta=4910.2,5194.5
XS Rating Curve= 0 ,0
Exp/Cntr=0.3,0.1

Type RM Length L Ch R = 1 ,213000  ,2000,2000,2000
BEGIN DESCRIPTION:
WFSJ Main 213.0
END DESCRIPTION:
XS GIS Cut Line= 3
      3854322.64     10084948.48      3850210.22     10079093.76
      3847084.23     10074452.63
#Sta/Elev= 30
 -2154.7  146.89  -425.3  125.81      60  108.17   989.3   104.5  1426.9  105.78
  1813.4  104.46  2201.1   104.2  2661.7   103.9  2950.3  103.71  3029.6   95.51
  3044.4  103.96  3109.1  111.48  3487.1  104.89    3854  103.04  4917.7  102.33
 4936.3795.71989  4945.8    88.6  4998.2   86.17  5242.1   95.03  5320.1    88.6
  5392.1  100.63  5455.1   98.27    5494   92.88    6103  103.17  7076.5  110.23
    8237   112.5  9510.4  116.79  9997.2  117.75 10510.1  120.45 10595.7   120.9
#Mann= 19 ,-1 , 0
 -2154.7     .11       0  -425.3     .17       0      60     .11       0
   989.3     .17       0  1426.9     .17       0  1813.4     .15       0
  2201.1     .15       0  2661.7     .17       0  3487.1     .17       0
    3854     .15       0 4936.37     .07       0  5242.1     .15       0
  5455.1     .17       0    6103     .15       0  7076.5     .11       0
    8237     .17       0  9510.4    .125       0  9997.2    .125       0
 10510.1     .11       0
#XS Ineff= 1 ,-1
    -200  3109.1  111.48
Permanent Ineff=
       F
Bank Sta=4936.37,5242.1
XS Rating Curve= 0 ,0
Exp/Cntr=0.3,0.1

Type RM Length L Ch R = 1 ,211000  ,1747,1747,1747
BEGIN DESCRIPTION:
WFSJ Main 211.0
END DESCRIPTION:
XS GIS Cut Line= 3
      3855115.47     10084685.26      3851087.52     10077597.56
      3847257.87     10074181.39
#Sta/Elev= 30
 -3152.3  138.83 -2544.7  141.61 -2357.6  141.87 -1866.7  140.96 -1470.5  138.11
 -1246.4  118.09 -1082.7   107.5  -684.3  105.22  -259.4  103.56   -18.9  107.86
   222.6   98.99   392.1  107.66   602.6   97.99  1310.4   99.85  1502.4  100.36
  1735.3  100.97  4512.1   97.52  4887.3  100.48 4916.38   93.03  4998.2   85.35
 5136.0693.39973  5712.4  109.88  7706.5  111.86  8010.9  112.31  8538.9  110.36
    8986  114.35  9191.8  115.64  9779.5  116.93 10057.6  121.28 10131.9     122
#Mann= 20 ,-1 , 0
 -3152.3     .11       0 -2544.7     .11       0 -2357.6     .17       0
 -1866.7     .11       0 -1246.4     .11       0  -684.3     .15       0
  -259.4     .15       0  1310.4     .17       0  1502.4     .11       0
  1735.3     .15       0  4512.1     .12       0 4916.38     .07       0
 5136.06     .12       0  7706.5     .17       0  8010.9     .11       0
  8538.9    .125       0    8986     .15       0  9191.8    .125       0
  9779.5     .11       0 10057.6     .11       0
#XS Ineff= 1 ,-1
   -1170   392.1  107.66
Permanent Ineff=
       F
Bank Sta=4916.38,5136.06
XS Rating Curve= 0 ,0
Exp/Cntr=0.3,0.1

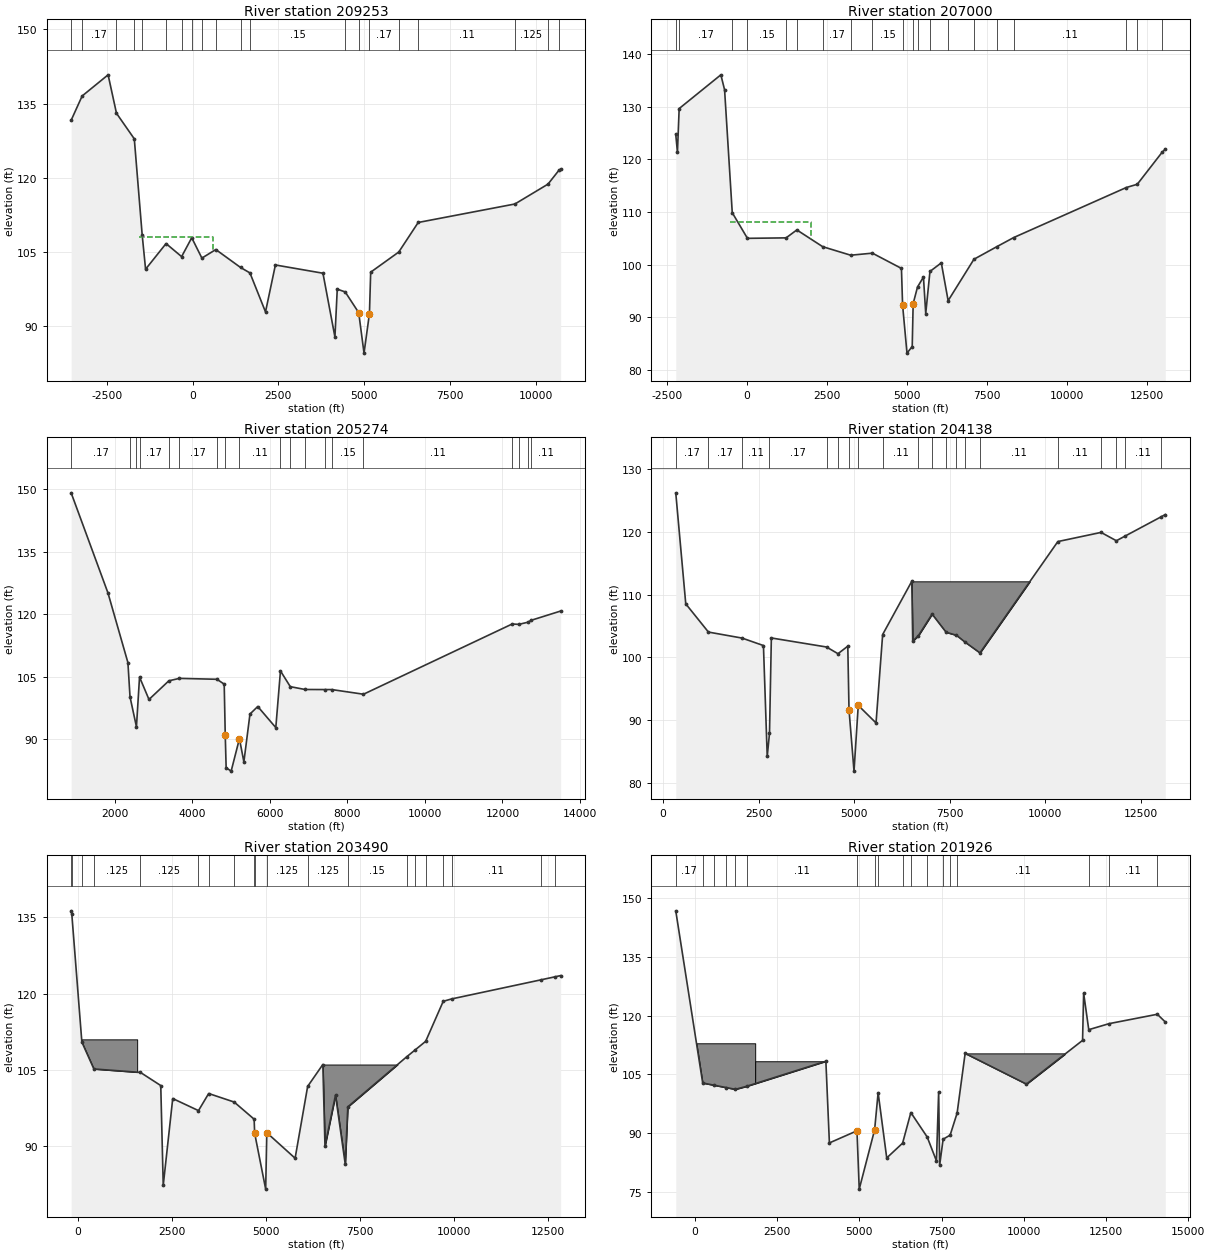
Type RM Length L Ch R = 1 ,209253  ,2253,2253,2253
BEGIN DESCRIPTION:
WFSJ Main 209.0
END DESCRIPTION:
XS GIS Cut Line= 3
      3855365.48     10084497.78      3852282.15      10076143.6
      3847323.85     10074101.95
#Sta/Elev= 30
 -3538.5  131.62 -3217.5  136.54 -2461.2  140.82   -2217  133.04 -1697.6  127.86
 -1468.8  108.49 -1368.8  101.48  -772.2  106.67  -318.8  104.03   -23.5  107.85
   272.3  103.73   677.9  105.46  1398.2  101.84  1673.2  100.73  2126.6   92.84
  2414.9  102.34  3800.9  100.67  4150.1   87.77    4218   97.45  4449.8   96.88
  4843.1   92.69  4998.1    84.5    5156    92.5  5192.3  100.88  6010.6  104.96
  6577.1  110.94  9395.8  114.68 10360.1   118.7 10674.9  121.47 10728.7  121.69
#Mann= 20 ,-1 , 0
 -3538.5     .11       0 -3217.5     .17       0   -2217     .11       0
 -1697.6     .17       0 -1468.8     .15       0  -772.2     .17       0
  -318.8     .15       0   -23.5     .17       0   272.3     .15       0
   677.9     .15       0  1398.2     .11       0  1673.2     .15       0
  4449.8     .17       0  4843.1     .09       0    5156     .17       0
  6010.6     .11       0  6577.1     .11       0  9395.8    .125       0
 10360.1    .125       0 10674.9     .11       0
#XS Ineff= 1 ,-1
   -1550   583.2  108.05
Permanent Ineff=
       F
Bank Sta=4843.1,5156
XS Rating Curve= 0 ,0
Exp/Cntr=0.3,0.1

Type RM Length L Ch R = 1 ,207000  ,1726,1726,1726
BEGIN DESCRIPTION:
WFSJ Main 207.0
END DESCRIPTION:
XS GIS Cut Line= 4
      3855636.32      10084372.8       3854336.8     10077258.52
      3853157.15      10075643.6      3847293.06     10074061.65
#Sta/Elev= 30
   -2232  124.76 -2179.4  121.37 -2125.5  129.68  -821.9   136.1  -705.2  133.25
  -465.6  109.87     9.5  104.99  1218.7  105.08  1553.8  106.59  2362.9   103.4
  3237.9  101.78  3916.5  102.17  4824.6   99.27 4860.97   92.26  4998.1   83.15
  5161.6    84.4    5191   92.56  5326.9   95.73    5513   97.62  5584.1   90.67
    5716   98.69  6071.4  100.32  6284.8   93.13  7091.7  101.01  7808.8  103.41
  8335.4  105.14 11855.8  114.66 12199.3  115.28 12970.6  121.33 13073.6  121.96
#Mann= 20 ,-1 , 0
   -2232    .125       0 -2125.5     .17       0  -465.6     .15       0
     9.5     .15       0  1218.7     .17       0  1553.8     .15       0
  2362.9     .17       0  3237.9     .15       0  3916.5     .15       0
 4860.97     .09       0    5191     .15       0  5326.9     .11       0
    5716     .11       0  6284.8     .15       0  7091.7     .11       0
  7808.8     .15       0  8335.4     .11       0 11855.8     .15       0
 12199.3    .125       0 12970.6     .11       0
#XS Ineff= 1 ,-1
    -550  2008.8   108.1
Permanent Ineff=
       F
Bank Sta=4860.97,5191
XS Rating Curve= 0 ,0
Exp/Cntr=0.3,0.1

Type RM Length L Ch R = 1 ,205274  ,1136,1136,1136
BEGIN DESCRIPTION:
WFSJ Main 205.0
END DESCRIPTION:
XS GIS Cut Line= 3
      3858851.43      10078655.9      3854844.44     10075736.28
      3847362.32     10074017.65
#Sta/Elev= 30
   867.9  149.15  1818.7  125.08  2333.3  108.35  2387.5  100.12  2553.6   92.93
  2633.2  104.87  2877.2   99.49  3389.3  103.97  3659.3  104.56  4632.5  104.34
  4818.7  103.17  4845.7   90.95  4868.8   83.08  4998.1   82.27  5211.9   90.06
  5326.6   84.49  5483.9   95.99  5684.7    97.8  6150.6   92.73    6271  106.35
  6524.7  102.57  6903.8  101.89  7419.6  101.87  7594.5  101.87  8414.1  100.75
 12252.1  117.63 12422.7  117.54 12660.9  118.06 12739.8  118.51 13502.7  120.74
#Mann= 19 ,-1 , 0
   867.9     .17       0  2387.5     .11       0  2553.6     .15       0
  2633.2     .17       0  3389.3     .11       0  3659.3     .17       0
  4632.5     .11       0  4845.7     .06       0  5211.9     .11       0
    6271     .15       0  6524.7     .17       0  6903.8     .15       0
  7419.6     .17       0  7594.5     .15       0  8414.1     .11       0
 12252.1    .125       0 12422.7     .15       0 12660.9    .125       0
 12739.8     .11       0
Bank Sta=4845.7,5211.9
XS Rating Curve= 0 ,0
Exp/Cntr=0.3,0.1

Type RM Length L Ch R = 1 ,204138  ,648,648,648
BEGIN DESCRIPTION:
WFSJ Main 204.0
END DESCRIPTION:
XS GIS Cut Line= 4
      3859426.04     10077101.67      3855389.56     10075267.89
      3853067.51     10074378.14      3847197.27     10073987.51
#Sta/Elev= 30
   335.6  126.24   597.2  108.54    1190  104.04  2071.6  103.08  2629.2  101.89
    2728   84.21  2787.5   87.89  2835.9   103.1  4278.6  101.66    4579  100.59
  4835.3  101.79  4867.3   91.64  4998.1   81.87  5108.9   92.35  5574.1   89.55
  5747.3  103.65    6509  112.13  6533.7  102.61  6679.8  103.44  7040.6   106.9
  7406.7  104.01  7677.9  103.53  7897.9  102.46  8292.3  100.72 10329.6  118.47
 11459.7  119.93 11860.6   118.6 12080.8  119.32 13025.7   122.4   13139  122.77
#Mann= 20 ,-1 , 0
   335.6     .17       0    1190     .17       0  2071.6     .11       0
  2787.5     .17       0  4278.6     .17       0    4579     .15       0
  4867.3     .09       0  5108.9    .125       0  5747.3     .11       0
  6679.8    .125       0  7040.6     .11       0  7406.7    .125       0
  7677.9     .11       0  7897.9     .15       0  8292.3     .11       0
 10329.6     .11       0 11459.7    .125       0 11860.6    .125       0
 12080.8     .11       0 13025.7     .17       0
#Block Obstruct= 1 ,-1
    6509    9950  112.13
Bank Sta=4867.3,5108.9
XS Rating Curve= 0 ,0
Exp/Cntr=0.3,0.1

Type RM Length L Ch R = 1 ,203490  ,1564,1564,1564
BEGIN DESCRIPTION:
WFSJ Main 203.0
END DESCRIPTION:
XS GIS Cut Line= 6
      3859498.83     10076891.05       3856995.4     10075759.13
      3855849.56     10075168.85      3855863.45     10075043.85
      3853241.12     10073824.75      3847284.08     10073640.29
#Sta/Elev= 30
  -173.9   136.3  -155.6   135.6   111.2  110.42   430.4  105.12  1668.8  104.44
  2208.7  101.85  2274.5   82.17  2526.9   99.29  3211.7   96.91  3482.9  100.28
  4160.4    98.6  4691.2   95.22 4704.83   92.46  4998.1   81.43 5027.9592.55892
  5780.6   87.52  6113.9  101.68  6517.7     106  6574.9    89.9  6854.7   99.96
  7113.5   86.36  7181.6   97.65  8745.4  107.51  8955.9  108.78  9251.6  110.57
  9718.6  118.46  9941.6  118.93 12307.4  122.68 12701.7  123.31   12840  123.53
#Mann= 20 ,-1 , 0
  -173.9     .11       0  -155.6    .125       0   111.2    .125       0
   430.4    .125       0  1668.8    .125       0  3211.7     .11       0
  3482.9    .125       0  4160.4    .125       0  4691.2     .15       0
 4704.83     .09       0 5027.95    .125       0  6113.9    .125       0
  7181.6     .15       0  8745.4    .125       0  8955.9     .17       0
  9251.6    .125       0  9718.6    .125       0  9941.6     .11       0
 12307.4     .11       0 12701.7     .17       0
#Block Obstruct= 2 ,-1
      38  1581.7  110.96  6517.7    8560     106
Bank Sta=4704.83,5027.95
XS Rating Curve= 0 ,0
Exp/Cntr=0.3,0.1

Type RM Length L Ch R = 1 ,201926  ,1092,1092,1092
BEGIN DESCRIPTION:
WFSJ Main 202.0
END DESCRIPTION:
XS GIS Cut Line= 4
      3861250.82     10076007.56      3856276.84     10074106.51
      3855977.36     10073637.76      3847111.54     10072088.52
#Sta/Elev= 30
  -579.6  146.71   239.3  102.82   592.7  102.24   956.9  101.65  1231.5   101.2
  1577.9  101.98  3984.1  108.36  4091.2   87.54  4929.7   90.63  4998.1   75.76
 5465.91   90.87  5572.6  100.35  5834.1   83.71  6316.6   87.48  6567.4   95.28
  7064.8   89.04  7345.6   82.96  7412.6  100.55    7443   81.84  7548.2   88.48
  7762.3   89.53  7973.8   95.14  8217.8  110.37 10082.4  102.53 11787.9  113.68
 11820.6  125.72 11975.9  116.41 12595.5  117.95 14060.4  120.34 14301.7  118.38
#Mann= 18 ,-1 , 0
  -579.6     .17       0   239.3     .15       0   592.7     .17       0
   956.9     .17       0  1231.5     .11       0  1577.9     .11       0
  4929.7     .07       0 5465.91     .11       0  5572.6     .15       0
  6316.6     .11       0  6567.4     .15       0  7064.8     .11       0
  7548.2     .15       0  7762.3     .15       0  7973.8     .11       0
 11975.9     .17       0 12595.5     .11       0 14060.4     .15       0
#Block Obstruct= 3 ,-1
  8217.8   11245  110.37     -65  1835.6  112.94    1836  3984.1  108.36
Bank Sta=4929.7,5465.91
XS Rating Curve= 0 ,0
Exp/Cntr=0.3,0.1

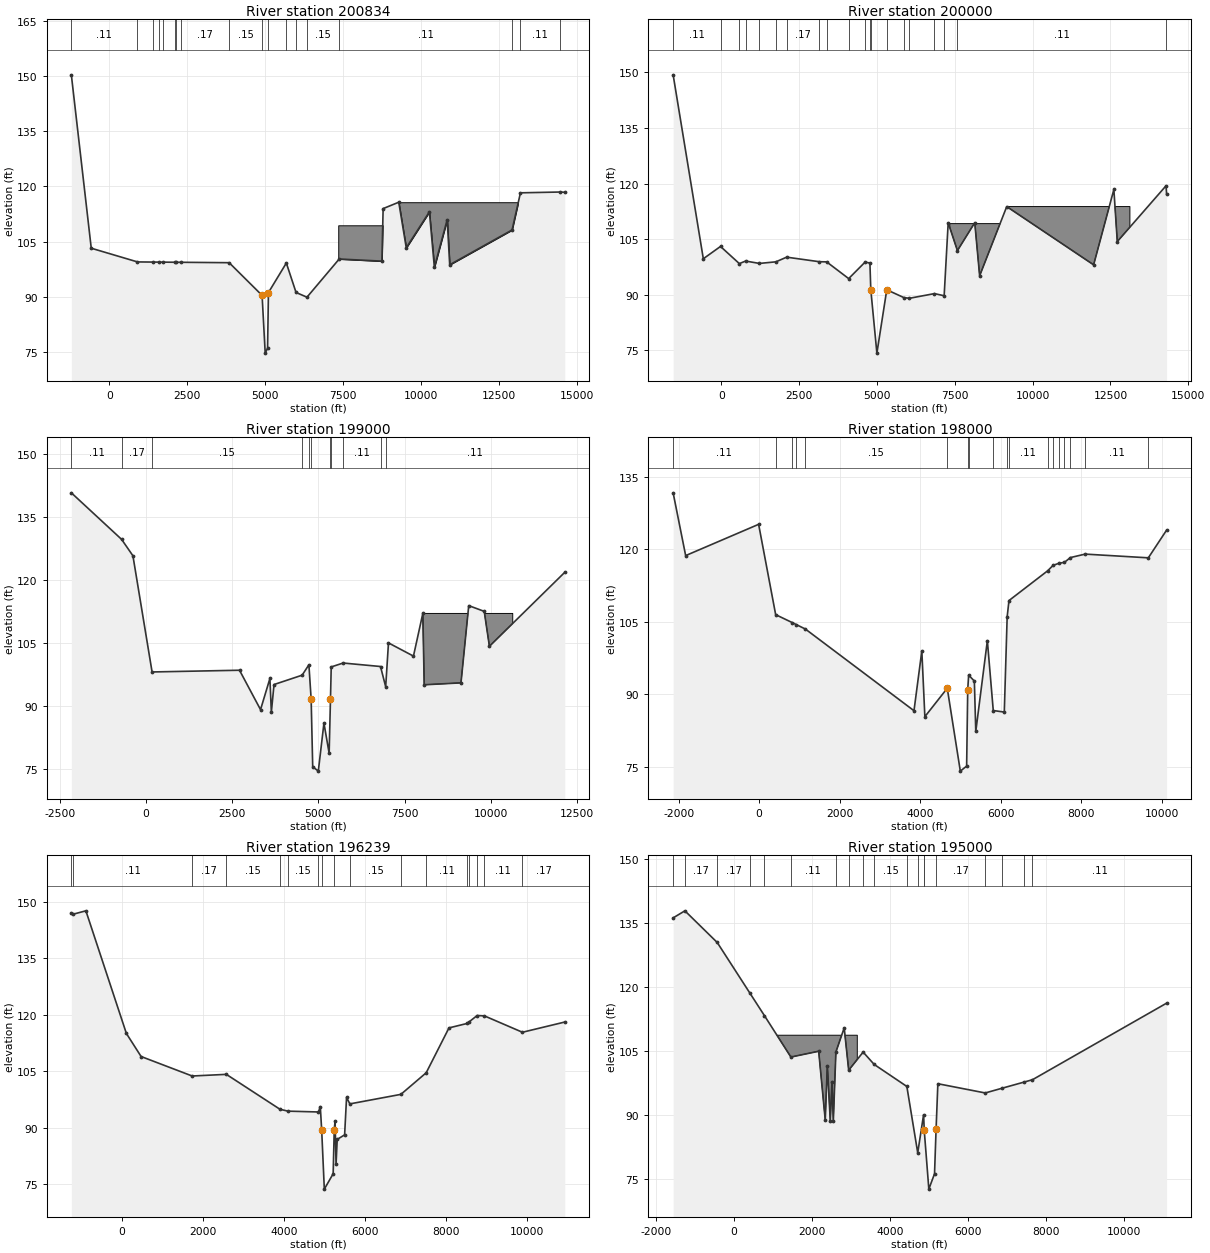
Type RM Length L Ch R = 1 ,200834  ,834,834,834
BEGIN DESCRIPTION:
WFSJ Main 201.0
END DESCRIPTION:
XS GIS Cut Line= 4
       3862891.4     10074575.25      3856537.25     10073169.01
      3854308.11     10072459.15      3847344.56     10071997.13
#Sta/Elev= 30
 -1219.5   150.3  -580.9  103.25   902.3   99.53    1410   99.49  1601.6   99.48
  1735.2   99.47  2108.4   99.44  2128.4   99.44  2288.2   99.43  3842.5   99.32
  4898.6   90.45  4998.1   74.78  5074.2    76.1 5102.29   91.22  5676.1   99.23
  5987.5   91.24  6337.9   89.96  7371.7  100.32  8740.5   99.74  8780.6     114
  9281.7  115.73  9522.3  103.35 10263.9  113.12 10424.2   98.06 10835.1  110.99
 10915.3   98.75 12915.8   108.2 13184.3  118.28 14466.2   118.5 14606.7  118.42
#Mann= 18 ,-1 , 0
 -1219.5     .11       0   902.3     .17       0    1410     .15       0
  1601.6     .17       0  1735.2     .15       0  2108.4     .17       0
  2128.4     .15       0  2288.2     .17       0  3842.5     .15       0
  4898.6     .07       0 5102.29     .12       0  5676.1     .15       0
  5987.5     .11       0  6337.9     .15       0  7371.7     .11       0
 12915.8     .17       0 13184.3     .11       0 14466.2     .17       0
#Block Obstruct= 2 ,-1
  7340.4    9085  109.47  9281.7   13100  115.73
Bank Sta=4898.6,5102.29
XS Rating Curve= 0 ,0
Exp/Cntr=0.3,0.1

Type RM Length L Ch R = 1 ,200000  ,1000,1000,1000
BEGIN DESCRIPTION:
WFSJ Main 200.0
END DESCRIPTION:
XS GIS Cut Line= 4
      3863099.79     10073963.29      3856738.23     10072412.29
      3855026.84     10072049.22      3847474.75     10071814.84
#Sta/Elev= 30
 -1547.9  149.31  -578.4   99.71   -25.9  103.03   578.7    98.4   780.5   99.09
  1224.5   98.45  1752.2   98.88  2099.3  100.14  3149.5   98.91  3383.5   98.87
  4091.5   94.36  4619.9   98.82 4774.02  98.549 4801.97   91.37  4998.1   74.26
  5315.6   91.35  5863.3   89.24  6042.8   89.05  6848.8   90.31    7159   89.73
  7288.7  109.43    7585   101.9  8142.2  109.44  8299.2   95.12  9169.6  113.78
   11961   98.07 12611.3  118.39 12721.3  104.34   14288   119.4 14305.2  117.17
#Mann= 20 ,-1 , 0
 -1547.9     .11       0   -25.9     .17       0   578.7     .15       0
   780.5     .17       0  1224.5     .15       0  1752.2     .15       0
  2099.3     .17       0  3149.5     .17       0  3383.5     .15       0
  4091.5     .17       0  4619.9     .15       0 4774.02     .11       0
 4801.97     .06       0  5315.6     .11       0  5863.3     .11       0
  6042.8     .15       0  6848.8     .11       0    7159     .15       0
    7585     .11       0   14288     .17       0
#Block Obstruct= 2 ,-1
  7338.8    9066  109.18  9169.6   13127  113.78
Bank Sta=4801.97,5315.6
XS Rating Curve= 0 ,0
Exp/Cntr=0.3,0.1

Type RM Length L Ch R = 1 ,199000  ,1000,1000,1000
BEGIN DESCRIPTION:
WFSJ Main 199.0
END DESCRIPTION:
XS GIS Cut Line= 3
      3863568.51     10073142.97      3856608.15     10071429.79
      3849506.01      10070603.9
#Sta/Elev= 30
 -2168.1  140.79  -709.6  129.69  -381.3  125.78   174.8   98.07  2711.6   98.48
  3321.7   89.08  3593.8   96.52  3635.3   88.47    3713   95.07  4528.3    97.3
  4725.1   99.78 4790.34   91.56  4835.5   75.47  4998.1   74.42  5161.4   85.86
  5312.4   78.69 5351.43   91.73  5372.8   99.27  5718.7   100.2  6802.8   99.37
  6953.1   94.54  7033.9     105  7758.8  101.85  8030.6  112.03  8070.8   95.01
    9138   95.47  9362.7  113.89  9812.5  112.52  9962.7  104.19   12150  121.84
#Mann= 11 ,-1 , 0
 -2168.1     .11       0  -709.6     .17       0   174.8     .15       0
  4528.3     .17       0  4725.1     .11       0 4790.34     .07       0
 5351.43     .11       0  5372.8     .15       0  5718.7     .11       0
  6802.8     .15       0  6953.1     .11       0
#Block Obstruct= 1 ,-1
  8030.6   10640  112.03
Bank Sta=4790.34,5351.43
XS Rating Curve= 0 ,0
Exp/Cntr=0.3,0.1

Type RM Length L Ch R = 1 ,198000  ,1761,1761,1761
BEGIN DESCRIPTION:
WFSJ Main 198.0
END DESCRIPTION:
XS GIS Cut Line= 5
      3863724.79     10072791.41      3856913.52     10070661.55
      3855847.15     10069861.72      3854675.27     10068598.69
      3852762.04     10067817.78
#Sta/Elev= 30
 -2136.5  131.72 -1825.4  118.73   -12.8   125.2   410.7  106.51   819.4  104.88
   921.5  104.46  1149.3  103.53  3846.9   86.63  4041.7      99  4117.1    85.4
  4673.5   91.28  4998.1   74.13    5155   75.17  5182.1   91.02    5205   93.99
  5346.6   92.77  5382.1   82.34  5669.6  101.13  5816.4   86.67  6090.4   86.35
  6161.7  106.06  6207.1  109.43  7168.5  115.59  7301.2   116.7  7446.7  117.14
  7585.8  117.34  7731.6  118.32    8099  119.04  9668.8  118.27 10122.4     124
#Mann= 18 ,-1 , 0
 -2136.5     .11       0   410.7     .17       0   819.4     .15       0
   921.5     .17       0  1149.3     .15       0  4673.5     .07       0
  5182.1     .11       0    5205     .15       0  5816.4     .11       0
  6161.7     .17       0  6207.1     .11       0  7168.5     .17       0
  7301.2     .11       0  7446.7    .125       0  7585.8     .11       0
  7731.6    .125       0    8099     .11       0  9668.8     .17       0
Bank Sta=4673.5,5182.1
XS Rating Curve= 0 ,0
Exp/Cntr=0.3,0.1

Type RM Length L Ch R = 1 ,196239  ,1239,1239,1239
BEGIN DESCRIPTION:
WFSJ Main 196.0
END DESCRIPTION:
XS GIS Cut Line= 3
      3864128.43     10072309.64      3858672.67     10069991.92
      3852904.43     10067570.04
#Sta/Elev= 30
 -1248.1     147   -1195  146.77  -888.9  147.64   110.6  115.05   474.6  108.91
  1735.8  103.73  2579.1  104.17  3904.5   94.88  4101.7   94.39  4852.7   94.17
  4898.8   95.59  4933.489.29115  4998.1   73.66  5216.5   77.75 5242.9289.42747
    5264   91.74  5287.8   80.28  5316.9   86.88  5499.5   88.09  5547.1   98.02
  5629.2   96.32  6888.5   98.85  7513.5  104.59  8076.3  116.52  8530.9  117.72
  8570.9   118.1  8771.6  119.81  8949.3  119.72  9889.7  115.36 10935.6  118.08
#Mann= 17 ,-1 , 0
 -1248.1     .17       0   -1195     .11       0  1735.8     .17       0
  2579.1     .15       0  3904.5     .17       0  4101.7     .15       0
  4852.7     .11       0  4933.4     .07       0 5242.92     .15       0
  5629.2     .15       0  6888.5     .17       0  7513.5     .11       0
  8530.9    .125       0  8570.9     .11       0  8771.6    .125       0
  8949.3     .11       0  9889.7     .17       0
Bank Sta=4933.4,5242.92
XS Rating Curve= 0 ,0
Exp/Cntr=0.3,0.1

Type RM Length L Ch R = 1 ,195000  ,1508,1508,1508
BEGIN DESCRIPTION:
WFSJ Main 195.0
END DESCRIPTION:
XS GIS Cut Line= 3
      3864948.68     10071307.02      3858877.01      10068844.6
      3852995.59     10067270.57
#Sta/Elev= 30
   -1552  136.13 -1250.8  137.78  -422.3  130.37   416.3   118.5   786.7  113.26
  1464.6  103.57  2176.4  104.93  2344.5   88.84  2398.4  101.51    2474   88.58
  2516.6   97.71  2551.5   88.67  2617.7  104.76  2830.1   110.4  2945.1  100.49
  3314.8  104.73  3598.3  101.84  4434.9   96.69  4713.6   81.16  4863.6   90.08
  4880.4    86.4  4998.1   72.67    5144   76.27    5184   86.76  5229.2   97.33
  6442.8   95.17  6879.2   96.29  7436.3   97.71  7653.4   98.27 11088.4  116.18
#Mann= 19 ,-1 , 0
   -1552     .11       0 -1250.8     .17       0  -422.3     .17       0
   416.3     .15       0   786.7     .11       0  1464.6     .11       0
  2617.7     .15       0  2945.1     .11       0  3314.8     .17       0
  3598.3     .15       0  4434.9     .17       0  4713.6     .15       0
  4863.6     .11       0  4880.4     .07       0    5184     .17       0
  6442.8     .15       0  6879.2     .11       0  7436.3     .17       0
  7653.4     .11       0
#Block Obstruct= 1 ,-1
     940  3165.1  108.68
Bank Sta=4880.4,5184
XS Rating Curve= 0 ,0
Exp/Cntr=0.3,0.1