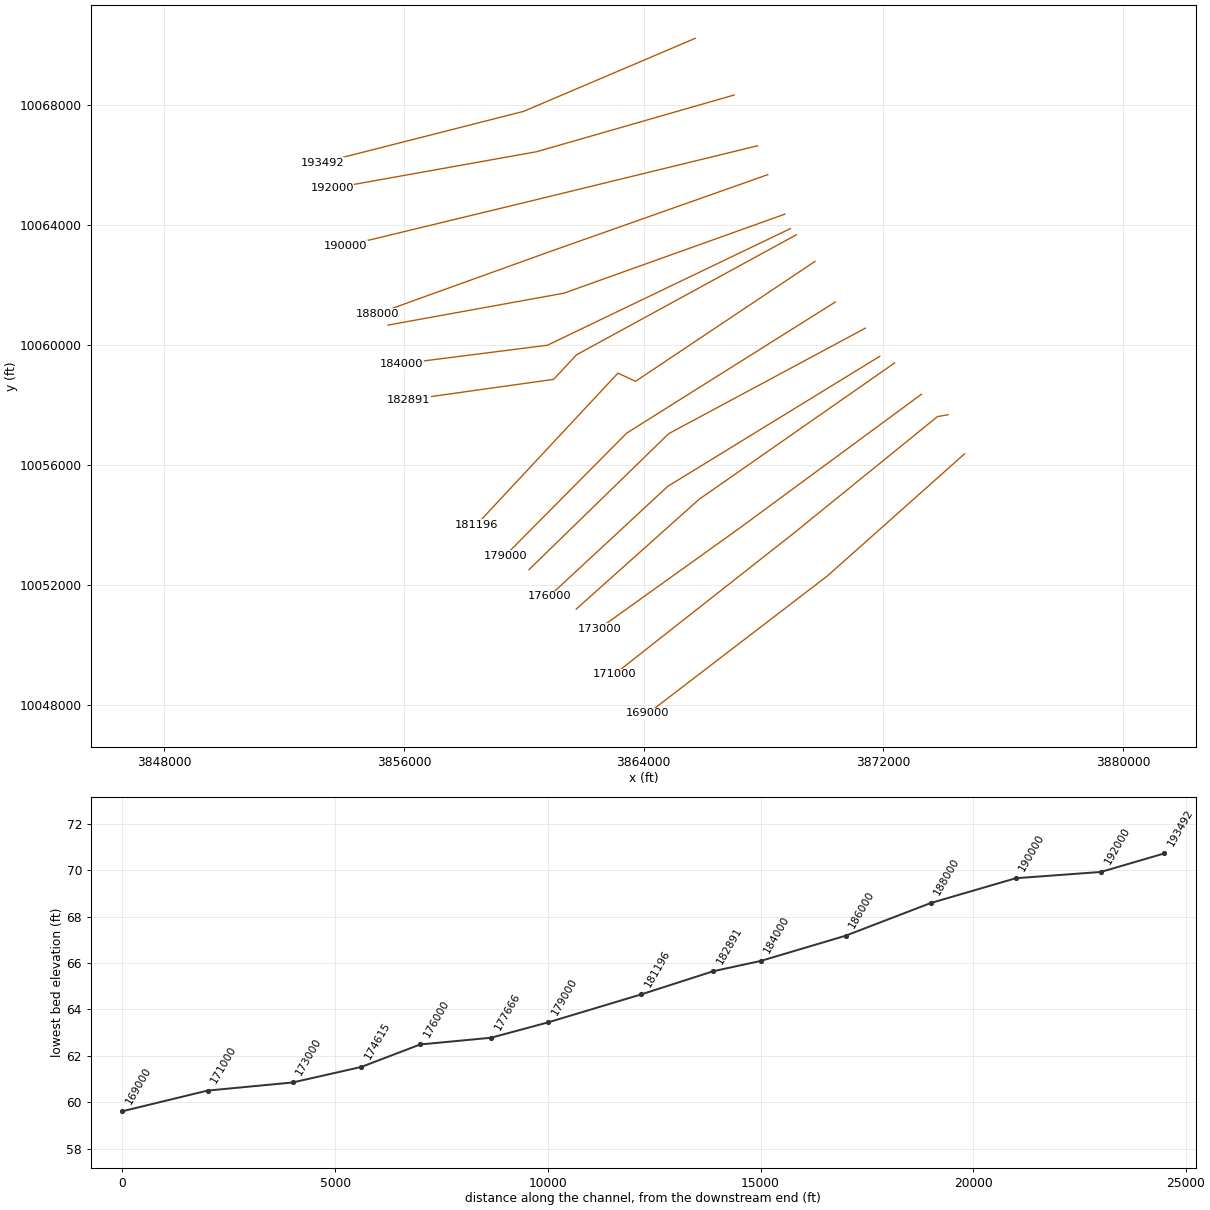
HEC-RAS study WFSJ Main.prj: WFSJ Main Base Level Engineering

--- WFSJ Main.g01 (geometry) --- (continued)

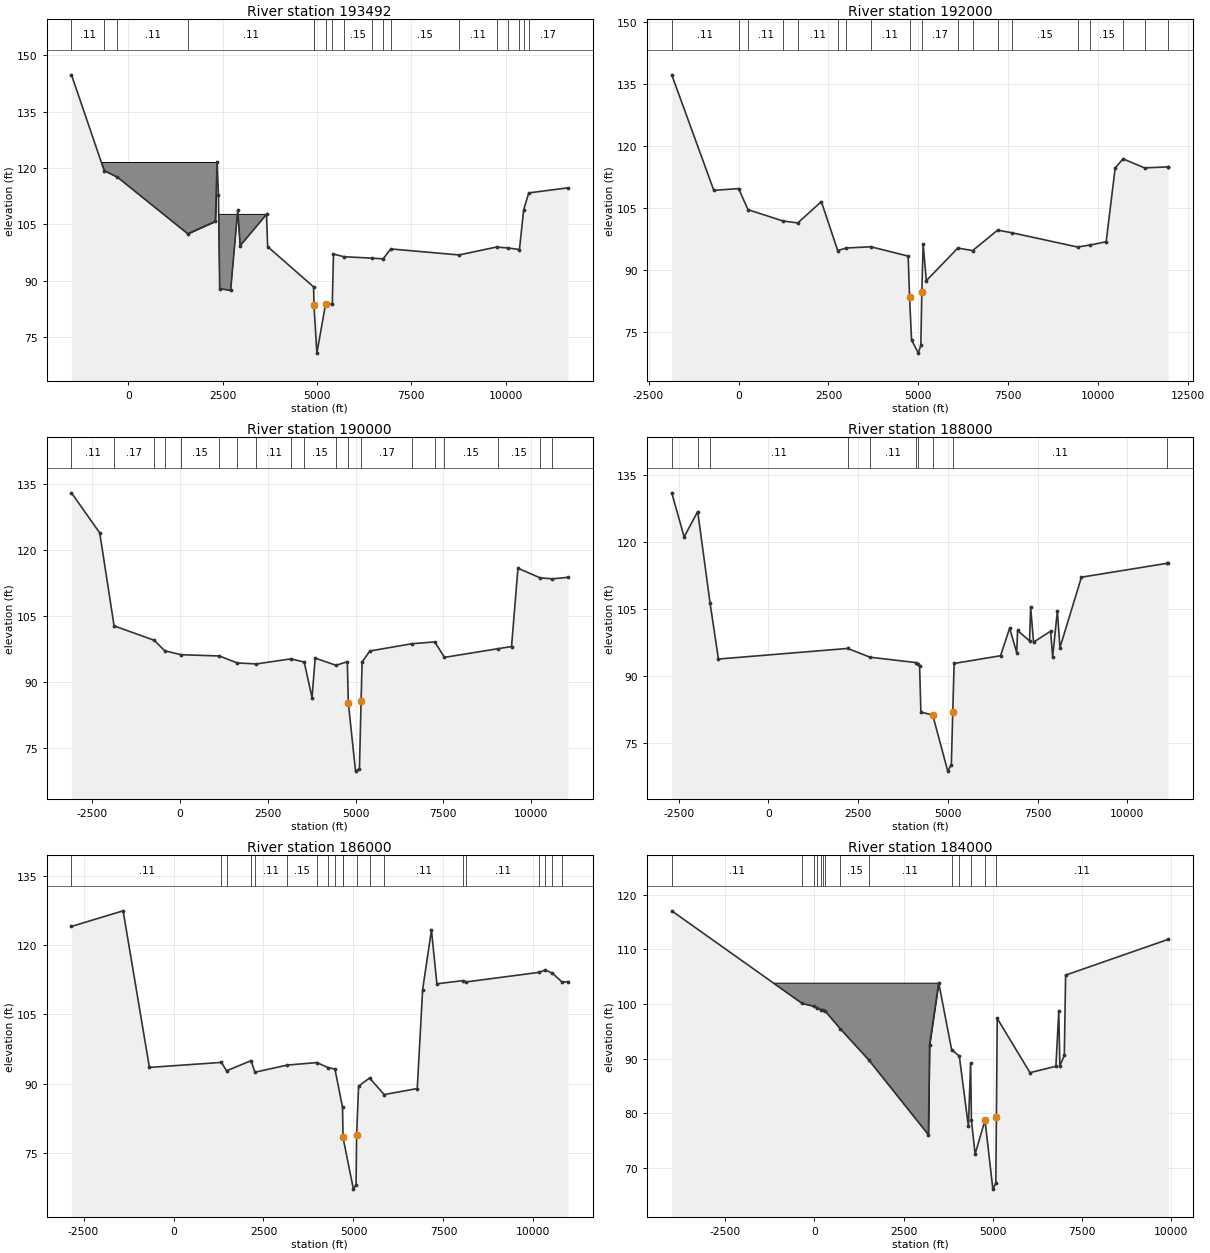
Type RM Length L Ch R = 1 ,193492  ,1492,1492,1492
BEGIN DESCRIPTION:
WFSJ Main 193.0
END DESCRIPTION:
XS GIS Cut Line= 3
      3865722.57     10070226.73      3859993.42     10067791.84
      3853274.66     10066086.11
#Sta/Elev= 30
 -1505.4   144.8  -639.9  119.32  -287.5  117.57  1575.1  102.51  2306.9  105.81
  2354.2  121.61  2389.6   112.8  2422.2   87.88  2712.4   87.42  2900.3  108.74
  2965.2   99.31  3663.5  107.66  3693.5   99.07  4911.2   88.37  4921.5   83.44
  4998.1   70.73  5228.3   83.75  5406.4   83.79  5438.2    97.1  5716.2   96.39
    6452   96.01  6754.4   95.82    6956   98.46  8770.3   96.86  9759.6   98.97
 10067.8   98.71 10366.8    98.3 10478.3  108.83 10612.2  113.37 11651.6  114.72
#Mann= 18 ,-1 , 0
 -1505.4     .11       0  -639.9     .15       0  -287.5     .11       0
  1575.1     .11       0  4911.2     .11       0  4921.5     .07       0
  5228.3     .11       0  5406.4     .17       0  5716.2     .15       0
    6452     .11       0  6754.4     .17       0    6956     .15       0
  8770.3     .11       0  9759.6     .17       0 10067.8     .15       0
 10366.8     .17       0 10478.3     .11       0 10612.2     .17       0
#Block Obstruct= 2 ,-1
    2376  3663.5  107.66    -900  2354.2  121.61
Bank Sta=4921.5,5228.3
XS Rating Curve= 0 ,0
Exp/Cntr=0.3,0.1

Type RM Length L Ch R = 1 ,192000  ,2000,2000,2000
BEGIN DESCRIPTION:
WFSJ Main 192.0
END DESCRIPTION:
XS GIS Cut Line= 3
      3867024.66     10068338.71      3860434.33     10066448.65
      3853601.49     10065226.96
#Sta/Elev= 30
   -1856  137.15  -687.3  109.25     3.4  109.67   262.6  104.59  1238.2  101.84
  1647.3  101.38  2301.9  106.53  2755.9   94.71  2998.9   95.32    3680   95.62
  4714.7   93.36  4753.6   83.42  4809.1   73.11  4998.1   69.93    5067   71.83
 5094.0584.61525  5130.9   96.26  5219.9   87.43  6094.3   95.31  6506.7    94.7
  7203.4   99.64  7601.5      99  9424.2   95.56  9780.3   96.06 10217.9   96.84
 10467.9  114.64 10686.8  116.86 11283.9  114.67 11929.6  114.91 11941.2  114.91
#Mann= 19 ,-1 , 0
   -1856     .11       0     3.4     .15       0   262.6     .11       0
  1238.2     .15       0  1647.3     .11       0  2755.9     .11       0
  2998.9     .15       0    3680     .11       0  4753.6     .07       0
 5094.05     .17       0  6094.3     .15       0  6506.7     .11       0
  7203.4     .17       0  7601.5     .15       0  9424.2     .11       0
  9780.3     .15       0 10686.8     .11       0 11283.9     .11       0
 11929.6     .15       0
Bank Sta=4753.6,5094.05
XS Rating Curve= 0 ,0
Exp/Cntr=0.3,0.1

Type RM Length L Ch R = 1 ,190000  ,2000,2000,2000
BEGIN DESCRIPTION:
WFSJ Main 190.0
END DESCRIPTION:
XS GIS Cut Line= 3
      3867805.92       10066646.      3859938.21     10064731.89
       3854055.9     10063312.67
#Sta/Elev= 30
 -3097.2  133.01 -2292.5  123.89 -1882.7  102.72  -737.1   99.44  -440.6   97.06
    23.5   96.16  1118.3   95.87  1625.1   94.29  2172.3   94.06  3158.6   95.22
  3536.2   94.48  3757.9   86.39  3847.7   95.39  4441.5   93.75  4763.7   94.57
 4792.18   85.27  4998.1   69.66  5109.2   70.16  5156.8   85.71  5185.5   94.54
  5407.6   97.01  6605.1   98.66    7257   99.08  7531.3   95.55  9050.1   97.52
  9444.3   98.02    9627  115.85 10258.5  113.66 10609.2  113.43 11051.1  113.78
#Mann= 19 ,-1 , 0
 -3097.2     .11       0 -1882.7     .17       0  -737.1     .15       0
  -440.6     .11       0    23.5     .15       0  1118.3     .15       0
  1625.1     .11       0  2172.3     .11       0  3158.6     .15       0
  3536.2     .15       0  4441.5     .11       0 4792.18     .07       0
  5156.8     .17       0  6605.1     .15       0    7257     .11       0
  7531.3     .15       0  9050.1     .15       0 10258.5     .17       0
 10609.2     .11       0
Bank Sta=4792.18,5156.8
XS Rating Curve= 0 ,0
Exp/Cntr=0.3,0.1

Type RM Length L Ch R = 1 ,188000  ,2000,2000,2000
BEGIN DESCRIPTION:
WFSJ Main 188.0
END DESCRIPTION:
XS GIS Cut Line= 3
      3868144.44     10065682.46       3860889.5     10063124.74
      3855111.68     10061047.43
#Sta/Elev= 30
 -2692.6  131.01 -2347.1  121.12 -1969.2  126.82 -1625.5  106.32   -1392   93.73
  2210.8   96.11  2832.3   94.14  4119.9   92.93  4158.4   92.66  4212.9   92.28
  4249.2   81.83  4578.9   81.18  4998.1   68.59  5097.4   70.06 5137.6381.74817
  5175.2   92.74  6468.2   94.47  6723.3  100.67  6918.6   95.18    6944  100.14
  7276.6    97.8  7307.7  105.37  7388.8   97.52  7864.4   99.98  7920.5   94.21
  8051.6  104.48  8124.9   96.31  8723.3  112.09 11109.1   115.2 11139.9  115.31
#Mann= 10 ,-1 , 0
 -2692.6     .11       0 -1969.2     .17       0 -1625.5     .11       0
  2210.8     .15       0  2832.3     .11       0  4119.9     .17       0
  4158.4     .11       0  4578.9     .06       0 5137.63     .11       0
 11109.1     .17       0
Bank Sta=4578.9,5137.63
XS Rating Curve= 0 ,0
Exp/Cntr=0.3,0.1

Type RM Length L Ch R = 1 ,186000  ,2000,2000,2000
BEGIN DESCRIPTION:
WFSJ Main 186.0
END DESCRIPTION:
XS GIS Cut Line= 3
      3868717.39     10064367.36      3861339.03     10061731.95
      3855475.21     10060669.45
#Sta/Elev= 30
 -2834.9  124.02 -1400.3  127.39  -669.2   93.51  1330.9    94.6  1473.1   92.77
  2156.7   94.98  2260.9   92.47  3160.3   94.02  3985.9   94.56  4293.8   93.47
  4485.7   93.16  4696.7   84.89 4709.97   78.36  4998.1   67.18  5072.3   68.13
  5088.3   78.89  5141.8   89.45  5447.3   91.23  5853.6   87.64  6773.1   88.94
    6922  110.32  7167.6  123.24  7318.3   111.6  8035.8  112.29  8135.4  112.01
 10167.4  114.09 10325.6  114.59 10524.7  113.92 10798.1  111.97 10959.3  112.07
#Mann= 20 ,-1 , 0
 -2834.9     .11       0  1330.9     .15       0  1473.1     .15       0
  2156.7     .15       0  2260.9     .11       0  3160.3     .15       0
  3985.9     .17       0  4293.8     .15       0  4485.7     .15       0
  4696.7     .11       0 4709.97     .07       0  5088.3     .11       0
  5447.3    .125       0  5853.6     .11       0  8035.8    .125       0
  8135.4     .11       0 10167.4     .17       0 10325.6     .11       0
 10524.7     .15       0 10798.1     .17       0
Bank Sta=4709.97,5088.3
XS Rating Curve= 0 ,0
Exp/Cntr=0.3,0.1

Type RM Length L Ch R = 1 ,184000  ,1109,1109,1109
BEGIN DESCRIPTION:
WFSJ Main 184.0
END DESCRIPTION:
XS GIS Cut Line= 3
       3868899.7      10063885.6      3860787.93     10059997.15
      3855917.93     10059380.38
#Sta/Elev= 30
 -3995.6  117.08  -345.8  100.13   -23.5   99.62      84   99.21   191.4   98.97
   254.2   98.83   298.8   98.73   728.5   95.43  1519.4   89.78  3192.5   76.06
  3226.2   92.56    3481  103.92  3843.9   91.63  4058.7   90.46  4313.3   77.62
  4375.7   89.17  4398.4   78.68  4501.1   72.51  4778.778.74182  4998.1   66.09
  5080.7   67.16 5097.55   79.22    5121   97.36  6038.3   87.43  6764.3    88.6
  6844.7   98.71  6874.9   88.68  6999.6   90.59  7036.2   105.3  9908.9  111.85
#Mann= 14 ,-1 , 0
 -3995.6     .11       0  -345.8     .15       0   -23.5     .17       0
      84     .15       0   191.4     .17       0   254.2     .15       0
   298.8     .17       0   728.5     .15       0  1519.4     .11       0
  3843.9     .17       0  4058.7     .11       0  4375.7     .08       0
  4778.7     .06       0 5097.55     .11       0
#XS Ineff= 1 ,-1
    5121    7150   97.36
Permanent Ineff=
       F
#Block Obstruct= 1 ,-1
   -1700    3481  103.92
Bank Sta=4778.7,5097.55
XS Rating Curve= 0 ,0
Exp/Cntr=0.3,0.1

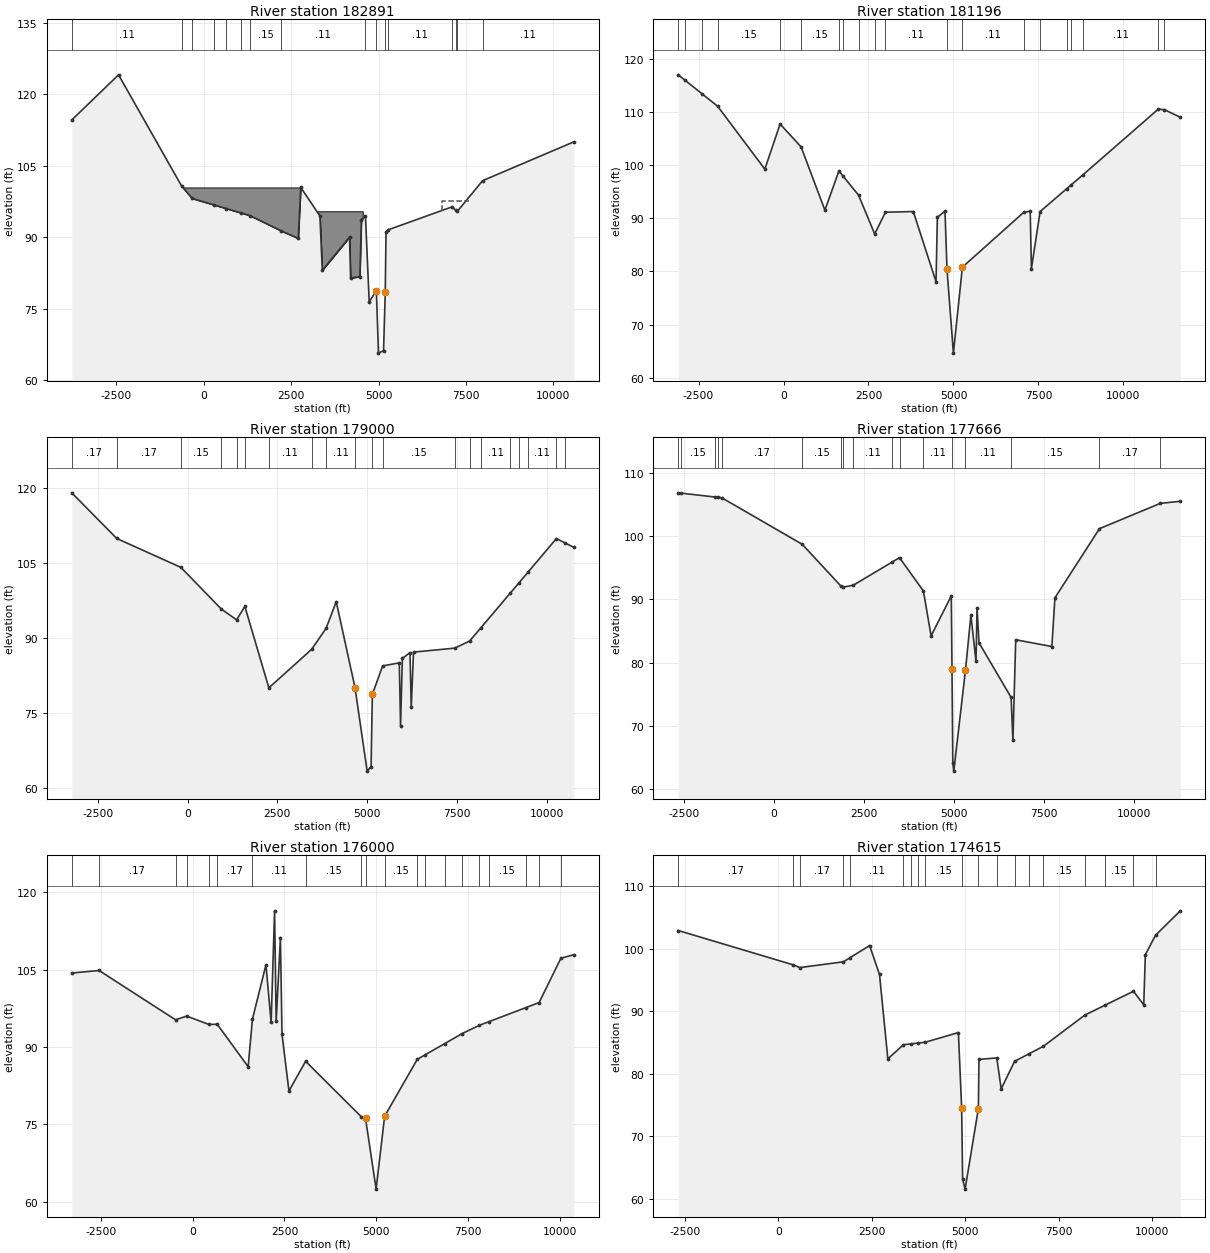
Type RM Length L Ch R = 1 ,182891  ,1695,1695,1695
BEGIN DESCRIPTION:
WFSJ Main 183.0
END DESCRIPTION:
XS GIS Cut Line= 4
      3869094.97     10063677.25      3861764.25     10059679.86
      3860996.02     10058859.55      3856165.28     10058182.46
#Sta/Elev= 30
 -3768.4  114.57 -2431.2  124.04  -626.2  100.68  -327.4    98.1   302.9   96.73
   648.9   95.98  1060.8   95.08  1317.8   94.52  2218.7    91.3  2706.5   89.71
  2777.7  100.41  3324.4   94.44  3392.7   83.03  4172.2      90  4201.4   81.37
  4466.5   81.72  4510.2   93.62  4627.5   94.33  4733.5   76.43  4938.6   78.74
  4998.1   65.65  5143.8   66.17 5191.98   78.38  5214.6   91.03  5264.4   91.49
  7089.7   96.31  7201.7   95.68  7254.4   95.41  7974.9  101.83 10583.2  109.98
#Mann= 16 ,-1 , 0
 -3768.4     .11       0  -626.2     .17       0  -327.4     .15       0
   302.9     .17       0   648.9     .15       0  1060.8     .17       0
  1317.8     .15       0  2218.7     .11       0  4627.5     .08       0
  4938.6     .06       0 5191.98     .08       0  5264.4     .11       0
  7089.7     .17       0  7201.7     .11       0  7254.4     .17       0
  7974.9     .11       0
#XS Ineff= 1 ,-1
    6804    7575   97.49
Permanent Ineff=
       F
#Block Obstruct= 2 ,-1
    -815  2777.7  100.41  2777.8  4548.1   95.41
Bank Sta=4938.6,5191.98
XS Rating Curve= 0 ,0
Exp/Cntr=0.3,0.1

Type RM Length L Ch R = 1 ,181196  ,2196,2196,2196
BEGIN DESCRIPTION:
WFSJ Main 182.0
END DESCRIPTION:
XS GIS Cut Line= 4
      3869719.95     10062791.82      3863730.39     10058794.44
      3863144.46     10059067.88      3858418.79     10054009.12
#Sta/Elev= 30
 -3096.9  116.94 -2908.5  115.98 -2401.4   113.4 -1938.3  111.04  -549.1   99.22
  -100.5  107.69   515.8  103.42  1217.3   91.51  1629.9   98.87  1745.4   97.96
  2208.1   94.33    2682   87.04  2999.5   91.13  3818.7   91.25  4486.9   78.07
  4526.2   90.19  4750.7   91.31  4809.7   80.37  4998.1   64.65  5262.6   80.81
  7065.4   91.09  7257.7   91.33  7292.9   80.54  7549.2   91.26  8328.8   95.53
  8468.5   96.29  8816.1   98.19 11026.7   110.5 11207.4  110.38 11673.3  108.97
#Mann= 20 ,-1 , 0
 -3096.9     .17       0 -2908.5     .11       0 -2401.4     .17       0
 -1938.3     .15       0  -100.5     .17       0   515.8     .15       0
  1629.9     .17       0  1745.4     .11       0  2208.1    .125       0
    2682     .15       0  2999.5     .11       0  4809.7     .06       0
  5262.6     .11       0  7065.4     .15       0  7549.2     .17       0
  8328.8     .17       0  8468.5     .15       0  8816.1     .11       0
 11026.7    .125       0 11207.4     .11       0
Bank Sta=4809.7,5262.6
XS Rating Curve= 0 ,0
Exp/Cntr=0.3,0.1

Type RM Length L Ch R = 1 ,179000  ,1334,1334,1334
BEGIN DESCRIPTION:
WFSJ Main 179.0
END DESCRIPTION:
XS GIS Cut Line= 3
       3870397.1     10061437.69      3863434.37     10057066.93
      3859382.16     10052987.88
#Sta/Elev= 30
 -3220.9  119.09 -1968.8  109.96  -184.2  104.18   938.1   95.87  1366.2   93.69
  1595.2   96.38  2263.3   80.09    3453   87.79  3855.7   91.99  4138.1   97.32
  4661.2   80.11  4998.1   63.44  5107.7   64.35  5143.1   78.79  5429.6   84.48
  5892.7   85.09    5928    72.5  5977.5   85.97  6189.6   87.14    6225   76.17
  6288.6   87.24  7434.4   88.03  7850.8   89.46  8167.3   92.14  8984.3   99.07
  9210.1  100.98  9477.2  103.25 10263.8  109.94 10510.2  109.05 10749.7  108.19
#Mann= 20 ,-1 , 0
 -3220.9     .17       0 -1968.8     .17       0  -184.2     .15       0
   938.1     .15       0  1366.2     .11       0  1595.2     .15       0
  2263.3     .11       0    3453     .15       0  3855.7     .11       0
  4661.2     .07       0  5143.1     .11       0  5429.6     .15       0
  7434.4     .15       0  7850.8     .17       0  8167.3     .11       0
  8984.3     .11       0  9210.1     .17       0  9477.2     .11       0
 10263.8     .11       0 10510.2    .125       0
Bank Sta=4661.2,5143.1
XS Rating Curve= 0 ,0
Exp/Cntr=0.3,0.1

Type RM Length L Ch R = 1 ,177666  ,1666,1666,1666
BEGIN DESCRIPTION:
WFSJ Main 178.0
END DESCRIPTION:
XS GIS Cut Line= 3
      3871399.67     10060565.28      3864837.17     10057049.65
      3860175.67     10052518.37
#Sta/Elev= 30
 -2655.6  106.91 -2579.7  106.86 -1640.5  106.25   -1548  106.19 -1444.6  106.12
     790   98.74  1852.4   92.19  1910.1   91.94  2206.6   92.26    3279   95.91
  3490.3   96.63  4153.7   91.35  4368.2   84.23  4929.1   90.57  4948.4   78.97
  4971.6   64.05  4998.1   62.78    5323  78.797  5473.7   87.51  5615.1   80.19
  5643.4   88.68    5700   83.12  6590.3   74.47  6640.7   67.64  6718.4   83.61
  7722.5   82.54  7807.4   90.26  9045.1  101.23 10736.7  105.24 11290.2  105.57
#Mann= 17 ,-1 , 0
 -2655.6     .17       0 -2579.7     .15       0 -1640.5     .17       0
   -1548     .15       0 -1444.6     .17       0     790     .15       0
  1852.4     .17       0  1910.1     .15       0  2206.6     .11       0
    3279     .17       0  3490.3     .11       0  4153.7     .11       0
  4948.4     .06       0    5323     .11       0  6590.3     .15       0
  9045.1     .17       0 10736.7     .11       0
Bank Sta=4948.4,5323
XS Rating Curve= 0 ,0
Exp/Cntr=0.3,0.1

Type RM Length L Ch R = 1 ,176000  ,1385,1385,1385
BEGIN DESCRIPTION:
WFSJ Main 176.0
END DESCRIPTION:
XS GIS Cut Line= 3
      3871881.46     10059627.79      3864805.66     10055293.44
       3860852.8     10051632.99
#Sta/Elev= 30
 -3297.8  104.32 -2553.5  104.81  -469.7   95.27  -166.1   95.98   442.3   94.36
   666.3   94.41  1509.7   86.19  1626.9   95.39  1995.3  105.91    2136    94.8
  2229.9  116.36  2273.7   95.02  2389.8  111.19  2432.4   92.49  2621.9   81.49
  3076.8   87.24  4591.8   76.52    4709   76.19  4998.1   62.49 5229.72   76.59
  6120.2   87.62  6319.3   88.43  6864.6   90.65  7340.5   92.59  7811.5    94.2
  8064.2   94.88  9082.4   97.63    9440    98.6 10034.9  107.19 10387.4  107.86
#Mann= 20 ,-1 , 0
 -3297.8     .15       0 -2553.5     .17       0  -469.7     .15       0
  -166.1     .17       0   442.3     .15       0   666.3     .17       0
  1626.9     .11       0  3076.8     .15       0  4591.8     .11       0
    4709     .07       0 5229.72     .15       0  6120.2     .11       0
  6319.3     .17       0  6864.6     .15       0  7340.5     .17       0
  7811.5     .15       0  8064.2     .15       0  9082.4     .17       0
    9440     .11       0 10034.9     .11       0
Bank Sta=4709,5229.72
XS Rating Curve= 0 ,0
Exp/Cntr=0.3,0.1

Type RM Length L Ch R = 1 ,174615  ,1615,1615,1615
BEGIN DESCRIPTION:
WFSJ Main 175.0
END DESCRIPTION:
XS GIS Cut Line= 3
      3872376.26     10059406.44      3865852.79     10054862.15
      3861752.05     10051204.03
#Sta/Elev= 30
 -2684.3  102.93   401.3   97.42   567.9   96.99  1740.6   97.92  1922.6    98.6
  2440.4  100.52  2705.7   95.89  2929.1   82.38  3346.6   84.64  3560.7   84.79
  3742.7   84.91  3932.1   85.04  4818.3   86.59 4905.73   74.46  4931.7   63.11
  4998.1   61.52 5353.5474.41957  5369.1   82.29  5846.5   82.53  5964.4   77.58
  6324.5   81.99  6717.7   83.22  7097.2    84.4  8204.7   89.39  8740.2   90.96
  9507.4    93.2  9781.8   91.03  9824.4   99.05 10097.5  102.17 10761.2  106.08
#Mann= 19 ,-1 , 0
 -2684.3     .17       0   401.3     .15       0   567.9     .17       0
  1740.6     .17       0  1922.6     .11       0  3346.6     .15       0
  3560.7     .11       0  3742.7     .17       0  3932.1     .15       0
 4905.73     .06       0 5353.54     .17       0  5846.5     .15       0
  6324.5     .17       0  6717.7     .15       0  7097.2     .15       0
  8204.7     .17       0  8740.2     .15       0  9507.4     .11       0
 10097.5     .17       0
Bank Sta=4905.73,5353.54
XS Rating Curve= 0 ,0
Exp/Cntr=0.3,0.1

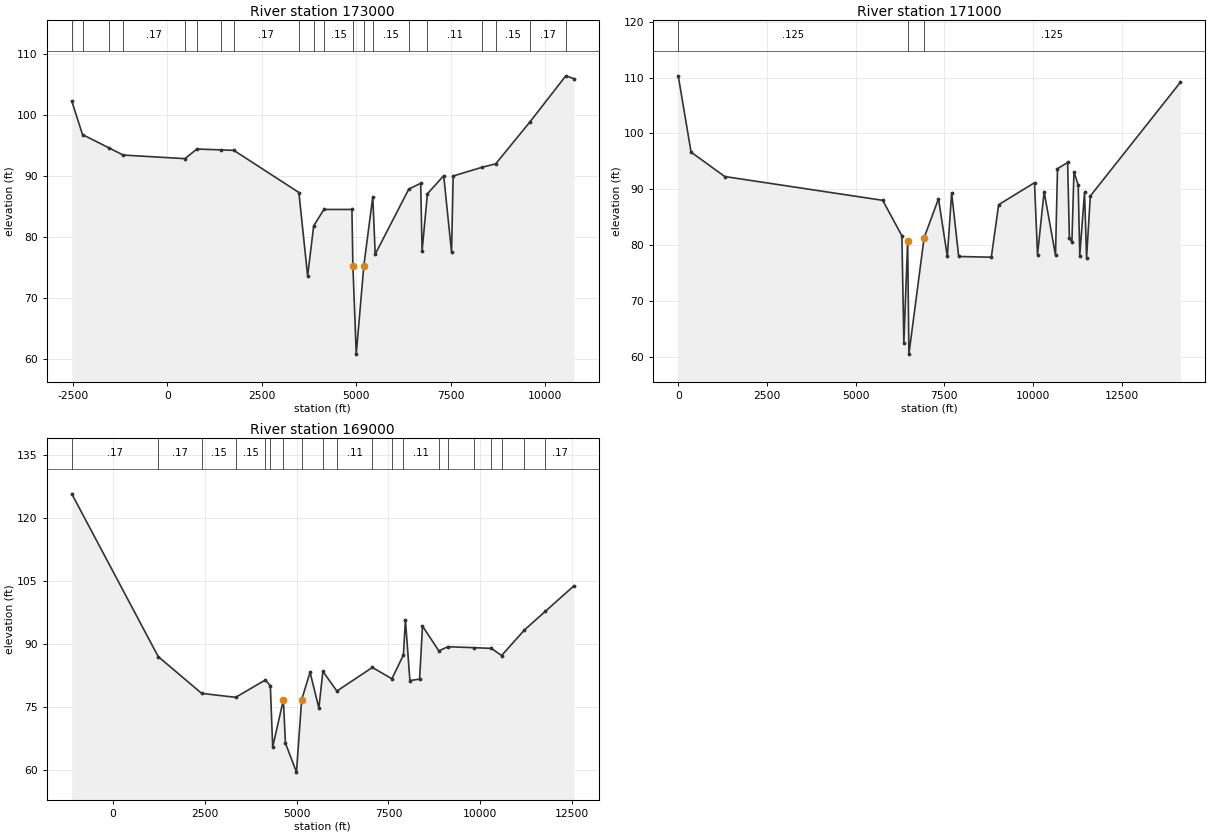
Type RM Length L Ch R = 1 ,173000  ,2000,2000,2000
BEGIN DESCRIPTION:
WFSJ Main 173.0
END DESCRIPTION:
XS GIS Cut Line= 3
      3873274.64     10058364.74       3867204.5     10053902.34
      3862519.43     10050552.24
#Sta/Elev= 30
 -2533.9  102.34 -2249.7   96.85 -1547.2   94.66 -1173.4   93.49   462.6    92.9
   779.4   94.48  1407.9   94.34  1757.4   94.26  3479.7   87.35  3710.9   73.67
  3871.1   81.88  4142.8   84.57  4884.1   84.57 4909.09   75.35  4998.1   60.85
  5199.3   75.36  5436.4   86.67  5499.9   77.23  6389.6   87.91  6704.7   88.86
  6741.3   77.75  6882.2   87.14  7313.9   90.11  7521.5   77.57  7565.2   90.06
  8338.2    91.5    8690   92.05  9599.7   98.94 10546.2  106.48 10759.6  106.02
#Mann= 20 ,-1 , 0
 -2533.9     .11       0 -2249.7     .17       0 -1547.2     .15       0
 -1173.4     .17       0   462.6     .15       0   779.4     .17       0
  1407.9     .15       0  1757.4     .17       0  3479.7     .15       0
  3871.1     .11       0  4142.8     .15       0 4909.09     .09       0
  5199.3     .12       0  5436.4     .15       0  6389.6     .15       0
  6882.2     .11       0  8338.2     .17       0    8690     .15       0
  9599.7     .17       0 10546.2     .15       0
Bank Sta=4909.09,5199.3
XS Rating Curve= 0 ,0
Exp/Cntr=0.3,0.1

Type RM Length L Ch R = 1 ,171000  ,2000,2000,2000
BEGIN DESCRIPTION:
WFSJ Main 171.0
END DESCRIPTION:
XS GIS Cut Line= 4
       3874163.1      10057681.5      3873806.71     10057617.96
       3869024.6     10053742.64      3863021.34     10049025.41
#Sta/Elev= 30
       0  110.32     362   96.66  1312.3   92.29  5762.7   88.03    6303   81.69
    6359   62.58  6466.1    80.7  6501.2    60.5  6929.4   81.32  7335.2   88.32
  7583.8   77.99  7705.8   89.37  7904.6   77.98  8823.8   77.85  9030.7   87.25
 10041.2   91.19 10126.1   78.33 10312.3   89.57 10633.1   78.21 10689.2   93.69
 10974.7   94.81 11024.4   81.26   11095   80.55 11152.8   93.15   11273   90.74
 11316.4   78.14 11451.1   89.45 11508.9   77.78 11614.6   88.81 14150.6  109.15
#Mann= 3 , 0 , 0
       0    .125       0  6466.1     .06       0  6929.4    .125       0
#XS Ineff= 3 ,-1
 10041.2   10692   91.19 10974.7   12530   94.81  7705.8    9960   89.37
Permanent Ineff=
       F       F       F
Bank Sta=6466.1,6929.4
XS Rating Curve= 0 ,0
Exp/Cntr=0.3,0.1

Type RM Length L Ch R = 1 ,169000  ,2000,2000,2000
BEGIN DESCRIPTION:
WFSJ Main 169.0
END DESCRIPTION:
XS GIS Cut Line= 3
      3874711.29      10056376.9      3870140.21     10052312.51
      3864147.09     10047726.75
#Sta/Elev= 30
 -1116.7  125.71  1235.9   87.05  2418.5   78.31  3344.1   77.38  4151.7    81.5
  4287.3   80.12  4350.8   65.57  4641.8   76.77  4697.9   66.49  4998.1   59.61
  5138.7   76.78  5367.2   83.34  5608.3   74.84  5716.3   83.55  6097.9   78.87
  7063.4   84.47  7595.1   81.79  7908.2   87.41  7962.3   95.83  8084.7   81.37
  8348.6   81.69  8427.5    94.3  8873.7    88.4    9115   89.39  9834.7   89.17
 10303.1      89 10579.7   87.31 11202.5   93.38 11770.1    97.8 12546.3  103.84
#Mann= 20 ,-1 , 0
 -1116.7     .17       0  1235.9     .17       0  2418.5     .15       0
  3344.1     .15       0  4151.7     .17       0  4287.3     .11       0
  4641.8     .06       0  5138.7     .11       0  5716.3     .15       0
  6097.9     .11       0  7063.4     .11       0  7595.1     .17       0
  7908.2     .11       0  8873.7     .11       0    9115     .15       0
  9834.7     .11       0 10303.1     .15       0 10579.7     .17       0
 11202.5     .15       0 11770.1     .17       0
#XS Ineff= 1 ,-1
  7962.3   11670   95.83
Permanent Ineff=
       F
Bank Sta=4641.8,5138.7
XS Rating Curve= 0 ,0
Exp/Cntr=0.3,0.1