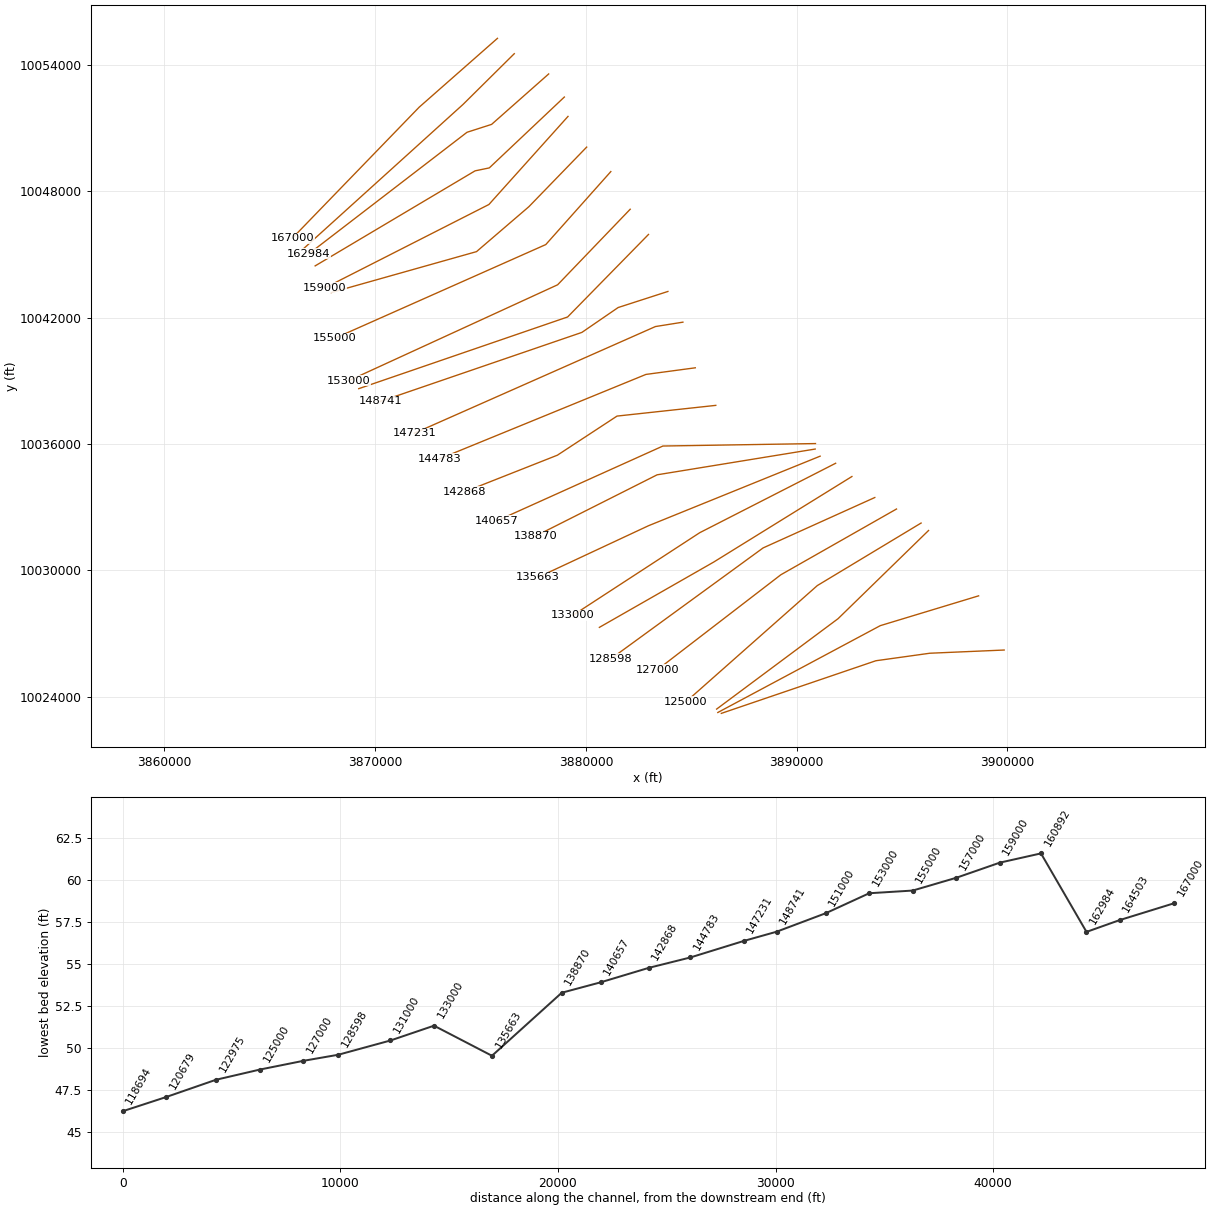
HEC-RAS study WFSJ Main.prj: WFSJ Main Base Level Engineering

--- WFSJ Main.g01 (geometry) --- (continued)

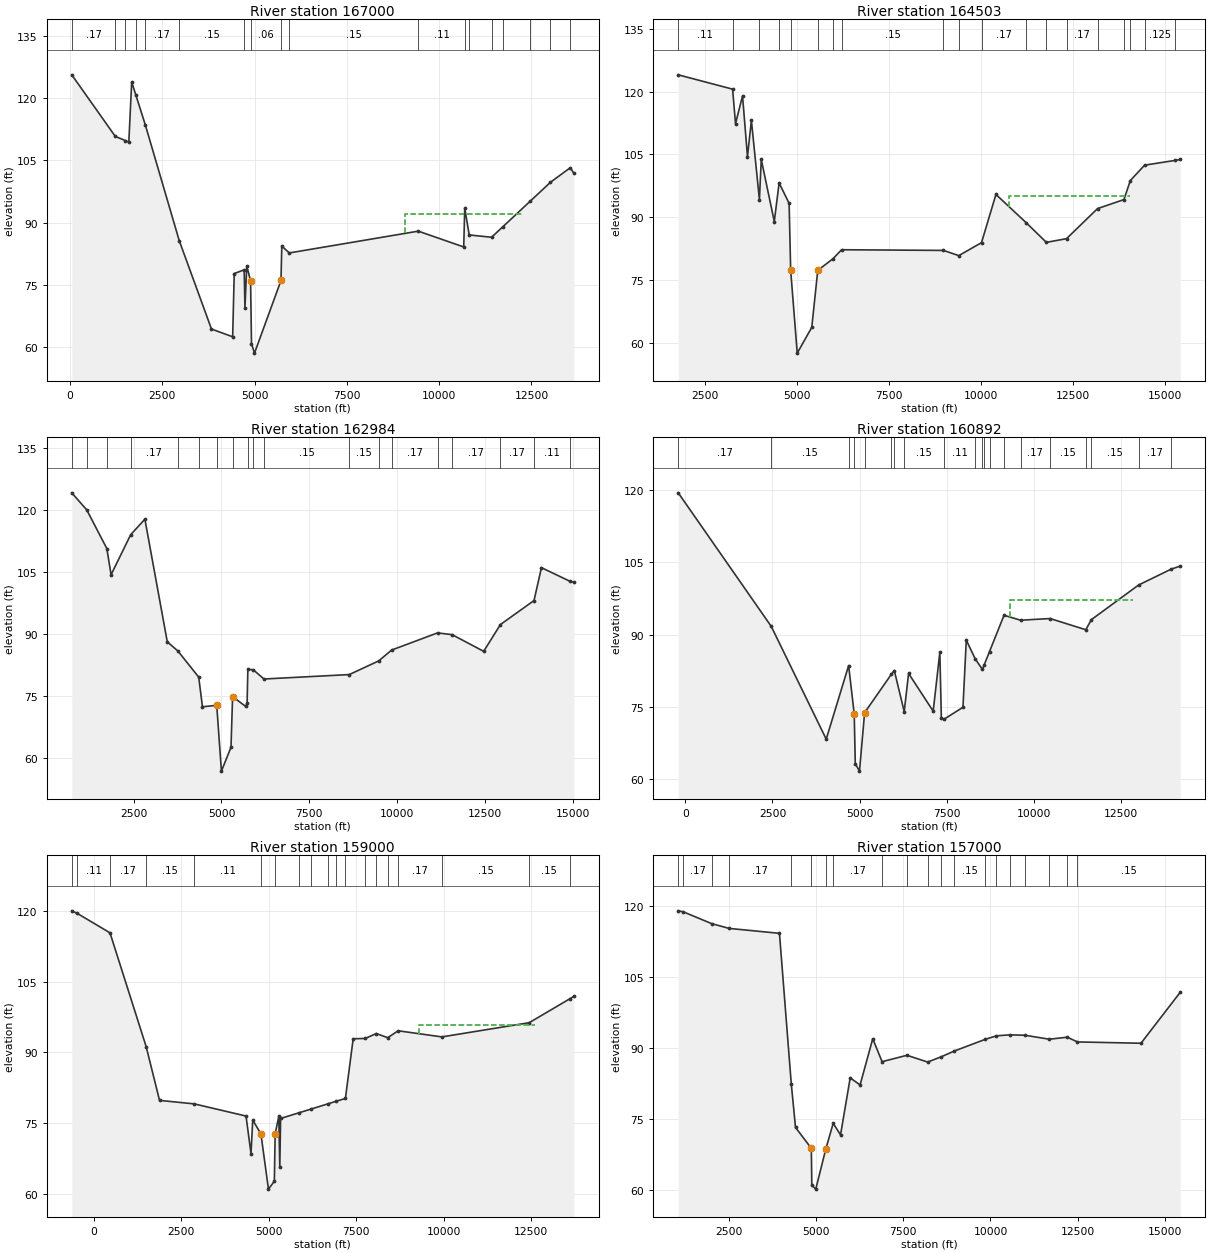
Type RM Length L Ch R = 1 ,167000  ,2497,2497,2497
BEGIN DESCRIPTION:
WFSJ Main 167.0
END DESCRIPTION:
XS GIS Cut Line= 3
      3875805.07     10055265.82      3872088.42     10051992.78
       3866075.3     10045774.81
#Sta/Elev= 30
    47.6  125.59    1227  110.77  1502.2  109.76  1593.4  109.43  1671.2  123.87
  1785.9  120.66  2040.2  113.54  2957.9   85.72  3832.4   64.42  4406.4   62.55
    4449   77.77  4718.5   78.67  4739.4   69.52  4788.7   79.61 4891.76   75.99
  4916.8   60.87  4998.1   58.62  5715.8    76.1  5737.2   84.36  5942.2   82.73
  9435.5   87.97 10666.2   84.17 10694.2   93.52 10815.1   87.06 11420.9    86.5
 11728.4   89.05 12467.5   95.18 13017.3   99.74 13552.5  103.23 13649.9  101.91
#Mann= 18 ,-1 , 0
    47.6     .17       0    1227     .15       0  1502.2     .17       0
  1785.9     .11       0  2040.2     .17       0  2957.9     .15       0
  4718.5     .11       0 4891.76     .06       0  5715.8     .11       0
  5942.2     .15       0  9435.5     .11       0 10694.2     .15       0
 10815.1     .11       0 11420.9     .15       0 11728.4     .17       0
 12467.5     .11       0 13017.3    .125       0 13552.5     .11       0
#XS Ineff= 1 ,-1
  9082.1   12250   92.15
Permanent Ineff=
       F
Bank Sta=4891.76,5715.8
XS Rating Curve= 0 ,0
Exp/Cntr=0.3,0.1

Type RM Length L Ch R = 1 ,164503  ,1519,1519,1519
BEGIN DESCRIPTION:
WFSJ Main 165.0
END DESCRIPTION:
XS GIS Cut Line= 3
      3876603.69     10054536.66       3874173.1     10052127.77
      3866595.13     10045265.93
#Sta/Elev= 30
    1764     124  3241.5  120.58  3320.7  112.36  3511.6  118.96  3645.9  104.48
    3752  113.14  3970.2   94.24  4020.7  103.82  4374.3   89.01  4505.5   98.22
  4777.3   93.35  4819.7   77.36  4998.1   57.62    5393   63.76  5555.8   77.35
  5966.1   80.11  6204.2   82.28  8972.6   82.12    9389   80.88 10006.2   83.97
 10398.4   95.47 11218.1   88.75 11768.4   84.04 12316.5   84.92   13159   92.09
 13877.3   94.25 14050.9   98.79 14438.5  102.45 15265.9  103.59 15409.1  103.81
#Mann= 19 ,-1 , 0
    1764     .11       0  3241.5     .17       0  3970.2     .17       0
  4505.5     .11       0  4819.7     .06       0  5555.8     .11       0
  5966.1     .17       0  6204.2     .15       0  8972.6     .15       0
    9389     .15       0 10006.2     .17       0 11218.1     .15       0
 11768.4     .17       0 12316.5     .17       0   13159     .15       0
 13877.3     .17       0 14050.9     .11       0 14438.5    .125       0
 15265.9    .125       0
#XS Ineff= 1 ,-1
   10766   14050   94.99
Permanent Ineff=
       F
Bank Sta=4819.7,5555.8
XS Rating Curve= 0 ,0
Exp/Cntr=0.3,0.1

Type RM Length L Ch R = 1 ,162984  ,2092,2092,2092
BEGIN DESCRIPTION:
WFSJ Main 163.0
END DESCRIPTION:
XS GIS Cut Line= 4
      3878235.58     10053573.93      3875527.27     10051178.12
       3874360.6     10050803.12       3866861.7     10045033.14
#Sta/Elev= 30
   734.9  124.17  1161.6  120.05  1734.2   110.7  1854.3  104.38  2413.4  114.05
  2817.9   117.8  3455.5   88.18    3758   85.95  4350.8   79.64    4458   72.47
  4864.9   72.82  4998.1   56.92  5270.9   62.68  5316.6   74.91  5686.6   72.58
  5730.1    73.3  5750.9   81.52    5907    81.4  6210.5   79.18  8639.9   80.25
  9478.4   83.55  9845.4   86.17 11154.2   90.32 11569.7    89.9 12468.9   85.87
 12947.9   92.35 13903.4   98.14 14115.3  106.09 14923.7  102.81 15038.1  102.55
#Mann= 19 ,-1 , 0
   734.9     .11       0  1161.6     .17       0  1734.2     .17       0
  2413.4     .17       0    3758     .15       0  4350.8     .11       0
  4864.9     .06       0  5316.6     .11       0  5750.9     .15       0
    5907     .17       0  6210.5     .15       0  8639.9     .15       0
  9478.4     .17       0  9845.4     .17       0 11154.2     .15       0
 11569.7     .17       0 12947.9     .17       0 13903.4     .11       0
 14923.7     .11       0
Bank Sta=4864.9,5316.6
XS Rating Curve= 0 ,0
Exp/Cntr=0.3,0.1

Type RM Length L Ch R = 1 ,160892  ,1892,1892,1892
BEGIN DESCRIPTION:
WFSJ Main 161.0
END DESCRIPTION:
XS GIS Cut Line= 4
      3878979.17     10052477.53      3875417.85     10049111.07
      3874742.37     10048970.47       3867155.6      10044456.6
#Sta/Elev= 30
  -206.9  119.46    2463    91.7    4043   68.24  4686.6   83.54  4846.9   73.51
  4877.6   63.15  4998.1   61.59 5145.56   73.74  5912.6   81.72  5997.8   82.51
  6282.8   73.96  6408.2    81.9  7115.1   74.06    7306   86.31  7348.8    72.7
  7426.5   72.38  7970.1   74.87  8065.2   88.82  8321.7   84.94  8527.2   82.74
  8579.2   83.68  8732.7   86.46  9149.3      94  9624.6   92.97 10472.5   93.32
 11497.1   90.99   11658   93.09 13015.1   100.3 13949.2  103.59 14211.7  104.23
#Mann= 20 ,-1 , 0
  -206.9     .17       0    2463     .15       0  4686.6     .11       0
  4846.9     .06       0 5145.56     .11       0  5912.6     .15       0
  5997.8     .11       0  6282.8     .15       0  7426.5     .11       0
  8321.7     .17       0  8527.2     .15       0  8579.2     .11       0
  8732.7     .17       0  9149.3     .11       0  9624.6     .17       0
 10472.5     .15       0 11497.1     .11       0   11658     .15       0
 13015.1     .17       0 13949.2     .15       0
#XS Ineff= 2 ,-1
  8065.2    8930   88.82  9319.7   12860   97.09
Permanent Ineff=
       F       F
Bank Sta=4846.9,5145.56
XS Rating Curve= 0 ,0
Exp/Cntr=0.3,0.1

Type RM Length L Ch R = 1 ,159000  ,2000,2000,2000
BEGIN DESCRIPTION:
WFSJ Main 159.0
END DESCRIPTION:
XS GIS Cut Line= 3
      3879152.84     10051557.44      3875399.55     10047372.46
      3867625.45     10043415.49
#Sta/Elev= 30
  -621.5     120  -469.9  119.48   470.1  115.34    1503   91.25    1886   79.84
  2878.7    79.1  4357.4   76.52  4499.5   68.56  4548.8   75.67  4782.8   72.75
  4998.1   61.04  5166.5   62.71  5188.7   72.76  5293.6   76.44  5322.2    65.7
  5344.5   76.01  5881.4   77.24  6200.9   77.97  6697.4   79.11  6941.1   79.67
  7196.7   80.25  7418.5   92.89  7764.5   92.96  8078.3      94  8406.6   93.12
  8701.8   94.59  9952.9   93.29 12448.3    96.3 13599.7  101.33 13723.2  101.87
#Mann= 19 ,-1 , 0
  -621.5     .17       0  -469.9     .11       0   470.1     .17       0
    1503     .15       0  2878.7     .11       0  4782.8     .06       0
  5188.7     .11       0  5881.4     .17       0  6200.9     .11       0
  6697.4     .17       0  6941.1     .15       0  7196.7     .17       0
  7764.5     .11       0  8078.3     .17       0  8406.6     .15       0
  8701.8     .17       0  9952.9     .15       0 12448.3     .15       0
 13599.7     .17       0
#XS Ineff= 1 ,-1
  9286.8   12600   95.78
Permanent Ineff=
       F
Bank Sta=4782.8,5188.7
XS Rating Curve= 0 ,0
Exp/Cntr=0.3,0.1

Type RM Length L Ch R = 1 ,157000  ,2000,2000,2000
BEGIN DESCRIPTION:
WFSJ Main 157.0
END DESCRIPTION:
XS GIS Cut Line= 4
      3880038.25      10050099.1      3877297.09     10047268.69
      3874811.82     10045133.67       3867921.2     10043189.71
#Sta/Elev= 30
  1059.8  118.88  1207.7  118.66  2016.1  116.18  2515.5  115.17  3958.2  114.13
  4296.3   82.38  4417.9   73.17  4870.6   68.75  4884.7   60.95  4998.1   60.14
  5281.3   68.51  5496.4   74.02  5707.1    71.6  5983.7   83.62  6266.8   82.13
  6628.9   91.88  6896.7   87.04  7609.1   88.39  8201.3   86.96  8585.9   88.06
  8955.8   89.26  9854.2   91.77 10172.5    92.5 10550.5    92.7 10983.6   92.62
 11686.6   91.78 12200.3   92.21 12490.5   91.21 14309.9   90.93   15436  101.71
#Mann= 20 ,-1 , 0
  1059.8     .11       0  1207.7     .17       0  2016.1     .17       0
  2515.5     .17       0  4296.3     .11       0  4870.6     .06       0
  5281.3     .11       0  5496.4     .17       0  6896.7     .11       0
  7609.1     .17       0  8201.3     .11       0  8585.9     .17       0
  8955.8     .15       0  9854.2     .15       0 10172.5     .17       0
 10550.5     .15       0 10983.6     .15       0 11686.6     .15       0
 12200.3     .17       0 12490.5     .15       0
#XS Ineff= 1 ,-1
  6628.9    9960   91.88
Permanent Ineff=
       F
Bank Sta=4870.6,5281.3
XS Rating Curve= 0 ,0
Exp/Cntr=0.3,0.1

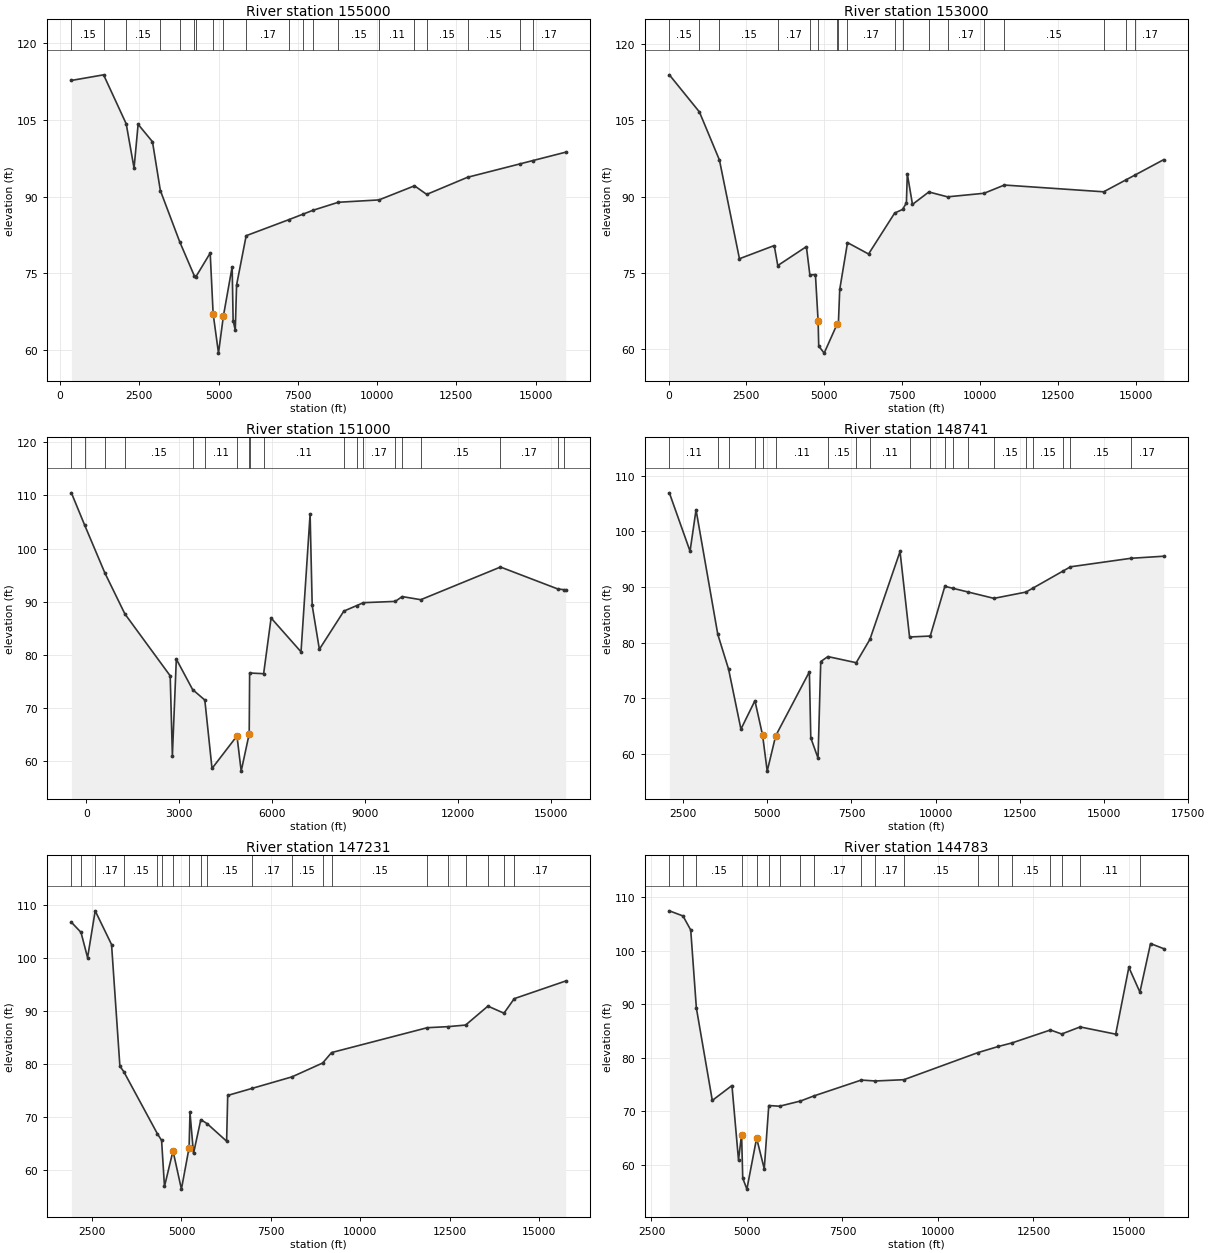
Type RM Length L Ch R = 1 ,155000  ,2000,2000,2000
BEGIN DESCRIPTION:
WFSJ Main 155.0
END DESCRIPTION:
XS GIS Cut Line= 3
      3881184.04     10048935.86      3878097.98     10045468.91
      3868093.82     10041019.24
#Sta/Elev= 30
   358.5  112.72  1374.5  113.82  2087.9  104.23  2335.1   95.57    2463  104.14
  2916.2  100.73  3164.2   91.19    3773   81.19  4237.2   74.47  4275.8   74.22
  4736.5   78.96  4828.5   67.13  4998.1   59.38  5151.3   66.58  5428.9   76.27
  5459.8   65.73  5527.3   63.84  5568.4    72.7  5870.7   82.35  7226.1   85.51
  7669.6   86.58  7981.2   87.33  8776.6   88.89 10059.2   89.35 11179.5   92.11
 11565.1   90.43 12853.2   93.78 14501.5   96.39 14901.8   97.03 15949.1   98.69
#Mann= 20 ,-1 , 0
   358.5     .15       0  1374.5     .11       0  2087.9     .15       0
  3164.2     .15       0    3773     .17       0  4237.2     .17       0
  4275.8     .11       0  4828.5     .06       0  5151.3     .11       0
  5870.7     .17       0  7226.1     .17       0  7669.6     .11       0
  7981.2     .15       0  8776.6     .15       0 10059.2     .11       0
 11179.5     .11       0 11565.1     .15       0 12853.2     .15       0
 14501.5     .17       0 14901.8     .17       0
Bank Sta=4828.5,5151.3
XS Rating Curve= 0 ,0
Exp/Cntr=0.3,0.1

Type RM Length L Ch R = 1 ,153000  ,2000,2000,2000
BEGIN DESCRIPTION:
WFSJ Main 153.0
END DESCRIPTION:
XS GIS Cut Line= 3
      3882104.19     10047147.68      3878660.37     10043558.69
      3868754.29      10039005.7
#Sta/Elev= 30
      26  113.94   990.8  106.65  1634.2    97.2  2277.2   77.78  3394.6   80.37
  3508.5   76.44  4427.3   80.16  4538.5   74.61  4717.3   74.66 4803.64    65.5
  4823.3   60.61  4998.1   59.22    5421   65.02    5454   64.92    5498   71.74
  5747.1   80.95  6423.5   78.71  7262.4   86.76  7516.9   87.48  7639.4   88.76
  7667.9   94.48  7834.3   88.46  8359.4   90.91  8959.7   89.95 10133.2   90.65
 10785.7   92.27 13973.8   90.94   14697   93.31 14990.8   94.27 15902.3   97.26
#Mann= 18 ,-1 , 0
      26     .15       0   990.8     .17       0  1634.2     .15       0
  3508.5     .17       0  4538.5     .15       0 4803.64     .06       0
    5421     .08       0    5454     .11       0  5747.1     .17       0
  7262.4     .17       0  7516.9     .11       0  8359.4     .11       0
  8959.7     .17       0 10133.2     .17       0 10785.7     .15       0
 13973.8     .17       0   14697     .11       0 14990.8     .17       0
Bank Sta=4803.64,5421
XS Rating Curve= 0 ,0
Exp/Cntr=0.3,0.1

Type RM Length L Ch R = 1 ,151000  ,2259,2259,2259
BEGIN DESCRIPTION:
WFSJ Main 151.0
END DESCRIPTION:
XS GIS Cut Line= 3
      3882972.26     10045949.78      3879133.97     10042029.41
      3869222.54     10038623.49
#Sta/Elev= 30
  -486.5   110.5   -61.8  104.47   593.1   95.42  1241.6   87.67  2704.9      76
  2775.6   60.95  2902.9   79.15  3429.1   73.41  3823.3   71.43  4055.6   58.53
  4861.7   64.66  4998.1   58.03 5256.91   65.06  5270.8   76.53  5723.1    76.4
  5963.8    86.9  6930.9   80.52  7223.7  106.48  7291.5   89.26  7523.1      81
  8313.9    88.2  8725.8   89.23  8946.2   89.79  9975.3   90.03 10197.5   90.94
   10798   90.35 13372.4   96.51 15221.6   92.38 15431.2   92.23 15480.3    92.2
#Mann= 19 ,-1 , 0
  -486.5     .11       0   -61.8     .11       0   593.1     .15       0
  1241.6     .15       0  3429.1     .15       0  3823.3     .11       0
  4861.7     .06       0 5256.91     .11       0  5270.8     .15       0
  5723.1     .11       0  8313.9     .17       0  8725.8     .15       0
  8946.2     .17       0  9975.3     .15       0 10197.5     .17       0
   10798     .15       0 13372.4     .17       0 15221.6     .15       0
 15431.2     .17       0
Bank Sta=4861.7,5256.91
XS Rating Curve= 0 ,0
Exp/Cntr=0.3,0.1

Type RM Length L Ch R = 1 ,148741  ,1510,1510,1510
BEGIN DESCRIPTION:
WFSJ Main 149.0
END DESCRIPTION:
XS GIS Cut Line= 4
       3883892.4     10043241.45      3881531.29     10042477.56
      3879812.54     10041297.01      3870247.06     10038015.93
#Sta/Elev= 30
  2092.3  106.93  2706.7   96.44  2884.8  103.88  3530.4   81.51  3852.2   75.22
  4218.1   64.47  4633.2   69.58  4860.5    63.4  4998.1   56.93 5249.87  63.274
  6250.3   74.77  6292.2   62.91  6507.4   59.26    6588   76.62  6800.8   77.51
  7640.5   76.41  8048.5   80.61  8942.5   96.39  9224.9   81.03  9839.6    81.2
 10272.7   90.13 10505.4   89.79 10956.3   89.12 11730.7   87.97 12681.5    89.1
 12903.4   89.86 13788.5    92.9 14003.1   93.64 15799.7   95.17 16771.6   95.54
#Mann= 20 ,-1 , 0
  2092.3     .11       0  3530.4     .17       0  3852.2     .15       0
  4633.2     .11       0  4860.5     .06       0 5249.87     .11       0
  6800.8     .15       0  7640.5     .17       0  8048.5     .11       0
  9224.9     .11       0  9839.6     .11       0 10272.7     .11       0
 10505.4     .17       0 10956.3     .15       0 11730.7     .15       0
 12681.5     .17       0 12903.4     .15       0 13788.5     .17       0
 14003.1     .15       0 15799.7     .17       0
Bank Sta=4860.5,5249.87
XS Rating Curve= 0 ,0
Exp/Cntr=0.3,0.1

Type RM Length L Ch R = 1 ,147231  ,2448,2448,2448
BEGIN DESCRIPTION:
WFSJ Main 147.0
END DESCRIPTION:
XS GIS Cut Line= 3
      3884605.29     10041782.93      3883302.12     10041574.78
      3871862.87      10036506.1
#Sta/Elev= 30
  1919.2  106.82  2188.3  104.91  2372.3  100.13  2585.4  108.98  3043.1  102.61
  3276.4   79.62  3385.6   78.58  4328.5   66.81  4443.2    65.6    4524   56.88
  4762.3   63.61  4998.1   56.38 5212.76   64.22  5237.4   70.88    5336   63.12
  5540.5   69.51  5716.8   68.76  6262.4   65.44  6293.2   74.09  6979.7   75.43
  8091.7    77.6  8950.7   80.22  9198.7   82.19 11876.5   86.89 12456.7   87.09
 12949.6   87.39 13573.9   90.97 14022.5   89.63 14310.1   92.38 15750.8   95.72
#Mann= 20 ,-1 , 0
  1919.2     .17       0  2188.3     .17       0  2585.4     .17       0
  3385.6     .15       0  4328.5     .11       0  4443.2     .08       0
  4762.3     .06       0 5212.76     .11       0  5540.5     .17       0
  5716.8     .15       0  6979.7     .17       0  8091.7     .15       0
  8950.7     .11       0  9198.7     .15       0 11876.5     .15       0
 12456.7     .17       0 12949.6     .17       0 13573.9     .17       0
 14022.5     .15       0 14310.1     .17       0
Bank Sta=4762.3,5212.76
XS Rating Curve= 0 ,0
Exp/Cntr=0.3,0.1

Type RM Length L Ch R = 1 ,144783  ,1915,1915,1915
BEGIN DESCRIPTION:
WFSJ Main 145.0
END DESCRIPTION:
XS GIS Cut Line= 3
      3885192.46     10039614.88      3882850.74     10039300.48
      3873059.03     10035290.05
#Sta/Elev= 30
  2967.7  107.46  3324.6   106.5  3527.3  103.88  3674.9   89.29  4092.3   71.99
  4606.9   74.78  4778.4   60.85  4859.1   65.61  4889.4   57.45  4998.1    55.4
 5252.5564.92963  5452.7    59.2    5571   71.04  5852.3   70.91  6400.8   71.88
  6750.9   72.83  7992.4    75.8  8362.6   75.63  9108.1   75.87 11048.2   80.94
 11583.6   82.09 11938.5   82.75 12945.5   85.17 13241.2   84.42 13722.6   85.74
 14654.8   84.39 14999.2   96.89 15288.7   92.25 15567.1  101.34 15911.6  100.38
#Mann= 19 ,-1 , 0
  2967.7     .17       0  3324.6     .11       0  3674.9     .15       0
  4859.1     .09       0 5252.55     .15       0    5571     .17       0
  5852.3     .15       0  6400.8     .15       0  6750.9     .17       0
  7992.4     .15       0  8362.6     .17       0  9108.1     .15       0
 11048.2     .17       0 11583.6     .11       0 11938.5     .15       0
 12945.5     .15       0 13241.2     .15       0 13722.6     .11       0
 15288.7     .17       0
Bank Sta=4859.1,5252.55
XS Rating Curve= 0 ,0
Exp/Cntr=0.3,0.1

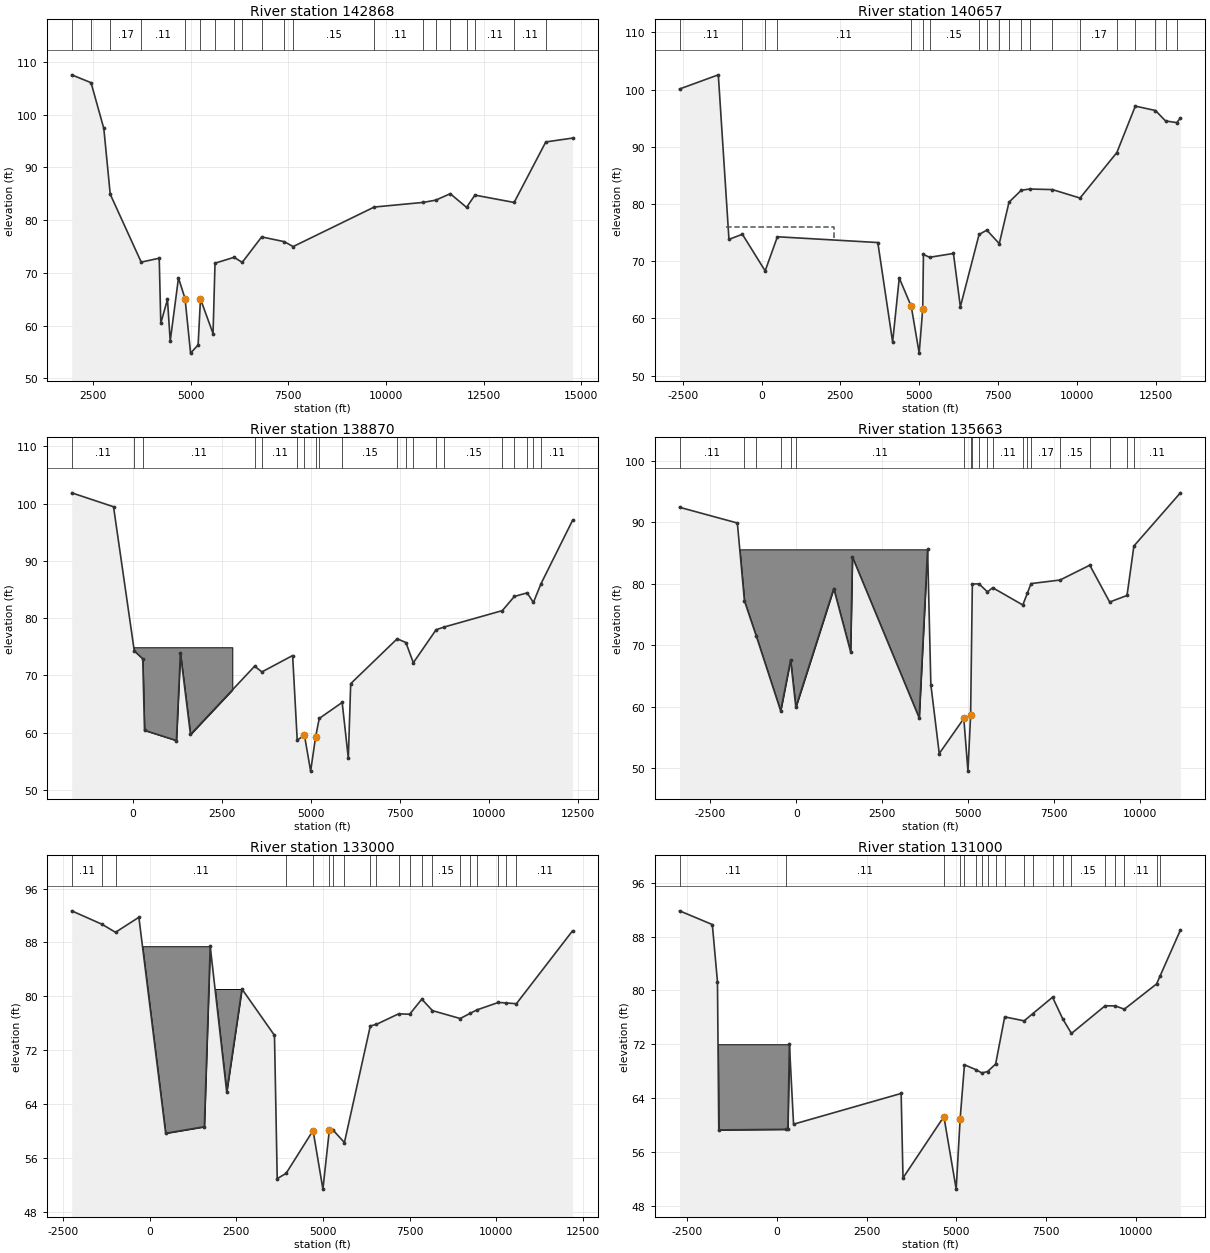
Type RM Length L Ch R = 1 ,142868  ,2211,2211,2211
BEGIN DESCRIPTION:
WFSJ Main 143.0
END DESCRIPTION:
XS GIS Cut Line= 4
      3886165.18     10037830.17      3881479.21     10037321.31
      3878649.35     10035463.67      3874257.02     10033727.58
#Sta/Elev= 30
  1955.1  107.53    2450  106.04  2777.2   97.36  2941.2    84.9  3734.3   72.03
  4195.5   72.77  4235.8   60.45  4406.8   64.96  4477.2   57.06  4688.4   69.02
 4856.48   65.13  4998.1   54.78  5191.3   56.33  5251.7   65.04  5573.6   58.49
  5623.9   71.83  6112.2   72.94  6320.1   71.98  6818.2   76.81  7395.2   75.91
    7624   74.98  9700.3   82.47 10954.1   83.35   11276   83.78 11646.2      85
 12063.3   82.41 12277.9   84.73 13281.3   83.34 14092.2   94.81 14776.7   95.54
#Mann= 20 ,-1 , 0
  1955.1     .17       0    2450     .11       0  2941.2     .17       0
  3734.3     .11       0 4856.48     .06       0  5251.7     .11       0
  5623.9     .15       0  6112.2     .17       0  6320.1     .15       0
  6818.2     .17       0  7395.2     .11       0    7624     .15       0
  9700.3     .11       0 10954.1     .17       0   11276     .11       0
 11646.2     .17       0 12063.3     .15       0 12277.9     .11       0
 13281.3     .11       0 14092.2     .11       0
Bank Sta=4856.48,5251.7
XS Rating Curve= 0 ,0
Exp/Cntr=0.3,0.1

Type RM Length L Ch R = 1 ,140657  ,1787,1787,1787
BEGIN DESCRIPTION:
WFSJ Main 141.0
END DESCRIPTION:
XS GIS Cut Line= 3
      3890894.78     10036015.93      3883655.16     10035898.74
       3875777.6     10032344.07
#Sta/Elev= 30
 -2601.6  100.11 -1372.1  102.59 -1034.5   73.81    -609   74.71   113.7    68.3
   501.4   74.27  3686.2   73.26  4156.2   55.86  4366.2   67.06    4747   62.09
  4998.1   53.92 5110.1161.62156  5133.5   71.17  5329.4   70.68  6084.8   71.35
  6303.9   62.02  6897.5   74.67  7142.8   75.43  7538.1   73.07  7846.9   80.32
  8236.3   82.41  8509.6   82.62  9225.2   82.52 10098.5   81.04 11266.9      89
 11853.1   97.12 12491.3   96.35 12810.4   94.53 13165.7   94.23 13281.4   95.02
#Mann= 20 ,-1 , 0
 -2601.6     .11       0    -609     .15       0   113.7     .11       0
   501.4     .11       0    4747     .06       0 5110.11     .11       0
  5329.4     .15       0  6897.5     .11       0  7142.8     .15       0
  7538.1     .17       0  7846.9     .11       0  8236.3     .17       0
  8509.6     .15       0  9225.2     .11       0 10098.5     .17       0
 11266.9     .11       0 11853.1     .11       0 12491.3     .11       0
 12810.4     .15       0 13165.7     .11       0
#XS Ineff= 1 ,-1
   -1125    2286   75.97
Permanent Ineff=
       F
Bank Sta=4747,5110.11
XS Rating Curve= 0 ,0
Exp/Cntr=0.3,0.1

Type RM Length L Ch R = 1 ,138870  ,3207,3207,3207
BEGIN DESCRIPTION:
WFSJ Main 139.0
END DESCRIPTION:
XS GIS Cut Line= 3
      3890881.74     10035755.52      3883381.73     10034531.55
      3877602.85     10031616.08
#Sta/Elev= 30
 -1714.9  101.88  -539.7   99.45    43.6   74.28   281.2    72.9   330.6   60.42
  1227.4   58.64  1338.9   73.91  1622.6    59.7  3424.4   71.61  3629.7   70.62
  4492.7   73.48  4621.5   58.71  4824.4   59.58  4998.1    53.3 5137.0359.23381
  5240.6    62.5  5884.5   65.29  6057.1   55.56    6124   68.57  7429.8    76.4
  7674.7   75.75  7883.7   72.22  8523.7   77.98  8759.1   78.47 10384.4   81.32
 10722.5   83.79 11081.5   84.42 11257.6   82.74 11468.3   85.98   12357   97.07
#Mann= 20 ,-1 , 0
 -1714.9     .11       0    43.6     .15       0   281.2     .11       0
  3424.4     .15       0  3629.7     .11       0  4621.5     .11       0
  4824.4     .06       0 5137.03     .11       0  5240.6     .17       0
  5884.5     .15       0  7429.8     .11       0  7674.7     .17       0
  7883.7     .15       0  8523.7     .17       0  8759.1     .15       0
 10384.4     .11       0 10722.5     .17       0 11081.5     .11       0
 11257.6     .17       0 11468.3     .11       0
#Block Obstruct= 1 ,-1
    -230  2797.9   74.92
Bank Sta=4824.4,5137.03
XS Rating Curve= 0 ,0
Exp/Cntr=0.3,0.1

Type RM Length L Ch R = 1 ,135663  ,2663,2663,2663
BEGIN DESCRIPTION:
WFSJ Main 137.0
END DESCRIPTION:
XS GIS Cut Line= 3
      3891116.08     10035416.96      3882965.06     10032109.68
       3877731.8     10029662.28
#Sta/Elev= 30
 -3394.6   92.46 -1712.1    89.9 -1506.7   77.24 -1163.7   71.55  -452.1   59.35
  -163.5   67.62   -10.7   59.94  1092.9   79.25  1582.7   68.96  1636.3   84.37
  3578.3   58.21  3823.2   85.62  3918.5   63.61  4162.3   52.41  4877.5   58.11
    4998   49.55  5075.1   58.64  5125.4   79.99  5320.3      80    5566    78.7
  5716.9   79.38  6594.1   76.57  6724.3   78.46  6833.7   80.05  7677.5   80.63
  8542.9   83.04  9121.3   77.05  9626.8   78.12  9826.6   86.16 11179.1   94.81
#Mann= 20 ,-1 , 0
 -3394.6     .11       0 -1506.7     .15       0 -1163.7     .11       0
  -452.1     .11       0  -163.5     .15       0   -10.7     .11       0
  4877.5     .06       0  5075.1     .11       0  5125.4     .11       0
  5320.3     .17       0    5566     .17       0  5716.9     .11       0
  6594.1     .17       0  6724.3     .11       0  6833.7     .17       0
  7677.5     .15       0  8542.9     .15       0  9121.3     .11       0
  9626.8    .125       0  9826.6     .11       0
#Block Obstruct= 1 ,-1
   -1750  3823.2   85.62
Bank Sta=4877.5,5075.1
XS Rating Curve= 0 ,0
Exp/Cntr=0.3,0.1

Type RM Length L Ch R = 1 ,133000  ,2000,2000,2000
BEGIN DESCRIPTION:
WFSJ Main 133.0
END DESCRIPTION:
XS GIS Cut Line= 3
      3891852.24     10035080.18      3885403.31     10031781.77
      3879377.57     10027852.24
#Sta/Elev= 30
 -2243.5   92.69 -1373.8    90.7    -981    89.5  -307.1   91.73   464.7   59.64
  1580.3   60.61  1748.8   87.43  2224.9   65.76  2663.5   81.08  3601.8   74.19
  3680.7    52.9  3936.9   53.68  4714.1   60.05    4998   51.34 5184.63   60.16
  5276.1   60.19  5618.2   58.26  6364.3   75.58  6539.9   75.82  7178.5   77.38
  7499.7   77.33  7848.1   79.57  8155.8   77.86  8955.7   76.69  9237.2   77.44
  9427.4   77.95 10056.5   79.08 10280.6      79 10575.4   78.89 12193.8   89.72
#Mann= 20 ,-1 , 0
 -2243.5     .11       0 -1373.8     .17       0    -981     .11       0
  3936.9     .11       0  4714.1     .06       0 5184.63     .11       0
  5276.1     .11       0  5618.2     .11       0  6364.3     .17       0
  6539.9     .11       0  7178.5     .17       0  7499.7     .15       0
  7848.1     .17       0  8155.8     .15       0  8955.7     .17       0
  9237.2     .11       0  9427.4     .17       0 10056.5     .17       0
 10280.6     .17       0 10575.4     .11       0
#XS Ineff= 1 ,-1
    2844  3601.8   74.19
Permanent Ineff=
       F
#Block Obstruct= 2 ,-1
    -298  1748.8   87.43    1750  2663.5   81.08
Bank Sta=4714.1,5184.63
XS Rating Curve= 0 ,0
Exp/Cntr=0.3,0.1

Type RM Length L Ch R = 1 ,131000  ,2402,2402,2402
BEGIN DESCRIPTION:
WFSJ Main 131.0
END DESCRIPTION:
XS GIS Cut Line= 3
      3892624.81     10034450.84      3886066.14     10030386.69
      3880641.41      10027284.5
#Sta/Elev= 30
 -2715.8   91.82 -1801.8   89.78 -1658.6   81.29   -1622   59.26   255.4   59.35
     304   59.36   347.5   71.99   463.3   60.11  3463.1   64.68  3515.1   52.12
  4655.2   61.24    4998   50.46 5108.4160.92697  5228.5   68.94  5541.5   68.23
  5713.7   67.73  5871.4   67.93  6097.7   69.05  6350.5   76.06  6893.1   75.47
  7128.9   76.52  7684.8   78.98  7972.9   75.72  8212.5    73.6  9151.3   77.71
  9436.3   77.69  9686.3    77.2 10586.3   80.96 10687.1   82.18 11249.1   88.95
#Mann= 20 ,-1 , 0
 -2715.8     .11       0   255.4     .11       0  4655.2     .06       0
 5108.41     .11       0  5228.5     .15       0  5541.5     .17       0
  5713.7     .15       0  5871.4     .15       0  6097.7     .15       0
  6350.5     .17       0  6893.1     .11       0  7128.9     .11       0
  7684.8     .17       0  7972.9     .17       0  8212.5     .15       0
  9151.3     .17       0  9436.3     .11       0  9686.3     .11       0
 10586.3    .125       0 10687.1     .11       0
#Block Obstruct= 1 ,-1
   -1760   347.5   71.99
Bank Sta=4655.2,5108.41
XS Rating Curve= 0 ,0
Exp/Cntr=0.3,0.1

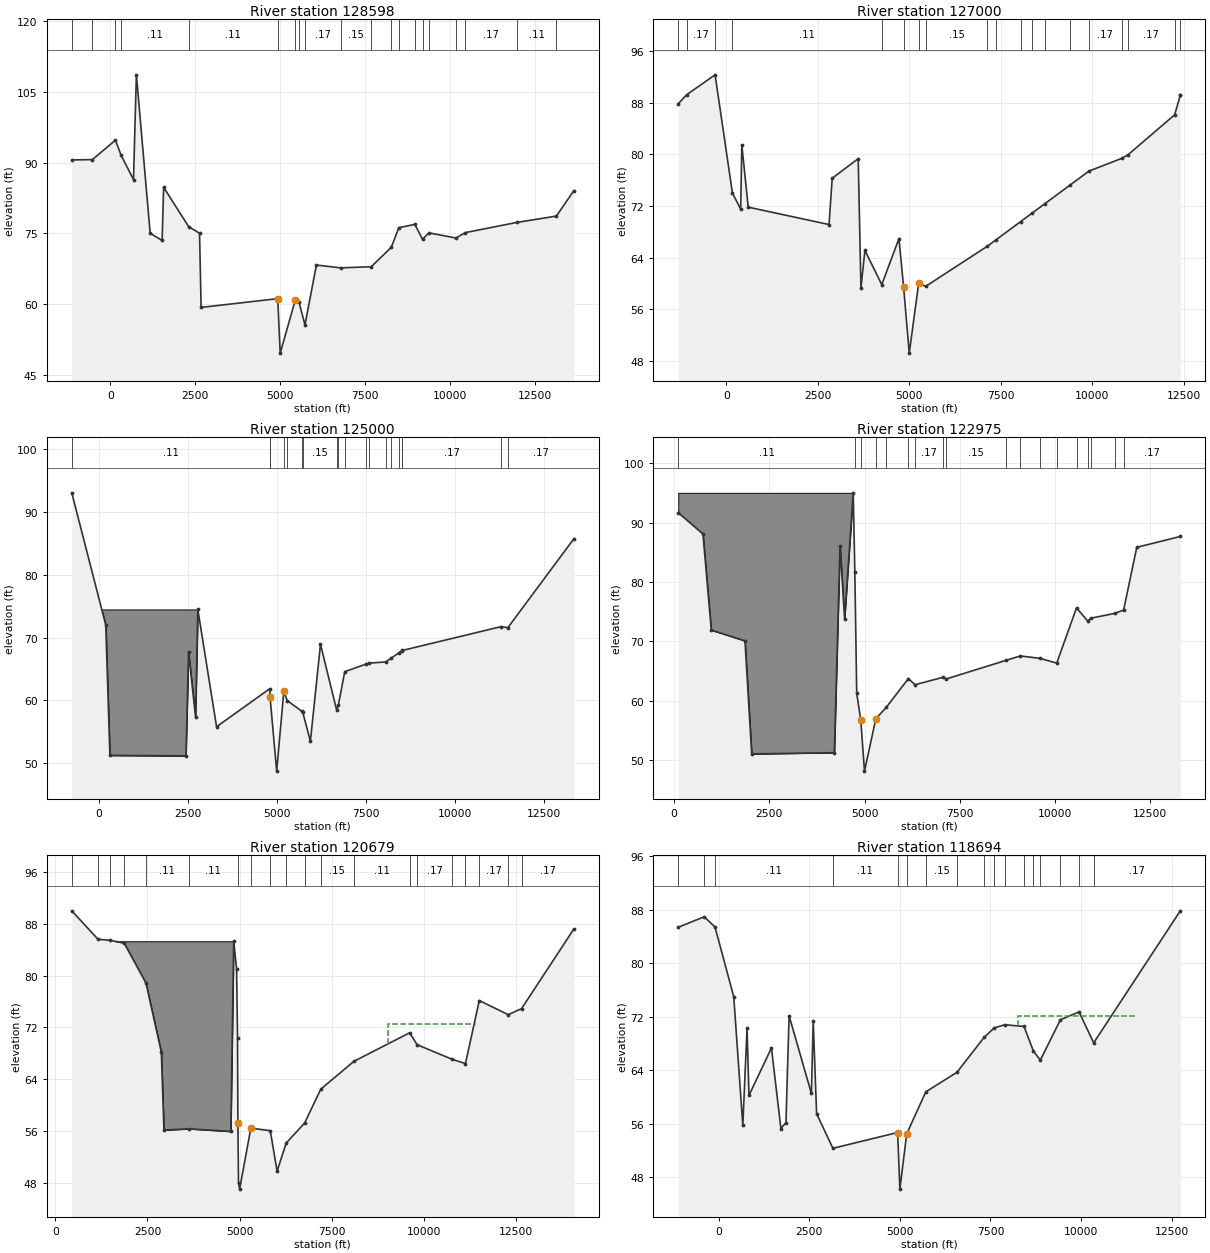
Type RM Length L Ch R = 1 ,128598  ,1598,1598,1598
BEGIN DESCRIPTION:
WFSJ Main 129.0
END DESCRIPTION:
XS GIS Cut Line= 3
      3893709.89     10033452.58      3888412.11     10031059.33
      3881177.45     10025782.14
#Sta/Elev= 30
 -1133.1   90.56  -525.5   90.63     151   94.75   320.4   91.51   682.7    86.4
   767.5   108.6  1173.5      75  1524.6    73.5  1568.5   84.75  2306.3   76.41
  2625.4   75.02  2671.6    59.3    4925   61.16    4998   49.61  5440.5   60.85
    5550   60.43  5726.1   55.59  6062.9   68.28  6782.6   67.68  7677.8   67.93
  8266.5   72.06  8486.3   76.19  8957.7    76.9  9184.8   73.75  9372.6    75.1
   10167   74.01 10442.6   75.15 11948.7    77.3 13121.9   78.66   13635   84.05
#Mann= 20 ,-1 , 0
 -1133.1     .17       0  -525.5     .15       0     151     .17       0
   320.4     .11       0  2306.3     .11       0    4925     .06       0
  5440.5     .11       0    5550     .11       0  5726.1     .17       0
  6782.6     .15       0  7677.8     .17       0  8266.5     .17       0
  8486.3     .11       0  8957.7     .17       0  9184.8     .15       0
  9372.6     .17       0   10167     .15       0 10442.6     .17       0
 11948.7     .11       0 13121.9     .11       0
Bank Sta=4925,5440.5
XS Rating Curve= 0 ,0
Exp/Cntr=0.3,0.1

Type RM Length L Ch R = 1 ,127000  ,2000,2000,2000
BEGIN DESCRIPTION:
WFSJ Main 127.0
END DESCRIPTION:
XS GIS Cut Line= 3
      3894739.98     10032907.15      3889252.05     10029783.15
       3883384.9     10025265.18
#Sta/Elev= 30
 -1314.8    87.8 -1087.2   89.19  -307.8   92.28   165.5   74.02   390.9   71.52
   422.6   81.41   597.8   71.82  2806.2   69.13  2892.6   76.29  3603.1   79.32
    3678   59.32  3786.1   65.14  4246.7   59.85  4717.2   66.96  4843.7   59.48
    4998   49.25  5254.4   60.02  5448.3   59.58  7130.6   65.77  7359.5   66.73
  8040.3   69.58  8358.1   70.91  8706.7   72.37  9403.2   75.28  9906.4   77.39
 10798.2   79.35 10968.5   79.88   12250    86.1 12403.8   89.09 12405.1   89.12
#Mann= 19 ,-1 , 0
 -1314.8     .15       0 -1087.2     .17       0  -307.8     .15       0
   165.5     .11       0  4246.7     .11       0  4843.7     .06       0
  5254.4     .11       0  5448.3     .15       0  7130.6     .11       0
  7359.5     .17       0  8040.3     .17       0  8358.1     .17       0
  8706.7     .17       0  9403.2     .11       0  9906.4     .17       0
 10798.2     .15       0 10968.5     .17       0   12250     .11       0
 12403.8     .17       0
#XS Ineff= 1 ,-1
    -175  3603.1   79.32
Permanent Ineff=
       F
Bank Sta=4843.7,5254.4
XS Rating Curve= 0 ,0
Exp/Cntr=0.3,0.1

Type RM Length L Ch R = 1 ,125000  ,2025,2025,2025
BEGIN DESCRIPTION:
WFSJ Main 125.0
END DESCRIPTION:
XS GIS Cut Line= 3
       3895906.6     10032240.46      3890981.84     10029269.33
       3884741.4     10023741.75
#Sta/Elev= 30
  -751.6   93.08   202.1   72.01   318.6   51.24  2451.9   51.16  2525.7   67.72
  2721.7   57.34  2785.8    74.5  3311.2    55.8  4806.1   61.87  4812.3   60.55
    4998   48.73  5198.8   61.48    5292   59.98  5708.9   58.25  5726.3   58.19
  5943.6   53.48  6227.1   68.93    6679    58.5  6728.6   59.25  6908.7   64.58
  7493.4   65.76  7583.1   65.94  8058.6   66.13  8205.5   66.71  8429.8   67.59
  8515.7   67.93  8523.4   67.96 11282.6   71.74 11486.3    71.6 13336.5   85.76
#Mann= 19 ,-1 , 0
  -751.6     .11       0  4806.1     .08       0  4812.3     .06       0
  5198.8     .11       0    5292     .11       0  5708.9     .17       0
  5726.3     .15       0    6679     .17       0  6728.6     .11       0
  6908.7     .15       0  7493.4     .17       0  7583.1     .15       0
  8058.6     .17       0  8205.5     .11       0  8429.8     .17       0
  8515.7     .11       0  8523.4     .17       0 11282.6     .15       0
 11486.3     .17       0
#Block Obstruct= 1 ,-1
    -175  2785.8    74.5
Bank Sta=4812.3,5198.8
XS Rating Curve= 0 ,0
Exp/Cntr=0.3,0.1

Type RM Length L Ch R = 1 ,122975  ,2296,2296,2296
BEGIN DESCRIPTION:
WFSJ Main 123.0
END DESCRIPTION:
XS GIS Cut Line= 3
      3896260.75     10031886.28      3891969.11      10027698.8
      3886205.33     10023402.72
#Sta/Elev= 30
     107   91.69   756.2    88.1   975.5   71.89  1859.4   70.08  2036.3   51.02
  4207.1   51.23  4355.7   86.12  4475.9   73.73  4702.2   95.03  4744.7   81.74
  4794.1   61.22  4900.3   56.79    4998   48.12  5296.2   56.96  5567.5   58.85
  6150.1   63.71  6324.6   62.68    7062   63.94  7147.4   63.66  8723.4   66.81
  9089.9   67.53  9600.2   67.14 10046.9   66.33 10565.9   75.64 10856.8   73.44
 10956.4   73.92 11566.7    74.7 11803.3   75.28 12147.9   85.84 13291.8   87.67
#Mann= 18 ,-1 , 0
     107     .11       0  4744.7     .11       0  4900.3     .06       0
  5296.2     .11       0  5567.5     .11       0  6150.1     .11       0
  6324.6     .17       0    7062     .17       0  7147.4     .15       0
  8723.4     .17       0  9089.9     .15       0  9600.2     .17       0
 10046.9     .15       0 10565.9     .17       0 10856.8     .11       0
 10956.4     .17       0 11566.7     .11       0 11803.3     .17       0
#Block Obstruct= 1 ,-1
     107  4702.2   95.03
Bank Sta=4900.3,5296.2
XS Rating Curve= 0 ,0
Exp/Cntr=0.3,0.1

Type RM Length L Ch R = 1 ,120679  ,1985,1985,1985
BEGIN DESCRIPTION:
WFSJ Main 121.0
END DESCRIPTION:
XS GIS Cut Line= 3
      3898635.81     10028782.14      3893969.11     10027365.47
      3886261.79     10023241.01
#Sta/Elev= 30
   446.1   89.97  1157.9   85.59  1489.6   85.42  1864.5   85.02  2457.3   78.86
  2875.3    68.2  2946.3   56.19    3624   56.38  4760.1   55.98  4838.8   85.28
  4916.8   81.02  4942.6   70.41 4952.27   57.34  4969.1   48.11    4998   47.09
  5303.5   56.49    5830   56.09    6016   49.86  6262.2   54.19  6761.6   57.27
  7200.1   62.49  8098.2   66.78  9611.9   71.18  9813.3   69.34 10764.7   67.09
   11125   66.44 11499.5   76.15 12284.6   73.97 12647.7   74.91 14064.6   87.17
#Mann= 20 ,-1 , 0
   446.1     .17       0  1157.9     .11       0  1489.6     .15       0
  1864.5     .17       0  2457.3     .11       0    3624     .11       0
 4952.27     .06       0  5303.5     .11       0    5830     .15       0
  6262.2     .15       0  6761.6     .11       0  7200.1     .15       0
  8098.2     .11       0  9611.9     .11       0  9813.3     .17       0
 10764.7     .15       0   11125     .11       0 11499.5     .17       0
 12284.6     .15       0 12647.7     .17       0
#XS Ineff= 1 ,-1
    9013   11400    72.6
Permanent Ineff=
       F
#Block Obstruct= 1 ,-1
     900  4838.8   85.28
Bank Sta=4952.27,5303.5
XS Rating Curve= 0 ,0
Exp/Cntr=0.3,0.1

Type RM Length L Ch R = 1 ,118694  ,1248,1248,1248
BEGIN DESCRIPTION:
WFSJ Main 119.0
END DESCRIPTION:
XS GIS Cut Line= 4
      3899849.35     10026207.92      3896322.84       10026056.
      3893760.78      10025698.8      3886427.43     10023198.79
#Sta/Elev= 30
 -1122.2   85.38  -402.4   86.94  -106.8   85.41   410.7      75     661   55.77
   777.8   70.31   831.1   60.25  1451.7   67.34  1712.9    55.3  1852.1   56.19
  1939.2   72.15  2555.5   60.54  2604.5   71.39  2698.6   57.53  3149.1   52.35
 4936.36   54.71    4998   46.25  5186.454.49432  5713.2   60.78  6575.3   63.71
  7326.1   68.93    7604   70.34  7898.3   70.81  8426.9   70.55  8682.3   66.92
    8876   65.51  9431.4   71.56    9946   72.73 10350.3   68.11 12742.2   87.83
#Mann= 17 ,-1 , 0
 -1122.2     .11       0  -402.4     .17       0  -106.8     .11       0
  3149.1     .11       0 4936.36     .06       0  5186.4     .11       0
  5713.2     .15       0  6575.3     .11       0  7326.1     .17       0
    7604     .17       0  7898.3     .17       0  8426.9     .11       0
  8682.3     .15       0    8876     .17       0  9431.4     .15       0
    9946     .17       0 10350.3     .17       0
#XS Ineff= 3 ,-1
     145  1939.2   72.15  1939.3  2604.5   71.39  8251.6   11500   72.05
Permanent Ineff=
       F       F       F
Bank Sta=4936.36,5186.4
XS Rating Curve= 0 ,0
Exp/Cntr=0.3,0.1