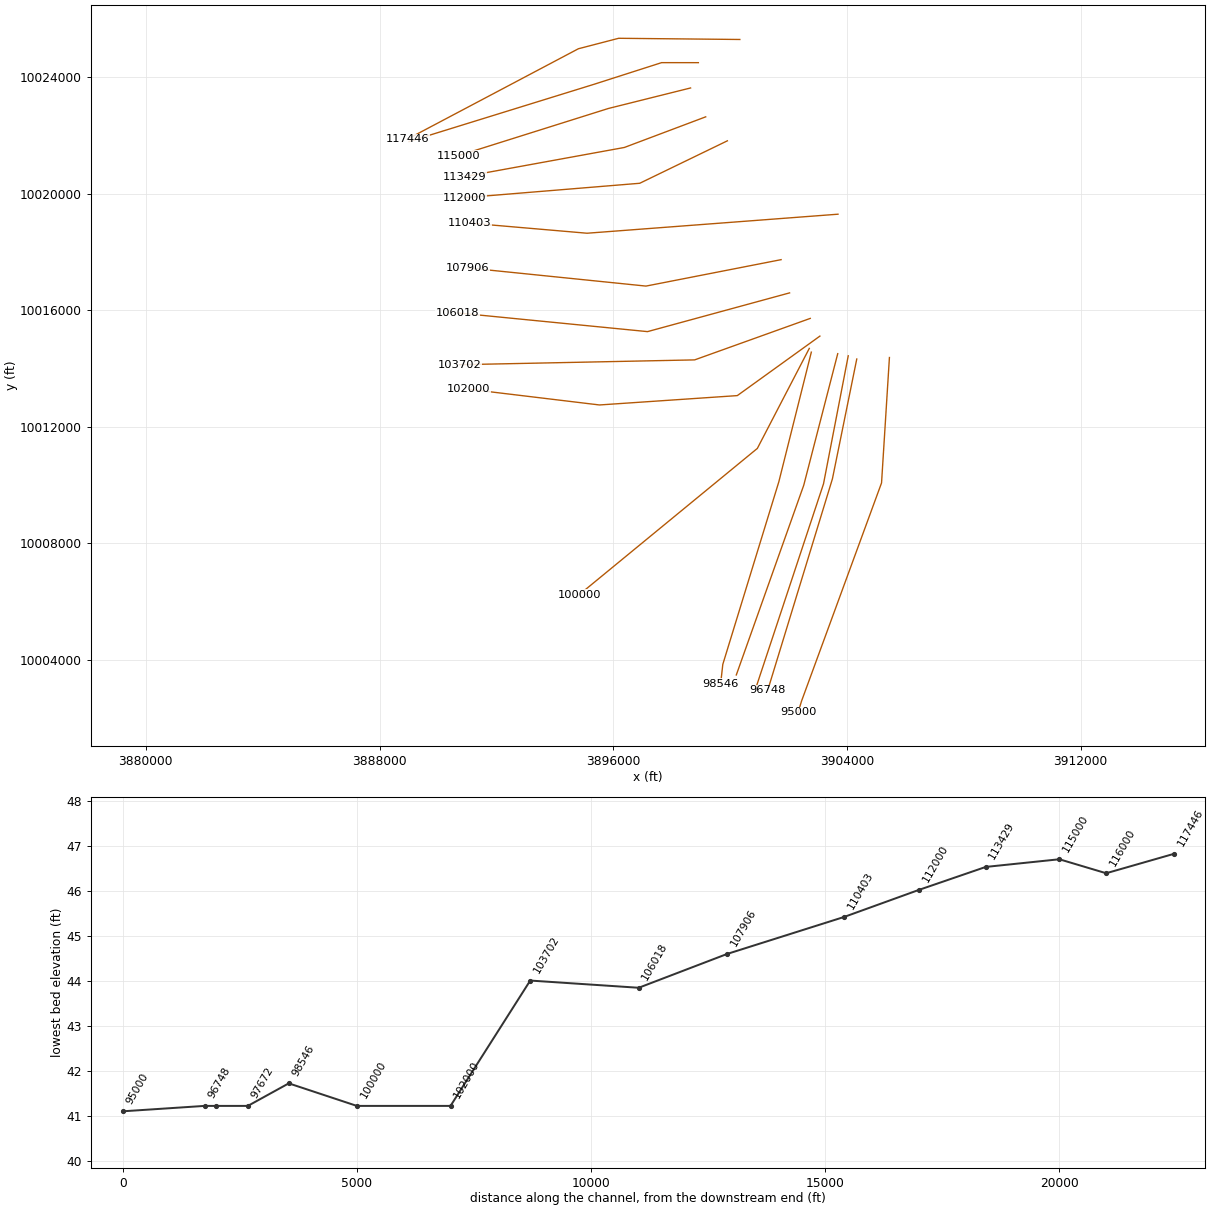
HEC-RAS study WFSJ Main.prj: WFSJ Main Base Level Engineering

--- WFSJ Main.g01 (geometry) --- (continued)

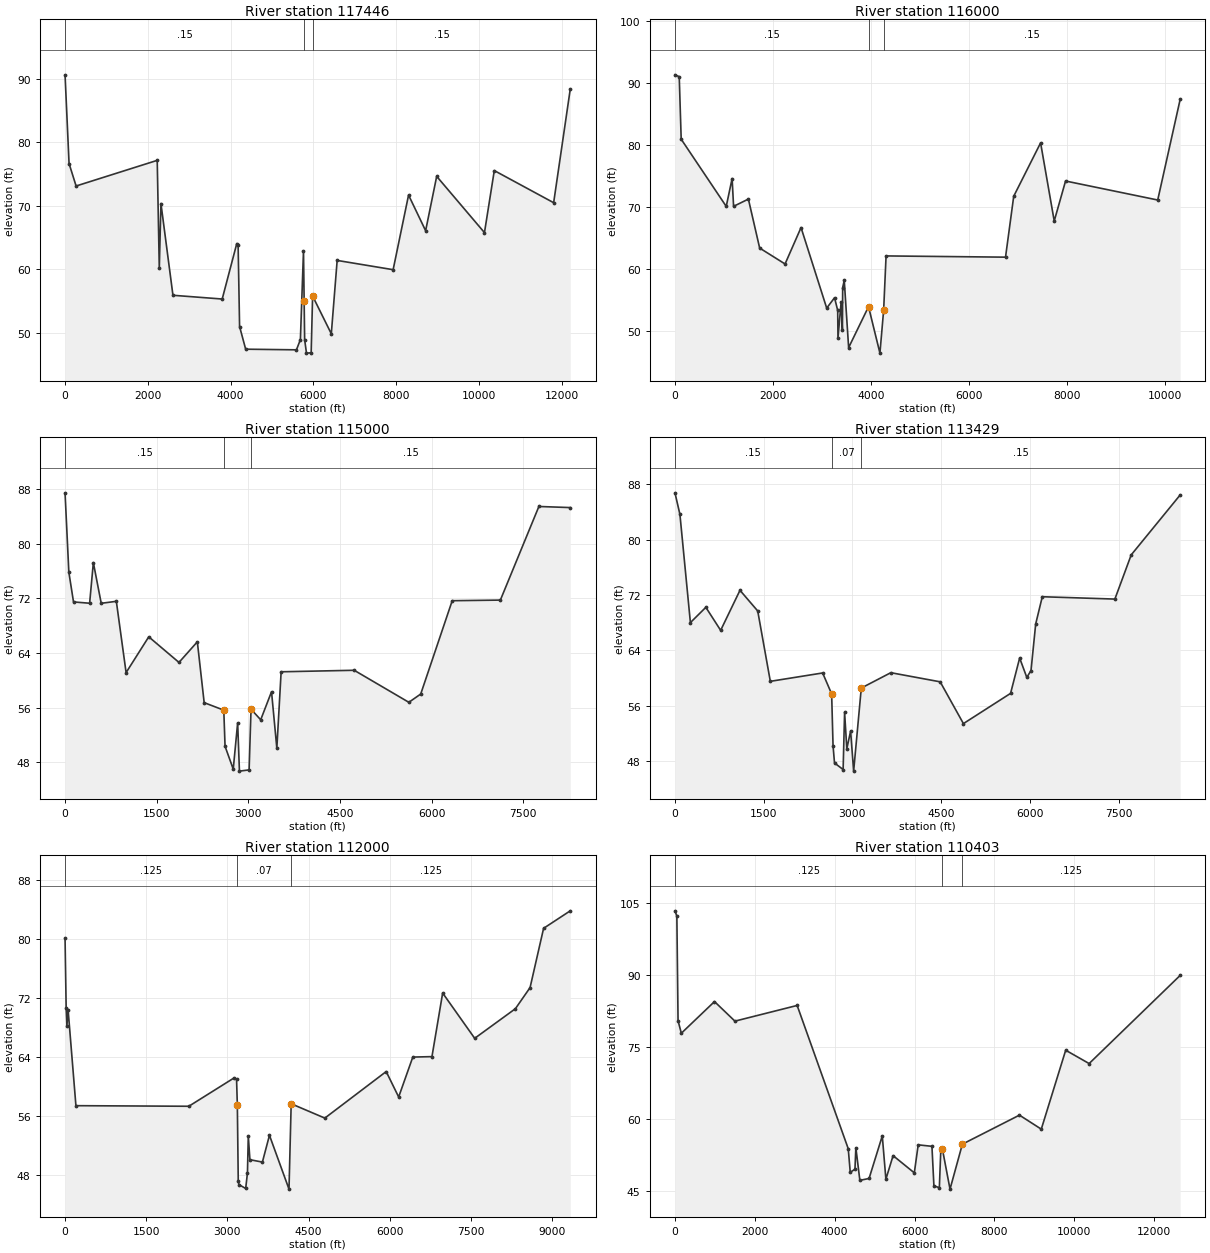
Type RM Length L Ch R = 1 ,117446  ,1446,1446,1446
BEGIN DESCRIPTION:
WFSJ Main 118.0
END DESCRIPTION:
XS GIS Cut Line= 4
      3900334.77     10025293.19      3896185.97     10025333.94
      3894808.16     10024975.02      3888946.21     10021869.59
#Sta/Elev= 30
       0   90.65    96.9   76.68   266.9   73.14    2227   77.18    2277   60.18
    2317   70.38    2607   55.93  3797.1   55.34    4149   64.07  4181.7   63.83
    4217   51.01  4364.1   47.44    5591   47.34  5686.3   48.95  5761.3   62.93
  5776.8   55.07    5789   48.94  5833.4   46.82  5946.6   46.87  5981.3   55.81
  6433.2   49.87  6574.6   61.42    7927   59.96  8299.8   71.71  8712.1    66.1
  8979.4   74.66 10133.7    65.8 10371.3   75.57 11805.5   70.51 12206.5   88.39
#Mann= 3 , 0 , 0
       0     .15       0  5776.8     .06       0  5981.3     .15       0
#XS Ineff= 2 ,-1
  8299.8    8910   71.71  8979.4   10350   74.66
Permanent Ineff=
       F       F
Bank Sta=5776.8,5981.3
XS Rating Curve= 0 ,0
Exp/Cntr=0.3,0.1

Type RM Length L Ch R = 1 ,116000  ,1000,1000,1000
BEGIN DESCRIPTION:
WFSJ Main 116.0
END DESCRIPTION:
XS GIS Cut Line= 4
      3898915.28     10024497.47      3897656.34      10024498.4
       3895348.1     10023756.89      3889010.06     10021791.03
#Sta/Elev= 30
       0   91.34    87.4   91.04   127.4   80.94  1047.4   70.09  1167.4   74.59
  1197.4    70.1  1499.8   71.27    1730   63.36  2248.7   60.79    2575   66.67
  3099.1   53.66  3259.6   55.34  3323.8   53.28  3329.1   48.79  3393.3   54.59
  3420.1   50.11  3425.4   56.98  3457.5   58.13  3547.1   47.28  3953.4   53.89
  4186.2   46.39  4262.3   53.35  4311.8   62.09  6751.3   61.89  6918.8   71.73
  7467.6   80.35    7746   67.73  7977.3   74.19  9859.6   71.12 10317.8   87.37
#Mann= 3 , 0 , 0
       0     .15       0  3953.4     .06       0  4262.3     .15       0
#XS Ineff= 1 ,-1
  7467.6   10180   80.35
Permanent Ineff=
       F
Bank Sta=3953.4,4262.3
XS Rating Curve= 0 ,0
Exp/Cntr=0.3,0.1

Type RM Length L Ch R = 1 ,115000  ,1571,1571,1571
BEGIN DESCRIPTION:
WFSJ Main 115.0
END DESCRIPTION:
XS GIS Cut Line= 3
      3898647.98     10023629.51      3895836.29      10022926.1
      3890715.72     10021310.91
#Sta/Elev= 30
       0   87.46      62   75.84   138.5   71.48   402.2   71.29   463.1   77.24
   591.9   71.28   839.3   71.57     999   61.13  1369.9   66.37  1864.6   62.62
  2164.9   65.64  2276.7   56.73  2597.8   55.63  2618.4   50.34  2752.4   46.99
  2824.6   53.77  2853.8    46.7  3012.1   46.88  3043.5   55.77  3201.8   54.22
    3379   58.33  3465.9   50.05  3536.3   61.25  4731.9   61.47  5626.3   56.78
  5820.4   57.99    6336   71.66    7124   71.75  7754.3   85.46  8267.6    85.3
#Mann= 3 , 0 , 0
       0     .15       0  2597.8     .07       0  3043.5     .15       0
Bank Sta=2597.8,3043.5
XS Rating Curve= 0 ,0
Exp/Cntr=0.3,0.1

Type RM Length L Ch R = 1 ,113429  ,1429,1429,1429
BEGIN DESCRIPTION:
WFSJ Main 113.0
END DESCRIPTION:
XS GIS Cut Line= 3
      3899166.31     10022638.59      3896381.44     10021587.69
      3890907.46     10020587.64
#Sta/Elev= 30
       0   86.76    83.9   83.65   261.1      68   522.2   70.21   772.6   66.88
  1099.3   72.67  1399.4   69.68  1612.3   59.51  2496.9   60.72  2649.1   57.69
  2672.7   50.22  2697.5   47.71  2843.2   46.76    2868   55.04  2905.6   49.77
  2969.7   52.32  3020.9   46.53  3150.2   58.54  3649.7   60.76  4483.8   59.44
  4876.7    53.4  5674.1   57.77  5827.5   62.88  5948.5   60.08  6019.7   61.07
  6098.7    67.8  6210.3   71.74  7437.4    71.4  7713.7   77.79  8541.1   86.45
#Mann= 3 , 0 , 0
       0     .15       0  2649.1     .07       0  3150.2     .15       0
Bank Sta=2649.1,3150.2
XS Rating Curve= 0 ,0
Exp/Cntr=0.3,0.1

Type RM Length L Ch R = 1 ,112000  ,1597,1597,1597
BEGIN DESCRIPTION:
WFSJ Main 112.0
END DESCRIPTION:
XS GIS Cut Line= 3
      3899908.72     10021816.18      3896908.23     10020358.96
      3890925.97     10019865.76
#Sta/Elev= 30
       0   80.12    20.4   70.69    34.3   68.26    56.6   70.39   200.9   57.37
  2287.4   57.29  3116.3   61.11  3169.3   61.01    3184   57.43    3201   47.06
  3213.8   46.63  3338.3   46.11    3371   48.24  3386.2   53.27  3416.3   50.02
  3647.1    49.7  3777.5   53.34  4138.7   46.02  4178.9   57.63    4801   55.68
  5934.8   62.01  6165.3   58.55  6426.5   63.98  6780.6   64.04  6978.3   72.69
  7570.3   66.53  8322.9   70.56  8593.8   73.43  8843.6   81.49  9336.3   83.87
#Mann= 3 , 0 , 0
       0    .125       0    3184     .07       0  4178.9    .125       0
Bank Sta=3184,4178.9
XS Rating Curve= 0 ,0
Exp/Cntr=0.3,0.1

Type RM Length L Ch R = 1 ,110403  ,2497,2497,2497
BEGIN DESCRIPTION:
WFSJ Main 111.0
END DESCRIPTION:
XS GIS Cut Line= 3
      3903695.26     10019297.95      3895105.39     10018644.98
      3891082.71     10018992.26
#Sta/Elev= 30
       0  103.42    47.5  102.33    77.6   80.51   159.8   77.91   990.3   84.51
  1501.7   80.43  3060.2    83.7  4339.9   53.84    4390   48.93  4507.9   49.56
  4530.4   54.05  4630.7   47.25  4861.4   47.64  5192.3   56.51  5282.6   47.49
  5463.1    52.4  5994.7   48.81  6091.7   54.65  6435.9   54.34  6485.2   46.12
  6621.4   45.71  6656.6   53.33  6696.7   53.83  6888.7   45.42  7198.1   54.79
  8627.3   60.84  9174.3   57.92  9785.7   74.37 10372.5   71.59 12652.2   89.96
#Mann= 3 , 0 , 0
       0    .125       0  6696.7     .06       0  7198.1    .125       0
Bank Sta=6696.7,7198.1
XS Rating Curve= 0 ,0
Exp/Cntr=0.3,0.1

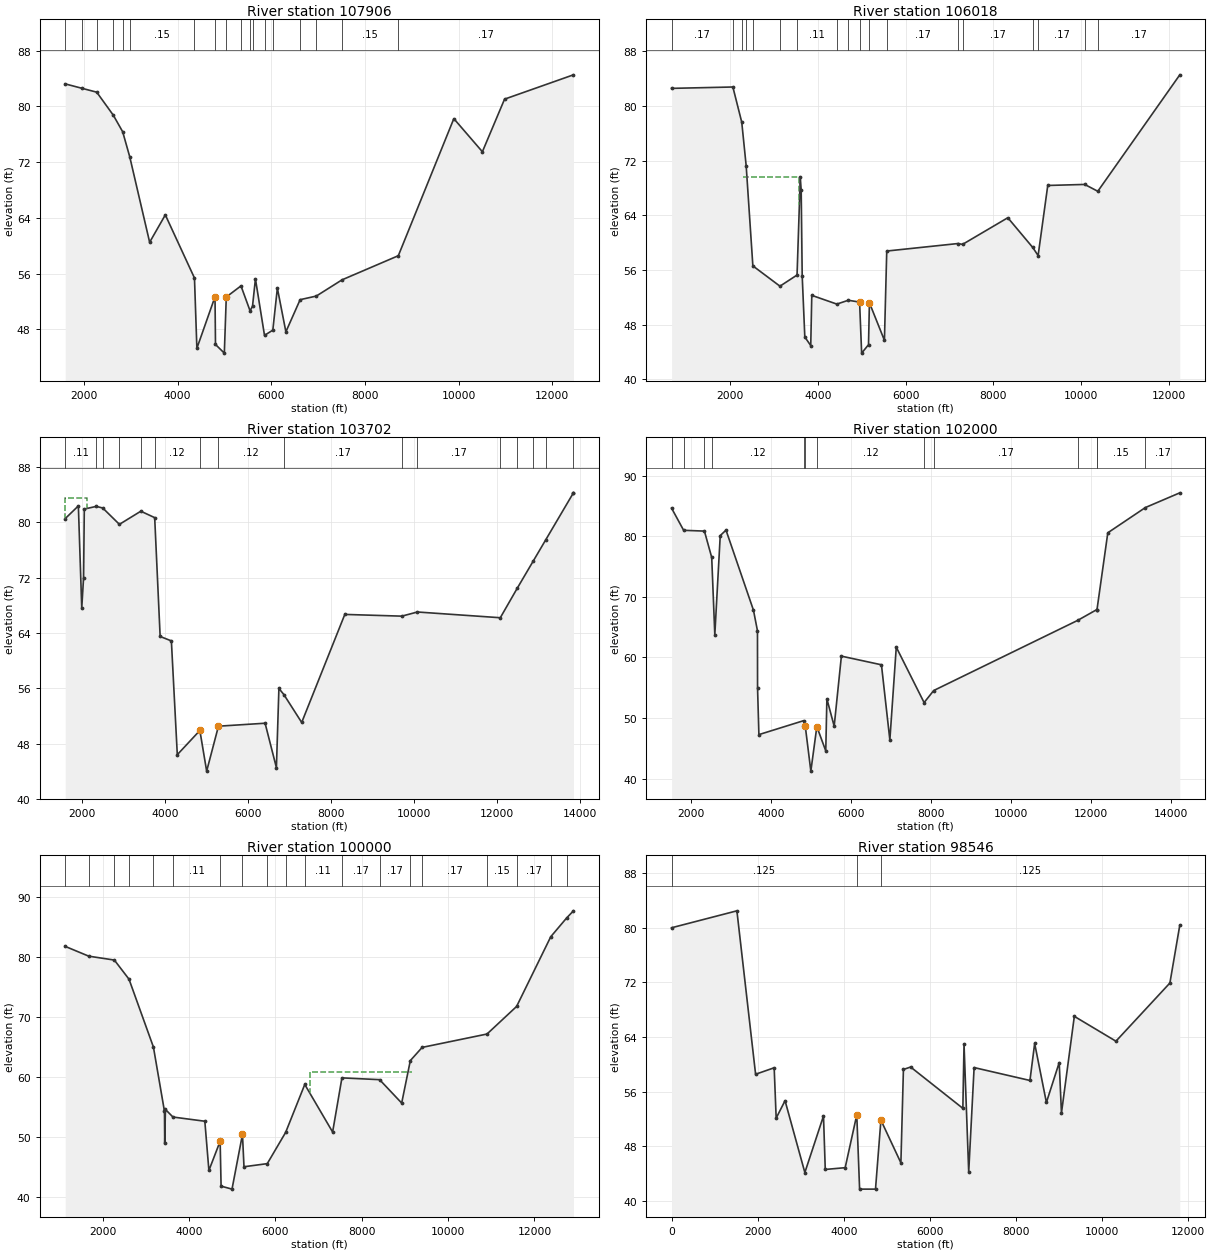
Type RM Length L Ch R = 1 ,107906  ,1888,1888,1888
BEGIN DESCRIPTION:
WFSJ Main 108.0
END DESCRIPTION:
XS GIS Cut Line= 3
      3901747.51     10017738.05      3897122.27     10016831.34
      3891013.31     10017456.12
#Sta/Elev= 30
  1599.7   83.24  1950.2   82.62  2272.9   82.05  2627.5   78.74    2827   76.37
  2977.9   72.78    3403   60.51  3737.7   64.44  4360.4   55.38  4411.9   45.29
  4799.1   52.69  4809.3   45.84    4998    44.6  5039.7   52.65  5353.6   54.25
  5547.7   50.67  5599.9   51.33  5662.4   55.25  5856.1   47.15  6033.7    47.9
  6130.7   53.93  6312.7   47.66  6616.8   52.27  6962.4   52.79  7512.4   55.12
  8713.9   58.58  9899.4   78.25 10509.2    73.5 10982.8   81.05 12453.8   84.54
#Mann= 18 ,-1 , 0
  1599.7     .15       0  1950.2    .125       0  2272.9     .11       0
  2627.5     .17       0    2827     .11       0  2977.9     .15       0
  4360.4     .11       0  4799.1     .06       0  5039.7     .11       0
  5353.6     .17       0  5547.7     .15       0  5599.9     .17       0
  5856.1     .15       0  6033.7     .17       0  6616.8     .15       0
  6962.4     .17       0  7512.4     .15       0  8713.9     .17       0
Bank Sta=4799.1,5039.7
XS Rating Curve= 0 ,0
Exp/Cntr=0.3,0.1

Type RM Length L Ch R = 1 ,106018  ,2316,2316,2316
BEGIN DESCRIPTION:
WFSJ Main 106.0
END DESCRIPTION:
XS GIS Cut Line= 3
      3902037.53     10016598.04      3897174.35     10015268.84
      3890663.92      10015911.2
#Sta/Elev= 30
     666   82.57  2063.1   82.77  2265.5   77.62  2366.7   71.22  2518.8   56.61
  3136.3   53.64  3525.9   55.27  3599.5   69.55  3620.2   67.67 3643.18   55.15
  3702.9   46.21  3837.9   44.95  3861.7    52.3  4432.7   51.02  4693.9   51.58
  4951.251.31457    4998   43.85  5154.5   45.08  5175.2   51.22  5517.3   45.72
  5570.3   58.78  7197.7   59.88  7297.1   59.75  8329.5   63.65  8897.8    59.3
  9020.3   58.12    9240   68.37 10082.1   68.52 10380.5   67.52 12249.6   84.55
#Mann= 18 ,-1 , 0
     666     .17       0  2063.1     .11       0  2265.5     .15       0
  2366.7     .17       0  2518.8     .15       0  3136.3     .15       0
  3525.9     .11       0  4432.7     .15       0  4693.9     .12       0
  4951.2     .07       0  5175.2     .12       0  5570.3     .17       0
  7197.7     .15       0  7297.1     .17       0  8897.8     .15       0
  9020.3     .17       0 10082.1     .15       0 10380.5     .17       0
#XS Ineff= 1 ,-1
    2290  3578.7   69.63
Permanent Ineff=
       F
Bank Sta=4951.2,5175.2
XS Rating Curve= 0 ,0
Exp/Cntr=0.3,0.1

Type RM Length L Ch R = 1 ,103702  ,1702,1702,1702
BEGIN DESCRIPTION:
WFSJ Main 104.0
END DESCRIPTION:
XS GIS Cut Line= 3
       3902745.1      10015722.4      3898786.76     10014298.79
      3890733.03     10014133.16
#Sta/Elev= 30
  1585.1   80.54  1902.8   82.38  1984.3   67.61  2028.5      72  2045.7   81.92
  2334.8   82.31  2491.6   82.07  2892.7   79.71  3409.6   81.61  3744.1   80.68
  3875.7   63.49  4146.8   62.85  4289.7   46.39  4834.1   49.89    4998   44.01
  5282.5   50.51  6407.9   50.94  6680.8   44.51  6740.8   55.97  6860.3   55.09
  7290.9   51.05  8331.1   66.68  9705.6   66.43 10083.1   67.03 12082.5    66.2
 12488.5   70.44 12879.1   74.42 13179.4   77.48 13841.7   84.22 13847.1   84.27
#Mann= 16 ,-1 , 0
  1585.1     .11       0  2334.8     .15       0  2491.6     .11       0
  2892.7     .11       0  3409.6     .15       0  3744.1     .12       0
  4834.1     .07       0  5282.5     .12       0  6860.3     .17       0
  9705.6     .15       0 10083.1     .17       0 12082.5     .15       0
 12488.5     .17       0 12879.1     .15       0 13179.4     .17       0
 13841.7     .11       0
#XS Ineff= 1 ,-1
    1586  2101.9   83.45
Permanent Ineff=
       F
Bank Sta=4834.1,5282.5
XS Rating Curve= 0 ,0
Exp/Cntr=0.3,0.1

Type RM Length L Ch R = 1 ,102000  ,2000,2000,2000
BEGIN DESCRIPTION:
WFSJ Main 102.0
END DESCRIPTION:
XS GIS Cut Line= 4
      3903074.94     10015114.75      3900248.19     10013073.37
      3895529.73     10012752.25      3891061.95     10013291.74
#Sta/Elev= 30
  1513.2   84.66  1815.2      81  2335.2   80.87  2517.6   76.52  2595.1   63.75
  2730.8   80.13    2875   81.03    3562   67.81  3662.6    64.4 3664.55   54.96
  3698.2   47.26  4815.4   49.56  4858.7   48.64    4998   41.23  5148.148.58382
  5371.2   44.57  5399.2   53.17  5581.7   48.65  5762.1   60.22  6764.4   58.79
  6974.9   46.38  7135.3    61.7  7831.7   52.55    8072   54.54 11675.9   66.13
 12156.6   67.92   12158   67.92 12428.1   80.59 13368.5   84.76 14229.6   87.19
#Mann= 13 ,-1 , 0
  1513.2    .125       0  1815.2     .15       0  2335.2    .125       0
  2517.6     .12       0  4815.4     .11       0  4858.7     .07       0
  5148.1     .12       0  7831.7     .15       0    8072     .17       0
 11675.9     .15       0 12156.6     .17       0   12158     .15       0
 13368.5     .17       0
#XS Ineff= 2 ,-1
  7135.3   11000    61.7    1565    2875   81.03
Permanent Ineff=
       F       F
Bank Sta=4858.7,5148.1
XS Rating Curve= 0 ,0
Exp/Cntr=0.3,0.1

Type RM Length L Ch R = 1 ,100000  ,1454,1454,1454
BEGIN DESCRIPTION:
WFSJ Main 100.0
END DESCRIPTION:
XS GIS Cut Line= 3
      3902712.35     10014692.97      3900934.24     10011261.39
      3894831.62     10006239.11
#Sta/Elev= 30
  1135.1    81.7  1680.6   80.07  2273.5   79.42  2612.6   76.23  3177.7   64.92
  3433.6   54.21  3439.3   48.87  3455.8   54.52  3629.8   53.25  4368.3   52.55
  4462.5   44.34 4722.82   49.22  4744.6   41.73  4997.6   41.23  5239.7   50.36
  5274.8   44.96  5814.1   45.48  6239.6   50.69  6682.4   58.68  7327.3   50.75
  7542.8   59.78    8415   59.48  8926.4   55.58  9126.6   62.66  9400.2   64.86
 10902.4   67.09 11587.7   71.69 12378.2   83.31 12744.6   86.43 12903.5   87.63
#Mann= 19 ,-1 , 0
  1135.1     .15       0  1680.6     .11       0  2273.5     .15       0
  2612.6     .11       0  3177.7     .17       0  3629.8     .11       0
 4722.82     .07       0  5239.7     .11       0  5814.1     .15       0
  6239.6     .17       0  6682.4     .11       0  7542.8     .17       0
    8415     .17       0  9126.6     .11       0  9400.2     .17       0
 10902.4     .15       0 11587.7     .17       0 12378.2     .11       0
 12744.6     .17       0
#XS Ineff= 1 ,-1
  6808.7    9170    60.7
Permanent Ineff=
       F
Bank Sta=4722.82,5239.7
XS Rating Curve= 0 ,0
Exp/Cntr=0.3,0.1

Type RM Length L Ch R = 1 ,98546   ,874,874,874
BEGIN DESCRIPTION:
WFSJ Main 99.0
END DESCRIPTION:
XS GIS Cut Line= 4
       3902781.8      10014564.5      3901670.69     10010120.06
      3899752.04     10003853.38      3899677.12     10003187.33
#Sta/Elev= 30
       0      80  1517.4   82.48  1951.7   58.55  2383.3    59.5  2429.6   52.13
  2635.8   54.68  3095.9   44.16  3528.8   52.44    3570   44.61  4032.5   44.87
  4301.9    52.6  4367.5   41.73    4737   41.73  4862.5   51.83  5326.6   45.58
  5385.4   59.25  5552.8   59.61  6765.9   53.56  6793.1   62.96  6901.9   44.24
  7027.4   59.53  8324.2   57.64  8433.9   63.06  8706.5   54.42    9004   60.26
  9056.3   52.87  9355.2   67.03 10321.7   63.39 11575.1   71.91 11805.3   80.39
#Mann= 3 , 0 , 0
       0    .125       0  4301.9     .07       0  4862.5    .125       0
#XS Ineff= 2 ,-1
                          6793.1    9740   62.96
Permanent Ineff=
       F       F
Bank Sta=4301.9,4862.5
XS Rating Curve= 0 ,0
Exp/Cntr=0.3,0.1

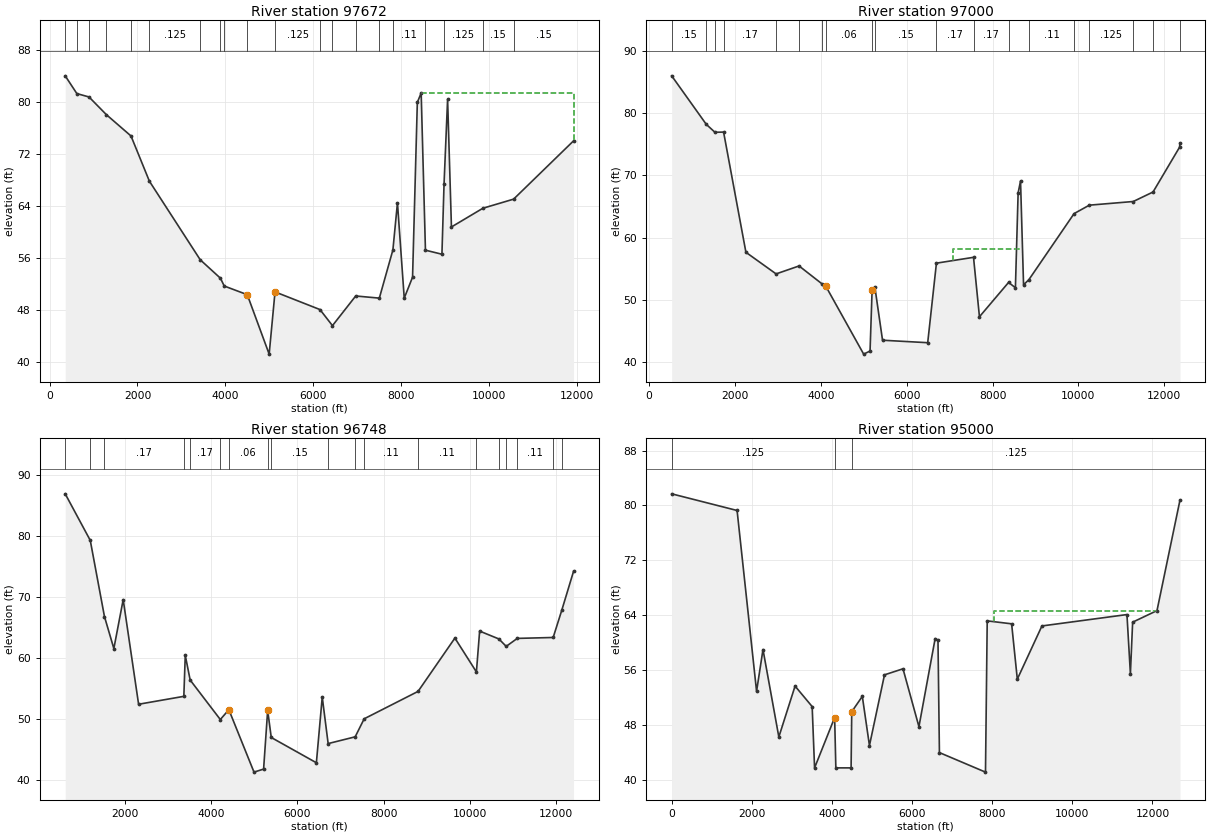
Type RM Length L Ch R = 1 ,97672   ,672,672,672
BEGIN DESCRIPTION:
WFSJ Main 98.0
END DESCRIPTION:
XS GIS Cut Line= 3
      3903685.88     10014512.43      3902522.68     10009998.53
      3900213.66     10003488.13
#Sta/Elev= 30
   355.8   84.02   620.7   81.29   897.3   80.77  1294.4   78.04  1853.4   74.77
  2271.8   67.82  3428.5   55.74  3888.9    52.9  3975.6    51.7  4499.4   50.37
  4997.6   41.23  5131.1    50.8  6154.3   48.08  6438.3   45.61  6967.4   50.17
  7505.2   49.84  7813.9   57.25  7917.5    64.5  8071.8   49.84  8261.2   53.06
    8370   79.94  8457.3   81.38  8554.6   57.21  8929.7   56.59  8977.8   67.38
  9058.8    80.4  9146.1   60.78    9862   63.66   10561   65.06 11924.9   74.02
#Mann= 20 ,-1 , 0
   355.8     .15       0   620.7    .125       0   897.3     .15       0
  1294.4     .15       0  1853.4     .15       0  2271.8    .125       0
  3428.5     .15       0  3888.9     .12       0  3975.6     .11       0
  4499.4     .07       0  5131.1    .125       0  6154.3     .11       0
  6438.3     .11       0  6967.4     .15       0  7505.2     .15       0
  7813.9     .11       0  8554.6     .11       0  8977.8    .125       0
    9862     .15       0   10561     .15       0
#XS Ineff= 2 ,-1
  7917.5    8450    64.5  8457.3   11925   81.38
Permanent Ineff=
       F       F
Bank Sta=4499.4,5131.1
XS Rating Curve= 0 ,0
Exp/Cntr=0.3,0.1

Type RM Length L Ch R = 1 ,97000   ,252,252,252
BEGIN DESCRIPTION:
WFSJ Main 97.0
END DESCRIPTION:
XS GIS Cut Line= 3
      3904045.68     10014439.49      3903198.75     10010045.16
      3900885.96     10003050.61
#Sta/Elev= 30
   524.8   86.05  1330.5   78.24  1532.4   76.96  1734.3   76.99  2254.5   57.63
  2957.5   54.15  3492.7   55.43  4020.9   52.58 4116.88   52.15  4997.6   41.23
  5146.4   41.73  5193.9   51.48  5257.1   52.09  5437.1   43.47  6489.4   43.07
  6692.7   55.88  7556.7   56.82  7694.9   47.25  8373.6   52.78  8532.7   51.92
  8595.9   67.19  8651.9   69.11  8722.3    52.4  8845.5   53.21  9899.3   63.86
 10254.7   65.22 11278.1   65.81   11739   67.34 12356.5   74.55   12367   75.25
#Mann= 19 ,-1 , 0
   524.8     .15       0  1330.5    .125       0  1532.4     .11       0
  1734.3     .17       0  2957.5     .15       0  3492.7     .17       0
  4020.9     .11       0 4116.88     .06       0  5193.9     .11       0
  5257.1     .15       0  6692.7     .17       0  7556.7     .17       0
  8373.6     .11       0  8845.5     .11       0  9899.3     .15       0
 10254.7    .125       0 11278.1     .15       0   11739     .15       0
 12356.5    .125       0
#XS Ineff= 2 ,-1
  8651.9   12205   69.11  7079.2    8650   58.23
Permanent Ineff=
       F       F
Bank Sta=4116.88,5193.9
XS Rating Curve= 0 ,0
Exp/Cntr=0.3,0.1

Type RM Length L Ch R = 1 ,96748   ,1748,1748,1748
BEGIN DESCRIPTION:
WFSJ Main 96.0
END DESCRIPTION:
XS GIS Cut Line= 3
      3904337.35      10014328.4      3903504.02     10010217.28
      3901288.73      10002960.3
#Sta/Elev= 30
   621.5   86.95  1202.3    79.3  1531.2   66.79  1748.9   61.53  1965.6   69.57
  2322.7   52.38  3371.1   53.68  3404.3   60.41  3517.9   56.36  4216.8   49.87
  4414.4   51.49  4997.6   41.23    5220   41.73  5314.1   51.37  5397.5   46.92
  6443.3   42.77  6579.2   53.56    6716   45.92  7342.7   47.03  7550.9   49.99
  8799.8   54.49    9654   63.25 10152.7   57.69 10227.4    64.4 10673.1   63.11
 10843.3   61.89 11099.9    63.2 11931.8   63.35 12130.2    67.8 12403.8   74.21
#Mann= 19 ,-1 , 0
   621.5     .17       0  1202.3     .11       0  1531.2     .17       0
  3371.1     .11       0  3517.9     .17       0  4216.8     .11       0
  4414.4     .06       0  5314.1     .11       0  5397.5     .15       0
    6716     .17       0  7342.7     .17       0  7550.9     .11       0
  8799.8     .11       0 10152.7     .11       0 10673.1     .11       0
 10843.3     .15       0 11099.9     .11       0 11931.8     .11       0
 12130.2    .125       0
#XS Ineff= 3 ,-1
    1430  1965.6   69.57    1966  3404.3   60.41    9654   12000   63.25
Permanent Ineff=
       F       F       F
Bank Sta=4414.4,5314.1
XS Rating Curve= 0 ,0
Exp/Cntr=0.3,0.1

Type RM Length L Ch R = 1 ,95000   ,2000,2000,2000
BEGIN DESCRIPTION:
WFSJ Main 95.0
END DESCRIPTION:
XS GIS Cut Line= 4
      3905455.41     10014380.47      3905185.77     10010077.86
      3902449.39     10002598.05      3902328.98     10002203.95
#Sta/Elev= 30
       0    81.7  1632.6   79.27  2118.9    52.9    2279   58.99  2674.6   46.24
  3079.5   53.66  3506.3   50.67  3566.4   41.73  4067.4   49.07  4097.4   41.73
    4478   41.73  4494.1   49.92  4758.2   52.16    4936   44.99  5311.5    55.3
  5773.3   56.18  6171.1   47.74  6575.7   60.59  6646.5   60.37  6682.3   43.96
  7832.2   41.11  7875.3   63.17  8484.4   62.74  8626.4   54.67  9240.8   62.43
 11362.7   64.09 11448.9   55.46 11504.7   62.98 12112.7   64.67 12686.7    80.8
#Mann= 3 , 0 , 0
       0    .125       0  4067.4     .06       0  4494.1    .125       0
#XS Ineff= 2 ,-1
  6575.7    7915   60.59  8055.8   12105   64.59
Permanent Ineff=
       F       F
Bank Sta=4067.4,4494.1
XS Rating Curve= 0 ,0
Exp/Cntr=0.3,0.1