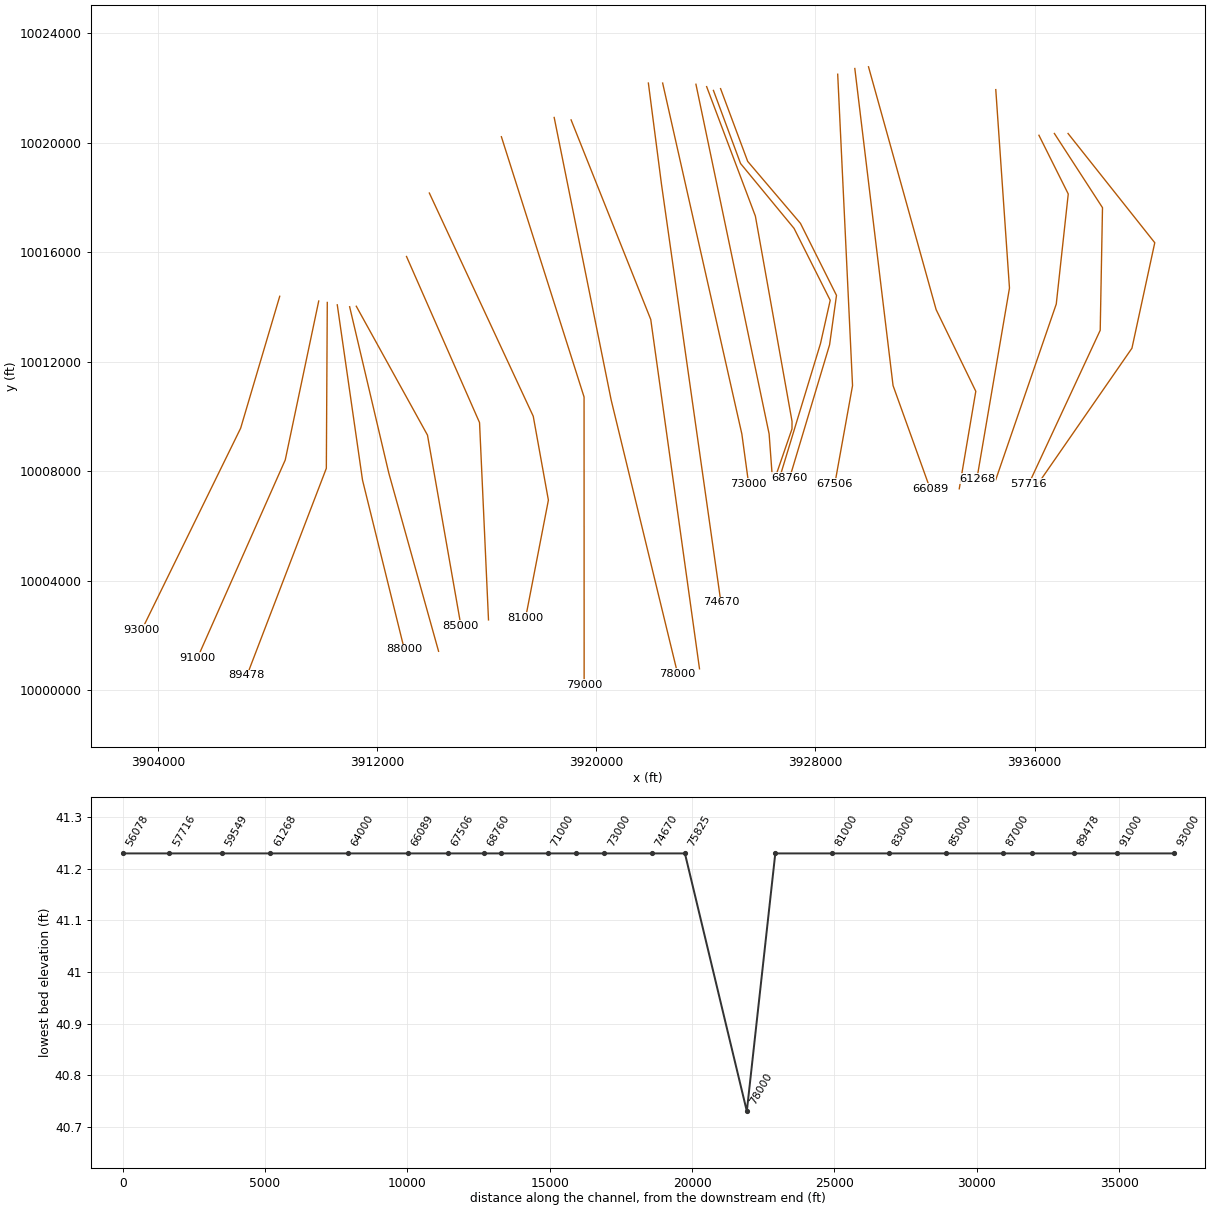
HEC-RAS study WFSJ Main.prj: WFSJ Main Base Level Engineering

--- WFSJ Main.g01 (geometry) --- (continued)

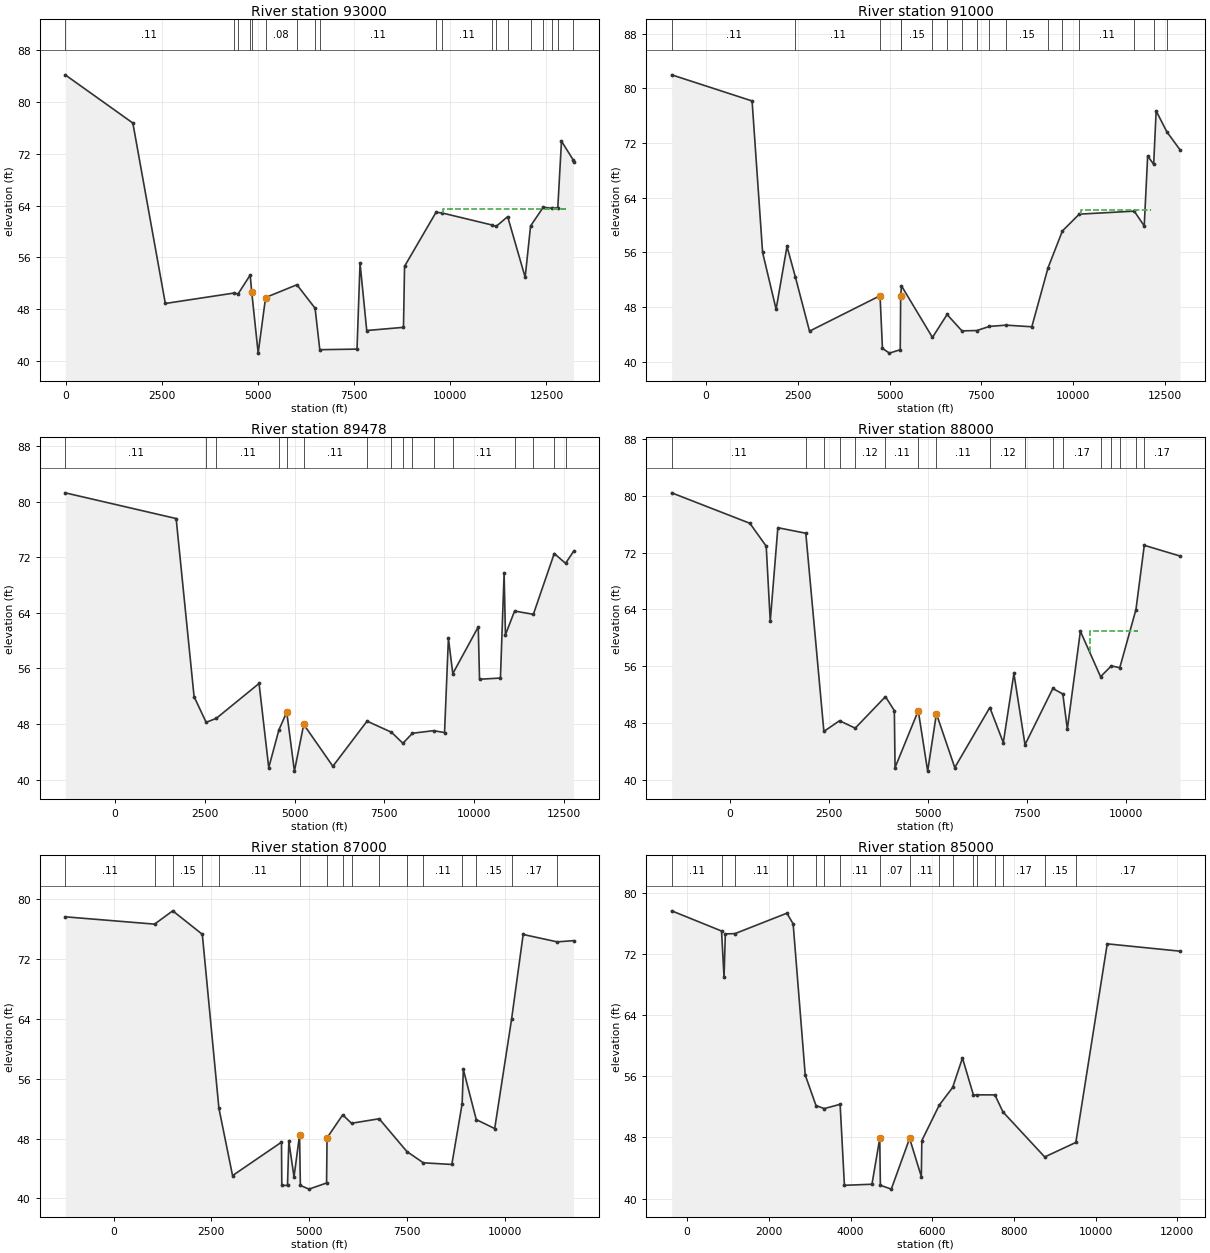
Type RM Length L Ch R = 1 ,93000   ,2000,2000,2000
BEGIN DESCRIPTION:
WFSJ Main 93.0
END DESCRIPTION:
XS GIS Cut Line= 3
      3908441.53     10014397.86       3907015.5     10009579.87
      3903406.78      10002210.3
#Sta/Elev= 30
   -24.6   84.17  1736.1   76.73  2581.3   48.89    4357   50.49  4476.5   50.38
  4790.2   53.28  4829.9   50.66  4997.6   41.23  5190.7   49.81  6006.4   51.78
  6478.9   48.16  6601.4   41.76  7570.3   41.85    7649   55.12  7823.4   44.72
  8779.7   45.21  8807.8   54.63  9626.3   62.95  9774.2   62.87 11077.4   61.01
   11189   60.77 11490.8   62.29 11946.7   52.93 12087.6   60.85 12416.9   63.73
 12655.8   63.57 12796.1   63.66 12891.9   73.93 13191.6    71.1 13205.7   70.72
#Mann= 19 ,-1 , 0
   -24.6     .11       0    4357    .125       0  4476.5     .11       0
  4790.2     .08       0  4829.9     .06       0  5190.7     .08       0
  6006.4     .11       0  6478.9     .15       0  6601.4     .11       0
  9626.3     .17       0  9774.2     .11       0 11077.4    .125       0
   11189    .125       0 11490.8     .11       0 12087.6    .125       0
 12416.9     .15       0 12655.8     .15       0 12796.1    .125       0
 13191.6     .15       0
#XS Ineff= 1 ,-1
  9803.5   13000   63.48
Permanent Ineff=
       F
Bank Sta=4829.9,5190.7
XS Rating Curve= 0 ,0
Exp/Cntr=0.3,0.1

Type RM Length L Ch R = 1 ,91000   ,1522,1522,1522
BEGIN DESCRIPTION:
WFSJ Main 91.0
END DESCRIPTION:
XS GIS Cut Line= 3
      3909865.13     10014224.23      3908643.07     10008418.65
      3905438.07     10001186.07
#Sta/Elev= 30
  -932.8      82  1257.3   78.17  1543.5   55.98  1911.3   47.66  2207.7   56.86
  2432.8   52.44  2821.2   44.45    4742   49.64  4807.7   41.92  4997.6   41.23
    5292   41.73  5303.6   49.66  5326.2   51.08    6169   43.53  6567.8   46.89
  6972.2   44.49  7378.8   44.54  7717.3   45.14  8175.6   45.33  8875.3   45.09
  9318.3   53.75  9708.5   59.13 10166.9   61.59 11664.9   62.03 11936.9   59.86
 12030.1   70.13 12193.7   68.89 12261.4   76.71 12554.3   73.64 12910.9   71.02
#Mann= 17 ,-1 , 0
  -932.8     .11       0  2432.8     .11       0    4742     .07       0
  5303.6     .11       0  5326.2     .15       0    6169     .11       0
  6567.8     .17       0  6972.2     .17       0  7378.8     .15       0
  7717.3     .17       0  8175.6     .15       0  9318.3     .17       0
  9708.5     .11       0 10166.9     .11       0 11664.9     .11       0
 12193.7     .11       0 12554.3     .15       0
#XS Ineff= 1 ,-1
 10225.7   12115   62.23
Permanent Ineff=
       F
Bank Sta=4742,5303.6
XS Rating Curve= 0 ,0
Exp/Cntr=0.3,0.1

Type RM Length L Ch R = 1 ,89478   ,1478,1478,1478
BEGIN DESCRIPTION:
WFSJ Main 90.0
END DESCRIPTION:
XS GIS Cut Line= 3
      3910177.63     10014172.16      3910142.91     10008113.11
      3907244.05     10000544.84
#Sta/Elev= 30
 -1389.4   81.27  1701.7   77.57  2201.7   51.94  2537.9   48.25  2819.4   48.82
  4011.8   53.84  4281.8   41.73  4564.8   47.16  4783.1   49.72  4997.6   41.23
  5256.3   47.95  6068.6   41.93  7020.4   48.42  7699.2   46.83    8020   45.24
  8286.4   46.68  8873.2   47.05  9180.2   46.78  9287.8   60.34  9409.8   55.26
 10119.4   61.98 10154.8   54.45 10737.5   54.62   10840   69.73   10877   60.85
 11131.5   64.26 11654.9   63.79 12236.6   72.54 12551.5   71.13 12774.2   72.84
#Mann= 16 ,-1 , 0
 -1389.4     .11       0  2537.9     .15       0  2819.4     .11       0
  4564.8     .11       0  4783.1     .07       0  5256.3     .11       0
  7020.4     .17       0  7699.2     .17       0    8020     .11       0
  8286.4     .15       0  8873.2     .11       0  9409.8     .11       0
 11131.5     .17       0 11654.9     .17       0 12236.6    .125       0
 12551.5     .11       0
#XS Ineff= 1 ,-1
 10119.4   10805   61.98
Permanent Ineff=
       F
Bank Sta=4783.1,5256.3
XS Rating Curve= 0 ,0
Exp/Cntr=0.3,0.1

Type RM Length L Ch R = 1 ,88000   ,1000,1000,1000
BEGIN DESCRIPTION:
WFSJ Main 88.0
END DESCRIPTION:
XS GIS Cut Line= 3
      3910542.21     10014085.38      3911463.47     10007683.32
      3912990.12     10001498.56
#Sta/Elev= 30
   -1468   80.42   506.9   76.13   919.6   72.91  1021.7   62.32  1213.6   75.51
  1919.4   74.73  2376.3   46.82  2771.8   48.33  3167.2   47.28  3931.4   51.72
  4155.9   49.75  4173.8   41.73  4759.8   49.74  4997.6   41.23  5218.6   49.31
  5682.1   41.73  6567.4   50.19  6907.8   45.24  7175.6   54.98  7456.1   44.95
  8158.9   52.87  8410.7   52.09    8525   47.15  8854.6   60.93  9363.8   54.53
  9636.9   56.05  9849.4   55.79 10257.6   63.97 10468.3   73.03 11370.4   71.52
#Mann= 17 ,-1 , 0
   -1468     .11       0  1919.4     .11       0  2376.3     .11       0
  2771.8     .11       0  3167.2     .12       0  3931.4     .11       0
  4759.8     .07       0  5218.6     .11       0  6567.4     .12       0
  7456.1     .11       0  8158.9     .11       0  8410.7     .17       0
  9363.8     .15       0  9636.9     .11       0  9849.4     .15       0
 10257.6     .11       0 10468.3     .17       0
#XS Ineff= 1 ,-1
  9091.7   10300   60.96
Permanent Ineff=
       F
Bank Sta=4759.8,5218.6
XS Rating Curve= 0 ,0
Exp/Cntr=0.3,0.1

Type RM Length L Ch R = 1 ,87000   ,2000,2000,2000
BEGIN DESCRIPTION:
WFSJ Main 87.0
END DESCRIPTION:
XS GIS Cut Line= 3
      3910993.61     10014015.85      3912421.94     10007943.48
      3914240.14     10001429.05
#Sta/Elev= 30
 -1238.1   77.65  1047.7   76.67  1511.9   78.45  2268.8   75.31  2692.7   52.06
  3042.1   43.04  4293.6   47.51    4302   41.73  4447.7   41.73  4481.8   47.64
  4614.1   42.86  4755.9   48.49  4776.5   41.73  4997.6   41.23  5446.8   42.05
  5459.3   48.09    5859   51.16  6085.4   50.04  6792.9   50.64  7500.5   46.26
  7922.7   44.75  8650.3   44.53  8914.6   52.66  8944.5   57.24  9275.4   50.53
  9747.2   49.33 10178.3   63.94 10475.3   75.29   11344    74.3 11763.4   74.46
#Mann= 16 ,-1 , 0
 -1238.1     .11       0  1047.7     .17       0  1511.9     .15       0
  2268.8     .17       0  2692.7     .11       0  4755.9     .07       0
  5459.3     .11       0    5859     .17       0  6085.4     .17       0
  6792.9     .17       0  7500.5     .17       0  7922.7     .11       0
  8914.6     .17       0  9275.4     .15       0 10178.3     .17       0
   11344     .11       0
#XS Ineff= 1 ,-1
  8944.5   10100   57.24
Permanent Ineff=
       F
Bank Sta=4755.9,5459.3
XS Rating Curve= 0 ,0
Exp/Cntr=0.3,0.1

Type RM Length L Ch R = 1 ,85000   ,2000,2000,2000
BEGIN DESCRIPTION:
WFSJ Main 85.0
END DESCRIPTION:
XS GIS Cut Line= 3
      3911236.67     10014033.23      3913835.59     10009325.23
      3915056.11     10002366.55
#Sta/Elev= 30
  -377.7   77.65     843   75.01   904.1   68.93   935.7   74.63  1173.3   74.67
  2441.9   77.34  2595.5   75.95  2891.6   56.16  3154.8   52.17  3357.4   51.77
 3745.45   52.33  3850.8   41.73    4525   41.87 4715.57   47.88  4730.8   41.74
  4997.6   41.23  5446.6   47.87  5733.4   42.87  5745.4   47.58 6172.73   52.23
    6499   54.53  6740.3   58.39  7009.4   53.53  7094.8   53.57  7533.9   53.56
  7732.2   51.33  8753.1   45.44  9515.2   47.34 10283.6   73.33 12064.9   72.37
#Mann= 18 ,-1 , 0
  -377.7     .11       0     843     .17       0  1173.3     .11       0
  2441.9    .125       0  2595.5     .11       0  3154.8     .12       0
  3357.4     .11       0 3745.45     .11       0 4715.57     .07       0
  5446.6     .11       0 6172.73     .12       0    6499     .11       0
  7009.4     .17       0  7094.8     .11       0  7533.9     .11       0
  7732.2     .17       0  8753.1     .15       0  9515.2     .17       0
#XS Ineff= 1 ,-1
  6740.3    9915   58.39
Permanent Ineff=
       F
Bank Sta=4715.57,5446.6
XS Rating Curve= 0 ,0
Exp/Cntr=0.3,0.1

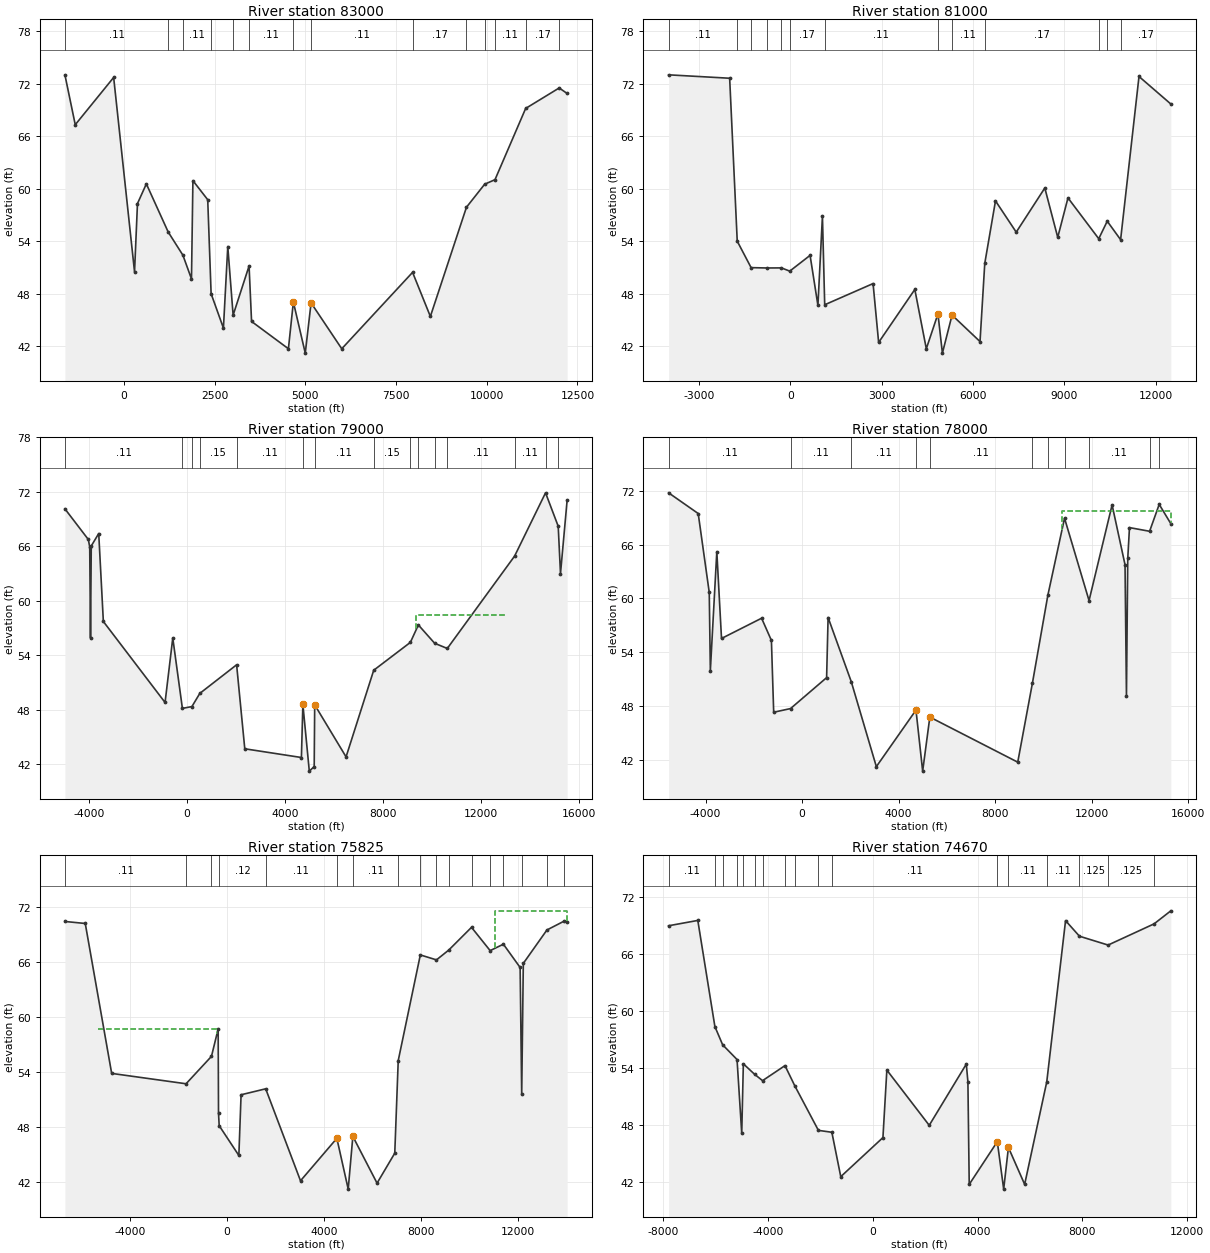
Type RM Length L Ch R = 1 ,83000   ,2000,2000,2000
BEGIN DESCRIPTION:
WFSJ Main 83.0
END DESCRIPTION:
XS GIS Cut Line= 3
        3913070.     10015851.52      3915735.68     10009783.64
      3916063.02     10002575.47
#Sta/Elev= 30
 -1627.6   73.03 -1342.3   67.33  -283.7   72.73   291.9   50.52   372.8   58.32
   617.3   60.57  1219.5   55.07    1625   52.42  1861.4   49.71  1900.8   60.94
  2309.1   58.76  2402.6   48.02  2741.9   44.09    2862   53.41  3009.3   45.57
  3448.9   51.19  3517.4   44.85  4533.1   41.73  4669.7   47.07  4997.6   41.23
  5157.9   46.97  6003.6   41.73  7955.6   50.46  8446.1   45.42  9440.9    57.9
  9942.6   60.53 10227.5   61.05 11072.5   69.19 11997.3   71.53 12215.6    70.9
#Mann= 14 ,-1 , 0
 -1627.6     .11       0  1219.5     .11       0    1625     .11       0
  2402.6     .17       0  3009.3     .15       0  3448.9     .11       0
  4669.7     .07       0  5157.9     .11       0  7955.6     .17       0
  9440.9     .11       0  9942.6     .15       0 10227.5     .11       0
 11072.5     .17       0 11997.3     .11       0
#XS Ineff= 1 ,-1
    -130  1900.8   60.94
Permanent Ineff=
       F
Bank Sta=4669.7,5157.9
XS Rating Curve= 0 ,0
Exp/Cntr=0.3,0.1

Type RM Length L Ch R = 1 ,81000   ,2000,2000,2000
BEGIN DESCRIPTION:
WFSJ Main 81.0
END DESCRIPTION:
XS GIS Cut Line= 4
      3913903.34      10018169.2      3917696.76     10010014.44
      3918249.39     10006949.92      3917416.23     10002645.25
#Sta/Elev= 30
 -3993.9      73 -1988.7   72.61 -1739.9   54.01 -1284.4   50.99  -763.9   50.95
    -288   50.96   -15.3   50.59   652.4   52.39   909.6   46.68  1057.9   56.85
  1132.5   46.75  2720.7   49.17  2903.5   42.45  4091.8    48.5    4469   41.73
  4851.6   45.71  4997.6   41.23  5314.7   45.57  6232.9   42.55  6388.6   51.47
    6741   58.61  7421.8   55.04  8360.6   60.08    8785   54.45  9121.1   58.95
 10131.4   54.29 10410.5   56.29 10849.5   54.18 11453.6   72.81 12498.5   69.67
#Mann= 13 ,-1 , 0
 -3993.9     .11       0 -1739.9     .15       0 -1284.4     .17       0
  -763.9     .17       0    -288     .15       0   -15.3     .17       0
  1132.5     .11       0  4851.6     .07       0  5314.7     .11       0
  6388.6     .17       0 10131.4     .15       0 10410.5     .17       0
 10849.5     .17       0
#XS Ineff= 1 ,-1
    6741   11100   58.61
Permanent Ineff=
       F
Bank Sta=4851.6,5314.7
XS Rating Curve= 0 ,0
Exp/Cntr=0.3,0.1

Type RM Length L Ch R = 1 ,79000   ,1000,1000,1000
BEGIN DESCRIPTION:
WFSJ Main 79.0
END DESCRIPTION:
XS GIS Cut Line= 3
      3916533.52     10020226.57      3919551.55     10010718.68
      3919554.37     10000200.48
#Sta/Elev= 30
 -4975.4   70.12 -4019.6   66.74 -3962.4   65.92 -3930.9   55.91 -3899.5   66.03
 -3595.2    67.4 -3406.4   57.71  -888.4   48.79  -573.6   55.89    -181   48.14
   207.5   48.34   529.7   49.79  2031.6   52.94  2364.7   43.69  4675.6   42.73
  4734.9   48.58  4997.6   41.23  5197.6   41.73  5217.6   48.53  6497.6    42.8
  7625.9   52.34  9122.2   55.41  9447.7   57.33 10112.7   55.31 10628.3   54.74
 13374.3   64.91 14637.8   71.88 15154.3    68.2 15247.6   62.99 15518.2   71.06
#Mann= 15 ,-1 , 0
 -4975.4     .11       0    -181     .17       0   207.5     .15       0
   529.7     .15       0  2031.6     .11       0  4734.9     .07       0
  5217.6     .11       0  7625.9     .15       0  9122.2     .11       0
  9447.7     .11       0 10112.7     .11       0 10628.3     .11       0
 13374.3     .11       0 14637.8    .125       0 15154.3     .11       0
#XS Ineff= 1 ,-1
  9367.6   13000   58.47
Permanent Ineff=
       F
Bank Sta=4734.9,5217.6
XS Rating Curve= 0 ,0
Exp/Cntr=0.3,0.1

Type RM Length L Ch R = 1 ,78000   ,2175,2175,2175
BEGIN DESCRIPTION:
WFSJ Main 78.0
END DESCRIPTION:
XS GIS Cut Line= 3
      3918460.61      10020929.7      3920541.11     10010607.18
      3922965.83     10000617.12
#Sta/Elev= 30
 -5530.1   71.78 -4303.1   69.47 -3845.9   60.67 -3800.2   51.94 -3532.1   65.22
 -3337.8   55.53 -1676.4   57.79 -1269.9   55.31 -1175.6    47.3    -477   47.71
  1017.6   51.16  1078.8   57.87  2037.7   50.72  3078.2   41.23  4720.6   47.54
  4997.6   40.73  5294.4   46.76  8937.2   41.73  9546.8   50.57 10186.1   60.37
 10875.5   68.95 11891.7   59.76 12846.6   70.43 13382.6   63.76 13441.8    49.1
 13495.8   64.46 13567.1    67.9 14400.9   67.49 14798.8   70.49 15280.1   68.34
#Mann= 11 ,-1 , 0
 -5530.1     .11       0    -477     .11       0  2037.7     .11       0
  4720.6     .07       0  5294.4     .11       0  9546.8     .17       0
 10186.1     .11       0 10875.5    .125       0 11891.7     .11       0
 14400.9    .125       0 14798.8     .15       0
#XS Ineff= 2 ,-1
 -4000.1  1078.8   57.87 10768.6   15300    69.8
Permanent Ineff=
       F       F
Bank Sta=4720.6,5294.4
XS Rating Curve= 0 ,0
Exp/Cntr=0.3,0.1

Type RM Length L Ch R = 1 ,75825   ,1155,1155,1155
BEGIN DESCRIPTION:
WFSJ Main 77.0
END DESCRIPTION:
XS GIS Cut Line= 3
       3919078.3     10020841.63      3921986.28     10013549.96
      3923765.79     10000789.59
#Sta/Elev= 30
 -6698.5   70.42 -5858.2    70.2 -4767.5   53.85 -1696.1   52.72  -647.5   55.71
  -371.1    58.7  -356.8   49.52  -328.9   48.15     483    44.9     575   51.52
 1590.91   52.17  3028.5   42.14  4528.8   46.77  4997.6   41.23  5189.2   46.98
  6188.8   41.88  6919.9   45.15  7062.9   55.25    7975   66.77  8641.7   66.23
  9148.3    67.3 10087.7   69.78 10857.2   67.24 11404.5   67.94 12095.4    65.4
 12160.2   51.56 12226.7   65.85 13201.3   69.49 13913.8   70.46 14035.5    70.4
#Mann= 17 ,-1 , 0
 -6698.5     .11       0 -1696.1     .11       0  -647.5    .125       0
  -328.9     .12       0 1590.91     .11       0  4528.8     .07       0
  5189.2     .11       0  7062.9     .12       0    7975    .125       0
  8641.7    .125       0  9148.3    .125       0 10087.7    .125       0
 10857.2     .11       0 11404.5     .11       0 12160.2     .11       0
 13201.3     .11       0 13913.8     .15       0
#XS Ineff= 2 ,-1
   -5350  -419.7   58.72 11048.1   14100   71.58
Permanent Ineff=
       F       F
Bank Sta=4528.8,5189.2
XS Rating Curve= 0 ,0
Exp/Cntr=0.3,0.1

Type RM Length L Ch R = 1 ,74670   ,1670,1670,1670
BEGIN DESCRIPTION:
WFSJ Main 75.0
END DESCRIPTION:
XS GIS Cut Line= 3
      3921899.47     10022187.15      3922376.91     10018497.88
      3924547.05     10003220.08
#Sta/Elev= 30
 -7780.2   68.93 -6666.5   69.49 -6015.1   58.33 -5719.5   56.41 -5170.1   54.86
 -4991.1    47.1 -4929.8   54.41 -4497.5    53.3 -4197.3   52.64   -3342   54.22
 -2967.2   52.09 -2067.5   47.41 -1554.7   47.21 -1215.1   42.54   393.3   46.65
   542.4   53.75  2158.5   47.94  3572.5   54.38  3633.1   52.53  3683.6   41.73
  4754.2   46.22  4997.6   41.23  5178.5   45.61  5797.2   41.73  6640.1   52.51
  7357.1   69.47  7886.8   67.83  8979.3    66.9   10733   69.13   11371    70.5
#Mann= 17 ,-1 , 0
 -7780.2     .11       0 -6015.1     .17       0 -5719.5     .15       0
 -5170.1     .17       0 -4929.8     .15       0 -4497.5     .17       0
 -4197.3     .11       0   -3342     .15       0 -2967.2     .11       0
 -2067.5     .17       0 -1554.7     .11       0  4754.2     .07       0
  5178.5     .11       0  6640.1     .11       0  7886.8    .125       0
  8979.3    .125       0   10733     .11       0
#XS Ineff= 1 ,-1
   -5650  3572.5   54.38
Permanent Ineff=
       F
Bank Sta=4754.2,5178.5
XS Rating Curve= 0 ,0
Exp/Cntr=0.3,0.1

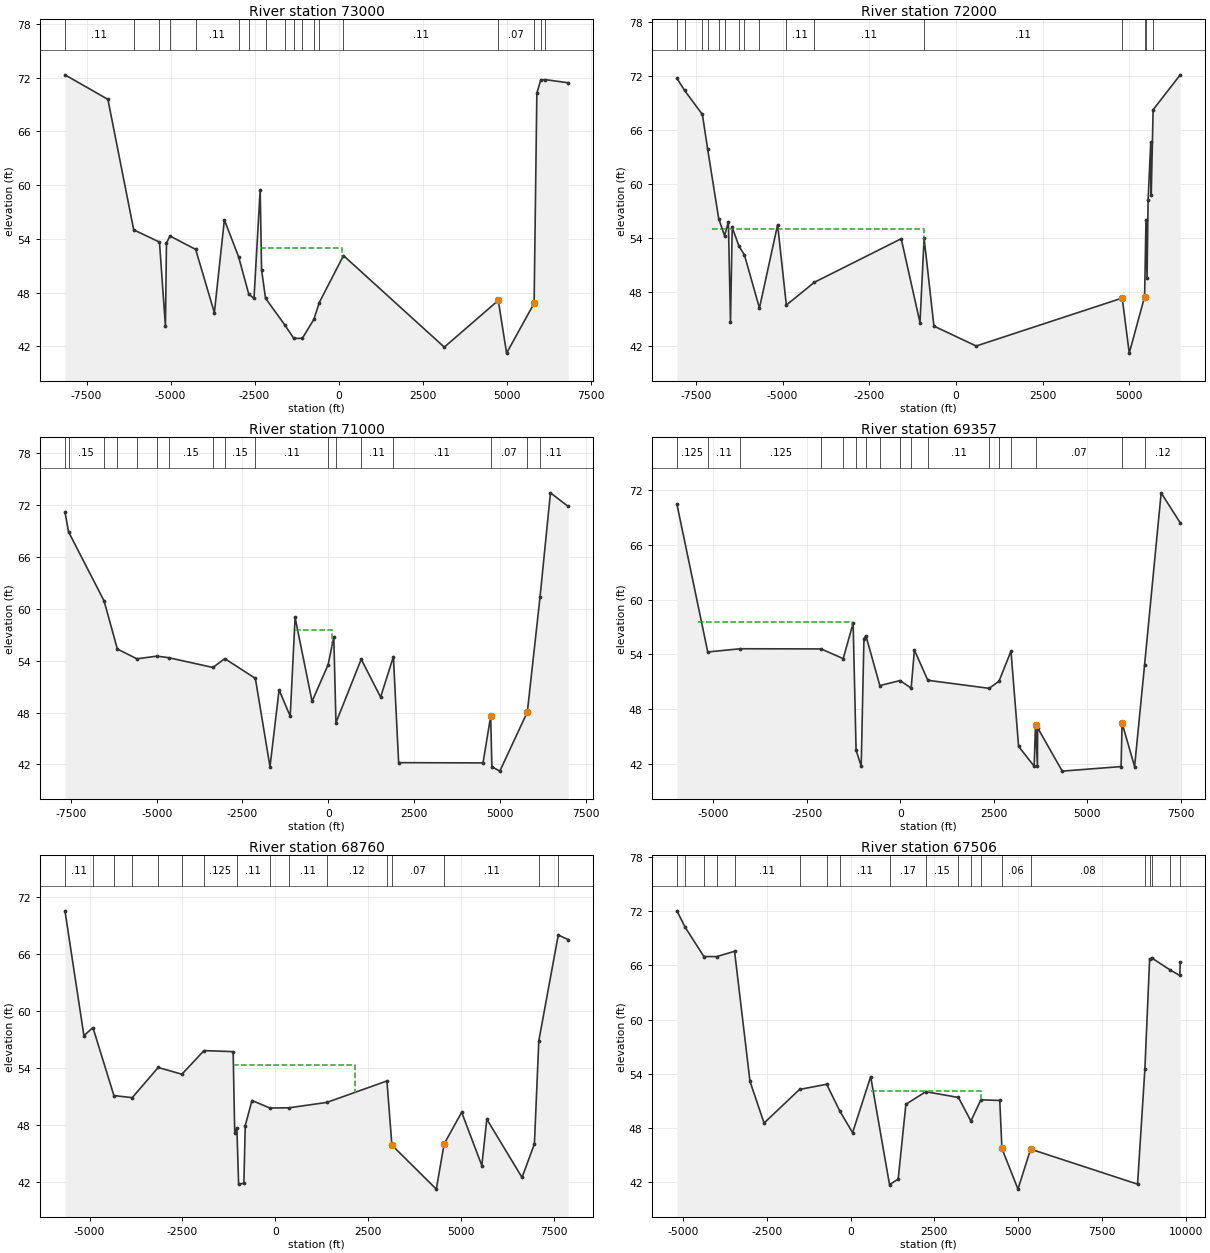
Type RM Length L Ch R = 1 ,73000   ,1000,1000,1000
BEGIN DESCRIPTION:
WFSJ Main 73.0
END DESCRIPTION:
XS GIS Cut Line= 3
      3922420.32     10022187.08      3925311.65      10009367.7
      3925559.62     10007551.55
#Sta/Elev= 30
 -8141.4   72.33 -6864.1   69.59   -6096   55.01 -5329.5   53.64 -5152.1   44.22
 -5121.4   53.53 -5017.4   54.32 -4252.4   52.82 -3696.5   45.75 -3398.5   56.13
   -2974   51.98   -2674   47.84 -2517.6   47.34 -2333.1   59.49 -2292.1   50.55
   -2174   47.36   -1595   44.35 -1332.1   42.87 -1078.9   42.89  -735.3   45.01
  -575.3   46.88  145.45   52.13  3144.1    41.9  4750.5   47.12  4997.6   41.23
  5816.6    46.8  5897.9   70.27    6014   71.76  6154.5   71.79    6833   71.44
#Mann= 18 ,-1 , 0
 -8141.4     .11       0   -6096     .17       0 -5329.5     .15       0
 -5017.4     .17       0 -4252.4     .11       0   -2974    .125       0
   -2674     .11       0   -2174     .11       0   -1595     .15       0
 -1332.1     .11       0 -1078.9     .11       0  -735.3     .17       0
  -575.3     .11       0  145.45     .11       0  4750.5     .07       0
  5816.6     .11       0    6014     .17       0  6154.5     .11       0
#XS Ineff= 2 ,-1
   -6500 -2333.1   59.49   -2330    94.1   53.03
Permanent Ineff=
       F       F
Bank Sta=4750.5,5816.6
XS Rating Curve= 0 ,0
Exp/Cntr=0.3,0.1

Type RM Length L Ch R = 1 ,72000   ,1000,1000,1000
BEGIN DESCRIPTION:
WFSJ Main 72.0
END DESCRIPTION:
XS GIS Cut Line= 3
      3923635.59     10022143.71      3926307.06     10009370.69
      3926415.43       10007906.
#Sta/Elev= 30
 -8049.4   71.71 -7830.6   70.38 -7314.8    67.7 -7165.3   63.91 -6844.3   56.15
 -6676.6   54.26 -6565.3   55.79 -6504.4   44.72 -6454.4   55.17 -6257.5   53.07
 -6102.7   52.13 -5669.1   46.23 -5145.2   55.47 -4893.4   46.56 -4083.8   49.09
 -1579.7   53.92 -1038.3   44.61 -920.13      54  -636.4   44.23   582.1   42.02
  4795.3   47.34  4997.6   41.23  5440.8   47.49  5480.5   56.04    5511   49.51
  5541.1   58.21  5618.4   64.63  5631.3   58.72  5686.1   68.23  6468.7    72.1
#Mann= 16 ,-1 , 0
 -8049.4    .125       0 -7830.6     .11       0 -7314.8    .125       0
 -7165.3     .15       0 -6844.3     .15       0 -6676.6     .11       0
 -6257.5     .17       0 -6102.7     .15       0 -5669.1     .11       0
 -4893.4     .11       0 -4083.8     .11       0 -920.13     .11       0
  4795.3     .07       0  5440.8     .11       0  5480.5     .11       0
  5686.1     .11       0
#XS Ineff= 1 ,-1
   -7050    -931   54.96
Permanent Ineff=
       F
Bank Sta=4795.3,5440.8
XS Rating Curve= 0 ,0
Exp/Cntr=0.3,0.1

Type RM Length L Ch R = 1 ,71000   ,1643,1643,1643
BEGIN DESCRIPTION:
WFSJ Main 71.0
END DESCRIPTION:
XS GIS Cut Line= 5
       3924026.2     10022056.94      3925805.73       10017326.
      3927143.93     10009827.12       3927142.2     10009551.71
      3926582.31     10007928.27
#Sta/Elev= 30
 -7671.9   71.18   -7567   68.88 -6532.3    60.9 -6144.8   55.34   -5576   54.21
 -4989.9   54.52 -4652.3   54.34 -3361.7   53.21 -3015.3   54.23 -2124.6   51.95
 -1698.1   41.74 -1433.6   50.61   -1109   47.58  -966.7   58.99  -472.4   49.29
      -4   53.53   160.8   56.74   224.3   46.83   959.7   54.16  1524.3   49.78
  1897.8   54.46  2050.2   42.21  4508.4   42.18  4731.9   47.58  4766.8   41.74
  4997.6   41.23    5800   48.06  6170.3   61.37  6473.2   73.39  6992.7   71.81
#Mann= 17 ,-1 , 0
 -7671.9     .15       0   -7567     .15       0 -6532.3    .125       0
 -6144.8     .15       0   -5576     .15       0 -4989.9    .125       0
 -4652.3     .15       0 -3361.7    .125       0 -3015.3     .15       0
 -2124.6     .11       0      -4    .125       0   224.3     .11       0
   959.7     .11       0  1897.8     .11       0  4731.9     .07       0
    5800     .11       0  6170.3     .11       0
#XS Ineff= 3 ,-1
   -6580  -966.7   58.99    -965   101.7   57.59     102  1897.8   54.46
Permanent Ineff=
       F       F       F
Bank Sta=4731.9,5800
XS Rating Curve= 0 ,0
Exp/Cntr=0.3,0.1

Type RM Length L Ch R = 1 ,69357   ,597,597,597
BEGIN DESCRIPTION:
WFSJ Main 70.0
END DESCRIPTION:
XS GIS Cut Line= 6
      3924274.65      10021917.5      3925264.23     10019248.22
      3927217.36     10016878.43      3928537.67     10014250.83
      3928183.33     10012671.49      3926709.54     10007828.92
#Sta/Elev= 30
-5974.27   70.43-5150.25   54.27-4277.81   54.62-2118.81    54.6-1528.44   53.54
-1263.01   57.43 -1184.2   43.53-1047.45   41.77-974.105   55.73-921.364   56.05
-548.974   50.59  -6.668   51.14 288.127   50.31 375.249   54.47 734.303   51.17
 2371.87   50.292636.094   51.062957.477   54.363160.733   43.943576.945   41.77
3612.971    46.33664.327   41.84 3668.83   45.984328.048   41.235901.097   41.73
 5928.29   46.486262.403   41.73  6528.1    52.8 6972.63   71.687483.152   68.39
#Mann= 17 ,-1 , 0
-5974.27    .125       0-5150.25     .11       0-4277.81    .125       0
-2118.81     .11       0-1528.44     .11       0 -1184.2    .125       0
-921.364     .11       0-548.974     .11       0  -6.668     .11       0
 288.127    .125       0 734.303     .11       0 2371.87    .125       0
2636.094     .12       02957.477     .11       03612.971     .07       0
 5928.29     .11       0  6528.1     .12       0
#XS Ineff= 2 ,-1
-5412.65 -1293.4    57.6-1292.112957.477   54.36
Permanent Ineff=
       F       F
Bank Sta=3612.971,5928.29
XS Rating Curve= 0 ,0
Skew Angle= 30
Exp/Cntr=0.5,0.3

Type RM Length L Ch R = 1 ,68760   ,1254,1254,1254
BEGIN DESCRIPTION:
WFSJ Main 69.0
END DESCRIPTION:
XS GIS Cut Line= 6
      3924535.06     10021982.62      3925524.65     10019326.35
      3927451.73     10017060.72      3928766.84     10014430.52
       3928515.1     10012627.13      3927061.11     10007776.87
#Sta/Elev= 30
-5661.12   70.56-5151.37   57.41-4908.11   58.25-4344.24   51.09-3851.04   50.87
 -3153.8   54.05-2514.59   53.34-1920.15   55.83-1136.83   55.72-1093.96   47.18
-1036.63   47.71-989.347   41.73-847.666   41.86-811.552   47.92 -630.38   50.57
-148.437   49.78  363.99    49.81384.861   50.373000.085   52.63 3133.54   45.87
4328.048   41.234538.406   45.995010.477   49.335553.128   43.715686.583    48.6
6633.928   42.466967.087   45.997086.166   56.877608.726   68.017878.319   67.53
#Mann= 16 ,-1 , 0
-5661.12     .11       0-4908.11     .11       0-4344.24    .125       0
-3851.04    .125       0 -3153.8     .15       0-2514.59     .15       0
-1920.15    .125       0-1036.63     .11       0-148.437     .11       0
  363.99     .11       01384.861     .12       03000.085     .11       0
 3133.54     .07       04538.406     .11       07086.166     .05       0
7608.726     .11       0
#XS Ineff= 2 ,-1
-5308.73-1136.83   55.72-1135.352129.556   54.32
Permanent Ineff=
       F       F
Bank Sta=3133.54,4538.406
XS Rating Curve= 0 ,0
Skew Angle= 30
Exp/Cntr=0.5,0.3

Type RM Length L Ch R = 1 ,67506   ,1417,1417,1417
BEGIN DESCRIPTION:
WFSJ Main 68.0
END DESCRIPTION:
XS GIS Cut Line= 3
      3928810.93     10022510.06       3929352.6     10011135.03
      3928706.77     10007551.69
#Sta/Elev= 30
   -5186   72.05 -4939.7   70.23 -4381.1   66.99 -3999.2   66.98   -3465   67.57
 -3004.5   53.16 -2584.1   48.55 -1524.8   52.27  -714.7   52.84  -327.3   49.91
    58.9   47.48   599.5   53.69  1161.7   41.73  1420.5   42.34  1650.7   50.63
  2245.8   52.02  3220.6   51.38  3591.1   48.77  3891.4   51.12  4453.9   51.05
 4518.18   45.73  4997.6   41.23  5374.9   45.66  8568.4   41.78  8786.9   54.53
  8929.1   66.75  9013.7   66.78  9529.2   65.53    9829   64.89    9843   66.39
#Mann= 20 ,-1 , 0
   -5186    .125       0 -4939.7     .15       0 -4381.1    .125       0
 -3999.2     .11       0   -3465     .11       0 -1524.8     .11       0
  -714.7    .125       0  -327.3     .11       0  1161.7     .17       0
  2245.8     .15       0  3220.6     .11       0  3591.1     .11       0
  3891.4     .08       0 4518.18     .06       0  5374.9     .08       0
  8786.9     .11       0  8929.1     .15       0  9013.7     .11       0
  9529.2     .11       0    9829    .125       0
#XS Ineff= 2 ,-1
   -3070   599.5   53.69     600  3896.4   52.11
Permanent Ineff=
       F       F
Bank Sta=4518.18,5374.9
XS Rating Curve= 0 ,0
Exp/Cntr=0.3,0.1

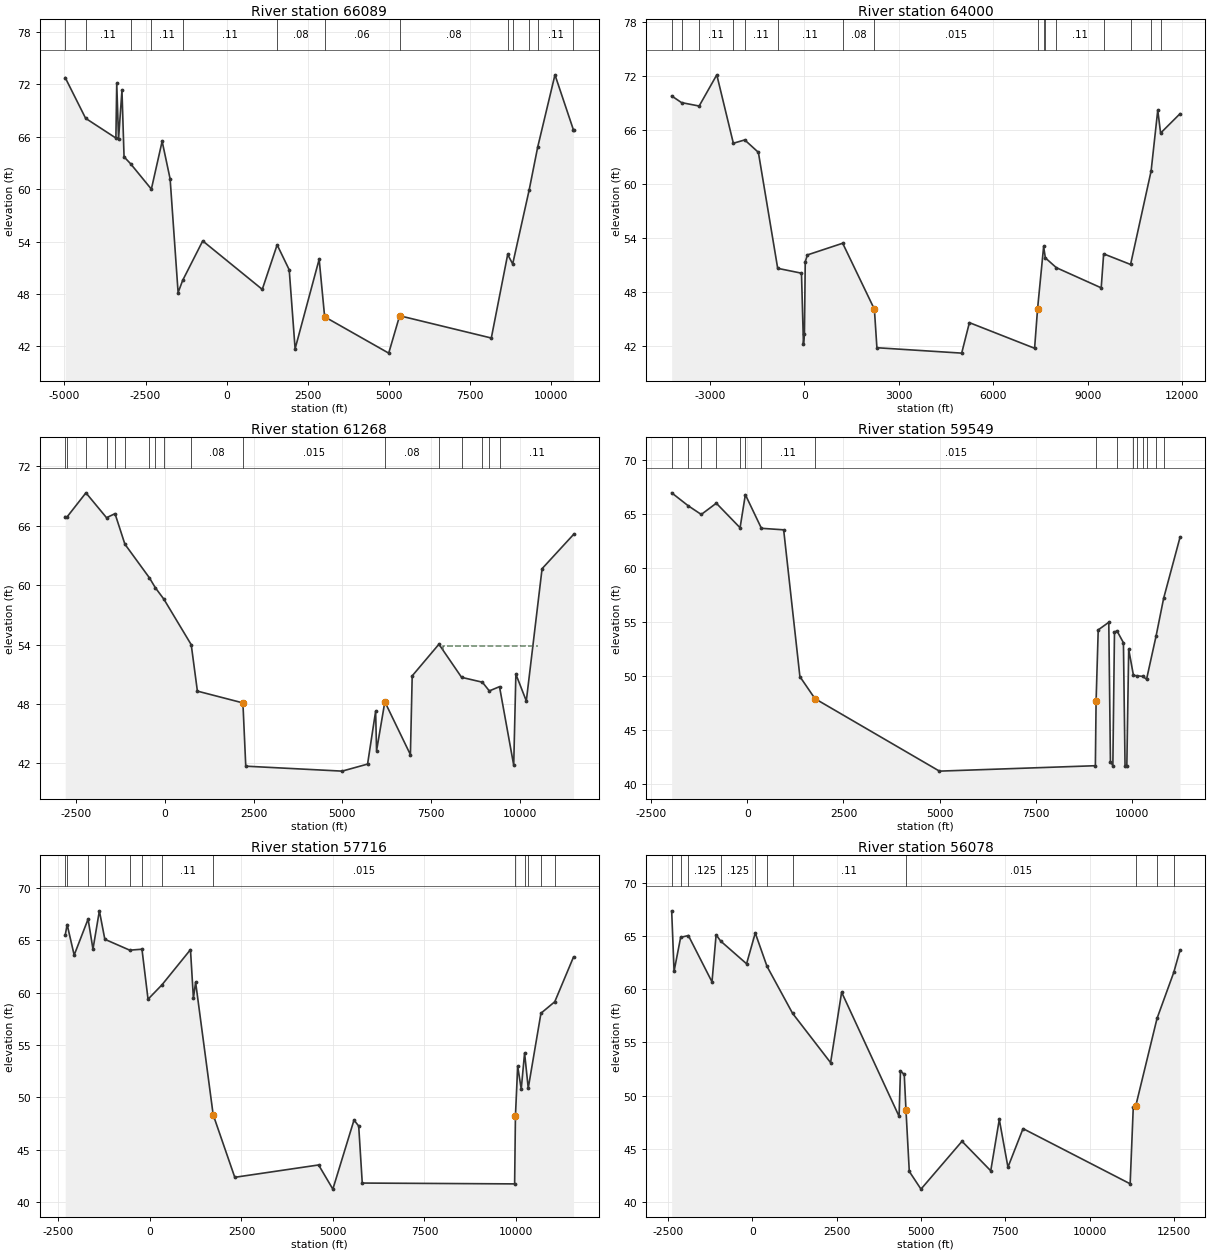
Type RM Length L Ch R = 1 ,66089   ,2089,2089,2089
BEGIN DESCRIPTION:
WFSJ Main 67.0
END DESCRIPTION:
XS GIS Cut Line= 3
      3929435.94     10022718.32      3930831.77     10011135.03
      3932185.59     10007365.14
#Sta/Elev= 30
 -4976.6   72.78   -4347   68.12 -3413.7   65.86 -3387.9   72.11 -3331.6   65.77
 -3226.8   71.33 -3162.4   63.71 -2961.6   62.92 -2320.3   60.01 -1987.9   65.49
 -1741.8   61.18 -1495.6   48.16 -1356.7   49.55  -736.7   54.08  1099.3   48.53
  1557.6   53.63  1930.2   50.77  2111.6   41.73  2853.3   51.98  3022.5   45.39
  4997.6   41.23  5334.7   45.51    8161   42.96 8665.91   52.53  8820.1   51.44
  9326.9   59.89  9589.9    64.8 10123.6    73.1 10694.2   66.78 10696.1   66.77
#Mann= 13 ,-1 , 0
 -4976.6     .11       0   -4347     .11       0 -2961.6    .125       0
 -2320.3     .11       0 -1356.7     .11       0  1557.6     .08       0
  3022.5     .06       0  5334.7     .08       0 8665.91     .11       0
  8820.1    .125       0  9326.9    .125       0  9589.9     .11       0
 10694.2    .125       0
#XS Ineff= 2 ,-1
   -1700  1557.6   53.63    1558  2853.3   51.98
Permanent Ineff=
       F       F
Bank Sta=3022.5,5334.7
XS Rating Curve= 0 ,0
Exp/Cntr=0.3,0.1

Type RM Length L Ch R = 1 ,64000   ,2732,2732,2732
BEGIN DESCRIPTION:
WFSJ Main 64.0
END DESCRIPTION:
XS GIS Cut Line= 4
      3929935.93     10022780.88      3932404.34     10013909.28
       3933852.6      10010926.7       3933248.6     10007365.16
#Sta/Elev= 30
 -4208.6   69.83 -3895.5   69.09 -3336.5   68.71 -2776.4   72.18 -2250.8   64.57
 -1889.3   64.94 -1456.2   63.56    -843   50.66     -88   50.12   -25.7   42.25
     5.4   43.32    32.1   51.39    98.8   52.15  1219.9   53.45  2226.7   46.11
  2306.5   41.83  4997.6   41.23  5242.6   44.62  7312.3   41.77  7407.3  46.186
  7599.3   53.09  7653.5   51.82  8004.4   50.73  9426.9   48.49  9504.3   52.27
 10358.7   51.09 11010.8   61.48 11222.2   68.25 11312.1    65.7   11928   67.85
#Mann= 16 ,-1 , 0
 -4208.6     .17       0 -3895.5     .11       0 -3336.5     .11       0
 -2250.8    .125       0 -1889.3     .11       0    -843     .11       0
  1219.9     .08       0  2226.7    .015       0  7407.3     .08       0
  7599.3     .11       0  7653.5     .11       0  8004.4     .11       0
  9504.3     .11       0 10358.7     .11       0 11010.8    .125       0
 11312.1     .11       0
#XS Ineff= 2 ,-1
   -1170  1219.9   53.45  7599.3   10650   53.09
Permanent Ineff=
       F       F
Bank Sta=2226.7,7407.3
XS Rating Curve= 0 ,0
Exp/Cntr=0.3,0.1

Type RM Length L Ch R = 1 ,61268   ,1719,1719,1719
BEGIN DESCRIPTION:
WFSJ Main 62.0
END DESCRIPTION:
XS GIS Cut Line= 3
      3934581.77      10021947.5      3935081.77     10014697.53
      3933894.27     10007739.22
#Sta/Elev= 30
 -2807.2    66.9 -2763.4   66.83 -2222.9    69.3 -1642.5   66.79 -1403.6    67.2
 -1124.9   64.12  -432.5   60.72  -267.4   59.73   -25.6   58.57   744.6   53.98
   918.1    49.3  2201.1   48.11  2281.3   41.73  4997.6   41.23  5714.3   41.94
  5941.1   47.26  5967.9   43.29  6201.3   48.22  6921.5   42.89  6972.2   50.84
  7725.5   54.03  8363.7   50.69  8949.4    50.2  9145.4   49.32  9432.6   49.75
    9833   41.83  9893.9   51.01 10188.1   48.31 10632.5   61.65 11518.9    65.1
#Mann= 17 ,-1 , 0
 -2807.2    .125       0 -2763.4     .11       0 -2222.9     .11       0
 -1642.5     .11       0 -1403.6    .125       0 -1124.9     .11       0
  -432.5    .125       0  -267.4     .11       0   -25.6     .11       0
   744.6     .08       0  2201.1    .015       0  6201.3     .08       0
  7725.5     .11       0  8363.7     .11       0  8949.4    .125       0
  9145.4     .11       0  9432.6     .11       0
#XS Ineff= 1 ,-1
  7840.7   10515    53.9
Permanent Ineff=
       F
Bank Sta=2201.1,6201.3
XS Rating Curve= 0 ,0
Exp/Cntr=0.3,0.1

Type RM Length L Ch R = 1 ,59549   ,1833,1833,1833
BEGIN DESCRIPTION:
WFSJ Main 60.0
END DESCRIPTION:
XS GIS Cut Line= 4
      3936157.27     10020279.34       3937227.6     10018135.03
       3936790.1      10014114.2      3934582.32     10007699.14
#Sta/Elev= 30
 -1969.1   66.96 -1537.6   65.76 -1198.9   64.96  -807.4      66  -189.3   63.73
     -52   66.79   365.8   63.68   944.5   63.54    1367   49.97  1759.3   47.93
  4997.6   41.23  9054.6   41.73 9073.37 47.7088  9128.7   54.29  9403.6   54.99
  9446.5   42.12  9509.4   41.73  9551.7   54.06  9615.1   54.21  9784.7    53.1
  9826.6   41.73  9873.1   41.73  9921.8    52.5 10045.1   50.08 10149.8   50.04
 10283.9   49.99 10386.8   49.73 10635.3   53.74 10830.2    57.2 11256.4   62.84
#Mann= 16 ,-1 , 0
 -1969.1    .125       0 -1537.6     .11       0 -1198.9    .125       0
  -807.4    .125       0  -189.3     .11       0     -52    .125       0
   365.8     .11       0  1759.3    .015       0 9073.37     .11       0
  9615.1    .125       0 10045.1     .11       0 10149.8    .125       0
 10283.9     .11       0 10386.8    .125       0 10635.3     .11       0
 10830.2     .11       0
#XS Ineff= 1 ,-1
  9165.4   10820   54.36
Permanent Ineff=
       F
Bank Sta=1759.3,9073.37
XS Rating Curve= 0 ,0
Exp/Cntr=0.3,0.1

Type RM Length L Ch R = 1 ,57716   ,1638,1638,1638
BEGIN DESCRIPTION:
WFSJ Main 58.0
END DESCRIPTION:
XS GIS Cut Line= 4
       3936721.5     10020344.44       3938477.6     10017635.03
      3938394.27     10013155.86      3935790.08     10007551.65
#Sta/Elev= 30
   -2315   65.49 -2262.3   66.52 -2070.1    63.6 -1690.1   67.04 -1556.5   64.17
 -1381.5   67.83 -1232.3   65.11  -552.5   64.07  -217.7   64.16   -51.9   59.38
   329.5   60.76  1107.7   64.12  1187.7   59.48  1247.8   61.01  1727.8   48.34
  2317.9   42.36  4608.3   43.54  4997.6   41.23  5575.4   47.83  5703.9   47.26
  5800.9   41.81  9964.1   41.73  9986.2   48.23 10047.5   52.98 10144.5   50.79
 10236.1   54.24 10335.9   50.88 10683.3   58.04 11060.7   59.14 11573.4   63.42
#Mann= 13 ,-1 , 0
   -2315     .11       0 -2262.3     .11       0 -1690.1     .11       0
 -1232.3     .11       0  -552.5     .11       0  -217.7    .125       0
   329.5     .11       0  1727.8    .015       0  9986.2    .125       0
 10236.1    .125       0 10335.9     .11       0 10683.3    .125       0
 11060.7     .11       0
Bank Sta=1727.8,9986.2
XS Rating Curve= 0 ,0
Exp/Cntr=0.3,0.1

Type RM Length L Ch R = 1 ,56078   ,2939,2939,2939
BEGIN DESCRIPTION:
WFSJ Main 56.0
END DESCRIPTION:
XS GIS Cut Line= 4
      3937220.66      10020344.4      3940385.93     10016354.47
       3939552.6     10012500.31      3936115.49     10007535.59
#Sta/Elev= 30
 -2395.7   67.35 -2324.5   61.68 -2129.6   64.86 -1899.8   65.03 -1199.7   60.68
 -1077.9    65.1  -942.5   64.51  -174.3   62.38    83.2   65.27   431.3   62.14
  1189.6   57.73  2317.3    53.1  2644.1   59.71    4348   48.06  4388.9   52.32
  4501.4   51.99  4552.4   48.66  4650.9   42.89  4997.6   41.23  6214.3   45.72
  7066.5   42.95  7319.9   47.77  7576.7   43.29    8024   46.91 11200.6   41.73
 11293.7   48.96 11365.3   49.02 11997.8   57.25 12494.8   61.58 12678.9   63.65
#Mann= 11 ,-1 , 0
 -2395.7    .125       0 -2129.6     .11       0 -1899.8    .125       0
  -942.5    .125       0    83.2    .125       0   431.3     .11       0
  1189.6     .11       0  4552.4    .015       0 11365.3    .125       0
 11997.8    .125       0 12494.8     .11       0
#XS Ineff= 1 ,-1
     570  2644.1   59.71
Permanent Ineff=
       F
Bank Sta=4552.4,11365.3
XS Rating Curve= 0 ,0
Exp/Cntr=0.3,0.1