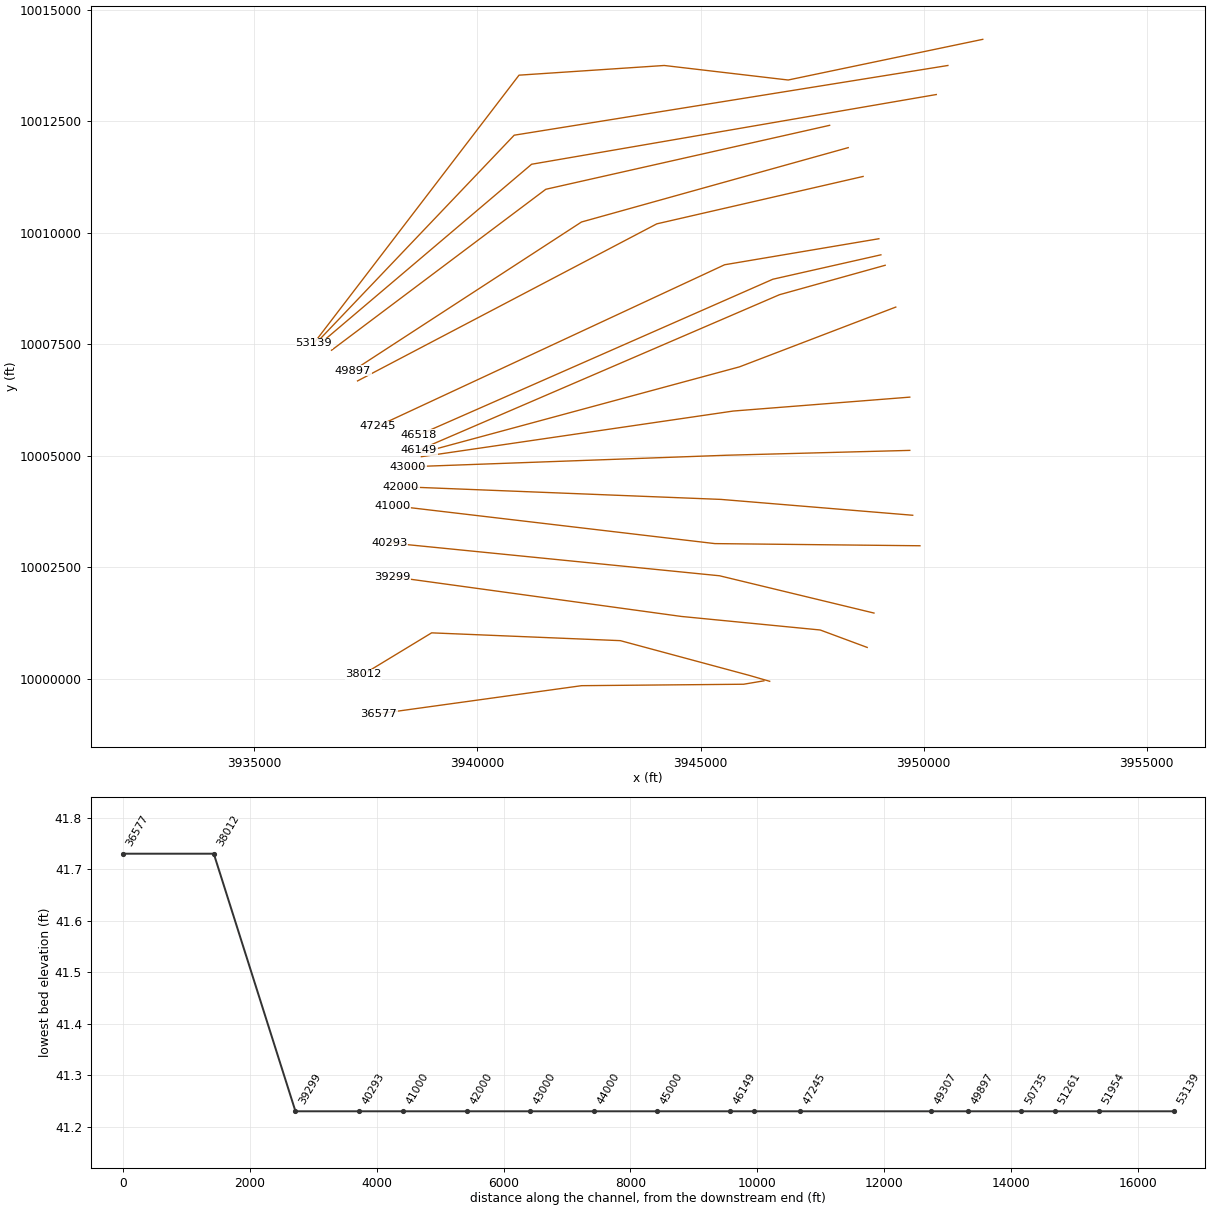
HEC-RAS study WFSJ Main.prj: WFSJ Main Base Level Engineering

--- WFSJ Main.g01 (geometry) --- (continued)

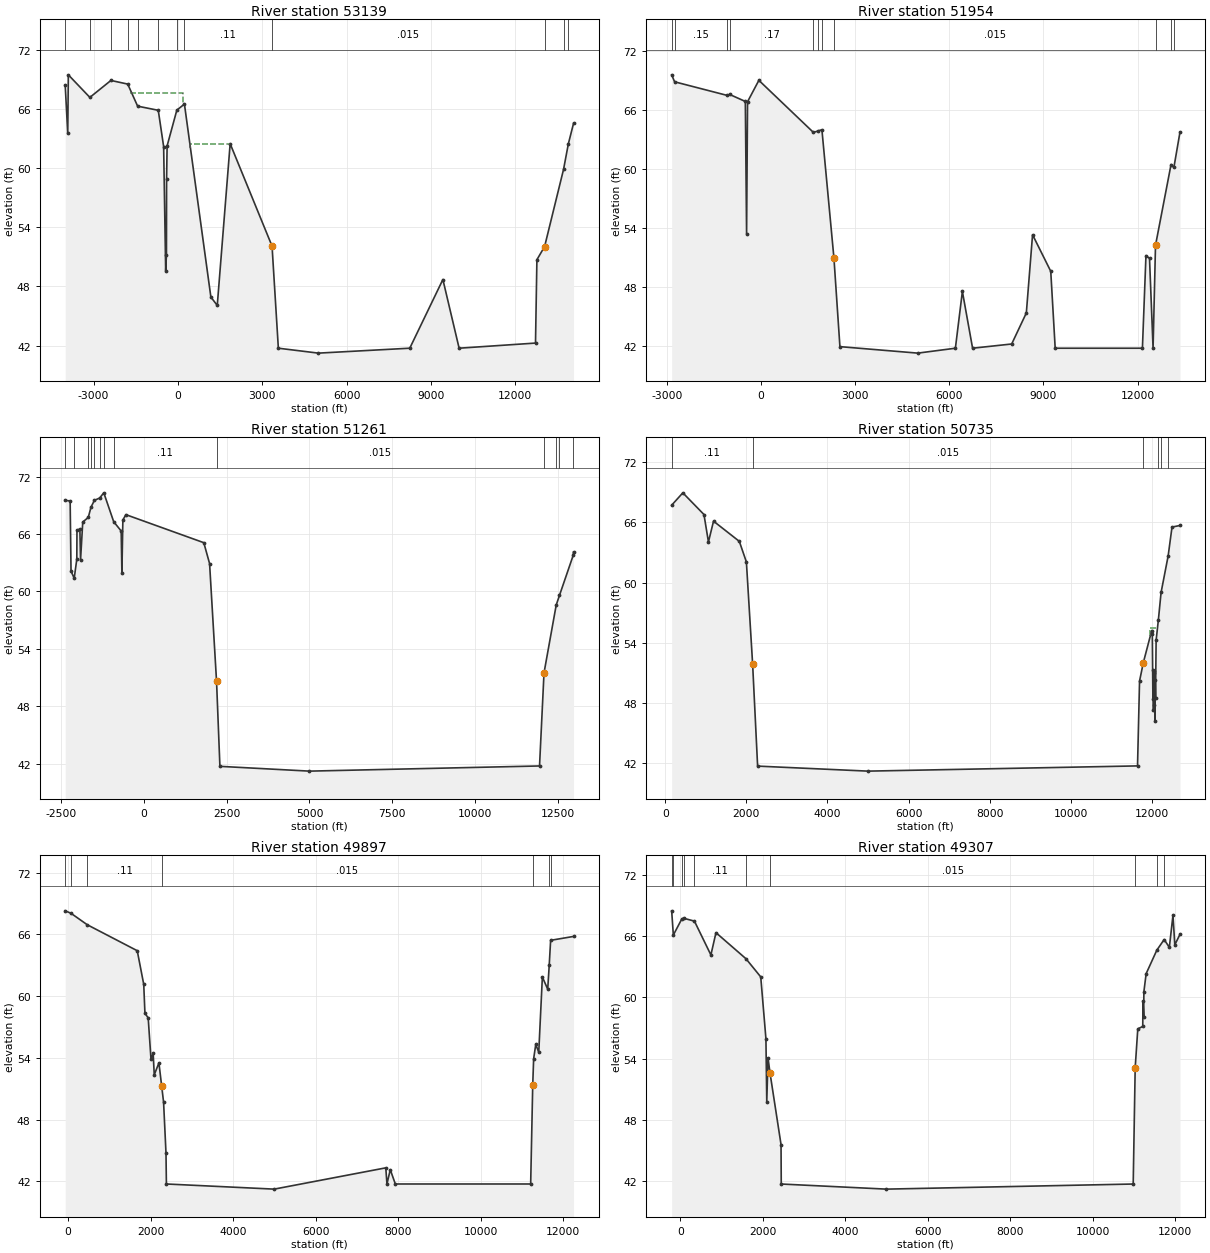
Type RM Length L Ch R = 1 ,53139   ,1185,1185,1185
BEGIN DESCRIPTION:
WFSJ Main 54.0
END DESCRIPTION:
XS GIS Cut Line= 5
      3951326.55     10014333.12      3946964.58     10013421.66
       3944186.8     10013747.18      3940931.59     10013530.17
      3936331.88     10007520.16
#Sta/Elev= 30
 -4008.6   68.42   -3918   63.52 -3897.6   69.47 -3131.4   67.18 -2382.2    68.9
 -1784.7   68.53 -1432.2   66.29    -698   65.87  -506.9   62.19  -434.3    49.6
    -407   51.21  -401.9    58.9  -383.3   62.26   -37.2   65.89   232.6    66.5
  1173.5   46.92  1400.8   46.07  1859.5   62.48 3349.6852.08987    3574   41.73
  4997.4   41.23  8249.3   41.73  9427.2    48.7 10004.7   41.73 12722.2   42.25
   12772   50.7113045.45   52.0413720.87   59.89 13891.8   62.48   14075   64.54
#Mann= 12 ,-1 , 0
 -4008.6     .17       0 -3131.4     .15       0 -2382.2     .17       0
 -1784.7     .15       0 -1432.2     .17       0    -698     .15       0
   -37.2     .17       0   232.6     .11       0 3349.68    .015       0
13045.45     .11       013720.87     .11       0 13891.8    .125       0
#XS Ineff= 2 ,-1
   -1690   182.6   67.65     445  1859.5   62.48
Permanent Ineff=
       F       F
Bank Sta=3349.68,13045.45
XS Rating Curve= 0 ,0
Exp/Cntr=0.3,0.1

Type RM Length L Ch R = 1 ,51954   ,693,693,693
BEGIN DESCRIPTION:
Mapping XS d13458fd
END DESCRIPTION:
XS GIS Cut Line= 3
      3950545.33     10013747.19      3940823.09     10012184.68
      3936440.42     10007585.05
#Sta/Elev= 30
 -2846.1   69.56 -2752.9   68.85 -1095.8   67.48  -996.6   67.56  -498.9   66.85
  -458.4   53.37    -428   66.82   -67.3      69  1670.4    63.7  1805.6   63.83
    1942   63.97  2325.2   50.91    2516   41.89  4997.4   41.23  6195.9   41.73
  6418.8   47.51    6744   41.73  7990.2   42.16    8457   45.32  8655.2   53.28
  9235.2   49.56  9376.7   41.73 12156.5   41.73 12269.4   51.16 12382.7   50.87
 12495.9   41.73 12573.6    52.2   13069   60.43 13159.6   60.13 13354.2   63.74
#Mann= 11 ,-1 , 0
 -2846.1     .17       0 -2752.9     .15       0 -1095.8     .11       0
  -996.6     .17       0  1670.4     .17       0  1805.6     .11       0
    1942     .11       0  2325.2    .015       0 12573.6     .11       0
   13069     .11       0 13159.6    .125       0
Bank Sta=2325.2,12573.6
XS Rating Curve= 0 ,0
Exp/Cntr=0.3,0.1

Type RM Length L Ch R = 1 ,51261   ,526,526,526
BEGIN DESCRIPTION:
WFSJ Main 52.0
END DESCRIPTION:
XS GIS Cut Line= 3
      3950284.86     10013096.13      3941213.71     10011533.64
      3936519.28     10007551.71
#Sta/Elev= 30
   -2381   69.52 -2231.8   69.46 -2205.2   62.13 -2109.1   61.38 -2030.6   63.37
 -2025.5   66.42 -1937.6   66.52 -1917.3   63.29 -1850.9   67.26 -1683.8   67.74
 -1602.8    68.8 -1500.1   69.52 -1339.1   69.77 -1214.9   70.31  -915.5   67.29
  -689.4   66.32  -668.1   61.94  -638.7   67.47  -547.4   68.03  1806.9    65.1
  1981.6   62.92  2192.4    50.6  2293.9   41.73  4997.4   41.23 11952.2   41.77
 12087.4   51.49 12456.5   58.59 12555.3    59.6 12969.8   63.78 12979.5   64.13
#Mann= 13 ,-1 , 0
   -2381     .17       0 -2109.1     .11       0 -1683.8     .17       0
 -1602.8     .11       0 -1500.1     .17       0 -1339.1     .11       0
 -1214.9     .17       0  -915.5     .11       0  2192.4    .015       0
 12087.4     .11       0 12456.5     .11       0 12555.3     .11       0
 12969.8    .125       0
Bank Sta=2192.4,12087.4
XS Rating Curve= 0 ,0
Exp/Cntr=0.3,0.1

Type RM Length L Ch R = 1 ,50735   ,838,838,838
BEGIN DESCRIPTION:
WFSJ Main 51.0
END DESCRIPTION:
XS GIS Cut Line= 3
      3947894.31     10012405.87      3941531.77     10010972.53
      3936728.83     10007365.11
#Sta/Elev= 30
   159.8    67.7     435   68.93   955.7   66.77  1066.1   64.04  1191.5   66.11
    1827    64.1  2001.3   62.05    2155   51.89    2278   41.73  4997.4   41.23
 11641.8   41.75 11691.7    50.2 11785.5   52.04 11991.7   55.22 12006.3   54.91
 12020.8   48.44 12027.1   51.28 12035.4   47.35 12041.7   50.98   12050   47.86
 12056.2   51.22 12070.8   46.26 12077.1   50.34 12085.4   48.55   12100   54.24
 12156.2    56.3 12222.3   59.01 12396.6   62.65 12491.6   65.52 12688.6   65.68
#Mann= 6 ,-1 , 0
   159.8     .11       0    2155    .015       0 11785.5     .11       0
 12156.2     .11       0 12222.3    .125       0 12396.6     .11       0
#XS Ineff= 1 ,-1
 11956.3   12130   55.52
Permanent Ineff=
       F
Bank Sta=2155,11785.5
XS Rating Curve= 0 ,0
Exp/Cntr=0.3,0.1

Type RM Length L Ch R = 1 ,49897   ,590,590,590
BEGIN DESCRIPTION:
WFSJ Main 50.0
END DESCRIPTION:
XS GIS Cut Line= 3
      3948310.97     10011905.87      3942331.77      10010239.2
      3937206.93     10006905.97
#Sta/Elev= 30
   -67.8    68.3    72.7   68.06   464.9   66.95  1678.1   64.42  1835.6   61.15
  1864.6   58.33  1943.4   57.89  2011.7   53.85  2063.6   54.45  2090.5   52.35
  2203.5   53.51  2271.2   51.22  2316.5   49.69    2375   44.74  2384.8   41.73
  4997.4   41.23  7702.4    43.3  7730.6   41.73  7811.1   43.12  7933.4   41.73
 11213.9   41.7311263.64   51.32   11286   53.91 11337.3    55.3 11409.8   54.55
 11497.4   61.86 11627.2   60.68 11663.5   63.01 11697.8   65.43 12252.8   65.81
#Mann= 7 ,-1 , 0
   -67.8     .15       0    72.7    .125       0   464.9     .11       0
  2271.2    .015       011263.64     .11       0 11663.5    .125       0
 11697.8     .11       0
Bank Sta=2271.2,11263.64
XS Rating Curve= 0 ,0
Exp/Cntr=0.3,0.1

Type RM Length L Ch R = 1 ,49307   ,2062,2062,2062
BEGIN DESCRIPTION:
WFSJ Main 49.0
END DESCRIPTION:
XS GIS Cut Line= 3
      3948644.25     10011260.02      3944019.27     10010197.53
      3937311.91     10006677.21
#Sta/Elev= 30
  -207.2   68.48  -166.7   66.11    41.6   67.71    95.5   67.74   344.5   67.47
   743.3   64.16   866.5   66.34  1593.4   63.79  1951.6   62.01  2077.2   55.96
  2097.7   49.79  2128.2   54.07  2176.1   52.61  2443.5   45.59  2448.6   41.73
  4997.4   41.23 10979.1   41.7311027.27   53.12 11090.2   56.92 11210.4   57.16
   11216   59.65 11232.4    58.1 11238.1   60.56 11292.9   62.33 11551.9   64.63
 11729.8   65.67   11855    64.9 11943.2   68.05 11987.3   65.15 12113.3   66.18
#Mann= 10 ,-1 , 0
  -207.2     .11       0  -166.7    .125       0    41.6     .15       0
    95.5    .125       0   344.5     .11       0  1593.4     .11       0
  2176.1    .015       011027.27     .11       0 11551.9    .125       0
 11729.8     .11       0
Bank Sta=2176.1,11027.27
XS Rating Curve= 0 ,0
Exp/Cntr=0.3,0.1

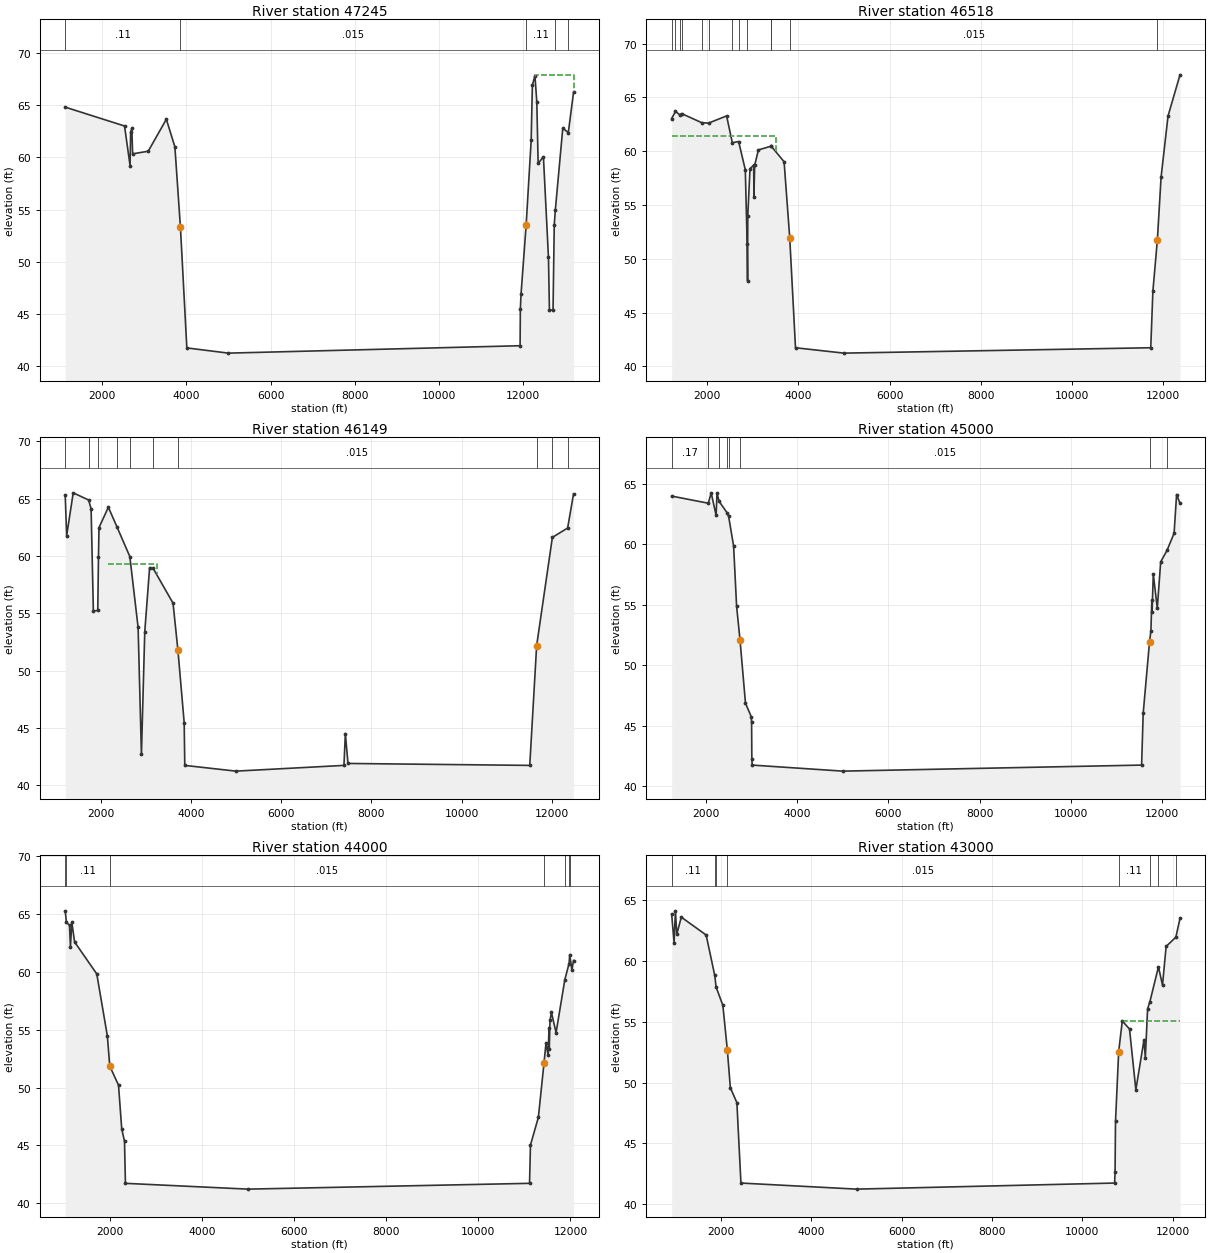
Type RM Length L Ch R = 1 ,47245   ,727,727,727
BEGIN DESCRIPTION:
WFSJ Main 48.0
END DESCRIPTION:
XS GIS Cut Line= 3
      3948998.39     10009864.19       3945540.1     10009280.86
      3937766.27       10005663.
#Sta/Elev= 30
  1119.6   64.83  2529.8   63.02  2661.6   59.21  2674.2   62.42  2702.2    62.8
  2722.5   60.35  3092.5    60.6  3523.6   63.67  3726.4   61.02  3858.3    53.3
  4010.4   41.73  4997.4   41.23   11931   41.94 11937.2   45.43 11953.1   46.88
 12074.4   53.49 12194.4   61.63 12222.8   66.94   12284   67.84 12328.1   65.35
   12360   59.43 12485.5   60.07 12605.4   50.41 12628.3   45.37 12714.1   45.35
 12742.7   53.51 12768.5   54.96 12945.8   62.81   13077   62.39 13201.2   66.25
#Mann= 5 ,-1 , 0
  1119.6     .11       0  3858.3    .015       0 12074.4     .11       0
 12768.5    .125       0   13077     .11       0
#XS Ineff= 2 , 0
                        12273.86           67.93
Permanent Ineff=
       F       F
Bank Sta=3858.3,12074.4
XS Rating Curve= 0 ,0
Exp/Cntr=0.3,0.1

Type RM Length L Ch R = 1 ,46518   ,369,369,369
BEGIN DESCRIPTION:
WFSJ Main 47.0
END DESCRIPTION:
XS GIS Cut Line= 3
      3949043.36     10009503.44      3946621.44     10008956.56
      3938687.43     10005466.98
#Sta/Elev= 30
  1221.6   63.04  1305.3    63.7  1400.2   63.38  1438.5    63.5  1881.9   62.65
  2029.4   62.61  2426.7   63.28  2551.9   60.79  2690.4    60.9  2836.8   58.27
  2877.6   51.33  2886.2   47.96  2891.3      54  2939.7   58.38  3020.9    58.7
  3026.1   55.78  3041.8   58.68  3123.8   60.12  3404.9   60.47  3410.9   60.44
  3687.7   59.02  3811.7   51.92  3937.8   41.73  4997.4   41.23 11730.5   41.73
 11777.1   46.98   11876   51.77 11956.9   57.58 12109.4   63.27   12372    67.1
#Mann= 13 ,-1 , 0
  1221.6    .125       0  1305.3     .15       0  1400.2    .125       0
  1438.5     .11       0  1881.9    .125       0  2029.4     .11       0
  2551.9    .125       0  2690.4     .11       0  2877.6    .125       0
  3404.9     .11       0  3410.9     .11       0  3811.7    .015       0
   11876     .11       0
#XS Ineff= 2 , 0
         3507.95   61.45
Permanent Ineff=
       F       F
Bank Sta=3811.7,11876
XS Rating Curve= 0 ,0
Exp/Cntr=0.3,0.1

Type RM Length L Ch R = 1 ,46149   ,1149,1149,1149
BEGIN DESCRIPTION:
WFSJ Main 46.0
END DESCRIPTION:
XS GIS Cut Line= 3
       3949138.8     10009269.06      3946769.01     10008609.33
      3938687.39     10005128.42
#Sta/Elev= 30
  1217.3   65.34  1249.4   61.78  1394.7   65.52  1736.9   64.89  1791.1   64.11
  1841.1   55.22  1938.3   55.25  1954.3   59.92  1965.7   62.49  2173.3   64.26
    2369    62.5  2648.8   59.96  2832.1   53.77  2905.7   42.69  2979.3   53.39
  3086.7   58.99    3166   58.92  3605.7   55.89  3713.7   51.79  3852.7   45.46
  3865.7   41.73  4997.4   41.23  7391.3   41.73  7422.6   44.51  7480.6    41.9
   11507   41.73 11659.5   52.18 12007.9   61.63   12346   62.45 12476.6   65.42
#Mann= 10 ,-1 , 0
  1217.3     .15       0  1736.9    .125       0  1954.3     .11       0
    2369    .125       0  2648.8     .17       0    3166     .11       0
  3713.7    .015       0 11659.5     .11       0 12007.9    .125       0
   12346     .15       0
#XS Ineff= 2 ,-1
    1580  2173.3   64.26    2175  3244.8   59.32
Permanent Ineff=
       F       F
Bank Sta=3713.7,11659.5
XS Rating Curve= 0 ,0
Exp/Cntr=0.3,0.1

Type RM Length L Ch R = 1 ,45000   ,1000,1000,1000
BEGIN DESCRIPTION:
WFSJ Main 45.0
END DESCRIPTION:
XS GIS Cut Line= 3
      3949376.45     10008332.24      3945874.03     10006992.82
       3938742.8     10005066.19
#Sta/Elev= 30
  1250.2   63.97  2052.9   63.38  2115.9   64.24  2223.8   62.37  2243.2   64.21
  2288.6   63.54  2462.4    62.6  2497.6    62.3  2607.2   59.84  2672.6   54.86
  2746.7   52.11    2867   46.85  2993.8   45.73  3001.2   45.31  3006.5   42.21
  3015.2   41.73  4997.4   41.23 11545.8   41.73 11580.5   46.01 11718.7    51.9
 11749.8   52.84 11769.6   55.38 11774.8   54.36 11801.6   57.53 11889.3    54.7
 11963.9   58.53   12102   59.48 12257.4   60.89 12312.5    64.1 12386.9   63.38
#Mann= 8 ,-1 , 0
  1250.2     .17       0  2052.9     .11       0  2288.6     .17       0
  2462.4     .11       0  2497.6     .11       0  2746.7    .015       0
 11718.7     .11       0   12102     .15       0
Bank Sta=2746.7,11718.7
XS Rating Curve= 0 ,0
Exp/Cntr=0.3,0.1

Type RM Length L Ch R = 1 ,44000   ,1000,1000,1000
BEGIN DESCRIPTION:
WFSJ Main 44.0
END DESCRIPTION:
XS GIS Cut Line= 3
      3949691.14     10006314.02      3945735.39     10006002.48
      3938742.84     10004979.39
#Sta/Elev= 30
    1032   65.26  1058.7   64.27  1125.6   64.01  1145.6   62.15  1175.7   64.28
  1235.9   62.57  1717.4   59.81  1948.1   54.43  1998.3   51.86  2188.9   50.21
  2259.1   46.43  2319.3   45.36  2339.3   41.73  4997.4   41.23 11111.9   41.73
 11132.1   45.04 11303.9   47.43 11425.2   52.09 11469.5   53.85 11516.2   52.78
 11534.3   55.18 11539.4   53.29 11556.6    55.8 11586.9   56.49   11688   54.74
 11878.8   59.33 11970.2   60.71 11984.3   61.47 12031.6   60.15   12067   60.97
#Mann= 7 ,-1 , 0
    1032     .15       0  1058.7     .11       0  1998.3    .015       0
 11425.2     .11       0 11878.8     .15       0 11970.2    .125       0
 11984.3     .15       0
Bank Sta=1998.3,11425.2
XS Rating Curve= 0 ,0
Exp/Cntr=0.3,0.1

Type RM Length L Ch R = 1 ,43000   ,1000,1000,1000
BEGIN DESCRIPTION:
WFSJ Main 43.0
END DESCRIPTION:
XS GIS Cut Line= 3
      3949691.12     10005120.45      3945596.76     10005012.13
       3938440.9     10004751.59
#Sta/Elev= 30
   904.2   63.85   957.5   61.51   987.5   64.13  1017.5    62.2  1117.5   63.61
  1667.7   62.14  1858.1   58.81  1887.8   57.86  2037.9   56.35  2137.9   52.64
  2203.5   49.57    2348   48.35    2438   41.73  4997.4   41.23 10712.7   41.73
 10722.7   42.65 10732.7   46.81 10802.7   52.54 10882.8   55.07 11042.9    54.4
   11183    49.4 11363.1   53.51 11393.1   52.05 11443.2   56.07 11493.2   56.64
 11683.3   59.52 11773.4   58.02 11853.4    61.2 12068.5   61.96 12160.6    63.5
#Mann= 8 ,-1 , 0
   904.2     .11       0  1858.1     .17       0  1887.8     .11       0
  2137.9    .015       0 10802.7     .11       0 11493.2     .11       0
 11683.3    .125       0 12068.5     .17       0
#XS Ineff= 2 , 0
                        10881.82           55.09
Permanent Ineff=
       F       F
Bank Sta=2137.9,10802.7
XS Rating Curve= 0 ,0
Exp/Cntr=0.3,0.1

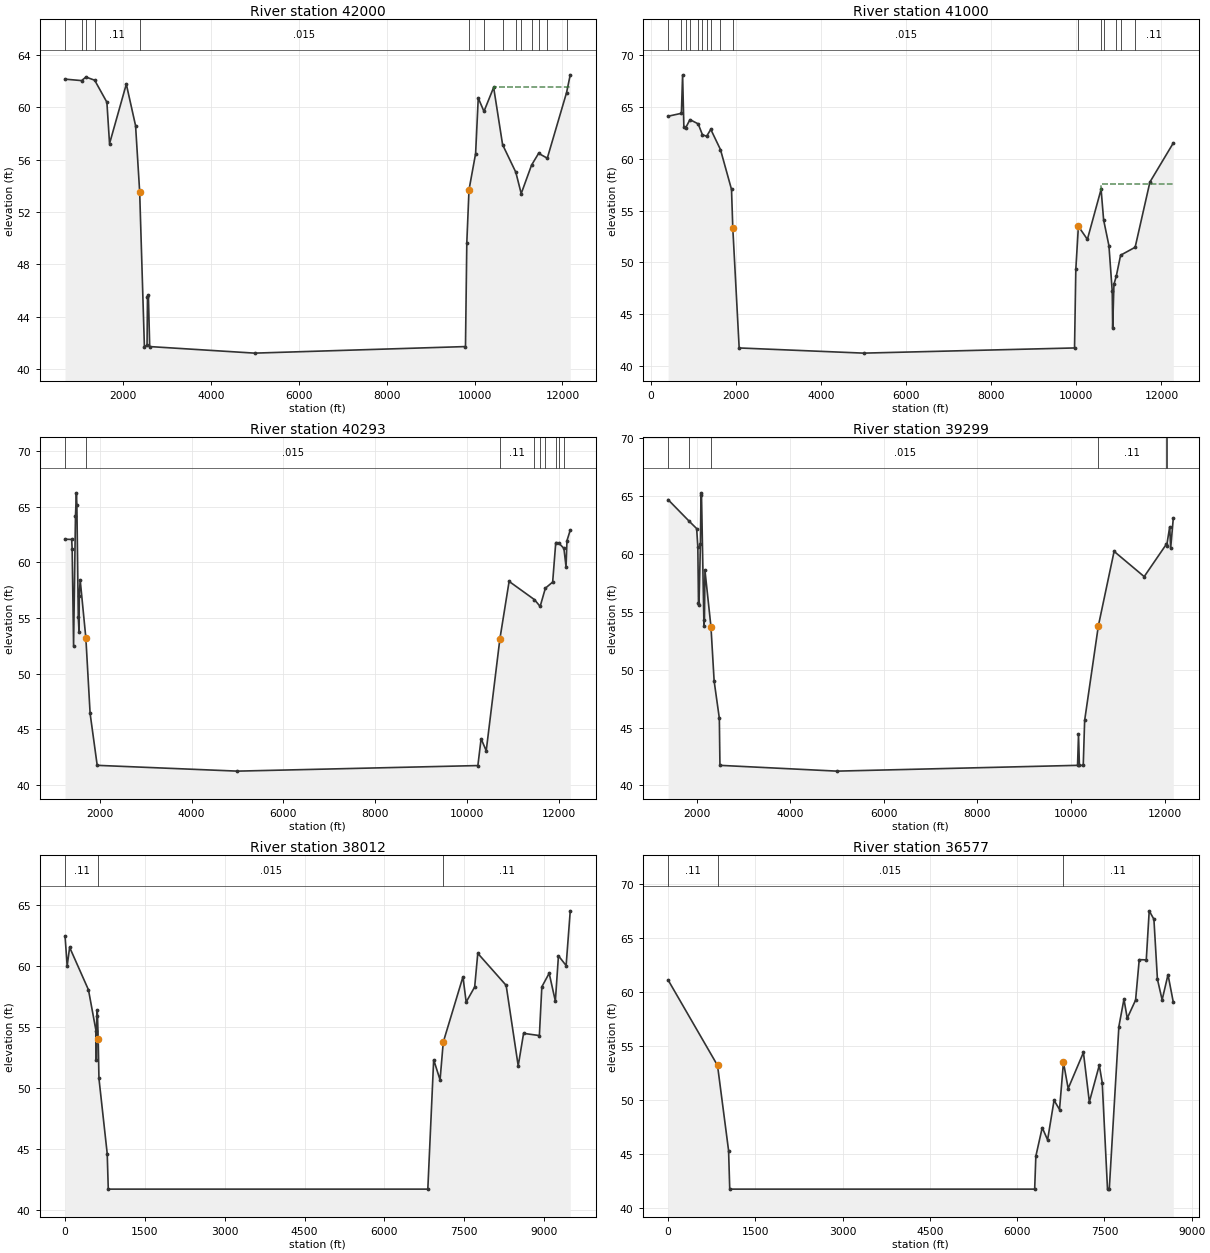
Type RM Length L Ch R = 1 ,42000   ,1000,1000,1000
BEGIN DESCRIPTION:
WFSJ Main 42.0
END DESCRIPTION:
XS GIS Cut Line= 3
      3949756.26     10003666.45      3945458.12     10004021.79
      3938287.08     10004306.64
#Sta/Elev= 30
   687.2   62.13    1063   62.02  1162.2   62.29  1360.7   62.05  1638.8   60.37
    1699   57.21  2080.3   61.75  2291.1   58.58  2384.1   53.54  2491.7   41.73
  2551.9   41.82    2562   45.49    2582   45.68  2612.2   41.73  4997.4   41.23
    9794   41.73  9824.1   49.65  9874.1   53.69 10024.2   56.45 10084.3   60.69
 10214.4   59.67 10434.6    61.5   10638   57.13 10938.6   55.03 11061.4    53.4
 11296.3   55.57 11456.8   56.47 11654.4    56.1 12092.4    61.1 12176.7   62.46
#Mann= 14 ,-1 , 0
   687.2     .15       0    1063     .11       0  1162.2     .17       0
  1360.7     .11       0  2384.1    .015       0  9874.1     .11       0
 10214.4     .11       0   10638     .15       0 10938.6     .17       0
 11061.4    .125       0 11296.3     .15       0 11456.8    .125       0
 11654.4     .11       0 12092.4     .17       0
#XS Ineff= 2 , 0
                        10444.32           61.52
Permanent Ineff=
       F       F
Bank Sta=2384.1,9874.1
XS Rating Curve= 0 ,0
Exp/Cntr=0.3,0.1

Type RM Length L Ch R = 1 ,41000   ,707,707,707
BEGIN DESCRIPTION:
WFSJ Main 41.0
END DESCRIPTION:
XS GIS Cut Line= 3
      3949918.97     10002982.86      3945321.42     10003031.19
      3938092.28      10003883.4
#Sta/Elev= 30
   402.2   64.12   715.5    64.4   743.3   68.12   773.3   63.09   814.1   62.99
   916.7   63.79  1110.1   63.38  1208.7   62.34  1307.4   62.18    1406   62.85
  1633.4    60.9  1893.4   57.05  1923.4   53.33  2073.4   41.73  4997.4   41.23
  9957.7   41.73  9987.9   49.34 10048.3   53.48 10259.7   52.22   10582   57.06
 10641.5    54.1 10766.4   51.61 10843.8    47.2 10854.4   43.67   10884   47.87
 10940.7    48.7 11040.4   50.69 11382.5   51.46 11729.9   57.76 12279.2   61.53
#Mann= 16 ,-1 , 0
   402.2     .15       0   715.5     .17       0   814.1     .15       0
   916.7     .17       0  1110.1     .15       0  1208.7     .17       0
  1307.4     .11       0    1406     .15       0  1633.4     .11       0
  1923.4    .015       0 10048.3     .11       0   10582    .125       0
 10641.5     .11       0 10940.7    .125       0 11040.4     .11       0
 11382.5     .11       0
#XS Ineff= 2 , 0
                        10571.59           57.61
Permanent Ineff=
       F       F
Bank Sta=1923.4,10048.3
XS Rating Curve= 0 ,0
Exp/Cntr=0.3,0.1

Type RM Length L Ch R = 1 ,40293   ,994,994,994
BEGIN DESCRIPTION:
WFSJ Main 40.0
END DESCRIPTION:
XS GIS Cut Line= 3
      3948888.19     10001474.61      3945426.82     10002310.12
       3938026.7     10003047.96
#Sta/Elev= 30
  1244.9   62.07  1389.3   62.05  1399.6    61.2  1430.4   52.48  1471.6   64.12
  1492.1   66.24  1502.1   65.15  1533.3   55.04  1549.1   53.76  1554.2      57
  1574.4   58.41  1697.9   53.19  1790.5   46.41  1944.8   41.75  4997.4   41.23
 10231.4   41.73 10301.8   44.14 10413.3   43.06 10710.2    53.1 10911.5   58.28
 11463.5   56.64 11587.3   56.03 11700.8   57.67 11859.5   58.22 11926.9   61.77
   11987   61.75 12104.3   61.25 12150.9   59.58   12171   61.94 12242.5   62.89
#Mann= 9 ,-1 , 0
  1244.9     .11       0  1697.9    .015       0 10710.2     .11       0
 11463.5    .125       0 11587.3     .11       0 11700.8    .125       0
 11926.9     .11       0   11987    .125       0 12104.3     .11       0
Bank Sta=1697.9,10710.2
XS Rating Curve= 0 ,0
Exp/Cntr=0.3,0.1

Type RM Length L Ch R = 1 ,39299   ,1287,1287,1287
BEGIN DESCRIPTION:
WFSJ Main 39.0
END DESCRIPTION:
XS GIS Cut Line= 4
      3948736.28     10000704.22      3947683.76     10001094.84
      3944569.62     10001398.66      3938092.33     10002288.34
#Sta/Elev= 30
  1391.9   64.69  1843.9   62.82  2002.2   62.19  2027.2    60.6  2040.9    55.8
  2051.5   55.57  2082.6   60.86  2094.2   65.07  2104.9   65.28  2158.2   53.77
  2168.4   54.31  2179.5   58.57  2307.5   53.71  2375.6   49.01  2486.5    45.8
  2499.5   41.73  4997.4   41.23 10137.1   41.73 10157.2   44.42 10176.6   41.73
 10258.7   41.73 10288.5   45.61 10581.2   53.78 10917.5   60.22 11560.3   58.04
 12030.5   60.82 12040.4   60.71 12105.4   62.35 12125.6    60.5 12181.6   63.09
#Mann= 6 ,-1 , 0
  1391.9     .11       0  1843.9     .11       0  2307.5    .015       0
 10581.2     .11       0 12030.5    .125       0 12040.4     .11       0
Bank Sta=2307.5,10581.2
XS Rating Curve= 0 ,0
Exp/Cntr=0.3,0.1

Type RM Length L Ch R = 1 ,38012   ,1435,1435,1435
XS GIS Cut Line= 5
      3946550.51       9999944.9      3946097.49     10000076.27
      3943202.43     10000856.12      3938972.57     10001030.91
      3937440.23     10000101.27
#Sta/Elev= 30
       0   62.45    39.7   59.99    86.1   61.52   440.2   58.04   583.1   54.66
   588.3   52.31   595.6   55.89   605.9   56.41   623.1   53.98     637   50.79
   792.4   44.63   812.4   41.73  6817.4   41.73  6927.5   52.32  7047.6   50.67
  7107.6   53.76  7477.9   59.11    7538   57.04  7698.1   58.28  7756.4   61.03
  8289.5   58.41    8516   51.82  8617.1   54.48  8913.8    54.3  8960.2   58.29
  9097.9    59.4  9214.2   57.12  9272.4   60.83  9416.6   60.03  9494.2   64.51
#Mann= 3 , 0 , 0
       0     .11       0   623.1    .015       0  7107.6     .11       0
Bank Sta=623.1,7107.6
XS Rating Curve= 0 ,0
Exp/Cntr=0.3,0.1

Type RM Length L Ch R = 1 ,36577   ,1547,1547,1547
XS GIS Cut Line= 4
      3946421.28      9999955.74      3945965.57      9999879.14
      3942334.37      9999847.01      3937787.93      9999217.67
#Sta/Elev= 30
       0   61.09   849.8   53.18  1039.8    45.3  1059.8   41.73  6300.8   41.73
    6321   44.78  6430.5   47.42  6522.9   46.29    6634   49.95  6727.8    49.1
 6795.45   53.47  6876.5   51.04  7138.7   54.38  7240.5    49.8  7411.3    53.2
  7461.8   51.59  7552.6   41.73  7582.9   41.73  7748.1   56.78  7835.3   59.31
  7891.7   57.55  8035.3   59.23  8097.8   62.97  8218.9   62.95  8269.4   67.49
  8350.2   66.71  8410.7   61.16  8491.5   59.25  8592.5   61.58  8683.2   59.04
#Mann= 3 , 0 , 0
       0     .11       0   849.8    .015       0 6795.45     .11       0
#XS Ineff= 1 ,-1
  7138.7    7890   54.38
Permanent Ineff=
       F
Bank Sta=849.8,6795.45
XS Rating Curve= 0 ,0
Exp/Cntr=0.3,0.1