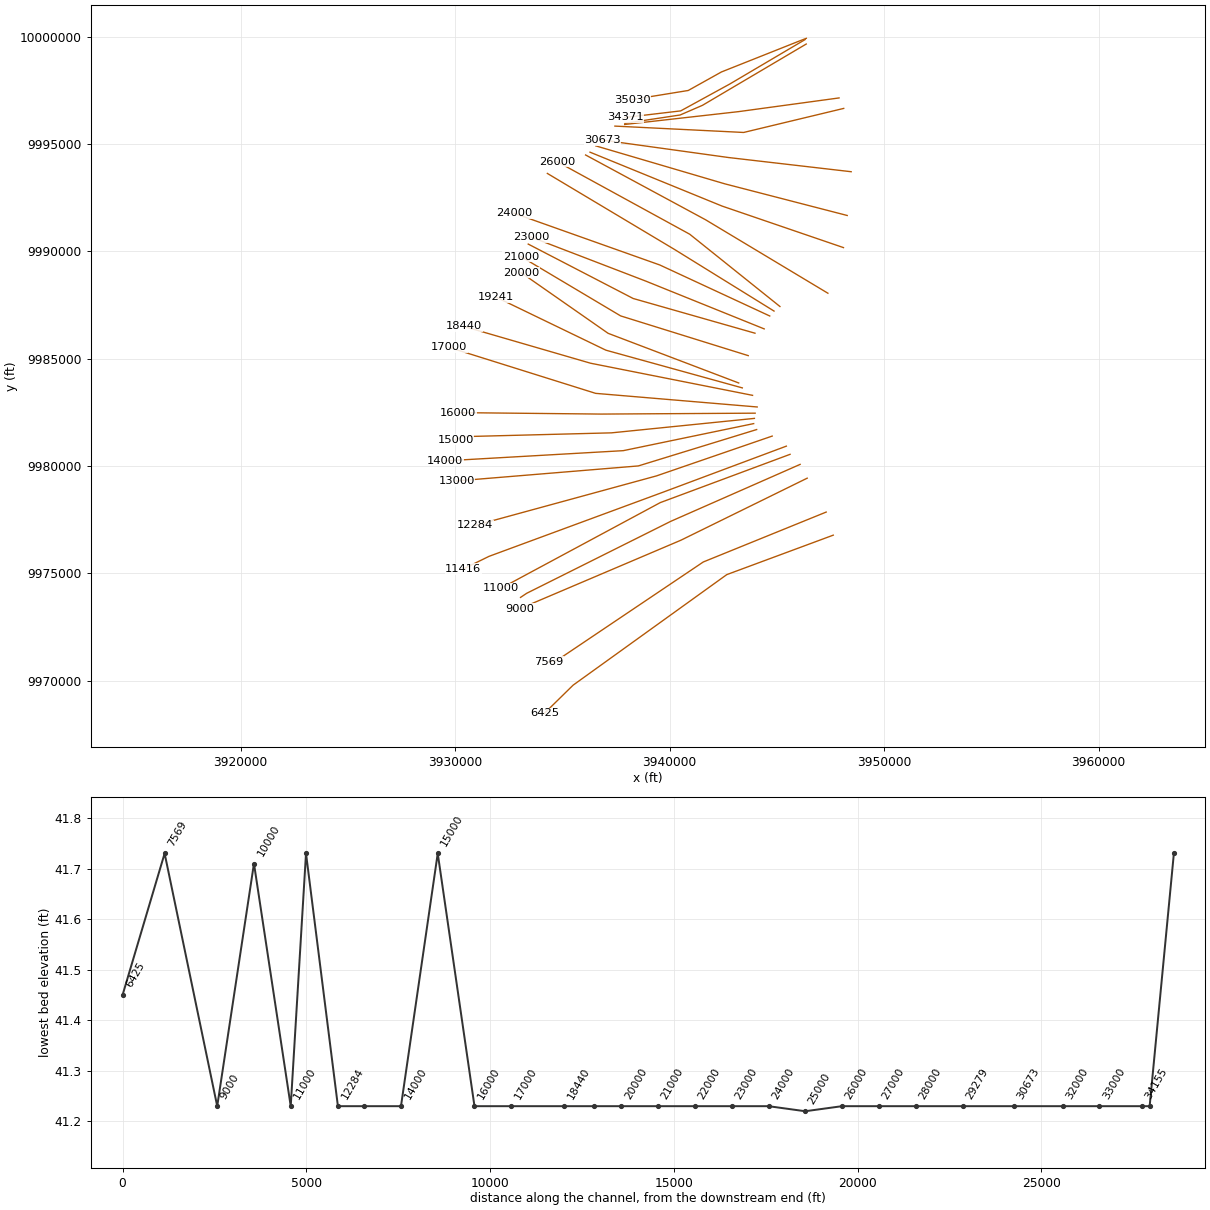
HEC-RAS study WFSJ Main.prj: WFSJ Main Base Level Engineering

--- WFSJ Main.g01 (geometry) --- (continued)

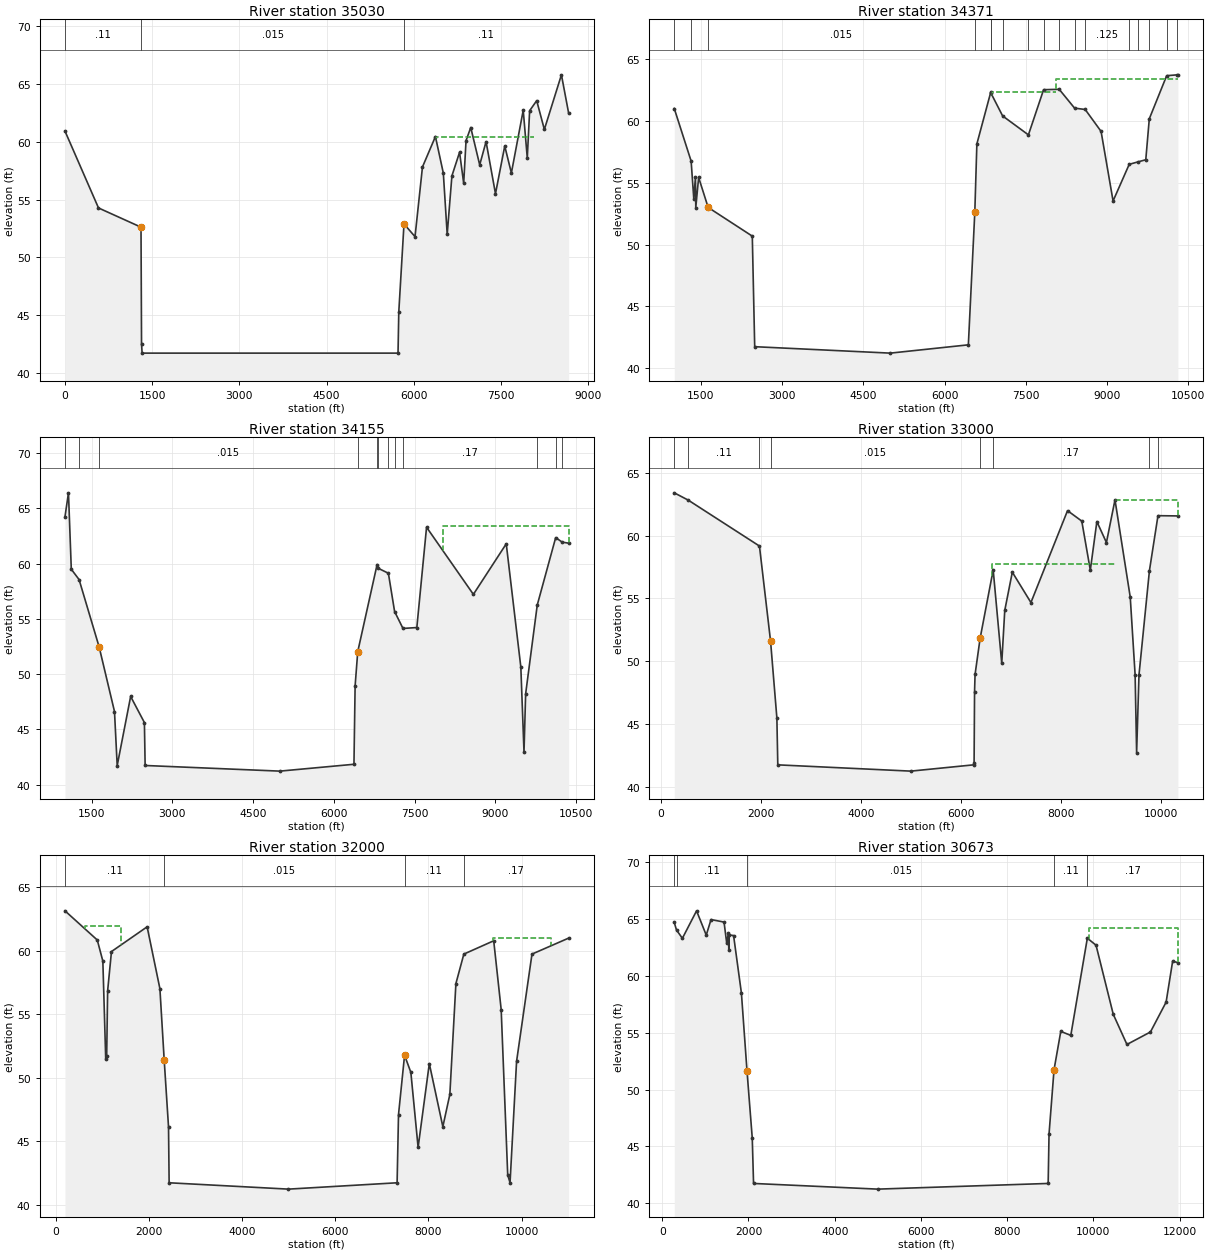
Type RM Length L Ch R = 1 ,35030   ,659,659,659
XS GIS Cut Line= 5
      3946373.53      9999934.04      3945994.53      9999787.74
      3942417.27      9998366.54      3940869.53      9997503.26
      3938265.36      9997080.08
#Sta/Elev= 30
       0   60.91   576.8   54.27  1308.2   52.61  1317.3   42.53  1327.2   41.73
  5730.4   41.73  5743.4   45.27  5833.2   52.89  6022.9   51.79    6151   57.81
  6373.9   60.44  6509.8   57.28  6576.5   51.99  6657.5   57.04  6789.2   59.08
  6860.2    56.4  6900.7   60.09  6981.7   61.22  7135.6   57.99  7245.2      60
  7407.2    55.5  7566.5   59.62  7680.8   57.29  7884.5   62.71  7954.3   58.59
  7994.9   62.67  8116.4   63.54  8248.1   61.05  8541.9   65.77    8666   62.46
#Mann= 3 , 0 , 0
       0     .11       0  1308.2    .015       0  5833.2     .11       0
#XS Ineff= 1 ,-1
  6386.7    8075   60.44
Permanent Ineff=
       F
Bank Sta=1308.2,5833.2
XS Rating Curve= 0 ,0
Exp/Cntr=0.3,0.1

Type RM Length L Ch R = 1 ,34371   ,216,216,216
BEGIN DESCRIPTION:
WFSJ Main 35.0
END DESCRIPTION:
XS GIS Cut Line= 4
      3946317.65      9999876.71      3942801.99      9997802.04
      3940519.01      9996552.04      3937918.18      9996244.58
#Sta/Elev= 30
    1007   60.99  1318.8   56.74  1367.5   53.71  1398.8   55.47  1404.6   52.99
  1457.3   55.42  1632.9      53  2448.5   50.68    2493   41.75  4997.4   41.23
  6439.6    41.9    6559   52.63    6597   58.13    6853    62.3  6853.9   62.26
  7072.6   60.39    7549   58.86  7829.5   62.51  8117.9   62.54  8401.6   61.02
    8598   60.91  8891.4   59.14  9112.9   53.52    9411   56.48  9566.8   56.67
  9717.1   56.85  9782.1   60.16   10103   63.64 10300.7   63.71 10310.9   63.67
#Mann= 17 ,-1 , 0
    1007     .17       0  1318.8     .11       0  1632.9    .015       0
    6559     .11       0    6853     .11       0  6853.9    .125       0
  7072.6     .11       0    7549     .11       0  7829.5     .11       0
  8117.9     .17       0  8401.6     .11       0    8598    .125       0
    9411     .11       0  9566.8    .125       0  9782.1     .11       0
   10103    .125       0 10300.7     .11       0
#XS Ineff= 2 ,-1
  6883.8    8055   62.31  8055.6   10310   63.34
Permanent Ineff=
       F       F
Bank Sta=1632.9,6559
XS Rating Curve= 0 ,0
Exp/Cntr=0.3,0.1

Type RM Length L Ch R = 1 ,34155   ,1155,1155,1155
BEGIN DESCRIPTION:
WFSJ Main 34.0
END DESCRIPTION:
XS GIS Cut Line= 4
       3946369.7      9999668.36      3941534.63      9996812.46
      3940492.97      9996361.07      3937918.18      9995973.32
#Sta/Elev= 30
  1006.5   64.22  1071.3   66.39    1124   59.48  1268.3   58.55  1640.9   52.46
  1926.2   46.62  1976.5   41.73  2226.2   47.98  2481.8   45.62  2495.3   41.74
  4997.4   41.23  6373.8   41.85  6395.2   48.93  6444.1   52.03  6803.8   59.91
  6811.4    59.6  7013.1   59.12  7128.6   55.66  7284.1   54.13  7541.5   54.21
  7722.1   63.28  8591.7   57.21  9202.3   61.78  9473.1   50.64    9532   42.96
  9562.5   48.22  9778.3   56.25 10120.4   62.34 10241.4   61.93 10361.1   61.84
#Mann= 12 ,-1 , 0
  1006.5     .15       0  1268.3     .11       0  1640.9    .015       0
  6444.1     .11       0  6803.8     .15       0  6811.4     .11       0
  7013.1     .15       0  7128.6     .11       0  7284.1     .17       0
  9778.3     .11       0 10120.4     .17       0 10241.4     .11       0
#XS Ineff= 2 ,-1
  6803.8    8024   59.91  8025.4   10361   63.39
Permanent Ineff=
       F       F
Bank Sta=1640.9,6444.1
XS Rating Curve= 0 ,0
Exp/Cntr=0.3,0.1

Type RM Length L Ch R = 1 ,33000   ,1000,1000,1000
BEGIN DESCRIPTION:
WFSJ Main 33.0
END DESCRIPTION:
XS GIS Cut Line= 3
      3947900.75      9997156.03      3943210.99      9996516.93
      3937907.29      9995919.06
#Sta/Elev= 30
   266.9    63.4   545.7   62.82  1970.2   59.16  2192.3   51.59  2318.6   45.46
    2337   41.73  4997.4   41.23    6251   41.73  6261.8   41.85  6271.1   47.56
  6281.2   48.93 6381.82    51.8  6643.5   57.26  6814.6   49.82  6874.9   54.03
  7025.9   57.08  7398.2   54.66    8130   61.98  8414.6   61.15  8585.7   57.24
  8716.5   61.11  8907.7   59.44  9078.8   62.84  9383.9   55.09  9481.3    48.9
  9511.5   42.71  9558.7   48.89  9767.8   57.21  9938.5   61.58 10337.3   61.56
#Mann= 8 ,-1 , 0
   266.9     .17       0   545.7     .11       0  1970.2     .11       0
  2192.3    .015       0 6381.82     .11       0  6643.5     .17       0
  9767.8     .11       0  9938.5     .17       0
#XS Ineff= 2 ,-1
  6616.4    9077    57.7  9078.8   10400   62.84
Permanent Ineff=
       F       F
Bank Sta=2192.3,6381.82
XS Rating Curve= 0 ,0
Exp/Cntr=0.3,0.1

Type RM Length L Ch R = 1 ,32000   ,1327,1327,1327
BEGIN DESCRIPTION:
WFSJ Main 32.0
END DESCRIPTION:
XS GIS Cut Line= 3
      3948117.83      9996667.76      3943453.25      9995546.72
      3937452.17      9995843.07
#Sta/Elev= 30
   202.6   63.16   895.7   60.86  1015.1    59.2  1076.8   51.49  1097.4   51.73
  1117.9   56.86  1200.2   59.95  1965.4    61.9    2239   57.03 2331.3551.40046
  2424.1   46.13  2437.3   41.73  4997.4   41.23  7328.2   41.73  7358.3    47.1
  7488.4   51.78  7623.1   50.43  7778.8   44.52  8019.1   51.12  8309.4   46.15
  8459.6   48.69  8589.8   57.43    8760   59.75  9400.8    60.8    9561   55.38
  9701.1   42.36  9751.2   41.73  9891.4    51.3 10221.8   59.75 11008.4   61.01
#Mann= 4 ,-1 , 0
   202.6     .11       0 2331.35    .015       0  7488.4     .11       0
    8760     .17       0
#XS Ineff= 2 ,-1
     630  1404.4   61.96  9380.7   10640   61.01
Permanent Ineff=
       F       F
Bank Sta=2331.35,7488.4
XS Rating Curve= 0 ,0
Exp/Cntr=0.3,0.1

Type RM Length L Ch R = 1 ,30673   ,1394,1394,1394
BEGIN DESCRIPTION:
WFSJ Main 31.0
END DESCRIPTION:
XS GIS Cut Line= 3
      3948464.99      9993716.37       3942746.7      9994378.26
      3936876.51      9995192.06
#Sta/Elev= 30
   278.6   64.72   330.6   64.05     467   63.32     796   65.74  1020.7    63.6
  1131.4   64.97  1433.4   64.75  1496.2   62.87  1534.1   63.77  1544.1   62.28
  1554.2   63.62  1654.9   63.56  1836.1    58.5  1966.9   51.59  2087.7   45.73
  2117.9   41.73  4997.4   41.23  8951.5   41.73  8971.7   46.08 9087.44   51.74
  9244.3   55.12  9476.5   54.77  9860.2   63.33 10062.1   62.71 10461.1   56.63
 10778.9   53.97   11324   55.07 11687.5    57.7 11838.9    61.3 11961.4   61.18
#Mann= 5 ,-1 , 0
   278.6     .15       0   330.6     .11       0  1966.9    .015       0
 9087.44     .11       0  9860.2     .17       0
#XS Ineff= 2 , 0
                            9900           64.21
Permanent Ineff=
       F       F
Bank Sta=1966.9,9087.44
XS Rating Curve= 0 ,0
Exp/Cntr=0.3,0.1

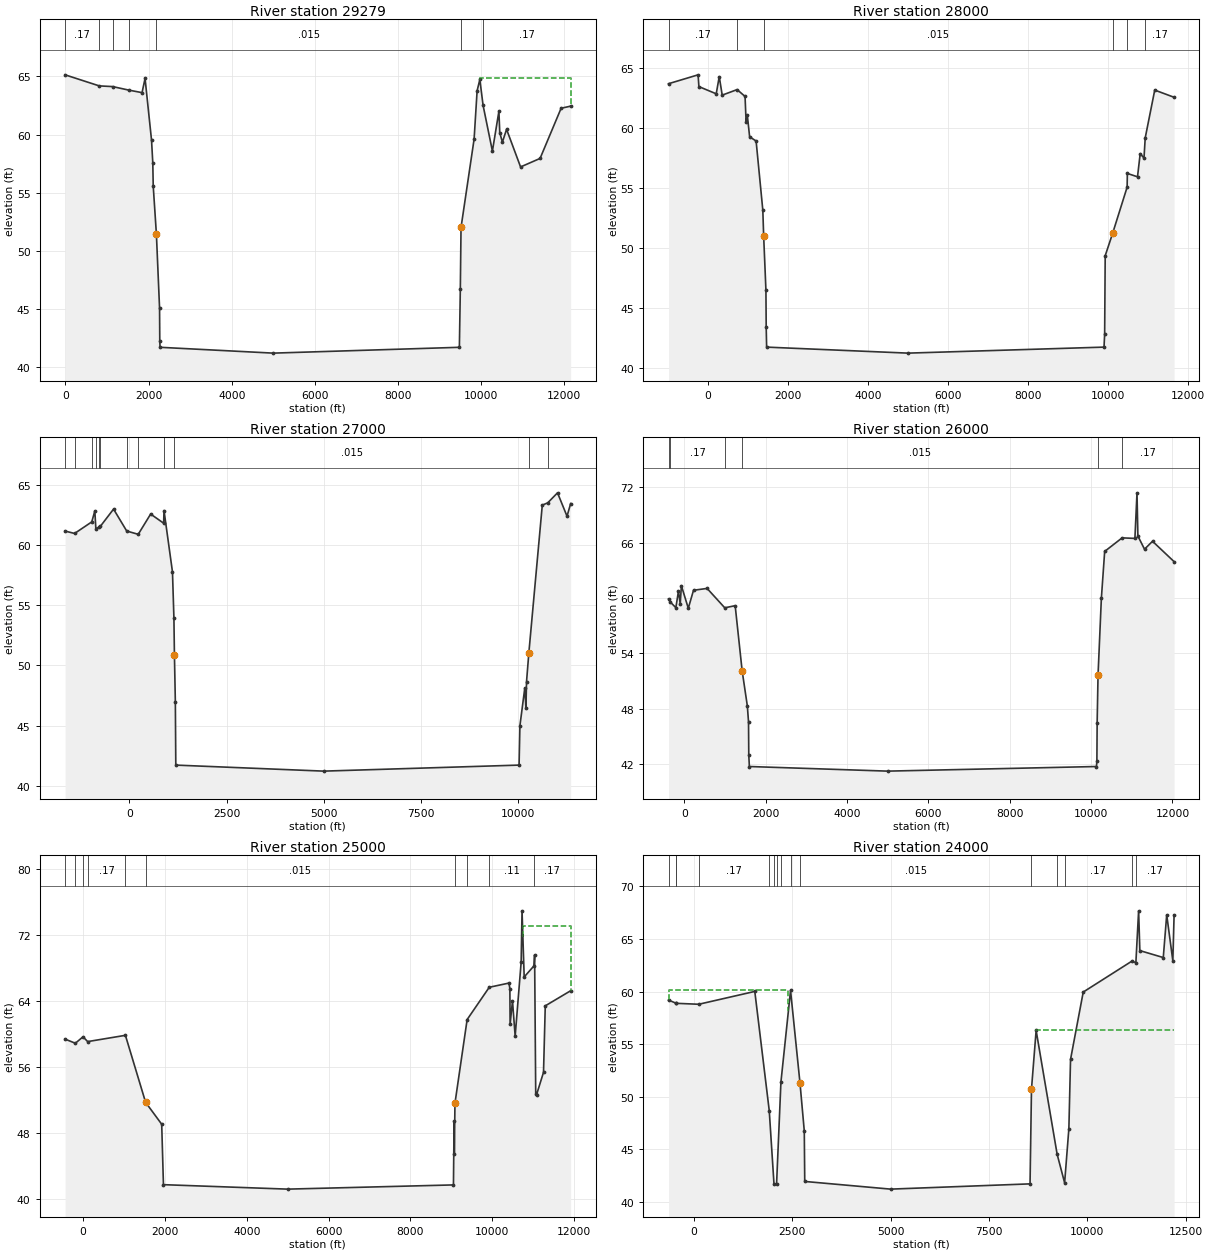
Type RM Length L Ch R = 1 ,29279   ,1279,1279,1279
BEGIN DESCRIPTION:
WFSJ Main 29.0
END DESCRIPTION:
XS GIS Cut Line= 3
       3948280.6      9991676.42      3942573.09      9993152.13
      3936562.36      9994920.63
#Sta/Elev= 30
    -8.9   65.13     813   64.18  1135.5   64.12  1520.5   63.82  1842.8    63.6
  1915.1   64.82  2071.1   59.51    2101   57.57  2111.7   55.57  2187.8   51.45
  2263.9   45.09  2269.1   42.23  2276.6   41.73  4997.4   41.23  9475.4   41.73
  9498.4   46.77 9515.11   52.02  9829.8   59.61  9901.7   63.75  9967.5   64.73
 10045.5   62.51 10269.8   58.58 10426.1      62   10447   60.15 10510.3   59.35
 10610.4   60.45 10947.3   57.22 11416.4   57.95 11922.5   62.26 12151.8   62.44
#Mann= 7 ,-1 , 0
    -8.9     .17       0     813     .15       0  1135.5     .17       0
  1520.5     .11       0  2187.8    .015       0 9515.11     .11       0
 10045.5     .17       0
#XS Ineff= 2 , 0
                         9963.64           64.82
Permanent Ineff=
       F       F
Bank Sta=2187.8,9515.11
XS Rating Curve= 0 ,0
Exp/Cntr=0.3,0.1

Type RM Length L Ch R = 1 ,28000   ,1000,1000,1000
BEGIN DESCRIPTION:
WFSJ Main 28.0
END DESCRIPTION:
XS GIS Cut Line= 3
      3948106.91      9990179.05      3942445.03      9992115.91
      3936291.72      9994627.34
#Sta/Elev= 30
    -984   63.66  -245.2    64.4  -225.1   63.42   207.9   62.82   283.3   64.25
   357.3   62.71   729.6   63.17     928    62.6   953.8   60.51   985.1   61.02
  1042.4   59.24  1204.2   58.89  1371.9   53.13    1393   50.97  1449.3   46.49
  1456.4   43.38    1467   41.73  4997.4   41.23  9895.6   41.73  9911.3   42.81
  9925.1   49.34 10109.5   51.19   10473   55.05 10478.4   56.19 10732.2   55.91
 10799.2   57.84 10894.2   57.47 10924.7   59.15 11162.6   63.13 11646.1   62.53
#Mann= 6 ,-1 , 0
    -984     .17       0   729.6     .11       0    1393    .015       0
 10109.5     .11       0   10473     .11       0 10924.7     .17       0
Bank Sta=1393,10109.5
XS Rating Curve= 0 ,0
Exp/Cntr=0.3,0.1

Type RM Length L Ch R = 1 ,27000   ,1000,1000,1000
BEGIN DESCRIPTION:
WFSJ Main 27.0
END DESCRIPTION:
XS GIS Cut Line= 3
      3947379.92      9988052.32      3941673.97      9991479.15
      3936085.81      9994496.84
#Sta/Elev= 30
 -1655.9   61.14 -1411.1   60.94  -968.7    61.9  -890.3   62.81  -863.7   61.32
  -788.9   61.46  -746.1   61.54  -408.4   62.96   -69.5   61.14   226.1   60.87
   545.8   62.55     880   61.79   889.4   62.84  1107.3   57.75  1144.3   53.93
  1157.7   50.83  1181.1   46.97  1192.8   41.73  4997.4   41.23   10024   41.73
 10045.9      45 10171.5   48.13 10200.7   46.44 10215.3   48.62 10275.3   51.03
 10621.2   63.29 10761.6   63.48 11012.9   64.31 11257.7   62.37 11350.9   63.42
#Mann= 12 ,-1 , 0
 -1655.9     .15       0 -1411.1     .17       0  -968.7     .11       0
  -863.7     .17       0  -788.9     .11       0  -746.1     .17       0
   -69.5     .15       0   226.1     .17       0   889.4     .11       0
  1157.7    .015       0 10275.3     .11       0 10761.6     .17       0
Bank Sta=1157.7,10275.3
XS Rating Curve= 0 ,0
Exp/Cntr=0.3,0.1

Type RM Length L Ch R = 1 ,26000   ,1000,1000,1000
BEGIN DESCRIPTION:
WFSJ Main 26.0
END DESCRIPTION:
XS GIS Cut Line= 3
      3945144.73      9987433.79      3940938.67      9990803.63
      3934762.71      9994183.89
#Sta/Elev= 30
  -389.5   59.88  -351.7   59.59  -208.8   58.94  -144.8   60.75  -101.6   59.35
   -73.2   61.33    96.9   58.88   224.9   60.83   559.4   61.03   993.2   58.93
  1249.3   59.16  1420.5   52.11  1548.6   48.29  1577.4   46.57  1583.8   42.98
  1598.2   41.73  4997.4   41.23 10132.7   41.73 10142.3   42.37 10148.8   46.48
 10170.6   51.62 10252.2   59.94 10333.7   65.04 10762.8   66.51   11077   66.45
 11128.5   71.39 11150.3   66.71 11313.4   65.28 11510.2   66.14 12040.5   63.93
#Mann= 6 ,-1 , 0
  -389.5     .11       0  -351.7     .17       0   993.2     .11       0
  1420.5    .015       0 10170.6     .11       0 10762.8     .17       0
Bank Sta=1420.5,10170.6
XS Rating Curve= 0 ,0
Exp/Cntr=0.3,0.1

Type RM Length L Ch R = 1 ,25000   ,1000,1000,1000
BEGIN DESCRIPTION:
WFSJ Main 25.0
END DESCRIPTION:
XS GIS Cut Line= 3
      3944869.39      9987220.72      3940242.06      9990086.18
      3934303.51      9993636.49
#Sta/Elev= 30
  -442.7   59.39    -191   58.89    -4.4   59.67   110.3   59.09  1032.6   59.85
  1526.6   51.73  1920.1   49.08  1962.6   41.76  4997.4   41.22  9053.4   41.73
    9069   49.43  9074.8   45.46  9090.4   51.63    9388   61.76  9928.7   65.67
 10410.9   66.18 10432.7   65.51 10438.5   61.19 10496.9   64.02 10562.3   59.75
 10708.9   68.73 10730.3   74.93 10782.8   66.92 11023.3   68.27 11037.7   69.59
 11064.9    52.8 11086.6   52.68 11255.5   55.37 11298.3   63.42 11918.9   65.25
#Mann= 10 ,-1 , 0
  -442.7     .15       0    -191     .17       0    -4.4     .15       0
   110.3     .17       0  1032.6     .11       0  1526.6    .015       0
  9090.4     .11       0    9388     .17       0  9928.7     .11       0
 11023.3     .17       0
#XS Ineff= 2 , 0
                        10751.14           73.08
Permanent Ineff=
       F       F
Bank Sta=1526.6,9090.4
XS Rating Curve= 0 ,0
Exp/Cntr=0.3,0.1

Type RM Length L Ch R = 1 ,24000   ,1000,1000,1000
BEGIN DESCRIPTION:
WFSJ Main 24.0
END DESCRIPTION:
XS GIS Cut Line= 3
      3944668.93      9986991.53      3939545.46      9989368.73
      3932757.42      9991779.43
#Sta/Elev= 30
  -648.1    59.2  -464.1   58.91  -453.3   58.89   121.5    58.8    1545   60.02
  1912.1    48.7  2032.9   41.73  2098.9   41.73  2209.5   51.41  2453.9   60.11
  2693.9   51.31    2803   46.76  2814.6   41.96  4997.4   41.23  8541.8   41.73
  8578.4   50.74  8696.5   56.31  9230.7   44.54  9420.6   41.83  9528.7   46.98
  9571.2   53.56  9893.7   59.96   11127   62.89   11232   62.76 11301.6   67.68
 11332.8    63.9 11928.4   63.24 12015.7    67.3 12171.1   62.94 12203.4    67.3
#Mann= 15 ,-1 , 0
  -648.1     .15       0  -464.1     .17       0  -453.3     .15       0
   121.5     .17       0  1912.1     .15       0  2032.9     .17       0
  2098.9     .11       0  2209.5     .17       0  2453.9     .11       0
  2693.9    .015       0  8578.4     .11       0  9230.7     .11       0
  9420.6     .17       0   11127     .11       0   11232     .17       0
#XS Ineff= 2 , 0
            2400   60.18    8700           56.34
Permanent Ineff=
       F       F
Bank Sta=2693.9,8578.4
XS Rating Curve= 0 ,0
Exp/Cntr=0.3,0.1

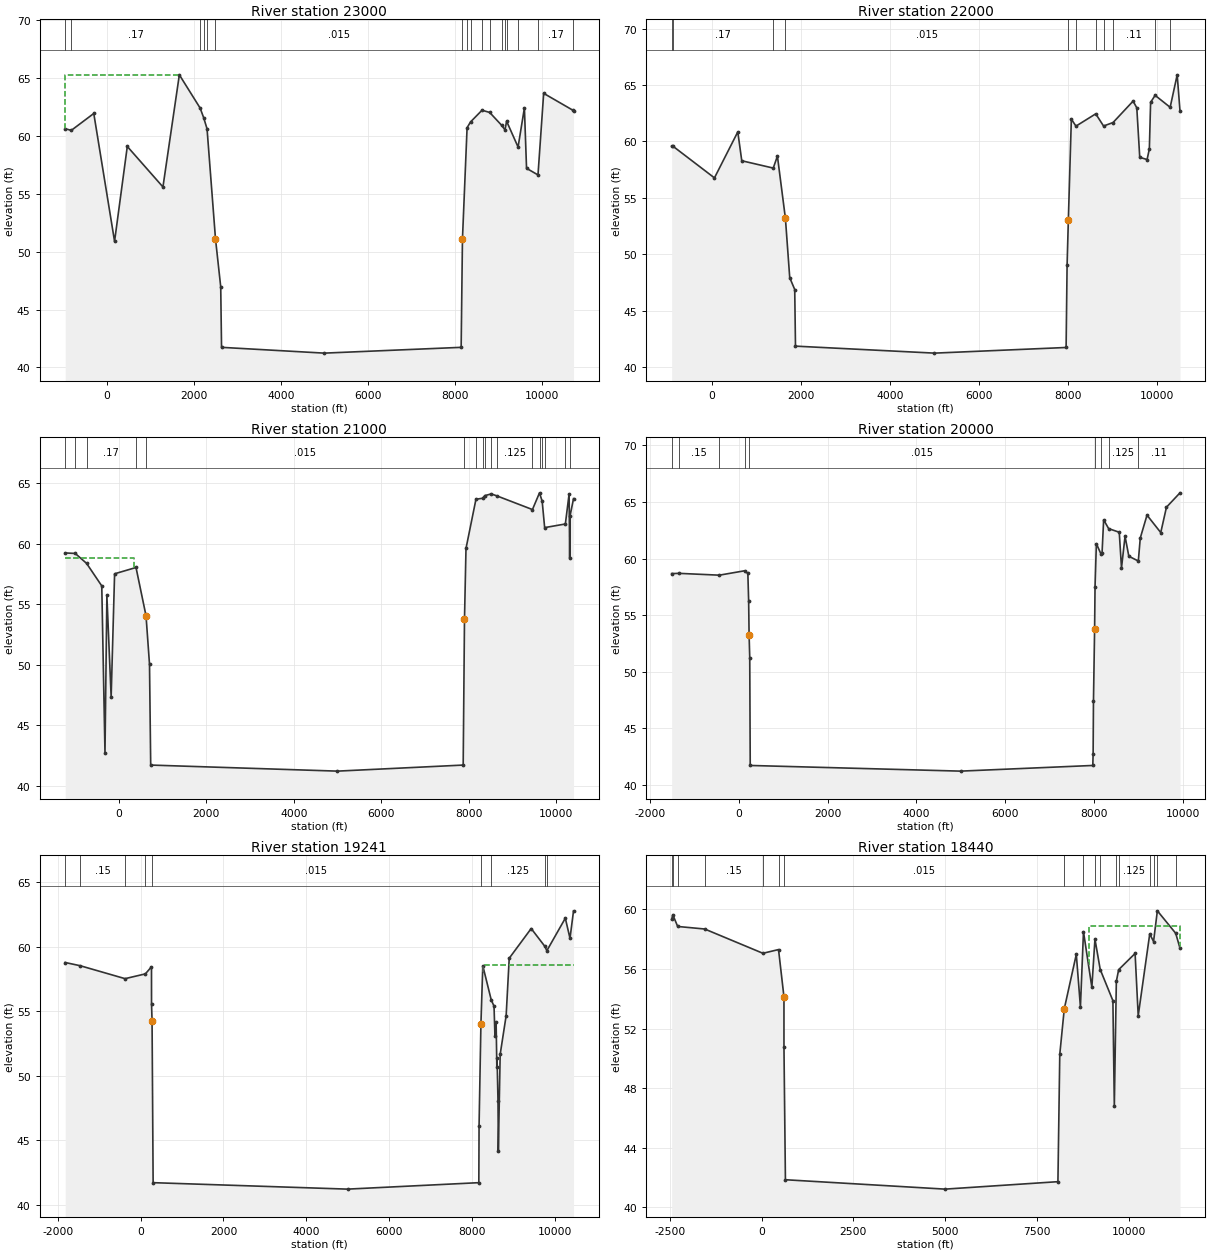
Type RM Length L Ch R = 1 ,23000   ,1000,1000,1000
BEGIN DESCRIPTION:
WFSJ Main 23.0
END DESCRIPTION:
XS GIS Cut Line= 3
      3944411.07      9986389.98      3938887.53      9988618.89
      3933541.41      9990671.99
#Sta/Elev= 30
  -956.3   60.62  -816.5   60.48  -299.6   61.94   178.2   50.89   470.6   59.09
  1290.1   55.59 1667.05   65.28  2144.3   62.41  2226.5   61.57  2303.8   60.61
  2497.9    51.1    2618   46.96  2636.8   41.73  4997.4   41.23  8143.9   41.73
 8173.86   51.09  8280.2   60.71  8359.8   61.21  8623.2   62.22  8799.4   62.03
  9074.1   60.92  9151.3   60.52  9188.7   61.27  9452.2   59.04  9597.5   62.42
  9646.8    57.2    9910   56.63 10040.3   63.68 10721.5    62.2 10726.8   62.15
#Mann= 17 ,-1 , 0
  -956.3     .15       0  -816.5     .17       0  2144.3     .15       0
  2226.5     .17       0  2303.8     .11       0  2497.9    .015       0
 8173.86     .11       0  8280.2    .125       0  8359.8     .11       0
  8623.2    .125       0  8799.4     .11       0  9074.1    .125       0
  9151.3     .11       0  9188.7    .125       0  9452.2     .11       0
    9910     .17       0 10721.5     .11       0
#XS Ineff= 2 , 0
         1659.09   65.28
Permanent Ineff=
       F       F
Bank Sta=2497.9,8173.86
XS Rating Curve= 0 ,0
Exp/Cntr=0.3,0.1

Type RM Length L Ch R = 1 ,22000   ,1000,1000,1000
BEGIN DESCRIPTION:
WFSJ Main 22.0
END DESCRIPTION:
XS GIS Cut Line= 3
      3943981.39      9986189.46      3938303.71        9987807.
      3933411.94      9990342.66
#Sta/Elev= 30
  -903.6   59.58  -875.3   59.58    56.7   56.77   581.1   60.85   670.2   58.29
  1377.2   57.64  1470.8    58.7 1650.26   53.18  1747.3   47.92  1859.3   46.87
  1876.3   41.85  4997.4   41.23  7952.6   41.73  7974.8   49.03  8002.7      53
  8070.3   61.98  8173.9   61.36  8617.5   62.45  8793.9   61.37  9006.9   61.68
    9457   63.58  9539.8   62.98  9606.2   58.59  9771.1    58.4  9821.9   59.34
    9850   63.47  9951.3   64.09 10288.9   63.03 10446.7   65.91 10509.9   62.71
#Mann= 11 ,-1 , 0
  -903.6     .15       0  -875.3     .17       0  1377.2     .11       0
 1650.26    .015       0  8002.7     .11       0  8173.9    .125       0
  8617.5     .11       0  8793.9    .125       0  9006.9     .11       0
  9951.3     .17       0 10288.9     .11       0
Bank Sta=1650.26,8002.7
XS Rating Curve= 0 ,0
Exp/Cntr=0.3,0.1

Type RM Length L Ch R = 1 ,21000   ,1000,1000,1000
BEGIN DESCRIPTION:
WFSJ Main 21.0
END DESCRIPTION:
XS GIS Cut Line= 3
      3943666.29      9985143.88       3937719.9      9986995.12
      3933082.24      9989755.52
#Sta/Elev= 30
 -1227.9   59.23  -998.3   59.19    -739   58.37  -391.7   56.51  -318.3   42.76
  -274.9   55.72  -177.3   47.35   -98.4   57.51   391.4   58.03   620.2   54.05
   699.9   50.05   727.2   41.73  4997.4   41.23  7873.5   41.73 7903.41   53.77
  7937.7    59.6  8165.6   63.66  8315.2   63.74  8369.1   63.96  8515.5    64.1
  8642.6   63.94  9457.4   62.81    9619   64.19  9680.2   63.49  9736.4   61.32
 10210.1   61.62 10295.9    64.1   10309   58.81 10317.6    62.3   10397   63.71
#Mann= 17 ,-1 , 0
 -1227.9     .17       0  -998.3     .15       0    -739     .17       0
   391.4     .11       0   620.2    .015       0 7903.41     .11       0
  8165.6    .125       0  8315.2     .11       0  8369.1    .125       0
  8515.5     .11       0  8642.6    .125       0  9457.4     .11       0
    9619    .125       0  9680.2     .11       0  9736.4    .125       0
 10210.1     .11       0 10317.6    .125       0
#XS Ineff= 2 , 0
          341.42   58.84
Permanent Ineff=
       F       F
Bank Sta=620.2,7903.41
XS Rating Curve= 0 ,0
Exp/Cntr=0.3,0.1

Type RM Length L Ch R = 1 ,20000   ,759,759,759
BEGIN DESCRIPTION:
WFSJ Main 20.0
END DESCRIPTION:
XS GIS Cut Line= 3
      3943222.29      9983869.14      3937136.08      9986183.23
       3933082.3      9989010.63
#Sta/Elev= 30
 -1511.3   58.67 -1341.1   58.69  -438.2   58.53   134.9   58.92   205.2   58.68
   222.9   56.28  233.2853.22231   247.7   51.26   258.7   41.73  4997.4   41.23
  7977.7   41.73  7984.9   42.76  7992.6   47.39 8018.31   53.77  8028.3   57.53
    8058   61.31  8165.3   60.37  8186.2   60.49    8222   63.42  8334.4   62.64
  8573.6   62.32  8624.2   59.17  8704.2   61.96  8789.6    60.2  9003.3   59.78
  9047.3   61.81  9199.1   63.83  9508.9   62.29  9637.1   64.53  9942.4    65.8
#Mann= 9 ,-1 , 0
 -1511.3     .17       0 -1341.1     .15       0  -438.2     .17       0
   134.9     .11       0  233.28    .015       0 8018.31     .11       0
  8165.3    .125       0  8334.4    .125       0  9003.3     .11       0
Bank Sta=233.28,8018.31
XS Rating Curve= 0 ,0
Exp/Cntr=0.3,0.1

Type RM Length L Ch R = 1 ,19241   ,801,801,801
BEGIN DESCRIPTION:
WFSJ Main 19.0
END DESCRIPTION:
XS GIS Cut Line= 3
      3943390.71      9983639.97      3937032.19      9985397.78
      3931911.72      9987871.23
#Sta/Elev= 30
 -1824.9   58.77 -1461.7   58.52  -378.5   57.52   112.5   57.89   260.2   58.44
     261   55.57   273.8   54.26   299.7   41.73  4997.4   41.23  8170.2   41.73
  8175.8   46.13    8221   54.03  8266.2   58.52  8469.6   55.88  8537.4   55.39
    8560   53.06  8588.2   54.15  8605.2   50.72  8610.8   51.37  8633.4   48.07
  8641.7   44.19  8686.1   51.66  8830.5   54.66  8904.6    59.1  9435.5    61.4
  9767.9   60.01  9813.4   59.68 10260.2    62.2 10373.2   60.64 10458.7   62.77
#Mann= 9 ,-1 , 0
 -1824.9     .17       0 -1461.7     .15       0  -378.5     .17       0
   112.5     .11       0   273.8    .015       0    8221     .11       0
  8469.6    .125       0  9767.9    .125       0  9813.4     .11       0
#XS Ineff= 2 , 0
                         8261.36           58.54
Permanent Ineff=
       F       F
Bank Sta=273.8,8221
XS Rating Curve= 0 ,0
Exp/Cntr=0.3,0.1

Type RM Length L Ch R = 1 ,18440   ,1440,1440,1440
BEGIN DESCRIPTION:
WFSJ Main 18.0
END DESCRIPTION:
XS GIS Cut Line= 3
      3943868.12      9983292.75      3936316.05      9984790.15
      3930413.26      9986504.56
#Sta/Elev= 30
 -2449.6   59.33 -2419.4   59.65 -2285.9   58.86 -1551.2   58.69    35.8   57.06
     461   57.31  609.09   54.13   609.1   50.74   648.6   41.86  4997.4   41.23
    8071   41.73  8121.7   50.28    8244   53.33  8571.9   56.99    8684   53.46
  8767.3   58.51  8995.3   54.78  9079.7   58.01  9223.3   55.97  9568.5   53.88
  9607.3    46.8  9662.2   55.17  9725.1   55.96 10173.1   57.05   10258   52.87
 10571.9   58.36 10675.8   57.85 10779.6   59.91 11279.9    58.4 11396.2    57.4
#Mann= 17 ,-1 , 0
 -2449.6     .17       0 -2419.4     .11       0 -2285.9     .17       0
 -1551.2     .15       0    35.8     .17       0     461     .11       0
  609.09    .015       0    8244     .11       0  8767.3    .125       0
  9079.7     .11       0  9223.3    .125       0  9662.2     .11       0
  9725.1    .125       0 10571.9     .11       0 10675.8    .125       0
 10779.6     .11       0 11279.9    .125       0
#XS Ineff= 2 , 0
                         8903.93           58.87
Permanent Ineff=
       F       F
Bank Sta=609.09,8244
XS Rating Curve= 0 ,0
Exp/Cntr=0.3,0.1

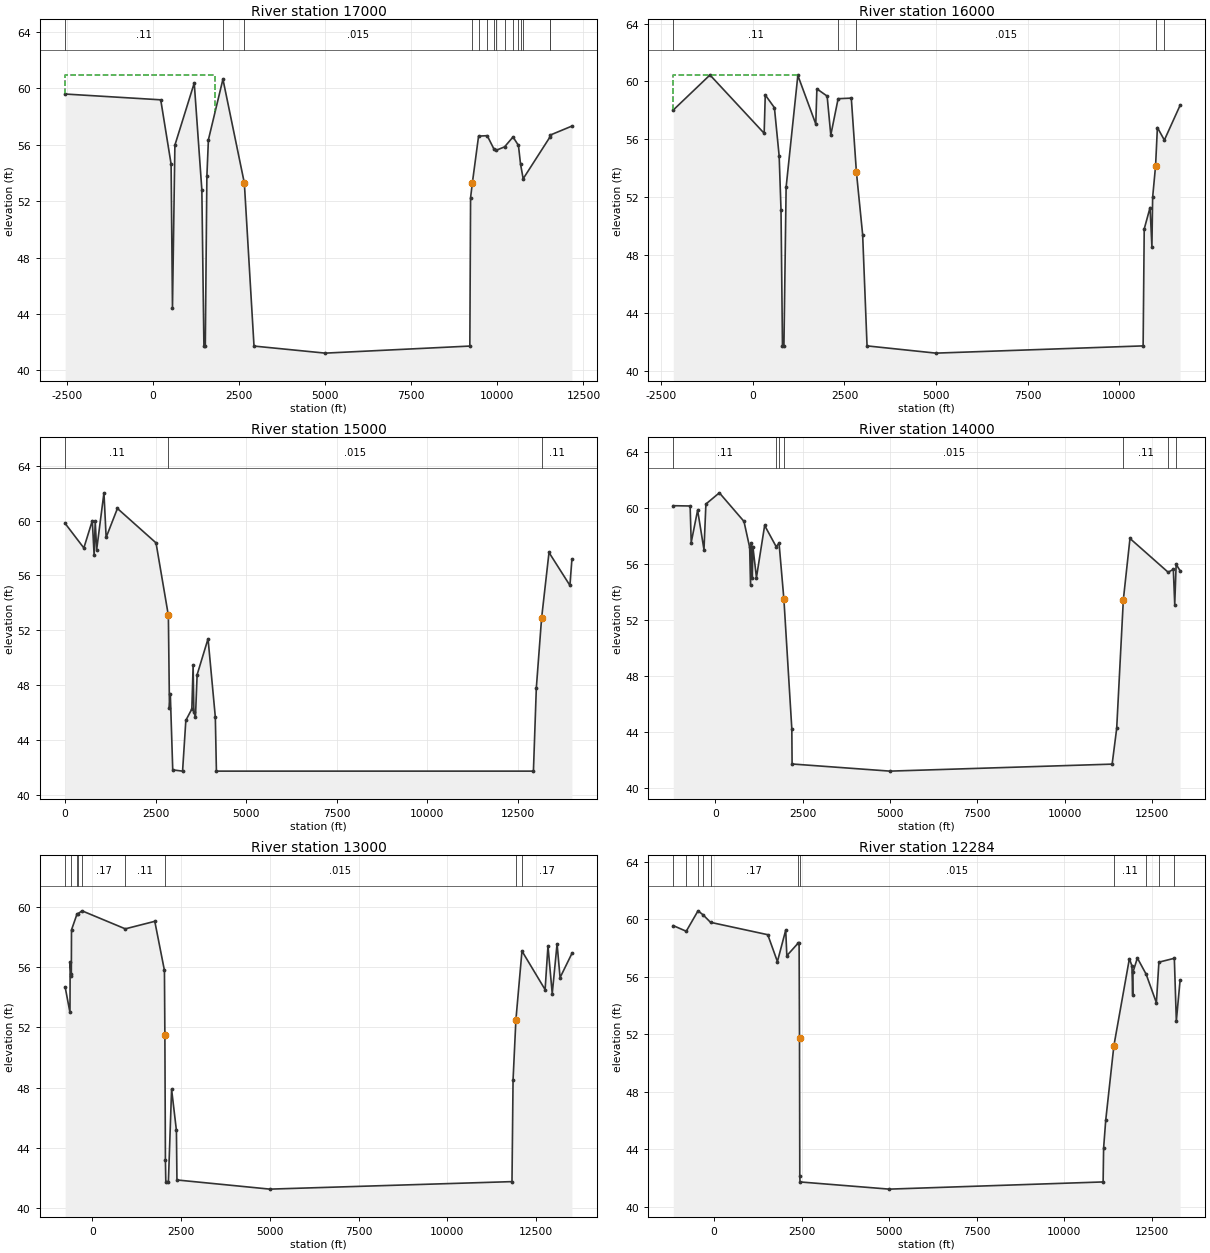
Type RM Length L Ch R = 1 ,17000   ,1000,1000,1000
BEGIN DESCRIPTION:
WFSJ Main 17.0
END DESCRIPTION:
XS GIS Cut Line= 3
      3944085.18      9982750.21      3936554.08      9983384.93
      3929718.86      9985527.98
#Sta/Elev= 30
 -2557.8   59.58   219.3   59.17   520.4   54.62   560.5   44.41   630.8   55.96
  1192.8   60.36  1413.6    52.8  1473.8   41.73  1513.9   41.73  1559.8   53.75
  1604.2   56.34  2026.4   60.63  2647.9   53.28  2928.9   41.73  4997.4   41.23
  9198.5   41.73  9220.1   52.24  9271.9   53.29  9452.4    56.6  9703.3   56.63
  9899.8   55.68  9968.9    55.6   10208   55.84   10453   56.54 10610.5   55.94
 10670.5   54.63 10747.6   53.58 11532.1   56.56   11540   56.68 12163.3   57.31
#Mann= 15 ,-1 , 0
 -2557.8     .11       0  2026.4     .11       0  2647.9    .015       0
  9271.9     .11       0  9452.4     .17       0  9703.3     .11       0
  9899.8     .17       0  9968.9     .11       0   10208    .125       0
   10453     .11       0 10610.5    .125       0 10670.5     .11       0
 10747.6    .125       0 11532.1     .11       0   11540    .125       0
#XS Ineff= 2 , 0
          1799.5   60.94
Permanent Ineff=
       F       F
Bank Sta=2647.9,9271.9
XS Rating Curve= 0 ,0
Exp/Cntr=0.3,0.1

Type RM Length L Ch R = 1 ,16000   ,1000,1000,1000
BEGIN DESCRIPTION:
WFSJ Main 16.0
END DESCRIPTION:
XS GIS Cut Line= 3
      3943989.33      9982461.43      3936814.65      9982419.48
      3930148.59      9982486.89
#Sta/Elev= 30
 -2174.8   58.03 -1173.3   60.45   306.7   56.42   336.7   59.07   586.7   58.19
   716.7   54.84   766.7   51.14   806.7   41.73   846.7   41.73   906.7    52.7
  1226.7   60.42  1716.7   57.06  1746.7   59.49  2026.7   58.99  2126.7    56.3
  2326.8   58.81  2686.8   58.85  2826.8   53.72  2996.8   49.41  3116.8   41.73
  4997.4   41.23 10657.1   41.73 10687.1   49.81 10847.1   51.29 10897.1   48.57
 10917.1      52 10997.1   54.17 11047.1   56.82 11237.1   55.95 11666.4   58.35
#Mann= 5 ,-1 , 0
 -2174.8     .11       0  2326.8     .11       0  2826.8    .015       0
 10997.1     .11       0 11237.1     .17       0
#XS Ineff= 2 , 0
         1227.27   60.46
Permanent Ineff=
       F       F
Bank Sta=2826.8,10997.1
XS Rating Curve= 0 ,0
Exp/Cntr=0.3,0.1

Type RM Length L Ch R = 1 ,15000   ,1000,1000,1000
XS GIS Cut Line= 4
      3943954.65      9982218.37      3937296.48      9981544.57
      3930319.27      9981365.72      3930024.06      9981232.95
#Sta/Elev= 30
       0   59.79   516.9      58   750.6   59.99   800.9   57.47     831   59.93
   871.2   57.88  1072.2   62.02  1132.6   58.77  1444.1   60.88  2510.2   58.37
  2851.3   53.08  2881.4   46.35  2904.8   47.37  2971.9   41.82  3243.3   41.73
  3333.7   45.43  3499.3   46.26  3534.8   49.44  3554.9   46.05  3599.2   45.66
  3645.3   48.76  3946.9   51.38  4147.9   45.67    4178   41.73 12932.9   41.73
 13012.9   47.79   13158  52.872   13363   57.67 13940.4   55.27 13995.4   57.17
#Mann= 3 , 0 , 0
       0     .11       0  2851.3    .015       0   13158     .11       0
#XS Ineff= 1 ,-1
    2800  3946.9   51.38
Permanent Ineff=
       F
Bank Sta=2851.3,13158
XS Rating Curve= 0 ,0
Exp/Cntr=0.3,0.1

Type RM Length L Ch R = 1 ,14000   ,1000,1000,1000
BEGIN DESCRIPTION:
WFSJ Main 14.0
END DESCRIPTION:
XS GIS Cut Line= 3
      3943919.94      9981975.32       3937841.5      9980714.14
      3929544.98      9980239.21
#Sta/Elev= 30
 -1207.9   60.19  -725.8   60.17  -695.1   57.56  -511.3   59.87  -329.1   57.05
  -273.8   60.31   111.7   61.11   816.4   59.07   979.8   57.21  1004.4   54.51
  1030.9   57.54  1054.5   55.02  1071.7   57.27  1173.9   55.06  1408.8   58.78
    1738   57.27  1821.6   57.51  1960.3   53.51  2187.4   44.25  2195.2   41.74
  4997.4   41.23   11364   41.73 11494.3   44.28 11684.6   53.47 11874.9   57.85
 12967.5   55.44 13116.9   55.64   13157   53.13 13197.6      56 13310.1   55.55
#Mann= 7 ,-1 , 0
 -1207.9     .11       0    1738    .125       0  1821.6     .11       0
  1960.3    .015       0 11684.6     .11       0 12967.5     .17       0
 13197.6     .17       0
Bank Sta=1960.3,11684.6
XS Rating Curve= 0 ,0
Exp/Cntr=0.3,0.1

Type RM Length L Ch R = 1 ,13000   ,716,716,716
BEGIN DESCRIPTION:
WFSJ Main 13.0
END DESCRIPTION:
XS GIS Cut Line= 3
       3944058.8      9981697.54      3938543.95       9980002.4
      3930065.75      9979301.71
#Sta/Elev= 30
  -769.5    54.7  -633.1      53  -627.8   56.34  -603.9   55.59  -595.1   55.41
  -589.9    58.5    -437   59.54    -400   59.59  -293.7   59.77   925.6   58.57
  1756.1   59.07  2028.2    55.8 2040.44   51.51  2055.7   43.15  2066.6   41.73
  2139.9   41.73  2229.7   47.88  2365.8   45.14  2380.5   41.84  4997.4   41.23
 11819.3   41.73 11849.4    48.5 11929.6   52.51 12100.2   57.09 12752.4   54.52
 12832.7   57.43 12953.1   54.25 13089.2   57.57 13173.9   55.32 13507.1   56.93
#Mann= 9 ,-1 , 0
  -769.5     .17       0  -603.9     .15       0    -437     .17       0
    -400     .15       0  -293.7     .17       0   925.6     .11       0
 2040.44    .015       0 11929.6     .11       0 12100.2     .17       0
Bank Sta=2040.44,11929.6
XS Rating Curve= 0 ,0
Exp/Cntr=0.3,0.1

Type RM Length L Ch R = 1 ,12284   ,868,868,868
BEGIN DESCRIPTION:
Mapping XS cd349adf
END DESCRIPTION:
XS GIS Cut Line= 3
      3944783.62      9981393.71      3939384.34      9979536.08
      3930931.21      9977227.53
#Sta/Elev= 30
 -1166.8   59.55  -797.2   59.16  -460.8   60.58  -315.6    60.3  -104.1   59.78
  1530.8   58.92  1806.6   57.05  2043.6   59.24  2075.3   57.46  2389.4   58.31
  2425.9   58.31 2437.16   51.75  2445.5   42.16  2451.9   41.73  4997.4   41.23
 11108.1   41.73   11122   44.08 11182.4   46.02 11415.5    51.2   11858   57.25
 11930.6   56.76 11951.3   54.76 11961.7   56.33 12086.1    57.3 12335.3   56.18
 12629.2   54.19 12701.3   57.01 13141.8   57.28 13198.9   52.92 13305.8   55.75
#Mann= 11 ,-1 , 0
 -1166.8     .17       0  -797.2     .15       0  -460.8     .17       0
  -315.6     .15       0  -104.1     .17       0  2389.4     .11       0
 2437.16    .015       0 11415.5     .11       0 12335.3    .125       0
 12701.3     .11       0 13141.8    .125       0
Bank Sta=2437.16,11415.5
XS Rating Curve= 0 ,0
Exp/Cntr=0.3,0.1

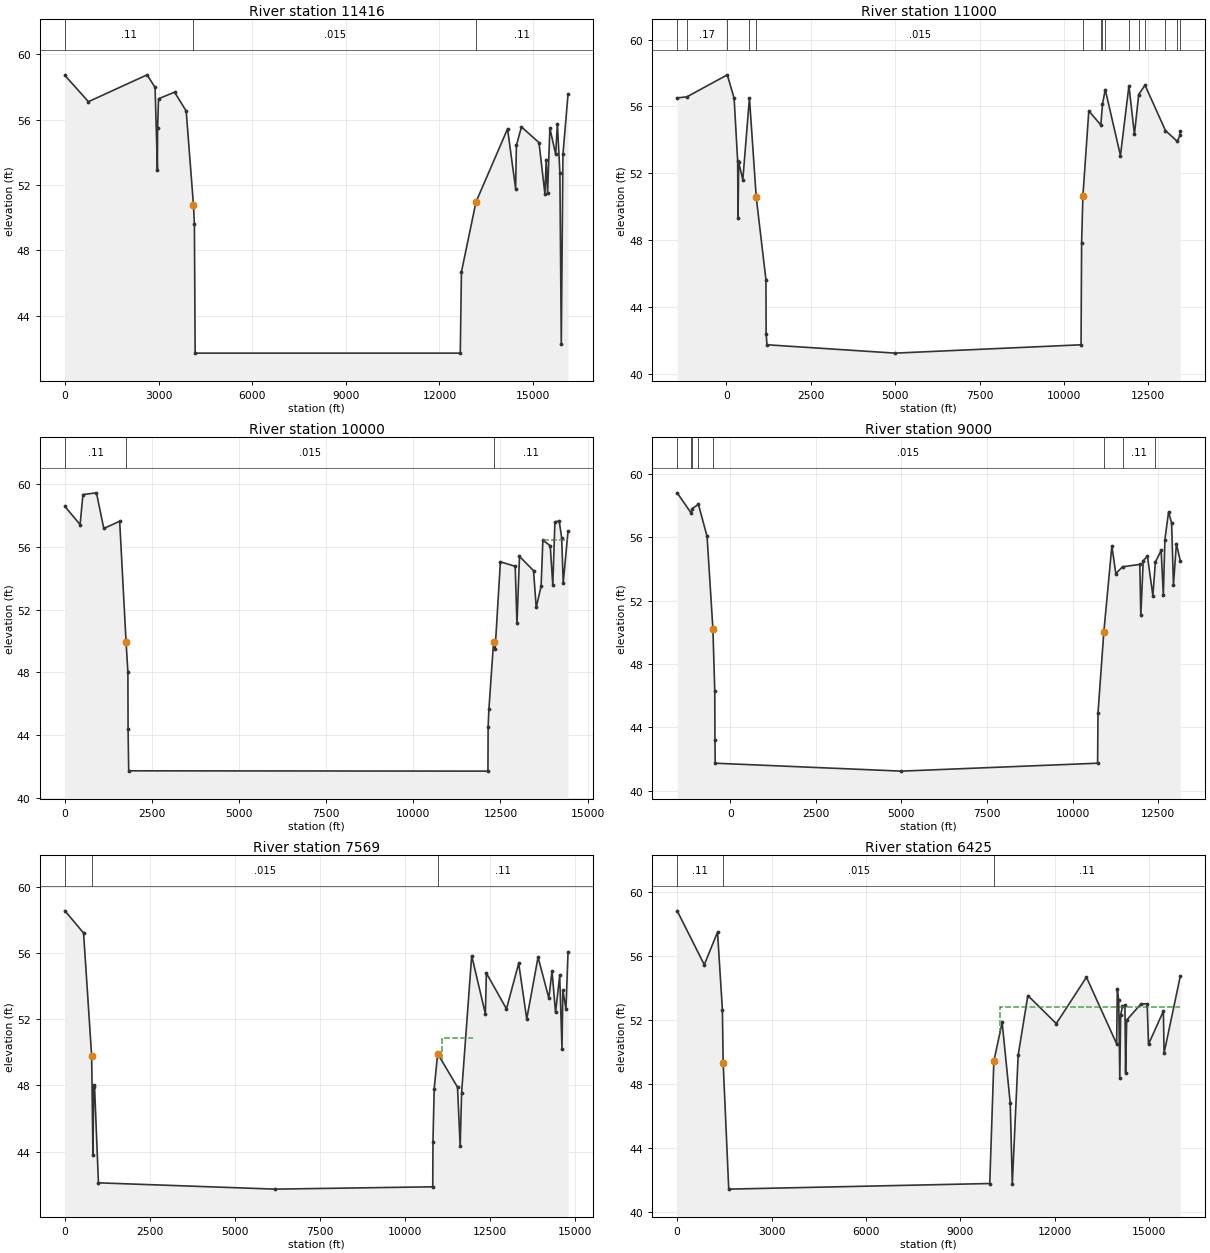
Type RM Length L Ch R = 1 ,11416   ,416,416,416
XS GIS Cut Line= 4
      3945443.37      9980924.97      3939679.48      9978772.19
       3931586.5      9975788.76      3930380.17      9975199.24
#Sta/Elev= 30
       0   58.69   753.1   57.09  2631.9   58.73  2888.5   57.96  2962.8   52.94
  2968.7   55.51    2999   57.27  3512.4   57.67    3885   56.52  4117.5  50.783
  4147.7   49.64    4172   41.73 12666.5   41.73 12704.1   46.69 13169.8   50.96
   14182   55.43   14440   51.78 14465.1   54.42 14627.5   55.55 15188.5   54.59
 15379.9   51.44 15419.3   53.55 15464.4   51.51 15537.5   55.47 15723.2   53.88
 15778.4   55.75 15858.3   52.75 15903.3   42.27 15956.5   53.87 16119.4   57.55
#Mann= 3 , 0 , 0
       0     .11       0  4117.5    .015       0 13169.8     .11       0
#XS Ineff= 1 ,-1
   14182   16105   55.43
Permanent Ineff=
       F
Bank Sta=4117.5,13169.8
XS Rating Curve= 0 ,0
Exp/Cntr=0.3,0.1

Type RM Length L Ch R = 1 ,11000   ,1000,1000,1000
BEGIN DESCRIPTION:
WFSJ Main 11.0
END DESCRIPTION:
XS GIS Cut Line= 3
      3945617.01      9980543.04      3939565.45      9978292.18
      3932127.39      9974293.02
#Sta/Elev= 30
 -1456.6   56.51 -1170.5   56.57    28.6   57.89   230.4   56.48   334.9   52.73
   346.4   49.34   366.1   52.66   487.5    51.6   683.9   56.51   885.6   50.55
  1173.1   45.62  1178.4    42.4  1203.5   41.73  4997.4   41.23 10506.4   41.73
 10522.7    47.8 10560.6   50.63 10736.1   55.73 11091.6   54.89 11141.1   56.13
   11223   57.01 11673.3   53.06 11924.7   57.24 12087.4   54.33 12213.8   56.71
 12400.8   57.27 13007.6   54.55   13360    53.9 13431.5   54.26   13445    54.5
#Mann= 15 ,-1 , 0
 -1456.6     .15       0 -1170.5     .17       0    28.6     .15       0
   683.9     .11       0   885.6    .015       0 10560.6     .11       0
 11091.6     .17       0 11141.1     .11       0   11223     .11       0
 11924.7     .11       0 12213.8     .11       0 12400.8     .11       0
 13007.6     .11       0   13360    .125       0 13431.5     .11       0
Bank Sta=885.6,10560.6
XS Rating Curve= 0 ,0
Exp/Cntr=0.3,0.1

Type RM Length L Ch R = 1 ,10000   ,1000,1000,1000
XS GIS Cut Line= 4
      3946085.73      9980074.28       3940049.7      9977417.25
      3933340.53      9974065.85      3933052.48      9973873.72
#Sta/Elev= 30
       0   58.56   434.7   57.41   516.7   59.32   904.5   59.43    1115   57.16
    1571   57.62  1754.6   49.93  1806.7   48.01  1812.2    44.4    1830   41.73
 12141.4   41.71 12147.1   44.51 12169.5   45.66 12303.7   49.94 12348.4   49.49
 12499.1   55.04 12923.9   54.75 12974.7   51.11 13047.4   55.38   13450   54.48
 13527.5   52.13 13668.1   53.49 13718.4   56.42 13929.9   56.06 14003.6   53.53
 14064.1   57.58 14186.2   57.64 14258.3   56.57 14302.2   53.69 14440.6   56.99
#Mann= 3 , 0 , 0
       0     .11       0  1754.6    .015       0 12303.7     .11       0
#XS Ineff= 2 ,-1
 12499.1   13700   55.04 13728.7   14450   56.44
Permanent Ineff=
       F       F
Bank Sta=1754.6,12303.7
XS Rating Curve= 0 ,0
Exp/Cntr=0.3,0.1

Type RM Length L Ch R = 1 ,9000    ,1431,1431,1431
BEGIN DESCRIPTION:
WFSJ Main 9.0
END DESCRIPTION:
XS GIS Cut Line= 3
      3946415.57      9979431.91      3940533.95      9976542.32
      3933034.81      9973353.67
#Sta/Elev= 30
 -1553.1    58.8 -1144.1   57.52 -1110.2   57.81  -932.4   58.07  -679.6   56.05
  -508.3   50.19  -454.7   46.31  -449.2   43.22  -441.5   41.73  4997.4   41.23
 10733.2   41.73   10745   44.91   10916   50.03 11150.5   55.45 11265.7    53.7
 11461.4   54.13 11966.9   54.28   11996   51.06 12066.9   54.52 12189.3    54.8
 12348.7   52.31 12421.7   54.43 12591.4   55.16 12654.2   52.32 12700.1   55.85
 12806.9   57.59 12895.7   56.91   12950   52.98   13036   55.59 13148.9   54.52
#Mann= 8 ,-1 , 0
 -1553.1     .15       0 -1144.1     .11       0 -1110.2     .17       0
  -932.4     .11       0  -508.3    .015       0   10916     .11       0
 11461.4     .11       0 12421.7     .11       0
Bank Sta=-508.3,10916
XS Rating Curve= 0 ,0
Exp/Cntr=0.3,0.1

Type RM Length L Ch R = 1 ,7569    ,1144,1144,1144
XS GIS Cut Line= 4
      3947301.01      9977852.06      3941571.84      9975525.67
      3934759.15      9970943.83      3934358.25       9970859.4
#Sta/Elev= 30
       0   58.54     548    57.2   786.3   49.76   823.7   43.81   845.3   47.89
   869.3   48.01   985.6   42.11  6182.4   41.73 10822.9   41.87 10828.9   44.59
 10864.9   47.79 10966.8   49.91 11551.1   47.89 11629.7   44.31 11671.8   47.56
 11968.7   55.83 12370.7   52.32 12400.6   54.78 12991.6   52.62 13351.5   55.37
 13588.5   52.01 13921.4   55.74 14238.5   53.27 14332.3    54.9 14436.1    52.4
 14558.4   54.64 14625.1   50.21 14650.4   53.75 14742.4   52.61 14803.3   56.04
#Mann= 3 , 0 , 0
       0     .11       0   786.3    .015       0 10966.8     .11       0
#XS Ineff= 1 ,-1
   11081   12000   50.84
Permanent Ineff=
       F
Bank Sta=786.3,10966.8
XS Rating Curve= 0 ,0
Exp/Cntr=0.3,0.1

Type RM Length L Ch R = 1 ,6425    ,1157,1157,1157
XS GIS Cut Line= 4
      3947630.87      9976775.67      3942665.59      9974935.39
      3935501.24      9969781.18       3934162.5       9968467.9
#Sta/Elev= 30
       0    58.8   861.9   55.44    1283   57.47  1437.6   52.64  1462.6   49.31
  1639.6   41.45  9938.8    41.8 10068.9   49.42 10332.8   51.85 10590.6    46.8
 10655.6   41.76 10842.2    49.8 11150.3   53.52 12053.7   51.77 13013.6   54.66
 13973.5   50.51 13994.4   53.92 14038.5   53.22 14074.1   48.35 14101.2   52.32
 14158.9   52.84 14236.8   52.92 14257.9   48.72 14293.3   51.99 14738.8   52.98
 14943.8   53.01 14986.3   50.48   15460   52.55 15481.3   49.93 15996.2   54.72
#Mann= 3 , 0 , 0
       0     .11       0  1462.6    .015       0 10068.9     .11       0
#XS Ineff= 1 ,-1
 10255.4 15996.2   52.82
Permanent Ineff=
       F
Bank Sta=1462.6,10068.9
XS Rating Curve= 0 ,0
Exp/Cntr=0.3,0.1