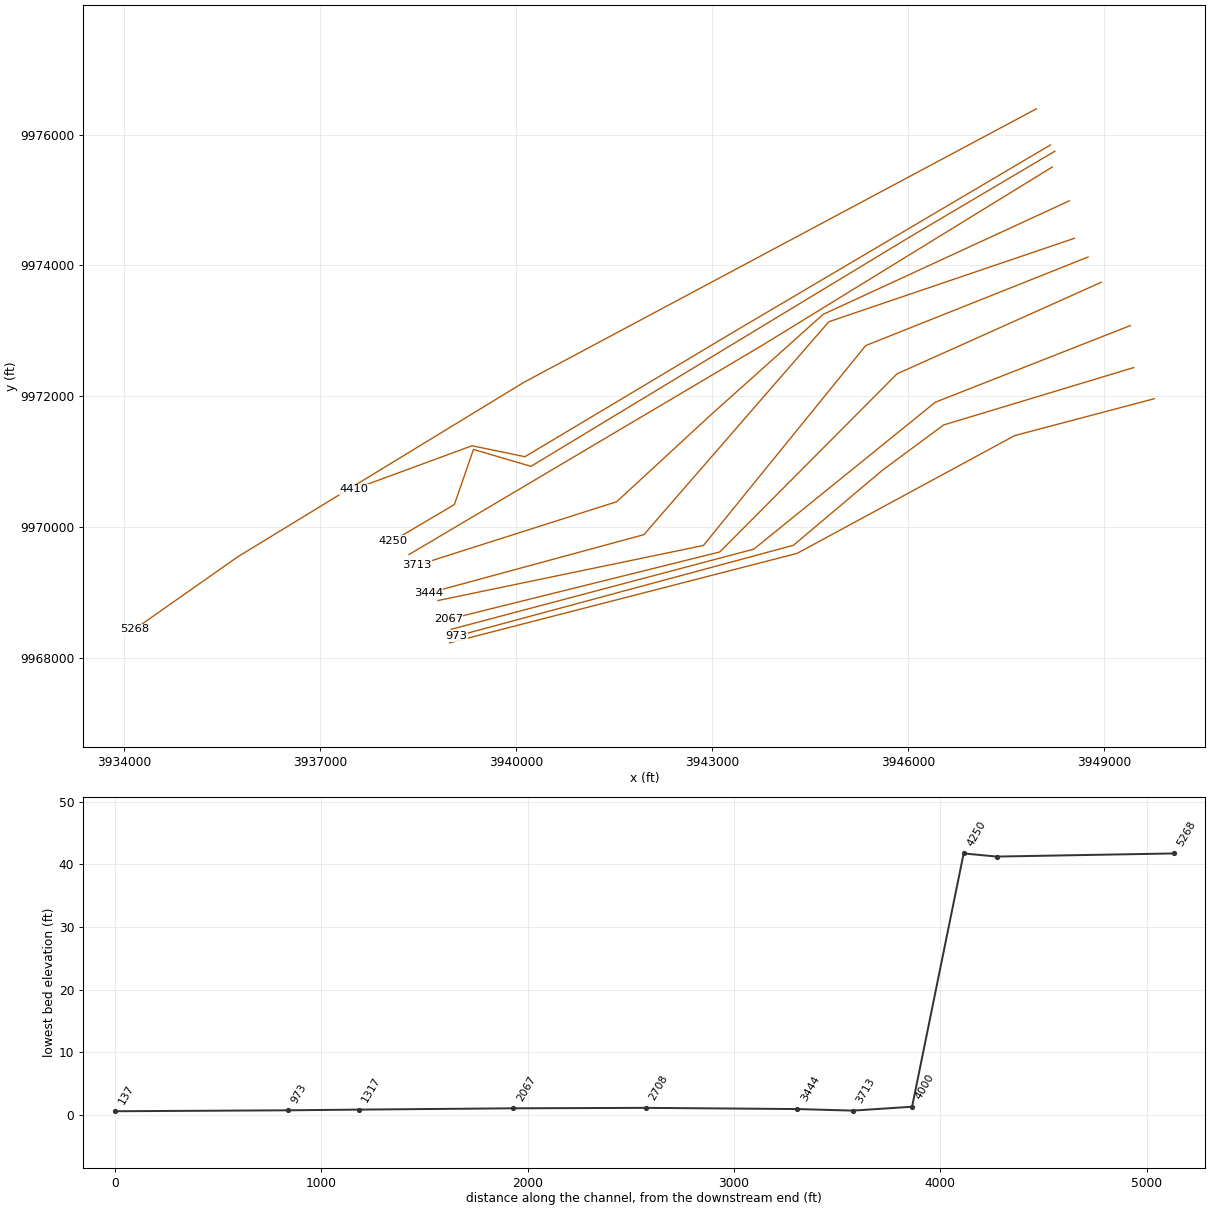
HEC-RAS study WFSJ Main.prj: WFSJ Main Base Level Engineering

--- WFSJ Main.g01 (geometry) --- (continued)

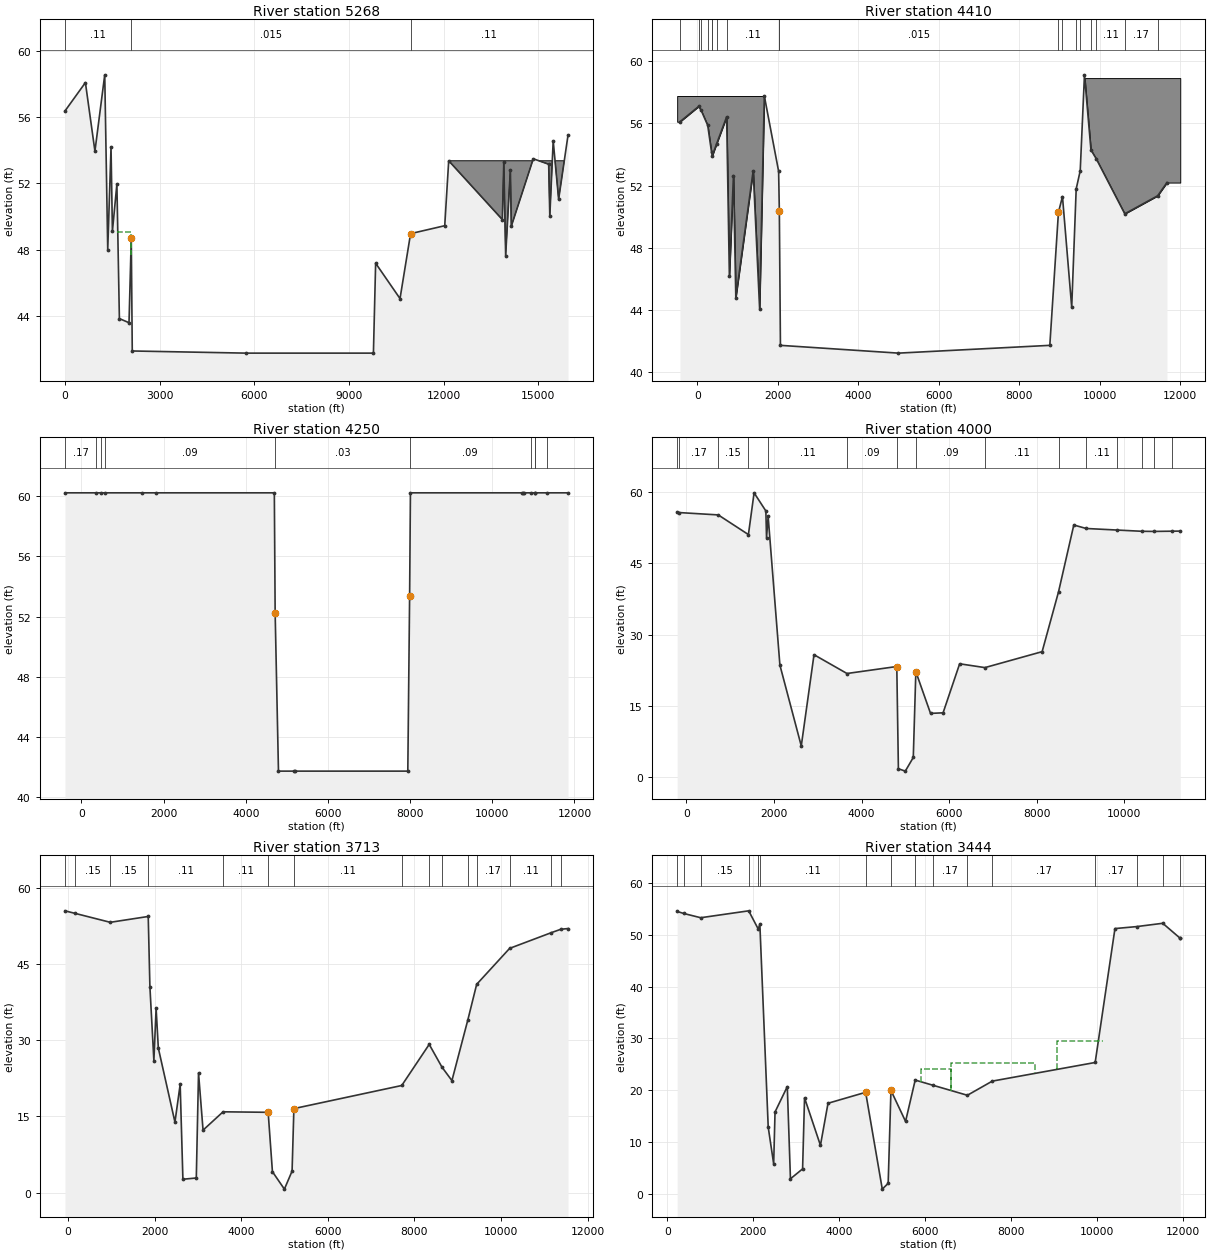
Type RM Length L Ch R = 1 ,5268    ,858,858,858
XS GIS Cut Line= 4
      3947960.73      9976393.72      3940113.51      9972209.69
      3935741.35       9969546.2       3934157.7      9968434.91
#Sta/Elev= 30
       0   56.38   648.7    58.1   950.5   53.95  1261.2   58.57  1356.4   47.99
  1460.5   54.19  1504.5   49.11  1646.5   51.96  1725.8   43.82  2030.8   43.57
  2102.3   48.68  2133.8   41.86  5738.5   41.73  9777.8   41.73  9848.1   47.17
 10620.9   45.03 10955.6   48.96 12038.3   49.44 12164.1   53.37 13864.6   49.81
   13911    53.3 13969.1   47.63 14118.9   52.82 14148.6   49.41 14844.9   53.49
   15333   53.16 15368.7   50.01 15475.9   54.58 15648.5   51.04 15946.2   54.92
#Mann= 3 , 0 , 0
       0     .11       0  2102.3    .015       0 10955.6     .11       0
#XS Ineff= 1 ,-1
    1660  2088.5   49.05
Permanent Ineff=
       F
#Block Obstruct= 1 ,-1
 12164.1 15946.2   53.37
Bank Sta=2102.3,10955.6
XS Rating Curve= 0 ,0
Exp/Cntr=0.3,0.1

Type RM Length L Ch R = 1 ,4410    ,160,160,160
BEGIN DESCRIPTION:
WFSJ Main 5.0
END DESCRIPTION:
XS GIS Cut Line= 5
      3948176.76      9975841.98      3943319.99       9972977.4
      3940133.12       9971074.8      3939324.13      9971242.58
      3937518.61      9970578.53
#Sta/Elev= 30
  -430.7   56.11    34.8    57.1    93.2   56.86   258.8   55.88   354.1   54.15
   370.8   53.92   482.7   54.71     729   56.43   797.1   46.19   898.6   52.65
   957.1    44.8  1388.4   52.96  1548.4    44.1  1665.5   57.77  2020.552.92557
  2038.3   50.38  2065.5   41.73  4997.4   41.23  8758.9   41.73    8973   50.28
  9073.3    51.3  9302.8   44.18  9414.1   51.79  9514.4   52.96  9619.8   59.13
    9781    54.3  9912.5   53.73 10621.5   50.19 11438.3   51.35 11669.5    52.2
#Mann= 18 ,-1 , 0
  -430.7     .17       0    34.8     .11       0    93.2     .11       0
   258.8     .11       0   354.1     .15       0   370.8     .11       0
   482.7     .15       0     729     .11       0  2020.5     .11       0
  2038.3    .015       0    8973     .11       0  9073.3     .11       0
  9414.1     .11       0  9514.4     .17       0    9781    .125       0
  9912.5     .11       0 10621.5     .17       0 11438.3     .11       0
#XS Ineff= 1 ,-1
  9073.3    9510    51.3
Permanent Ineff=
       F
#Block Obstruct= 2 ,-1
    9620   12000   58.92    -500  1665.5   57.77
Bank Sta=2038.3,8973
XS Rating Curve= 0 ,0
Exp/Cntr=0.5,0.3

Type RM Length L Ch R = 1 ,4250    ,250,250,250
BEGIN DESCRIPTION:
Mapping XS 4ca105be
Elevations from the TWDB website
END DESCRIPTION:
XS GIS Cut Line= 6
      3948244.09      9975745.96      3945995.86      9974417.86
      3940226.75      9970927.54      3939345.83      9971186.16
      3939055.03      9970344.14       3938122.4      9969793.24
#Sta/Elev= 22
    -401   60.23   361.1   60.23   473.2   60.23   585.2   60.23  1481.3   60.23
    1809   60.23    4696   60.23    4716  52.225  4796.6   41.73    5177   41.73
    5200   41.73    7945   41.73    7989  53.342    8009   60.23   10731   60.23
 10760.9   60.23 10770.3   60.23 10934.1   60.23 11046.1   60.23 11053.2   60.23
 11324.7   60.23 11845.1   60.23
#Mann= 10 ,-1 , 0
    -401     .17       0   361.1     .15       0   473.2     .17       0
   585.2     .09       0    4716     .03       0    7989     .09       0
 10934.1     .17       0 11046.1     .11       0 11053.2     .17       0
 11324.7     .11       0
Bank Sta=4716,7989
XS Rating Curve= 0 ,0
Exp/Cntr=0.5,0.3

Type RM Length L Ch R = 1 ,4000    ,287,287,287
BEGIN DESCRIPTION:
WFSJ Main 4.0
END DESCRIPTION:
XS GIS Cut Line= 3
       3948202.8      9975503.44      3943761.23      9972775.33
      3938359.02      9969578.95
#Sta/Elev= 30
  -212.5   55.67  -179.4   55.65   725.3   55.15  1414.4   51.02    1544   59.79
  1812.7   55.98  1828.2   50.36  1864.9   54.82  2133.6   23.59  2621.6    6.61
  2912.5   25.78  3665.6   21.83  4803.1    23.3  4839.7    1.82  4997.4    1.32
  5179.7    4.19  5238.2   22.21  5573.6   13.45  5860.3   13.57  6238.6   23.87
  6815.4   23.07  8122.3   26.42  8496.3   38.97  8845.8   53.03  9126.9    52.3
    9834   51.97 10401.3   51.71 10672.1   51.68 11081.3   51.73   11277   51.75
#Mann= 15 ,-1 , 0
  -212.5     .15       0  -179.4     .17       0   725.3     .15       0
  1414.4     .17       0  1864.9     .11       0  3665.6     .09       0
  4803.1     .03       0  5238.2     .09       0  6815.4     .11       0
  8496.3     .11       0  9126.9     .11       0    9834     .11       0
 10401.3     .11       0 10672.1     .17       0 11081.3     .11       0
Bank Sta=4803.1,5238.2
XS Rating Curve= 0 ,0
Exp/Cntr=0.5,0.3

Type RM Length L Ch R = 1 ,3713    ,269,269,269
BEGIN DESCRIPTION:
Mapping XS 49cbcb47
END DESCRIPTION:
XS GIS Cut Line= 5
      3948464.77      9974987.38      3944697.39      9973251.26
      3942978.64       9971714.8      3941537.67      9970386.68
      3938482.51      9969414.58
#Sta/Elev= 30
     -71   55.48     172   54.96   975.5   53.22  1852.5   54.37  1891.2   40.55
    1983   25.99  2034.4   36.29  2085.9   28.46  2469.7   13.89  2590.2   21.31
  2653.4    2.65  2962.8    2.89  3014.2   23.57  3118.7   12.31  3581.2   15.92
  4622.4   15.82  4721.1    4.13  4997.4      .7    5175    4.25  5216.8   16.55
 7707.6321.09797  8342.2   29.19  8637.1   24.71  8866.7   22.06  9235.2   34.04
  9438.1   41.01 10199.6   48.09 11161.7   51.18 11382.1   51.85 11548.3   51.99
#Mann= 15 ,-1 , 0
     -71     .17       0     172     .15       0   975.5     .15       0
  1852.5     .11       0  3581.2     .11       0  4622.4     .03       0
  5216.8     .11       0 7707.63     .15       0  8342.2     .17       0
  8637.1     .15       0  9235.2     .11       0  9438.1     .17       0
 10199.6     .11       0 11161.7     .17       0 11382.1     .11       0
#XS Ineff= 1 ,-1
  8342.2    9195   29.19
Permanent Ineff=
       F
Bank Sta=4622.4,5216.8
XS Rating Curve= 0 ,0
Exp/Cntr=0.3,0.1

Type RM Length L Ch R = 1 ,3444    ,736,736,736
BEGIN DESCRIPTION:
Mapping XS c612900c
END DESCRIPTION:
XS GIS Cut Line= 4
      3948542.84      9974414.44       3944784.2      9973138.41
      3941954.34      9969883.21      3938655.69       9968989.1
#Sta/Elev= 30
   227.4   54.47   379.4   54.08   774.9   53.26  1890.7   54.59  2111.4    51.1
  2150.2   51.99  2344.8   12.89  2471.5    5.82  2503.2   15.82  2788.3   20.71
  2861.7    2.94  3144.2    4.85  3189.6   18.54  3559.2    9.39  3735.5    17.5
  4610.5   19.61  4997.4     .95  5134.6    2.07  5199.2   19.97  5539.1      14
    5763   21.97  6171.4   20.98  6976.3   19.04  7556.5   21.77  9948.7   25.36
 10408.9   51.17 10913.4   51.55 11520.1   52.19 11924.5   49.31 11927.7   49.32
#Mann= 16 ,-1 , 0
   227.4     .17       0   379.4     .15       0   774.9     .15       0
  1890.7     .11       0  2111.4     .15       0  2150.2     .11       0
  4610.5     .03       0  5199.2     .11       0    5763     .15       0
  6171.4     .17       0  6976.3     .15       0  7556.5     .17       0
  9948.7     .17       0 10913.4     .11       0 11520.1     .11       0
 11924.5     .17       0
#XS Ineff= 3 ,-1
  5907.5    6600   24.05  6602.6    8550   25.33  9071.7   10125   29.47
Permanent Ineff=
       F       F       F
Bank Sta=4610.5,5199.2
XS Rating Curve= 0 ,0
Exp/Cntr=0.3,0.1

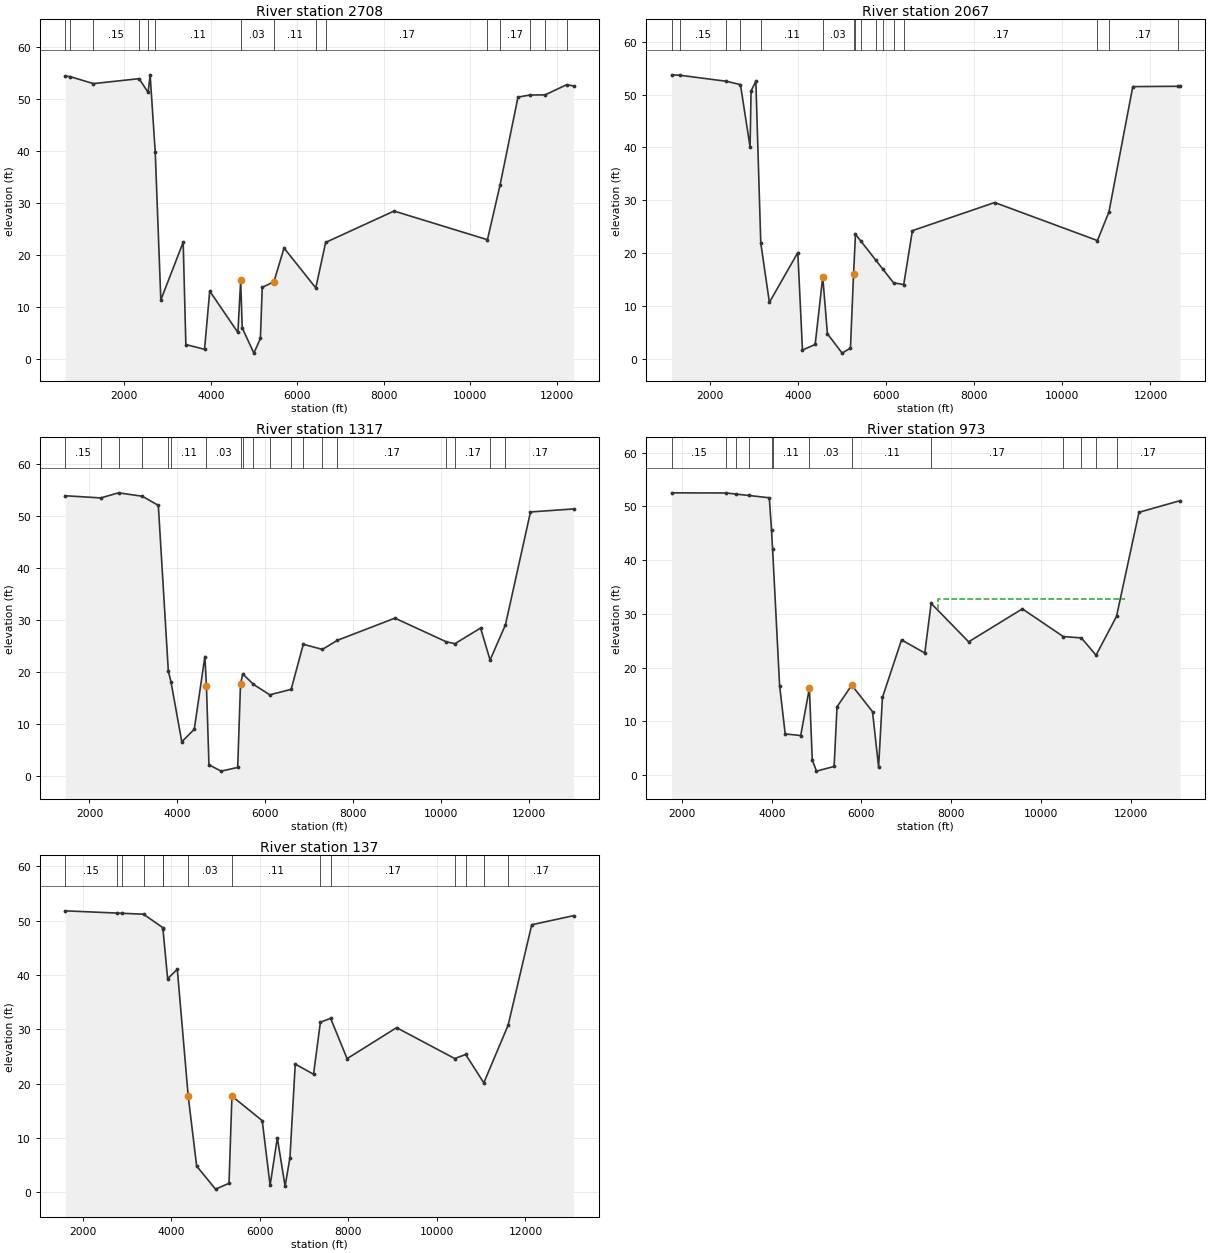
Type RM Length L Ch R = 1 ,2708    ,641,641,641
BEGIN DESCRIPTION:
WFSJ Main 3.0
END DESCRIPTION:
XS GIS Cut Line= 4
      3948751.23        9974128.      3945348.43      9972773.83
       3942865.8      9969718.28      3938803.28      9968876.26
#Sta/Elev= 30
   637.1   54.45   746.8    54.4  1286.8   53.04  2344.4   53.99  2553.5   51.34
  2599.6   54.73    2718   39.84  2847.1   11.38  3363.7    22.5  3425.4    2.79
    3857    1.88  3977.2   13.09  4628.5    5.12  4692.4   15.14  4728.2       6
  4997.4    1.14  5147.9    3.96    5191    13.8  5461.1   14.89  5694.6   21.38
  6428.7    13.7  6656.4   22.46  8236.4    28.5 10395.9   22.98 10689.5   33.61
   11102   50.44 11372.9   50.84 11728.2   50.87 12227.7   52.83 12385.3   52.59
#Mann= 15 ,-1 , 0
   637.1     .17       0   746.8     .15       0  1286.8     .15       0
  2344.4     .11       0  2553.5     .17       0    2718     .11       0
  4692.4     .03       0  5461.1     .11       0  6428.7     .11       0
  6656.4     .17       0 10395.9     .15       0 10689.5     .17       0
 11372.9     .15       0 11728.2     .17       0 12227.7     .11       0
#XS Ineff= 1 ,-1
  8236.4   10620    28.5
Permanent Ineff=
       F
Bank Sta=4692.4,5461.1
XS Rating Curve= 0 ,0
Exp/Cntr=0.3,0.1

Type RM Length L Ch R = 1 ,2067    ,750,750,750
BEGIN DESCRIPTION:
WFSJ Main 2.0
END DESCRIPTION:
XS GIS Cut Line= 4
      3948953.06      9973741.72      3945828.04      9972341.97
      3943115.36      9969618.45      3938961.22      9968588.05
#Sta/Elev= 30
  1124.2   53.75  1314.7   53.67  2366.6   52.53  2686.7    51.9    2905   40.11
  2928.1   50.71  3036.5   52.52  3148.5    21.9  3344.2   10.68  3989.8    20.1
  4095.9    1.66  4384.2    2.71  4556.2   15.49  4662.3    4.74  4997.4    1.07
  5185.5    2.03 5256.44   16.06  5299.9   23.58  5427.8   22.22  5759.8   18.69
  5925.5   16.93  6163.7   14.39  6395.8   14.04  6592.7   24.25  8461.9   29.58
 10796.7   22.38 11057.9    27.8 11599.9   51.52   12616   51.58 12672.4   51.58
#Mann= 16 ,-1 , 0
  1124.2     .17       0  1314.7     .15       0  2366.6     .11       0
  2686.7     .17       0  3148.5     .11       0  4556.2     .03       0
 5256.44     .11       0  5299.9     .11       0  5427.8     .15       0
  5759.8     .15       0  5925.5     .11       0  6163.7     .11       0
  6395.8     .17       0 10796.7     .15       0 11057.9     .17       0
   12616     .15       0
#XS Ineff= 1 ,-1
  8461.9   11210   29.58
Permanent Ineff=
       F
Bank Sta=4556.2,5256.44
XS Rating Curve= 0 ,0
Exp/Cntr=0.3,0.1

Type RM Length L Ch R = 1 ,1317    ,344,344,344
BEGIN DESCRIPTION:
Mapping XS 278d6e0c
END DESCRIPTION:
XS GIS Cut Line= 4
      3949397.94      9973079.83      3946413.97      9971907.95
       3943636.2      9969661.85      3939003.65      9968435.91
#Sta/Elev= 30
    1448   53.87  2258.2   53.45  2661.9   54.43  3204.1   53.77  3567.3   52.02
  3795.5   20.09  3854.6    18.1  4101.7    6.51  4385.9    8.92  4627.2   22.92
  4662.5   17.31    4720    2.07  4997.4     .86    5374    1.57  5437.9   17.59
  5487.7   19.57  5733.7   17.56  6102.9   15.55  6590.7    16.6  6867.4   25.28
  7301.5   24.29  7639.8   26.03    8953   30.31 10114.4   25.78 10317.8   25.39
 10902.5    28.4 11118.7   22.25 11468.8   29.04 12038.2   50.75 13018.1   51.33
#Mann= 19 ,-1 , 0
    1448     .15       0  2258.2     .11       0  2661.9     .15       0
  3204.1     .17       0  3795.5     .15       0  3854.6     .11       0
  4662.5     .03       0  5437.9     .11       0  5487.7     .11       0
  5733.7     .11       0  6102.9     .11       0  6590.7     .15       0
  6867.4     .17       0  7301.5     .15       0  7639.8     .17       0
 10114.4     .15       0 10317.8     .17       0 11118.7     .15       0
 11468.8     .17       0
#XS Ineff= 1 ,-1
    8953   11720   30.31
Permanent Ineff=
       F
Bank Sta=4662.5,5437.9
XS Rating Curve= 0 ,0
Exp/Cntr=0.3,0.1

Type RM Length L Ch R = 1 ,973     ,836,836,836
BEGIN DESCRIPTION:
Mapping XS 129b9c40
END DESCRIPTION:
XS GIS Cut Line= 5
      3949450.02      9972437.47      3946542.01      9971560.72
      3945613.19      9970874.96      3944241.66      9969720.45
      3939085.46      9968331.57
#Sta/Elev= 30
  1771.3   52.51  2989.6   52.48  3209.9   52.27  3485.5   52.02    3946   51.59
    3996   45.61  4019.2   42.14  4175.8   16.66  4300.5    7.67  4645.8    7.37
  4839.1   16.17  4903.8    2.83  4997.4     .75  5390.3    1.62  5455.1   12.72
  5783.3   16.74    6246   11.81  6381.3    1.53  6466.8   14.45  6892.4   25.16
    7410   22.72  7551.8   31.95  8387.2    24.8  9583.8   30.93 10495.1   25.78
 10897.6   25.53   11226   22.31 11681.3   29.53 12182.1   48.89 13095.9   51.05
#Mann= 13 ,-1 , 0
  1771.3     .15       0  2989.6     .11       0  3209.9     .15       0
  3485.5     .17       0    3996     .15       0  4019.2     .11       0
  4839.1     .03       0  5783.3     .11       0  7551.8     .17       0
 10495.1     .15       0 10897.6     .17       0   11226     .15       0
 11681.3     .17       0
#XS Ineff= 1 ,-1
  7701.3   11880    32.8
Permanent Ineff=
       F
Bank Sta=4839.1,5783.3
XS Rating Curve= 0 ,0
Exp/Cntr=0.3,0.1

Type RM Length L Ch R = 1 ,137     ,0,0,0
BEGIN DESCRIPTION:
WFSJ Main 1.0
END DESCRIPTION:
XS GIS Cut Line= 4
      3949766.85       9971962.2      3947629.25      9971397.96
      3944298.09      9969596.75      3938982.09      9968229.78
#Sta/Elev= 30
  1600.5   51.79  2761.7   51.38  2879.2   51.34  3369.8   51.17  3802.1   48.72
  3809.4   48.44    3915    39.3  4133.8   41.03  4379.3   17.75  4570.5    4.84
  4997.4      .6  5302.1    1.67  5367.9   17.71  6052.4    13.2  6230.9    1.28
  6393.5   10.05  6569.6    1.13    6679    6.41  6798.9    23.6    7212   21.73
  7366.9    31.3  7598.3   32.02  7970.2    24.6  9088.6    30.3 10402.4   24.62
 10650.4   25.37 11059.8   20.15 11609.8   30.77 12142.6   49.23 13087.2    50.9
#Mann= 14 ,-1 , 0
  1600.5     .15       0  2761.7     .11       0  2879.2     .15       0
  3369.8     .17       0  3802.1     .15       0  3809.4     .11       0
  4379.3     .03       0  5367.9     .11       0  7366.9     .15       0
  7598.3     .17       0 10402.4     .15       0 10650.4     .17       0
 11059.8     .15       0 11609.8     .17       0
#XS Ineff= 1 ,-1
  7598.3   11800   32.02
Permanent Ineff=
       F
Bank Sta=4379.3,5367.9
XS Rating Curve= 0 ,0
Exp/Cntr=0.3,0.1

Chan Stop Cuts=-1
Use User Specified Reach Order=0
Composite Channel Slope=5

--- WFSJ Main.g02 (geometry) ---

Geom Title=Orig_BLE_Geom_BACKUP
Program Version=4.10

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
River Reach=WFSJ Main       ,Reach-1

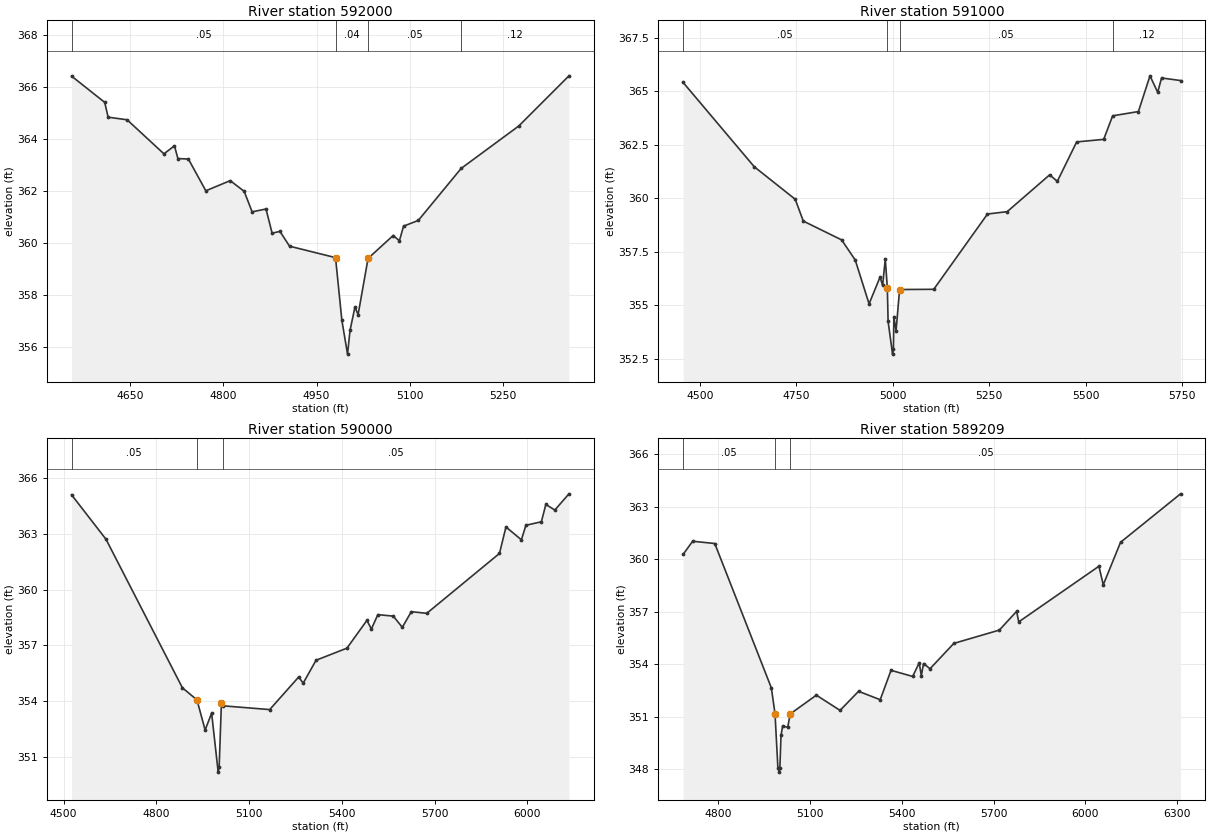
Type RM Length L Ch R = 1 ,592000  ,1000,1000,1000
BEGIN DESCRIPTION:
WFSJ Main 581.0
END DESCRIPTION:
XS GIS Cut Line= 3
      3707117.85     10233111.08      3707314.96     10232713.57
      3707267.86      10232361.1
#Sta/Elev= 30
  4556.3  366.43  4609.6  365.42  4615.1  364.85  4645.6  364.75  4704.8  363.44
  4721.7  363.75  4727.2  363.26  4744.1  363.24  4772.1  362.02  4811.3  362.41
  4833.7     362  4846.5  361.21  4868.8  361.32  4878.6  360.39  4891.2  360.46
  4906.6  359.89  4980.5  359.45  4990.7  357.04  4999.8  355.74  5003.8  356.65
  5011.7  357.55  5016.8  357.26  5032.8  359.42  5073.1   360.3  5083.2   360.1
  5089.8  360.66  5113.5  360.88  5182.4  362.88  5274.9  364.51  5355.6  366.44
#Mann= 4 ,-1 , 0
  4556.3     .05       0  4980.5     .04       0  5032.8     .05       0
  5182.4     .12       0
Bank Sta=4980.5,5032.8
XS Rating Curve= 0 ,0
Exp/Cntr=0.3,0.1

Type RM Length L Ch R = 1 ,591000  ,1000,1000,1000
BEGIN DESCRIPTION:
WFSJ Main 580.0
END DESCRIPTION:
XS GIS Cut Line= 4
      3707517.82     10233411.11      3707880.34     10233006.84
      3708001.94     10232784.03      3707990.63      10232291.9
#Sta/Elev= 30
    4457  365.42  4641.3  361.48  4747.5  359.96  4768.4  358.94  4867.8  358.06
    4903  357.12  4938.9  355.07  4967.3  356.32    4974  355.94  4980.9  357.17
 4986.25  355.81  4988.2  354.25  4999.8  352.72    5002  352.97  5003.1  354.47
  5008.8  353.81    5018  355.74  5106.5  355.75  5245.8  359.27  5296.8  359.38
  5406.8   361.1  5426.8   360.8  5476.9  362.64  5546.9  362.76  5570.1  363.86
  5636.9  364.06  5666.9  365.73  5686.9  364.96  5696.9  365.63  5746.1  365.51
#Mann= 4 ,-1 , 0
    4457     .05       0 4986.25     .03       0    5018     .05       0
  5570.1     .12       0
Bank Sta=4986.25,5018
XS Rating Curve= 0 ,0
Exp/Cntr=0.3,0.1

Type RM Length L Ch R = 1 ,590000  ,791,791,791
BEGIN DESCRIPTION:
WFSJ Main 579.0
END DESCRIPTION:
XS GIS Cut Line= 3
      3707826.56     10233740.08      3708278.23     10233594.99
      3709183.52     10232911.88
#Sta/Elev= 30
  4525.6  365.09    4637   362.7  4884.1  354.72  4931.2  354.07  4957.6  352.45
  4978.6  353.36  4999.8  350.19  5002.9  350.44  5010.3  353.92  5016.6  353.75
  5166.4  353.55  5260.1   355.3  5274.7  354.97  5316.3   356.2  5416.2  356.85
  5480.7  358.34  5495.3  357.88  5516.1  358.65  5566.1  358.57  5595.2  357.97
  5624.4  358.81  5674.3  358.72  5909.5  361.94  5930.4  363.36  5980.3  362.67
  5994.9  363.45  6044.9  363.64  6059.4  364.57  6088.5  364.27  6134.1  365.14
#Mann= 3 ,-1 , 0
  4525.6     .05       0  4931.2     .04       0  5016.6     .05       0
Bank Sta=4931.2,5010.3
XS Rating Curve= 0 ,0
Exp/Cntr=0.3,0.1

Type RM Length L Ch R = 1 ,589209  ,618,618,618
BEGIN DESCRIPTION:
WFSJ Main 578.0
END DESCRIPTION:
XS GIS Cut Line= 4
       3708202.8      10234260.5      3708420.56     10234116.27
      3708528.05     10233830.59      3709266.33     10233072.51
#Sta/Elev= 30
    4686  360.27  4717.1  361.02  4789.3  360.89  4974.1  352.64  4986.1  351.17
  4995.5  348.07  4999.8  347.82    5002  348.07  5005.7  349.92    5011  350.46
  5027.5  350.38  5035.9  351.15  5121.2  352.22  5198.5  351.35    5259  352.44
  5329.7  351.96    5365  353.64  5435.7  353.29  5457.1  354.07    5464  353.33
  5471.2  354.03  5492.3  353.73  5570.2  355.18  5718.7  355.94  5775.2  357.01
  5782.2  356.41    6044  359.59  6058.2  358.53  6114.7  360.96  6310.6  363.73
#Mann= 3 , 0 , 0
    4686     .05       0  4986.1     .04       0  5035.9     .05       0
Bank Sta=4986.1,5035.9
XS Rating Curve= 0 ,0
Exp/Cntr=0.3,0.1