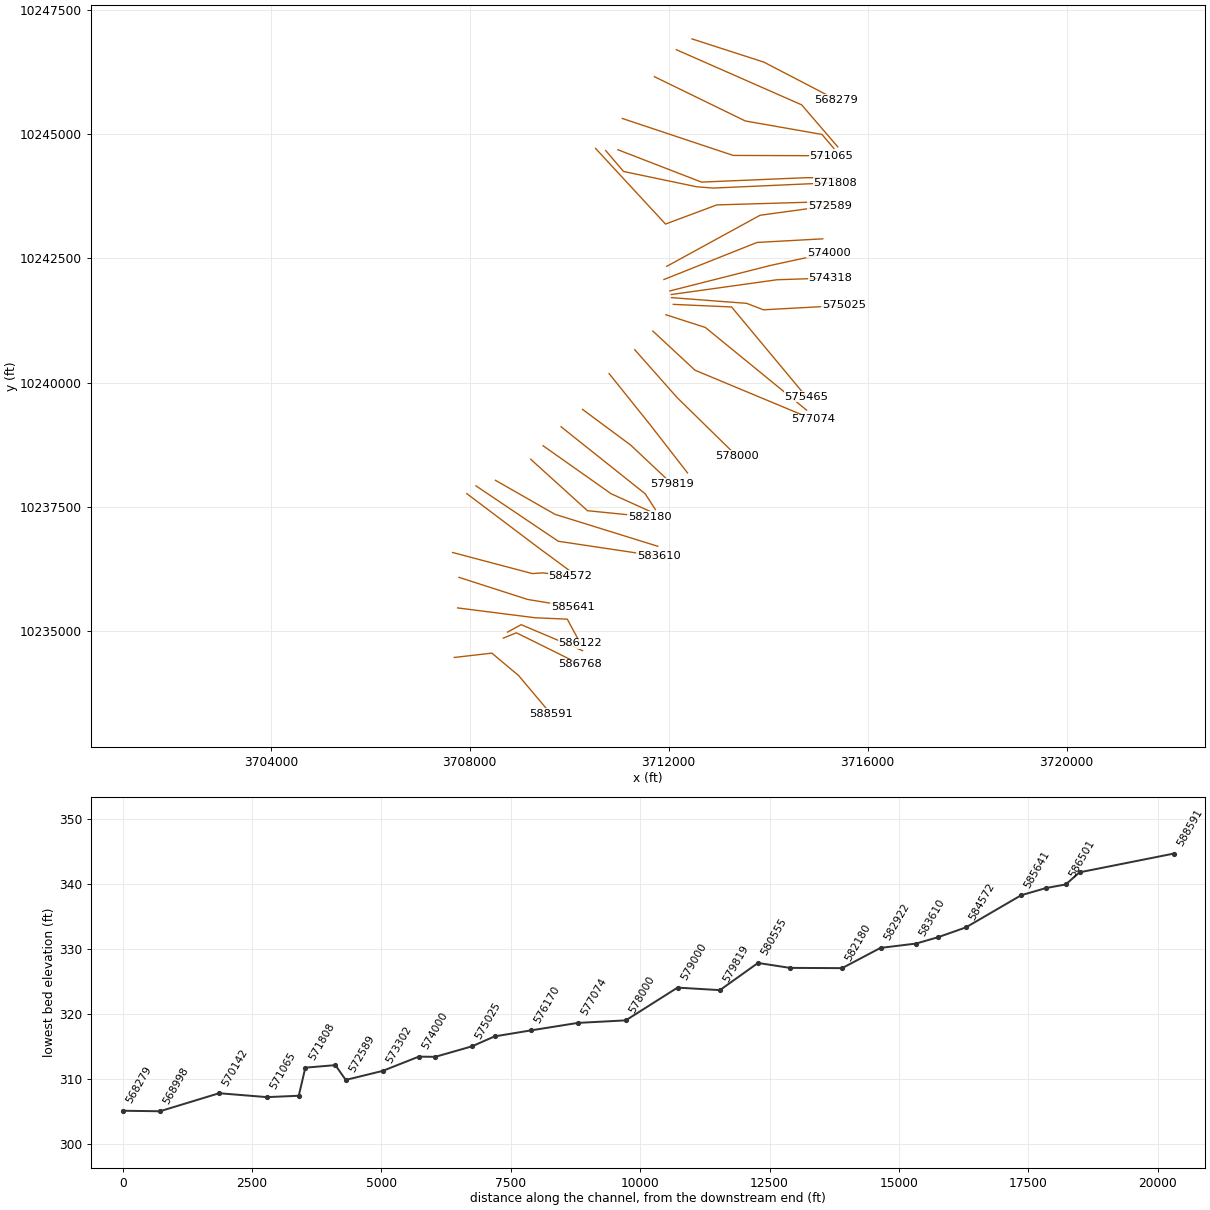
HEC-RAS study WFSJ Main.prj: WFSJ Main Base Level Engineering

--- WFSJ Main.g02 (geometry) --- (continued)

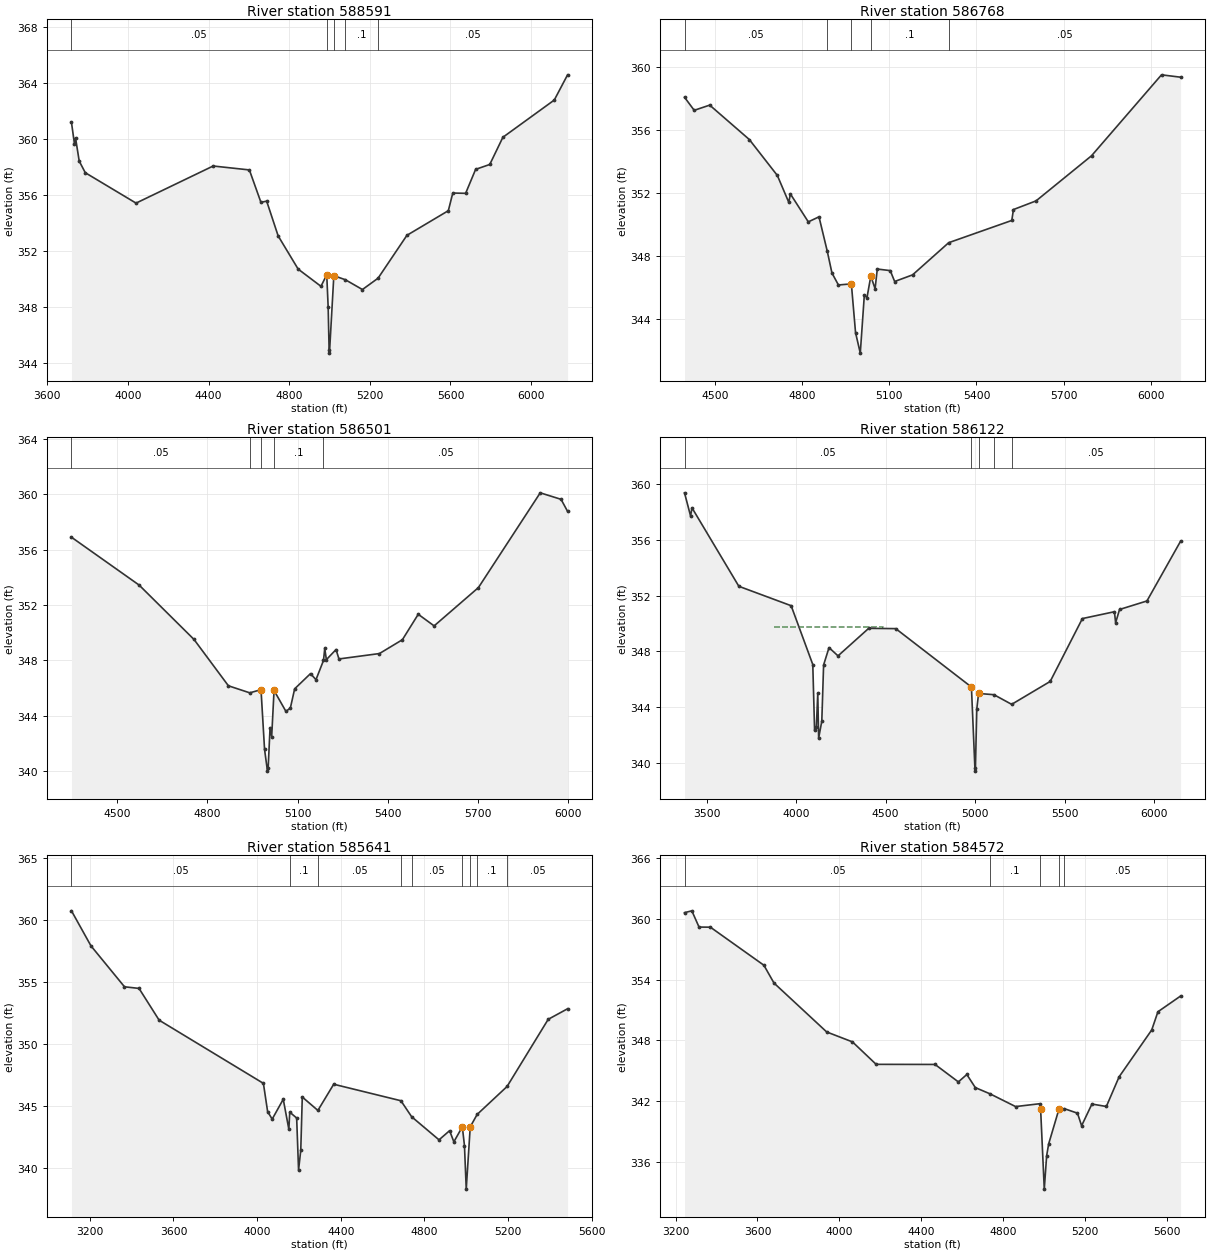
Type RM Length L Ch R = 1 ,588591  ,1823,1823,1823
BEGIN DESCRIPTION:
Mapping XS e04d3abc
END DESCRIPTION:
XS GIS Cut Line= 4
      3707689.68     10234474.16      3708444.84     10234560.96
      3708983.03     10234109.57      3709625.37      10233345.7
#Sta/Elev= 30
  3720.2  361.21  3735.2  359.67  3740.3  360.11  3758.6  358.45  3788.8  357.62
  4040.5  355.45    4423   358.1  4602.6  357.82  4659.8  355.51  4688.4  355.59
  4745.3  353.11  4844.5  350.74  4957.7  349.51  4986.3  350.34  4993.3  348.05
    4998  344.99  4999.8  344.74  5021.5  350.27  5078.7  349.98  5163.3  349.28
  5240.9  350.09  5383.9  353.15  5589.4  354.91  5611.5  356.17  5675.2  356.15
  5724.7  357.86  5794.9  358.21  5859.9  360.15  6114.9  362.81  6180.8  364.61
#Mann= 5 ,-1 , 0
  3720.2     .05       0  4986.3     .04       0  5021.5     .05       0
  5078.7      .1       0  5240.9     .05       0
Bank Sta=4986.3,5021.5
XS Rating Curve= 0 ,0
Exp/Cntr=0.3,0.1

Type RM Length L Ch R = 1 ,586768  ,267,267,267
BEGIN DESCRIPTION:
WFSJ Main 577.0
END DESCRIPTION:
XS GIS Cut Line= 4
      3708674.24     10234862.53      3708937.43       10234970.
      3709361.91     10234760.37      3710213.92     10234337.93
#Sta/Elev= 30
  4394.4  358.07  4427.8  357.24  4481.2  357.57  4617.6  355.39  4714.2  353.11
  4753.5  351.41  4759.1  351.94  4820.8  350.17  4857.6  350.49  4886.2   348.3
  4902.2  346.93  4924.5  346.17  4969.1  346.24  4983.5  343.15  4999.8  341.85
  5013.8  345.54  5022.8  345.36  5036.1  346.73  5050.8  345.93  5058.4  347.18
    5103  347.08  5118.2  346.39  5179.9  346.81  5304.3  348.85  5521.7  350.26
  5527.3  350.95  5605.2   351.5  5796.3  354.36  6037.3  359.49  6103.1  359.34
#Mann= 5 ,-1 , 0
  4394.4     .05       0  4886.2      .1       0  4969.1     .07       0
  5036.1      .1       0  5304.3     .05       0
Bank Sta=4969.1,5036.1
XS Rating Curve= 0 ,0
Exp/Cntr=0.3,0.1

Type RM Length L Ch R = 1 ,586501  ,379,379,379
BEGIN DESCRIPTION:
WFSJ Main 576.0
END DESCRIPTION:
XS GIS Cut Line= 3
      3708759.96     10234983.91      3709034.22      10235133.2
      3710267.82     10234611.08
#Sta/Elev= 30
  4347.2  356.89  4572.5  353.43  4755.2   349.5  4869.7  346.15  4940.9  345.64
  4978.3  345.87  4990.1  341.55  4999.8  339.98    5002  340.18  5008.4  343.12
  5013.8  342.48  5021.7  345.81  5061.2   344.3    5076  344.54  5090.3  345.93
  5143.1  347.03  5161.3  346.59  5186.3  347.98  5190.5  348.85  5195.9  348.04
  5228.1  348.77  5237.8  348.09  5372.6  348.48    5449  349.48  5501.8  351.32
  5554.7  350.48  5702.2  353.25    5908   360.1  5977.3  359.63    5999  358.76
#Mann= 5 ,-1 , 0
  4347.2     .05       0  4940.9      .1       0  4978.3     .07       0
  5021.7      .1       0  5186.3     .05       0
Bank Sta=4978.3,5021.7
XS Rating Curve= 0 ,0
Exp/Cntr=0.3,0.1

Type RM Length L Ch R = 1 ,586122  ,481,481,481
BEGIN DESCRIPTION:
Mapping XS b6025ac1
END DESCRIPTION:
XS GIS Cut Line= 4
      3707756.46       10235470.      3709318.94     10235272.08
       3709961.3     10235244.31      3710224.81     10234755.43
#Sta/Elev= 30
  3375.7  359.35  3409.7  357.69  3417.4  358.28  3679.5  352.66  3971.8  351.27
  4092.8  347.06  4102.9  342.35  4112.9   342.6  4120.6  345.01  4125.6  341.79
  4143.2  343.01  4153.3  347.03  4183.5  348.27  4233.9  347.68  4405.3  349.65
  4556.5  349.63  4979.6  345.45  4999.8  339.43    5002  339.63  5009.6  343.88
  5019.6  344.99  5105.6   344.9  5204.6  344.21    5420  345.85  5599.9  350.35
  5779.1  350.84  5785.7  350.05  5807.6     351  5960.8  351.61    6149  355.89
#Mann= 5 ,-1 , 0
  3375.7     .05       0  4979.6     .04       0  5019.6     .05       0
  5105.6      .1       0  5204.6     .05       0
#XS Ineff= 1 ,-1
    3875  4485.9  349.78
Permanent Ineff=
       F
Bank Sta=4979.6,5019.6
XS Rating Curve= 0 ,0
Exp/Cntr=0.3,0.1

Type RM Length L Ch R = 1 ,585641  ,1069,1069,1069
BEGIN DESCRIPTION:
Mapping XS a9c090c9
END DESCRIPTION:
XS GIS Cut Line= 3
      3707784.23     10236084.58      3709166.16     10235640.14
      3710074.37     10235491.08
#Sta/Elev= 30
  3112.3  360.74  3205.4  357.92  3365.8  354.62  3435.3  354.49  3531.5  351.93
    4030  346.84  4050.2  344.56    4072  343.96  4124.9  345.56  4151.7  343.14
  4155.9  344.52    4189  344.05  4198.1  339.86  4208.6  341.45  4215.9  345.74
  4290.5  344.66  4366.1  346.77  4687.5  345.44  4738.8  344.15  4869.7  342.29
  4920.3  343.03  4940.6  342.13  4981.1  343.34  4991.3  341.83  4999.8  338.32
  5018.9  343.34  5052.1  344.34  5195.1  346.59  5391.7     352  5484.3  352.85
#Mann= 9 ,-1 , 0
  3112.3     .05       0  4155.9      .1       0  4290.5     .05       0
  4687.5      .1       0  4738.8     .05       0  4981.1     .04       0
  5018.9     .05       0  5052.1      .1       0  5195.1     .05       0
#XS Ineff= 1 ,-1
    3920  4366.1  346.77
Permanent Ineff=
       F
Bank Sta=4981.1,5018.9
XS Rating Curve= 0 ,0
Exp/Cntr=0.3,0.1

Type RM Length L Ch R = 1 ,584572  ,537,537,537
BEGIN DESCRIPTION:
WFSJ Main 575.0
END DESCRIPTION:
XS GIS Cut Line= 4
      3707655.77     10236584.58      3709256.44     10236160.97
      3709468.25     10236174.86      3710017.82     10236111.07
#Sta/Elev= 30
  3243.9  360.59  3279.7  360.77  3314.8  359.17  3370.2  359.16  3631.4  355.41
  3680.5  353.66  3937.8  348.84  4063.7  347.86  4179.2  345.65  4466.7  345.64
  4580.5  343.92  4621.8  344.65  4663.2  343.36  4735.6  342.74  4859.8  341.49
  4976.9  341.77  4981.9  341.26  4999.8  333.36  5011.3  336.64  5021.3  337.82
  5071.5  341.24  5098.3  341.28  5161.9  340.84    5182   339.6  5232.3  341.74
  5302.8   341.5    5365  344.42  5524.3  349.04  5554.5  350.83  5665.2  352.38
#Mann= 5 ,-1 , 0
  3243.9     .05       0  4735.6      .1       0  4976.9     .07       0
  5071.5      .1       0  5098.3     .05       0
Bank Sta=4981.9,5071.5
XS Rating Curve= 0 ,0
Exp/Cntr=0.3,0.1

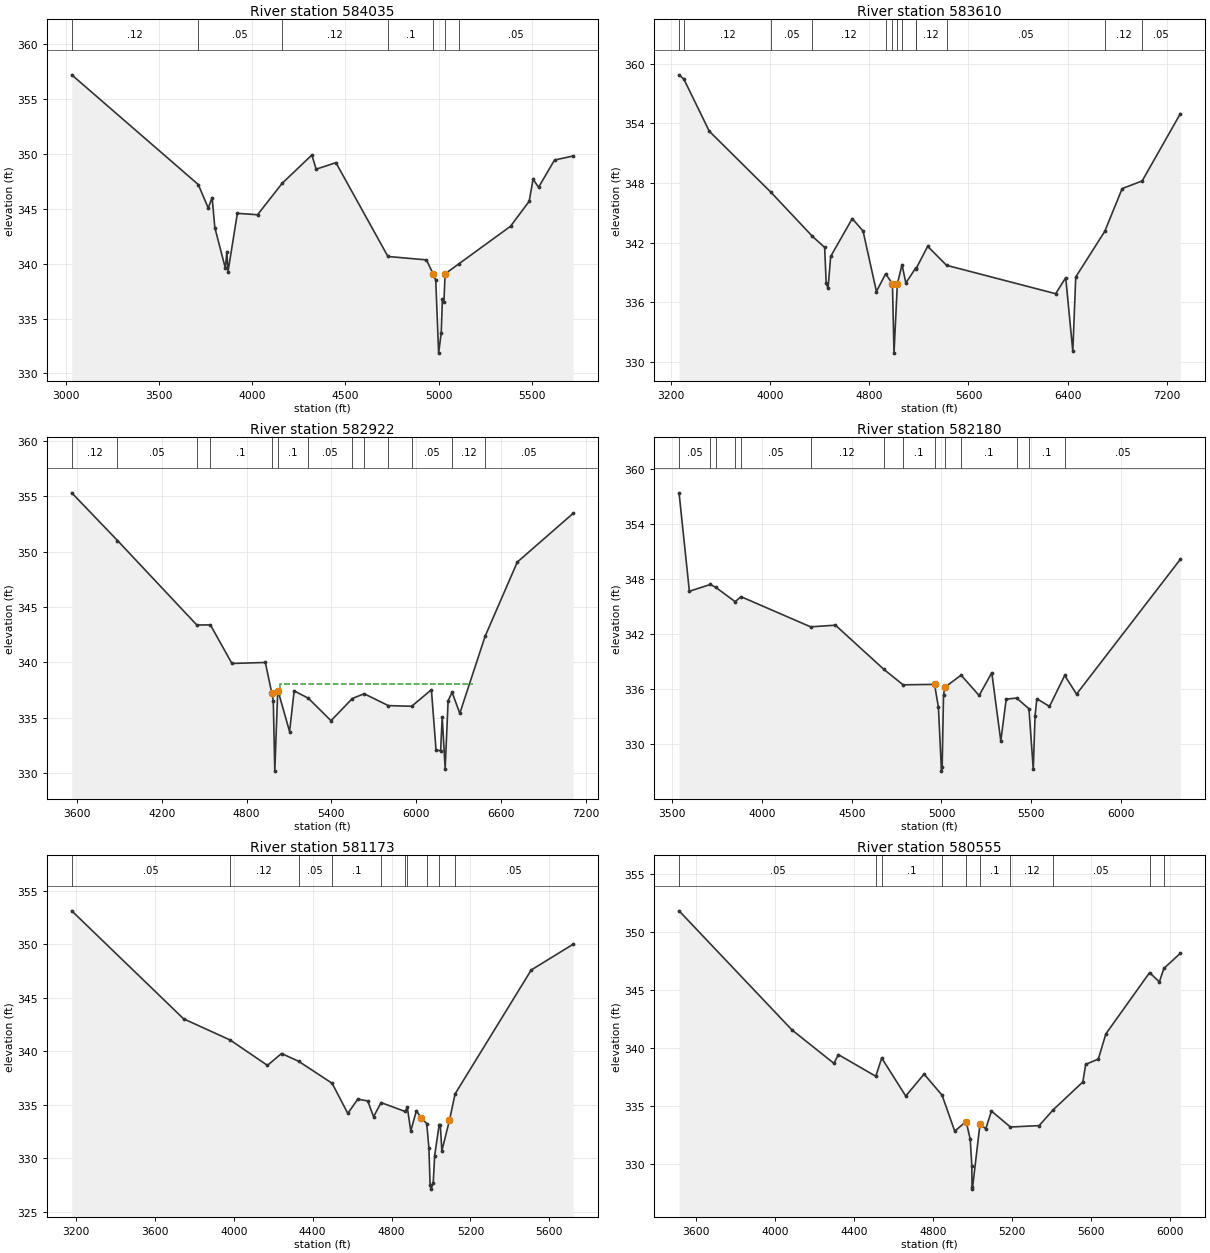
Type RM Length L Ch R = 1 ,584035  ,425,425,425
BEGIN DESCRIPTION:
WFSJ Main 574.0
END DESCRIPTION:
XS GIS Cut Line= 3
      3707940.44     10237768.64      3709357.14     10236699.17
      3710092.17     10236156.67
#Sta/Elev= 30
    3032  357.19  3710.8   347.2  3764.1  345.06    3785  346.01  3799.5  343.28
  3855.8  339.59  3864.1   341.1  3870.3  339.27  3920.3  344.58  4028.5  344.45
    4161  347.32  4319.9  349.89  4342.8   348.6    4449  349.19  4727.9  340.65
  4934.3  340.34  4969.8  339.08  4984.4  338.48  4999.8  331.85  5013.7  333.68
  5019.9  336.75  5028.3  336.55  5034.5  339.07  5109.9     340  5385.3   343.4
  5485.6  345.68  5506.4  347.69  5535.7  346.95  5621.3  349.43  5720.6   349.8
#Mann= 7 ,-1 , 0
    3032     .12       0  3710.8     .05       0    4161     .12       0
  4727.9      .1       0  4969.8     .07       0  5034.5      .1       0
  5109.9     .05       0
#XS Ineff= 1 ,-1
    3300  4319.9  349.89
Permanent Ineff=
       F
Bank Sta=4969.8,5034.5
XS Rating Curve= 0 ,0
Exp/Cntr=0.3,0.1

Type RM Length L Ch R = 1 ,583610  ,688,688,688
BEGIN DESCRIPTION:
Mapping XS 853c9f54
END DESCRIPTION:
XS GIS Cut Line= 3
      3708124.52     10237924.85      3709780.75     10236810.28
      3711801.56      10236508.2
#Sta/Elev= 30
  3267.6  358.88  3306.4  358.45  3511.4   353.2  4008.8  347.05  4341.1  342.64
  4440.8  341.51  4453.2  337.91  4468.2  337.38  4489.2   340.6  4663.1  344.41
  4750.1  343.17  4858.1  337.07  4932.2  338.86  4987.1  337.85  4999.8  330.87
 5026.61  337.83  5064.4  339.77    5095  337.93  5173.1  339.41  5176.5  339.35
  5271.1  341.62  5422.9  339.71  6302.2  336.85  6383.3  338.46  6440.6  331.07
  6464.2  338.53  6698.2  343.13  6838.3  347.43  6999.4   348.2  7307.2  354.97
#Mann= 13 ,-1 , 0
  3267.6     .05       0  3306.4     .12       0  4008.8     .05       0
  4341.1     .12       0  4932.2      .1       0  4987.1     .07       0
 5026.61      .1       0  5064.4     .12       0  5173.1      .1       0
  5176.5     .12       0  5422.9     .05       0  6698.2     .12       0
  6999.4     .05       0
#XS Ineff= 2 ,-1
    4045  4663.1  344.41  5271.1    6650  341.62
Permanent Ineff=
       F       F
Bank Sta=4987.1,5026.61
XS Rating Curve= 0 ,0
Exp/Cntr=0.3,0.1

Type RM Length L Ch R = 1 ,582922  ,742,742,742
BEGIN DESCRIPTION:
WFSJ Main 573.0
END DESCRIPTION:
XS GIS Cut Line= 3
      3708516.88     10238035.96      3709714.77     10237351.95
      3711780.78     10236709.57
#Sta/Elev= 30
  3564.6   355.3  3887.9     351  4448.8  343.38  4544.5  343.39  4696.9  339.91
    4933     340  4978.7  337.23  4989.1  336.55  4999.8   330.2  5020.6  337.46
  5021.5   337.5  5104.3  333.77  5136.6  337.44  5236.3  336.78    5397  334.75
  5547.9  336.75  5631.3  337.18  5802.2  336.11  5967.3  336.05  6106.7  337.54
  6139.3  332.13  6171.8  332.02    6183   335.1  6203.9  330.43  6224.9  336.56
  6253.2  337.31  6307.2  335.41  6486.6  342.37  6713.5  349.05  7107.6  353.44
#Mann= 13 ,-1 , 0
  3564.6     .12       0  3887.9     .05       0  4448.8     .12       0
  4544.5      .1       0  4978.7     .07       0  5021.5      .1       0
  5236.3     .05       0  5547.9     .12       0  5631.3     .05       0
  5802.2     .12       0  5967.3     .05       0  6253.2     .12       0
  6486.6     .05       0
#XS Ineff= 1 ,-1
  5033.7    6400   338.1
Permanent Ineff=
       T
Bank Sta=4978.7,5020.6
XS Rating Curve= 0 ,0
Exp/Cntr=0.3,0.1

Type RM Length L Ch R = 1 ,582180  ,1007,1007,1007
BEGIN DESCRIPTION:
WFSJ Main 572.0
END DESCRIPTION:
XS GIS Cut Line= 3
      3709225.22     10238459.56      3710367.55     10237424.86
      3711613.43     10237299.93
#Sta/Elev= 30
  3537.6  357.36  3595.1  346.65  3712.2  347.39  3742.4  347.07  3850.2  345.52
  3882.8  346.06  4270.7  342.78  4409.1  342.96  4678.5  338.16  4786.1  336.47
  4961.3  336.52  4982.9  334.02  4999.8  327.08  5003.8  327.58  5011.3  335.33
    5018   336.2  5109.3  337.52  5209.8  335.31  5280.2  337.79  5330.4  330.36
  5360.6  334.91  5418.3  335.03  5487.3  333.87  5511.3  327.28  5521.4  333.11
  5531.4  334.96  5601.8  334.12  5686.5  337.49  5752.5  335.46    6331  350.13
#Mann= 14 ,-1 , 0
  3537.6     .05       0  3712.2     .12       0  3742.4     .05       0
  3850.2     .12       0  3882.8     .05       0  4270.7     .12       0
  4678.5     .12       0  4786.1      .1       0  4961.3     .07       0
    5018      .1       0  5109.3      .1       0  5418.3     .12       0
  5487.3      .1       0  5686.5     .05       0
#XS Ineff= 2 ,-1
  5109.3  5280.1  337.52  5280.2    5850  337.79
Permanent Ineff=
       F       T
Bank Sta=4961.3,5018
XS Rating Curve= 0 ,0
Exp/Cntr=0.3,0.1

Type RM Length L Ch R = 1 ,581173  ,618,618,618
BEGIN DESCRIPTION:
WFSJ Main 571.0
END DESCRIPTION:
XS GIS Cut Line= 3
      3709475.17     10238730.43      3710843.25     10237765.14
      3711633.87     10237407.97
#Sta/Elev= 30
  3178.2  353.14  3745.7  343.04  3981.7  341.06  4170.6  338.69    4242   339.8
  4328.1  339.08  4498.3  337.02  4578.1   334.2  4628.6  335.53  4679.1  335.37
  4708.7  333.89  4746.7  335.21  4868.9  334.38  4879.8  334.78  4897.4  332.55
    4926  334.46  4949.2  333.79  4978.3  333.25  4989.3  330.98  4995.4  327.54
  4999.8  327.12  5011.2  327.68  5018.5  330.25  5041.6  333.16  5047.1  333.12
  5055.1  330.71  5093.4  333.54    5122  336.02  5508.3  347.61  5720.1  350.01
#Mann= 10 ,-1 , 0
  3178.2     .05       0  3981.7     .12       0  4328.1     .05       0
  4498.3      .1       0  4746.7      .1       0  4868.9     .12       0
  4879.8      .1       0  4978.3     .07       0  5041.6      .1       0
    5122     .05       0
Bank Sta=4949.2,5093.4
XS Rating Curve= 0 ,0
Exp/Cntr=0.3,0.1

Type RM Length L Ch R = 1 ,580555  ,736,736,736
BEGIN DESCRIPTION:
Mapping XS 067ed6a7
END DESCRIPTION:
XS GIS Cut Line= 3
      3709836.31     10239112.35      3711527.27     10237765.14
      3711732.14     10237449.16
#Sta/Elev= 30
  3514.4   351.8  4085.7  341.57  4298.7  338.69  4321.2  339.44  4510.6  337.58
  4540.6  339.15  4662.3  335.88  4755.2  337.77  4846.4  335.95  4910.5  332.86
  4968.2   333.7  4968.8  333.65    4989  332.17    4997  329.87    4998  328.08
  4999.8  327.88  5038.6  333.51  5067.5  333.05  5096.3  334.59  5192.4  333.22
  5338.1  333.34  5407.9  334.68  5559.1  337.09  5573.6   338.6  5637.6  339.06
  5675.7  341.22  5897.2  346.49  5946.7  345.69  5969.7  346.85    6053  348.15
#Mann= 10 ,-1 , 0
  3514.4     .05       0  4510.6     .12       0  4540.6      .1       0
  4846.4      .1       0  4968.2     .07       0  5038.6      .1       0
  5192.4     .12       0  5407.9     .05       0  5897.2     .12       0
  5969.7     .05       0
Bank Sta=4968.8,5038.6
XS Rating Curve= 0 ,0
Exp/Cntr=0.3,0.1

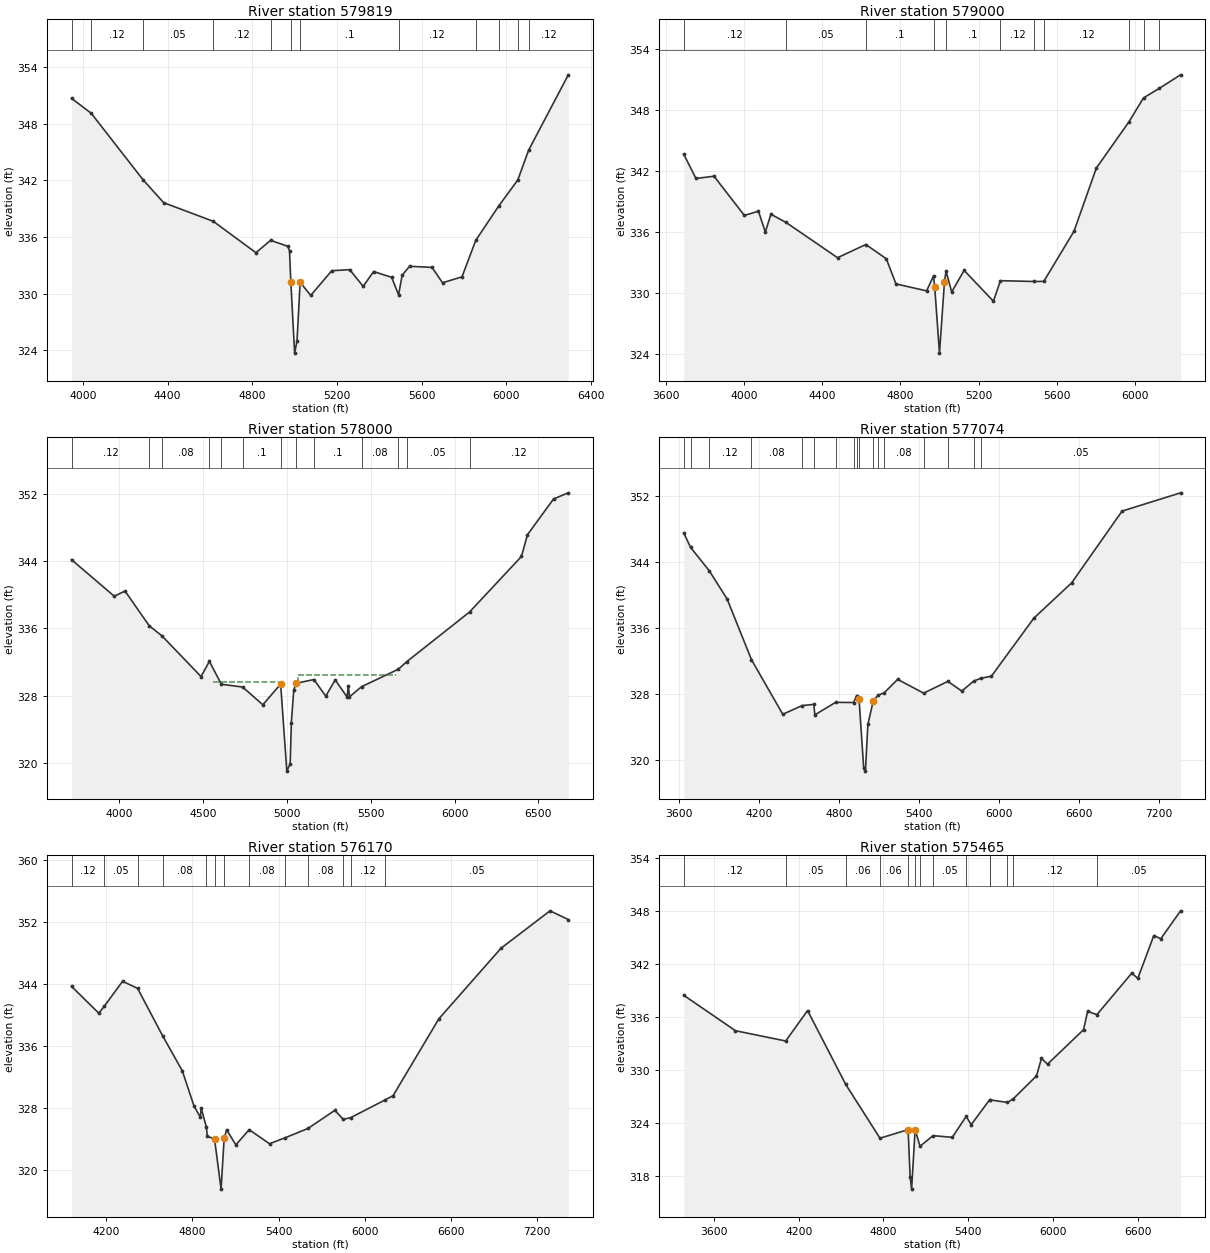
Type RM Length L Ch R = 1 ,579819  ,819,819,819
BEGIN DESCRIPTION:
WFSJ Main 570.0
END DESCRIPTION:
XS GIS Cut Line= 3
      3710267.82      10239461.1      3711235.61     10238744.31
      3712067.87     10237961.05
#Sta/Elev= 30
  3945.6  350.71  4038.5  349.13  4284.4  342.05  4381.2  339.64  4615.2  337.67
  4816.9  334.34  4886.3  335.65  4967.2  335.02  4975.6  334.56  4981.8  331.24
  4999.8  323.69  5011.1  324.99  5025.7   331.2  5075.8  329.81  5175.1  332.43
    5260  332.54  5323.6  330.77  5372.9  332.34  5457.9  331.73    5491  329.87
  5507.7  331.95  5542.8   332.9  5648.8  332.78  5698.6  331.15  5790.5  331.78
  5855.6  335.65  5964.6  339.31  6053.9  342.04  6105.3  345.21  6292.8   353.2
#Mann= 12 ,-1 , 0
  3945.6     .05       0  4038.5     .12       0  4284.4     .05       0
  4615.2     .12       0  4886.3      .1       0  4981.8     .07       0
  5025.7      .1       0    5491     .12       0  5855.6     .05       0
  5964.6     .12       0  6053.9     .05       0  6105.3     .12       0
Bank Sta=4981.8,5025.7
XS Rating Curve= 0 ,0
Exp/Cntr=0.3,0.1

Type RM Length L Ch R = 1 ,579000  ,1000,1000,1000
BEGIN DESCRIPTION:
WFSJ Main 569.0
END DESCRIPTION:
XS GIS Cut Line= 3
       3710801.6     10240181.78      3711620.99     10239160.57
      3712377.67     10238185.67
#Sta/Elev= 30
  3690.7  343.66    3753  341.27  3845.5  341.49    4001  337.63    4073  338.05
  4108.2     336    4137  337.75  4214.4  336.94  4477.9  333.47  4622.7  334.77
  4727.5  333.37  4777.1  330.89    4934  330.21  4969.2  331.67  4975.6  330.54
  4999.8  324.08  5025.2  331.06  5033.3  332.15  5062.3   330.1    5126  332.22
  5275.9  329.19  5311.9  331.21  5485.4  331.13  5533.8  331.14  5688.6  336.08
  5802.7  342.29    5970  346.85  6044.4   349.2  6125.2  350.14  6234.1  351.47
#Mann= 11 ,-1 , 0
  3690.7     .12       0  4214.4     .05       0  4622.7      .1       0
  4969.2     .07       0  5033.3      .1       0  5311.9     .12       0
  5485.4     .05       0  5533.8     .12       0    5970     .05       0
  6044.4     .12       0  6125.2     .05       0
Bank Sta=4975.6,5025.2
XS Rating Curve= 0 ,0
Exp/Cntr=0.3,0.1

Type RM Length L Ch R = 1 ,578000  ,926,926,926
BEGIN DESCRIPTION:
WFSJ Main 568.0
END DESCRIPTION:
XS GIS Cut Line= 3
      3711317.83     10240661.09      3712168.58     10239699.66
      3713367.26     10238525.84
#Sta/Elev= 30
  3716.2  344.17  3970.9  339.83  4035.3  340.44  4179.6  336.31  4254.5  335.13
  4488.7  330.27    4538  332.09  4609.5  329.36  4736.3  329.03  4856.7  326.92
  4962.9  329.38  4999.8  319.03  5019.7  319.91  5026.8  324.81    5041  328.69
    5055  329.47  5161.1  329.92  5231.9  327.95  5288.4  329.88  5359.2  327.83
  5366.2   329.2  5373.3  327.87  5445.2  329.07  5664.8  331.15  5713.2  332.02
    6089  337.95  6398.6  344.56    6434  347.13  6589.6  351.39  6677.7  352.12
#Mann= 13 ,-1 , 0
  3716.2     .12       0  4179.6     .05       0  4254.5     .08       0
    4538     .08       0  4609.5      .1       0  4736.3      .1       0
  4962.9     .07       0    5055      .1       0  5161.1      .1       0
  5445.2     .08       0  5664.8     .12       0  5713.2     .05       0
    6089     .12       0
#XS Ineff= 2 ,-1
  5069.1    5650  330.49    4560  4956.3  329.68
Permanent Ineff=
       T       T
Bank Sta=4962.9,5055
XS Rating Curve= 0 ,0
Exp/Cntr=0.3,0.1

Type RM Length L Ch R = 1 ,577074  ,904,904,904
BEGIN DESCRIPTION:
WFSJ Main 567.0
END DESCRIPTION:
XS GIS Cut Line= 3
      3711682.66      10241035.1      3712529.01     10240249.51
      3714902.99       10239260.
#Sta/Elev= 30
  3637.2  347.56  3688.1  345.81  3827.8  342.98    3962  339.55  4144.8  332.18
  4379.8  325.54  4524.7   326.6    4613  326.74  4620.2  325.47  4776.1  326.99
  4911.5  326.97  4933.9  327.82  4952.3  327.34    4987  318.99  4999.8  318.64
  5018.2  324.31  5058.5  327.16    5094  327.85  5140.8  328.15  5241.5  329.78
  5436.5  328.11  5618.5  329.54  5722.4  328.36  5812.1  329.57  5866.5  329.92
  5944.5  330.16  6264.1  337.23  6546.8   341.5    6925  350.21  7363.9  352.43
#Mann= 17 ,-1 , 0
  3637.2     .12       0  3688.1     .05       0  3827.8     .12       0
  4144.8     .08       0  4524.7     .08       0    4613      .1       0
  4776.1      .1       0  4911.5      .1       0  4933.9     .08       0
  4952.3     .06       0  5058.5     .08       0    5094      .1       0
  5140.8     .08       0  5436.5     .12       0  5618.5     .05       0
  5812.1     .12       0  5866.5     .05       0
#XS Ineff= 2 ,-1
  5241.5    5940  329.78    4280  4933.9  327.82
Permanent Ineff=
       T       T
Bank Sta=4952.3,5058.5
XS Rating Curve= 0 ,0
Exp/Cntr=0.3,0.1

Type RM Length L Ch R = 1 ,576170  ,705,705,705
BEGIN DESCRIPTION:
WFSJ Main 566.0
END DESCRIPTION:
XS GIS Cut Line= 3
      3711943.08     10241364.97      3712737.34     10241108.89
      3714772.91     10239446.59
#Sta/Elev= 30
  3957.3  343.71  4147.7  340.24    4185  341.12  4313.2  344.37  4417.9  343.45
  4593.8  337.27  4729.3   332.8    4812  328.19  4855.1  326.81  4861.5  327.94
  4896.7  325.55  4904.6   324.3  4954.1     324  4999.8  317.49 5021.25  324.09
  5038.8  325.15  5102.7  323.21  5195.4  325.18  5337.5  323.36  5445.8  324.13
    5606  325.34  5792.7  327.68  5851.7  326.51  5904.7  326.75  6140.2     329
  6198.3  329.57  6517.8  339.52  6950.7  348.64  7292.5  353.48  7419.9  352.35
#Mann= 13 ,-1 , 0
  3957.3     .12       0    4185     .05       0  4417.9     .12       0
  4593.8     .08       0  4896.7     .08       0  4954.1     .06       0
 5021.25     .08       0  5195.4     .08       0  5445.8     .08       0
    5606     .08       0  5851.7     .05       0  5904.7     .12       0
  6140.2     .05       0
Bank Sta=4954.1,5021.25
XS Rating Curve= 0 ,0
Exp/Cntr=0.3,0.1

Type RM Length L Ch R = 1 ,575465  ,440,440,440
BEGIN DESCRIPTION:
WFSJ Main 565.0
END DESCRIPTION:
XS GIS Cut Line= 3
      3712092.37      10241573.3      3713264.25     10241521.22
      3714763.54     10239719.99
#Sta/Elev= 30
    3387  338.45  3752.8  334.45  4108.6  333.29  4263.3  336.73  4533.6  328.38
  4775.8  322.31    4975  323.28  4989.3  317.94  4999.8  316.56  5024.5  323.28
  5059.1   321.4  5151.7   322.6  5287.4  322.41  5386.2  324.77  5421.5  323.84
  5551.9  326.65  5556.1  326.64  5678.3  326.35  5717.9  326.74  5883.7  329.35
  5918.8  331.32  5961.8  330.67  6216.9  334.57  6245.6  336.63  6311.5  336.27
    6558  340.95    6601  340.36  6714.2   345.2  6763.7  344.84  6903.6  347.99
#Mann= 14 ,-1 , 0
    3387     .12       0  4108.6     .05       0  4533.6     .06       0
  4775.8     .06       0    4975     .05       0  5024.5     .06       0
  5059.1      .1       0  5151.7     .05       0  5386.2     .12       0
  5551.9     .05       0  5556.1     .12       0  5678.3     .05       0
  5717.9     .12       0  6311.5     .05       0
Bank Sta=4975,5024.5
XS Rating Curve= 0 ,0
Exp/Cntr=0.3,0.1

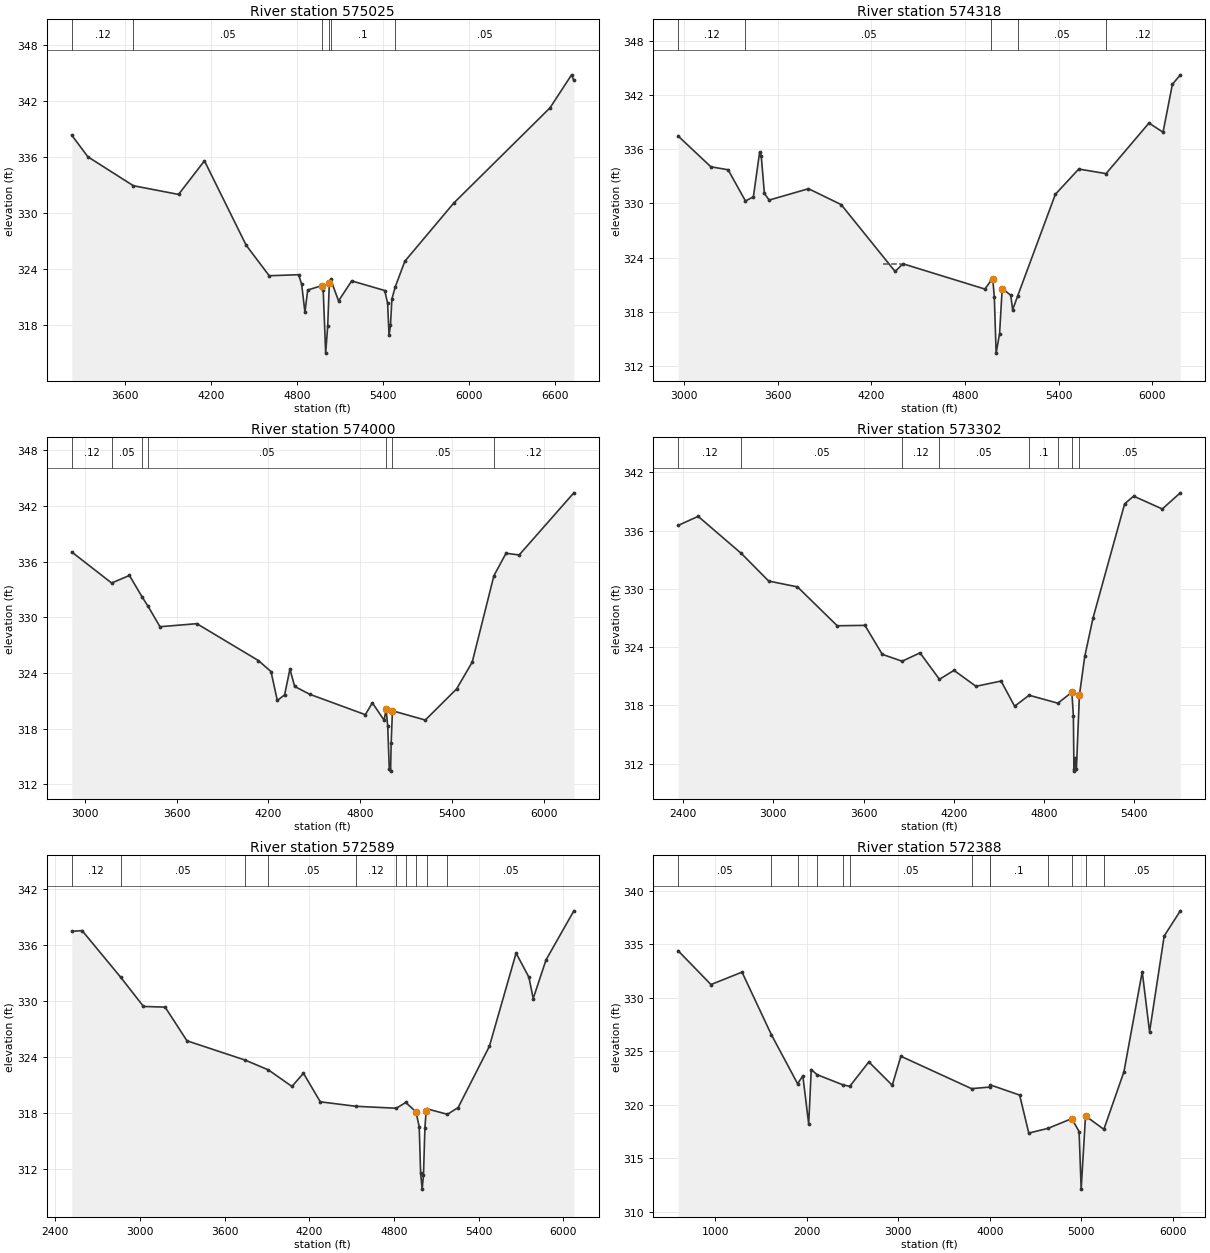
Type RM Length L Ch R = 1 ,575025  ,707,707,707
BEGIN DESCRIPTION:
Mapping XS bc753f61
END DESCRIPTION:
XS GIS Cut Line= 4
      3712055.91     10241708.72      3713566.34     10241594.13
      3713904.88     10241463.92      3715523.77     10241552.42
#Sta/Elev= 30
  3230.5  338.31  3342.8     336  3659.5  332.91  3974.6  331.98  4155.1  335.57
  4445.9  326.55  4606.4  323.29  4811.2   323.4  4832.6  322.38  4855.3  319.37
  4874.6  321.76  4971.9  322.23  4982.6  321.79  4999.8  315.02  5013.9  317.89
  5025.5  322.51  5034.5  322.91  5089.7   320.6  5181.1  322.74  5411.4  321.71
  5431.4  320.37  5441.5  316.93  5451.5  318.01  5461.5  320.82  5485.3  322.13
  5551.6  324.84  5892.1  331.05  6563.1  341.23  6713.4  344.76  6729.3  344.16
#Mann= 6 ,-1 , 0
  3230.5     .12       0  3659.5     .05       0  4971.9     .04       0
  5025.5     .05       0  5034.5      .1       0  5485.3     .05       0
Bank Sta=4971.9,5025.5
XS Rating Curve= 0 ,0
Exp/Cntr=0.3,0.1

Type RM Length L Ch R = 1 ,574318  ,318,318,318
BEGIN DESCRIPTION:
Mapping XS 8fdcb224
END DESCRIPTION:
XS GIS Cut Line= 3
      3712050.68     10241771.21      3714175.71     10242068.09
      3715248.63     10242104.55
#Sta/Elev= 30
  2961.5  337.46  3170.7  334.06  3281.2  333.73  3392.6  330.27  3443.3  330.73
  3483.7  335.72  3493.8  335.26    3514  331.11  3544.3  330.37  3796.7  331.63
  4006.1  329.87    4352  322.46  4402.5  323.31  4927.6  320.51    4968  321.48
  4978.1  321.66  4988.2  319.61  4999.8  313.41  5021.9  315.58  5038.6  320.57
  5093.4  319.83  5105.7  318.21  5137.5  319.73  5379.5  331.01  5529.6  333.81
  5704.4   333.3  5979.8  338.91  6069.9  337.89  6129.9   343.2  6180.7  344.25
#Mann= 5 ,-1 , 0
  2961.5     .12       0  3392.6     .05       0    4968     .04       0
  5137.5     .05       0  5704.4     .12       0
#XS Ineff= 1 ,-1
    4275  4392.4  323.32
Permanent Ineff=
       F
Bank Sta=4978.1,5038.6
XS Rating Curve= 0 ,0
Exp/Cntr=0.3,0.1

Type RM Length L Ch R = 1 ,574000  ,698,698,698
BEGIN DESCRIPTION:
WFSJ Main 564.0
END DESCRIPTION:
XS GIS Cut Line= 3
      3712024.65     10241844.13      3714046.26     10242356.01
      3715217.38     10242609.76
#Sta/Elev= 30
  2914.6  337.04  3175.1   333.7  3291.8  334.51  3376.8  332.14    3413  331.21
  3491.6  328.99  3732.5  329.32  4135.1  325.35  4217.7  324.16  4258.9  321.05
  4306.5  321.65  4341.4  324.42  4372.4  322.56  4470.5  321.72  4834.4  319.52
  4880.5  320.79  4957.4  318.93  4970.7  320.09    4981  318.29  4991.3  313.65
  4999.8  313.44  5003.5  316.47  5011.9  319.94  5226.7  318.94  5431.4  322.29
  5533.7  325.18  5675.6  334.49  5754.8   336.9  5840.7  336.72  6198.3  343.41
#Mann= 7 ,-1 , 0
  2914.6     .12       0  3175.1     .05       0  3376.8     .12       0
    3413     .05       0  4970.7     .04       0  5011.9     .05       0
  5675.6     .12       0
#XS Ineff= 1 ,-1
    4120  4341.4  324.42
Permanent Ineff=
       F
Bank Sta=4970.7,5011.9
XS Rating Curve= 0 ,0
Exp/Cntr=0.3,0.1

Type RM Length L Ch R = 1 ,573302  ,713,713,713
BEGIN DESCRIPTION:
WFSJ Main 563.0
END DESCRIPTION:
XS GIS Cut Line= 3
       3711904.9     10242073.31      3713774.67     10242818.09
      3715097.62     10242891.01
#Sta/Elev= 30
  2367.6  336.53  2499.9  337.46  2787.3  333.64  2968.9   330.8  3160.3   330.2
  3424.6   326.2  3608.7  326.24    3724  323.26  3855.9  322.55  3974.7  323.41
  4104.1  320.69  4200.7  321.61  4346.9  319.97  4513.6  320.51  4603.8  317.92
  4700.2  319.05  4891.4  318.23  4984.3  319.36  4994.4  316.91    4998  311.44
  4999.8  311.24  5004.4  312.56  5014.4  311.44  5034.4  319.04  5069.9  323.04
  5124.6  326.98  5334.9  338.74    5395  339.54  5585.3  338.22  5705.2  339.88
#Mann= 8 ,-1 , 0
  2367.6     .12       0  2787.3     .05       0  3855.9     .12       0
  4104.1     .05       0  4700.2      .1       0  4891.4     .05       0
  4984.3     .04       0  5034.4     .05       0
Bank Sta=4984.3,5034.4
XS Rating Curve= 0 ,0
Exp/Cntr=0.3,0.1

Type RM Length L Ch R = 1 ,572589  ,201,201,201
BEGIN DESCRIPTION:
WFSJ Main 562.0
END DESCRIPTION:
XS GIS Cut Line= 3
      3711962.15     10242338.91      3713837.17     10243364.97
      3715243.13     10243557.63
#Sta/Elev= 30
  2517.6  337.48  2590.9  337.56  2864.1  332.56  3025.7  329.43  3178.9  329.36
  3333.5  325.75    3746  323.68  3910.4  322.63  4077.1  320.86  4158.6  322.27
  4278.1  319.21  4529.3  318.73  4816.5  318.52  4883.3  319.14  4955.6  318.14
  4978.7  316.56  4988.8  311.54  4999.8  309.85    5009  311.38  5019.1  316.44
  5027.8  318.18  5032.8  318.46  5178.8  317.87  5254.3  318.59  5475.8  325.16
    5665  335.15  5755.9  332.56  5786.2  330.28    5877  334.42  6074.1  339.68
#Mann= 10 ,-1 , 0
  2517.6     .12       0  2864.1     .05       0    3746     .12       0
  3910.4     .05       0  4529.3     .12       0  4816.5     .05       0
  4883.3      .1       0  4955.6     .07       0  5032.8      .1       0
  5178.8     .05       0
Bank Sta=4955.6,5027.8
XS Rating Curve= 0 ,0
Exp/Cntr=0.3,0.1

Type RM Length L Ch R = 1 ,572388  ,580,580,580
BEGIN DESCRIPTION:
Mapping XS 62c277cc
END DESCRIPTION:
XS GIS Cut Line= 4
      3710529.88     10244708.71      3711936.13     10243187.88
      3712967.38      10243573.3      3715283.93     10243640.97
#Sta/Elev= 30
   594.1   334.4   951.9  331.25  1291.5  332.41  1612.1  326.57  1899.4  321.98
  1956.6  322.72  2020.7   318.2  2048.5  323.31  2111.8  322.83  2396.9  321.87
    2470  321.74    2678  324.02  2934.2  321.84  3028.3  324.55  3801.6  321.52
  3999.2  321.67  4002.8  321.88  4327.1  320.92  4427.1  317.37  4637.4  317.81
  4897.3  318.72  4977.3  317.51  4999.8  312.13  5047.4  318.97  5247.9  317.72
  5467.6   323.1  5667.6  332.45  5747.7  326.83  5907.7  335.79  6083.9  338.14
#Mann= 13 ,-1 , 0
   594.1     .05       0  1612.1     .12       0  1899.4      .1       0
  2111.8     .05       0  2396.9     .12       0    2470     .05       0
  3801.6     .12       0  3999.2     .05       0  4002.8      .1       0
  4637.4     .08       0  4897.3     .07       0  5047.4     .08       0
  5247.9     .05       0
#XS Ineff= 1 ,-1
    1450  3028.3  324.55
Permanent Ineff=
       F
Bank Sta=4897.3,5047.4
XS Rating Curve= 0 ,0
Exp/Cntr=0.3,0.1

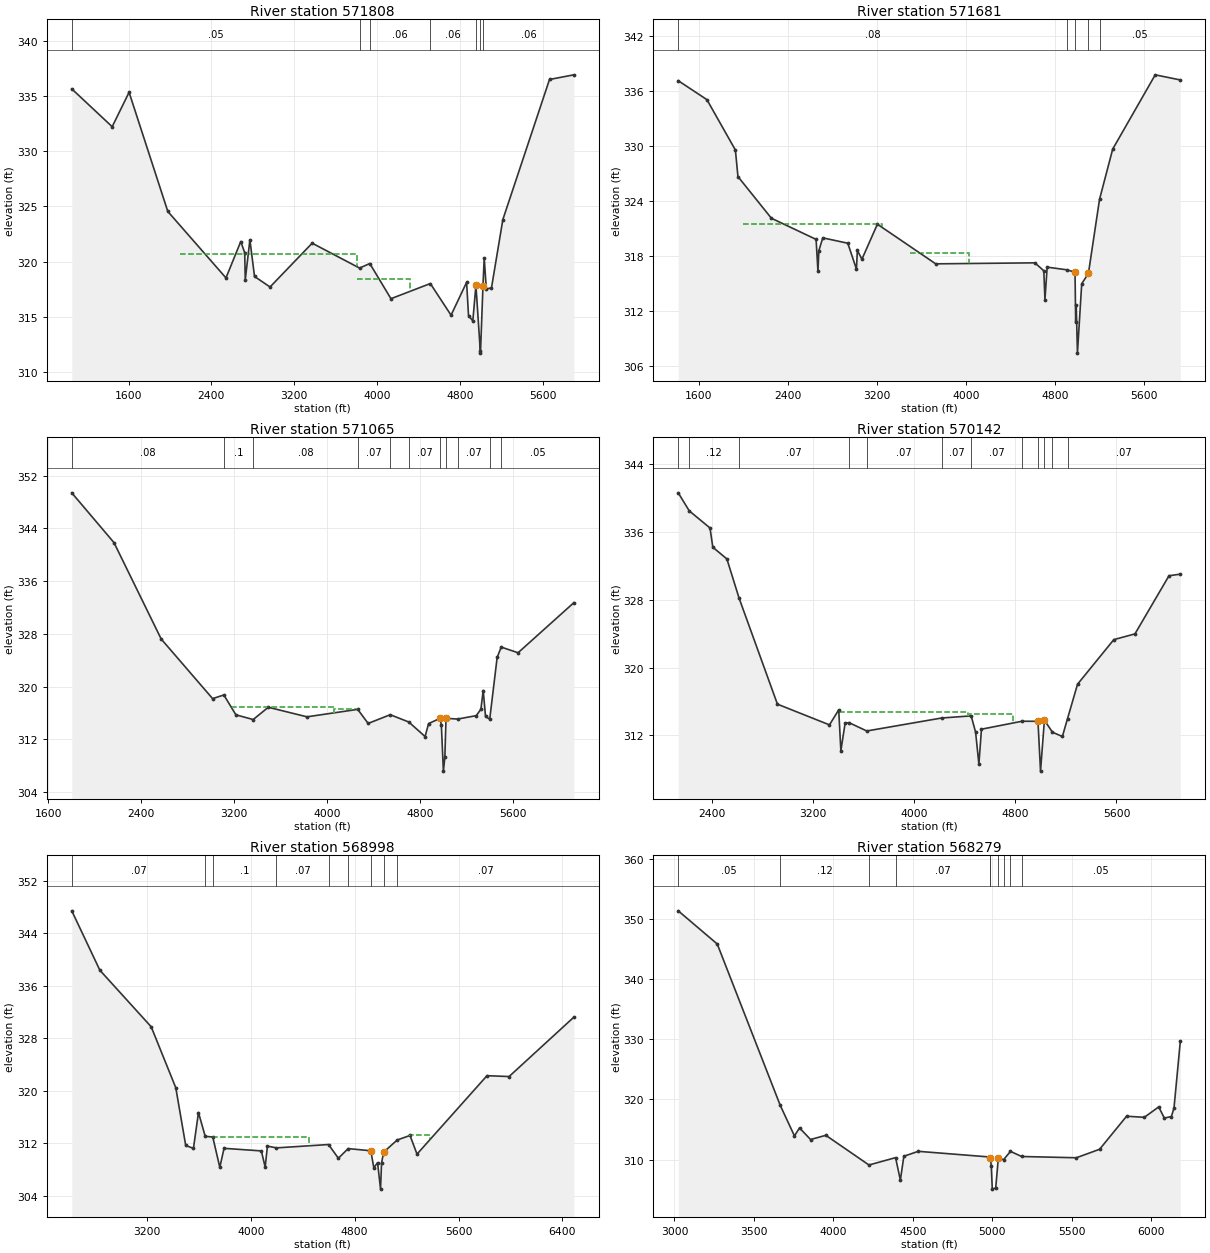
Type RM Length L Ch R = 1 ,571808  ,127,127,127
BEGIN DESCRIPTION:
Mapping XS 6d246c40
END DESCRIPTION:
XS GIS Cut Line= 5
      3710733.01     10244667.04      3711092.38     10244245.17
      3712561.13     10243937.88      3712899.67     10243911.84
      3715352.76     10244021.21
#Sta/Elev= 30
  1051.9  335.63  1442.2  332.21  1605.5  335.32  1979.5  324.55  2541.4  318.54
  2684.4  321.83  2722.5  320.81  2727.6  318.36  2772.5  321.99  2817.2  318.67
  2967.2  317.72  3374.1  321.68  3831.9  319.43  3930.6  319.84    4135  316.66
  4515.4  318.03  4715.6  315.17  4865.8  318.14  4884.5  315.12  4925.8  314.66
  4955.9  317.86    4998  311.94  4999.8  311.74 5023.76  317.81  5035.9  320.35
    5056  317.55    5106  317.63  5216.1  323.82  5666.6  336.48  5901.7   336.9
#Mann= 7 ,-1 , 0
  1051.9     .05       0  3831.9     .12       0  3930.6     .06       0
  4515.4     .06       0  4955.9     .05       0    4998     .05       0
 5023.76     .06       0
#XS Ineff= 3 ,-1
  5035.9    5170  320.35    2100  3804.7   320.7    3805  4315.2  318.45
Permanent Ineff=
       F       F       F
Bank Sta=4955.9,5023.76
XS Rating Curve= 0 ,0
Exp/Cntr=0.3,0.1

Type RM Length L Ch R = 1 ,571681  ,616,616,616
BEGIN DESCRIPTION:
WFSJ Main 561.0
END DESCRIPTION:
XS GIS Cut Line= 4
      3710977.75     10244682.69      3712660.09     10244031.63
      3714759.05     10244120.17        3715363.     10244120.17
#Sta/Elev= 30
  1414.9  337.16  1672.3  335.09  1928.2  329.59  1951.1  326.69  2251.4  322.14
  2652.9  319.83  2669.6  316.34  2677.5  318.59  2712.8     320  2937.6  319.41
  3015.3  316.58  3023.4  318.62  3064.5  317.67  3203.4  321.49    3727  317.16
  4617.8  317.27  4697.9   316.4  4707.9  313.23  4727.9   316.8  4903.3  316.51
  4978.1  316.25  4984.1  310.76  4989.1  312.64  4999.8  307.41  5038.2  314.99
  5098.3  316.11  5198.3  324.21  5316.5  329.69  5698.4   337.8  5923.6  337.24
#Mann= 5 ,-1 , 0
  1414.9     .08       0  4903.3     .08       0  4978.1     .05       0
  5098.3     .08       0  5198.3     .05       0
#XS Ineff= 2 ,-1
    2000  3246.6  321.48    3500  4027.3  318.29
Permanent Ineff=
       F       F
Bank Sta=4978.1,5098.3
XS Rating Curve= 0 ,0
Exp/Cntr=0.3,0.1

Type RM Length L Ch R = 1 ,571065  ,923,923,923
BEGIN DESCRIPTION:
WFSJ Main 560.0
END DESCRIPTION:
XS GIS Cut Line= 3
      3711067.89     10245311.06       3713295.5     10244568.09
      3715267.85     10244561.07
#Sta/Elev= 30
  1801.8  349.38  2165.3  341.83  2571.1  327.23  3013.7  318.19  3110.5  318.74
  3214.3  315.73    3363  315.02  3493.2  316.88  3825.7  315.43  4262.4  316.56
  4352.4  314.43  4542.4  315.75  4702.4  314.64  4842.4  312.44  4872.4  314.41
  4972.4   315.2  4982.4  314.13  4999.8   307.2  5012.4   309.3  5022.4  315.21
  5122.4  315.09  5282.4  315.61  5322.4  316.57  5342.4  319.42  5362.4  315.49
  5398.5  315.07  5462.4  324.43  5497.3     326  5642.4  325.14  6122.4  332.73
#Mann= 11 ,-1 , 0
  1801.8     .08       0  3110.5      .1       0    3363     .08       0
  4262.4     .07       0  4542.4     .07       0  4702.4     .07       0
  4972.4     .06       0  5022.4     .07       0  5122.4     .07       0
  5398.5      .1       0  5497.3     .05       0
#XS Ineff= 3 ,-1
  5342.4    5450  319.42    3170  4062.3  316.94  4062.5  4262.4  316.56
Permanent Ineff=
       F       T       F
Bank Sta=4972.4,5022.4
XS Rating Curve= 0 ,0
Exp/Cntr=0.3,0.1

Type RM Length L Ch R = 1 ,570142  ,1144,1144,1144
BEGIN DESCRIPTION:
Mapping XS 4490f281
END DESCRIPTION:
XS GIS Cut Line= 4
      3711712.16     10246151.43       3713540.3      10245260.8
      3715081.96     10244989.97      3715321.55     10244708.71
#Sta/Elev= 30
  2136.3  340.59  2223.6  338.46  2387.4  336.45  2409.6  334.18  2520.8   332.8
  2617.5  328.17  2920.3  315.69  3331.6  313.25  3404.7  315.02  3421.7   310.2
  3455.4  313.46  3486.3  313.51  3626.5  312.53  4218.1  314.06  4451.7  314.31
  4486.7  312.38  4512.6  308.62  4532.9  312.74  4854.4  313.68  4979.6  313.67
  4999.8   307.8  5030.4  313.81  5094.3  312.38  5172.5  311.88  5213.1  313.98
  5292.3  318.04  5578.7  323.29  5746.1  323.97  6015.1  330.82  6104.6  331.01
#Mann= 12 ,-1 , 0
  2136.3     .05       0  2223.6     .12       0  2617.5     .07       0
  3486.3      .1       0  3626.5     .07       0  4218.1     .07       0
  4451.7     .07       0  4854.4     .08       0  4979.6     .06       0
  5030.4     .08       0  5094.3     .07       0  5213.1     .07       0
#XS Ineff= 3 ,-1
    2980  3404.7  315.02  3404.8  4427.2  314.78  4429.2  4778.4  314.55
Permanent Ineff=
       T       T       T
Bank Sta=4979.6,5030.4
XS Rating Curve= 0 ,0
Exp/Cntr=0.3,0.1

Type RM Length L Ch R = 1 ,568998  ,719,719,719
BEGIN DESCRIPTION:
WFSJ Main 559.0
END DESCRIPTION:
XS GIS Cut Line= 3
      3712154.89     10246693.09      3714673.07     10245584.97
      3715399.64       10244740.
#Sta/Elev= 30
  2622.4  347.39  2838.6  338.35  3233.8  329.74  3423.2  320.46  3499.7  311.67
  3559.1  311.22    3598  316.68  3649.9  313.05  3707.9  312.96  3762.2  308.34
  3794.7  311.23    4082  310.84  4111.5  308.36  4128.7  311.57  4198.6   311.3
  4599.4  311.81  4674.9  309.72  4750.4  311.19  4924.7  310.86    4948  308.27
  4976.8  309.05  4999.8  305.02  5007.4  308.98  5023.5  310.65  5127.8   312.5
  5226.6  313.19  5280.5  310.35  5819.3  322.29  5989.4  322.16    6488   331.2
#Mann= 9 ,-1 , 0
  2622.4     .07       0  3649.9     .12       0  3707.9      .1       0
  4198.6     .07       0  4599.4     .07       0  4750.4     .07       0
  4924.7     .06       0  5023.5     .07       0  5127.8     .07       0
#XS Ineff= 3 ,-1
    3440    3598  316.68    3700  4448.5  312.93    5215    5380  313.25
Permanent Ineff=
       T       T       T
Bank Sta=4924.7,5023.5
XS Rating Curve= 0 ,0
Exp/Cntr=0.3,0.1

Type RM Length L Ch R = 1 ,568279  ,1590,1590,1590
BEGIN DESCRIPTION:
WFSJ Main 558.0
END DESCRIPTION:
XS GIS Cut Line= 3
      3712467.88     10246911.06      3713912.37     10246444.47
      3715368.45     10245687.87
#Sta/Elev= 30
  3023.8  351.33  3269.3  345.82  3665.5  319.02    3755  313.94    3787  315.27
  3856.3  313.34  3952.4  314.04  4223.8  309.11  4391.2  310.33  4421.4   306.6
  4443.3  310.56  4534.2  311.38  4983.2  310.44  4987.5  310.35  4993.4  308.92
  4999.8   305.1  5021.3   305.3  5037.7  310.27  5070.9     310  5114.1  311.37
  5184.5  310.52  5528.4  310.31  5674.9  311.72  5844.6  317.21  5956.6  317.03
  6046.8  318.76  6082.2   316.9  6126.4  317.16  6142.9  318.56  6182.7  329.64
#Mann= 10 ,-1 , 0
  3023.8     .05       0  3665.5     .12       0  4223.8      .1       0
  4391.2     .07       0  4983.2      .1       0  4987.5     .07       0
  5037.7      .1       0  5070.9     .05       0  5114.1      .1       0
  5184.5     .05       0
Bank Sta=4987.5,5037.7
XS Rating Curve= 0 ,0
Exp/Cntr=0.3,0.1