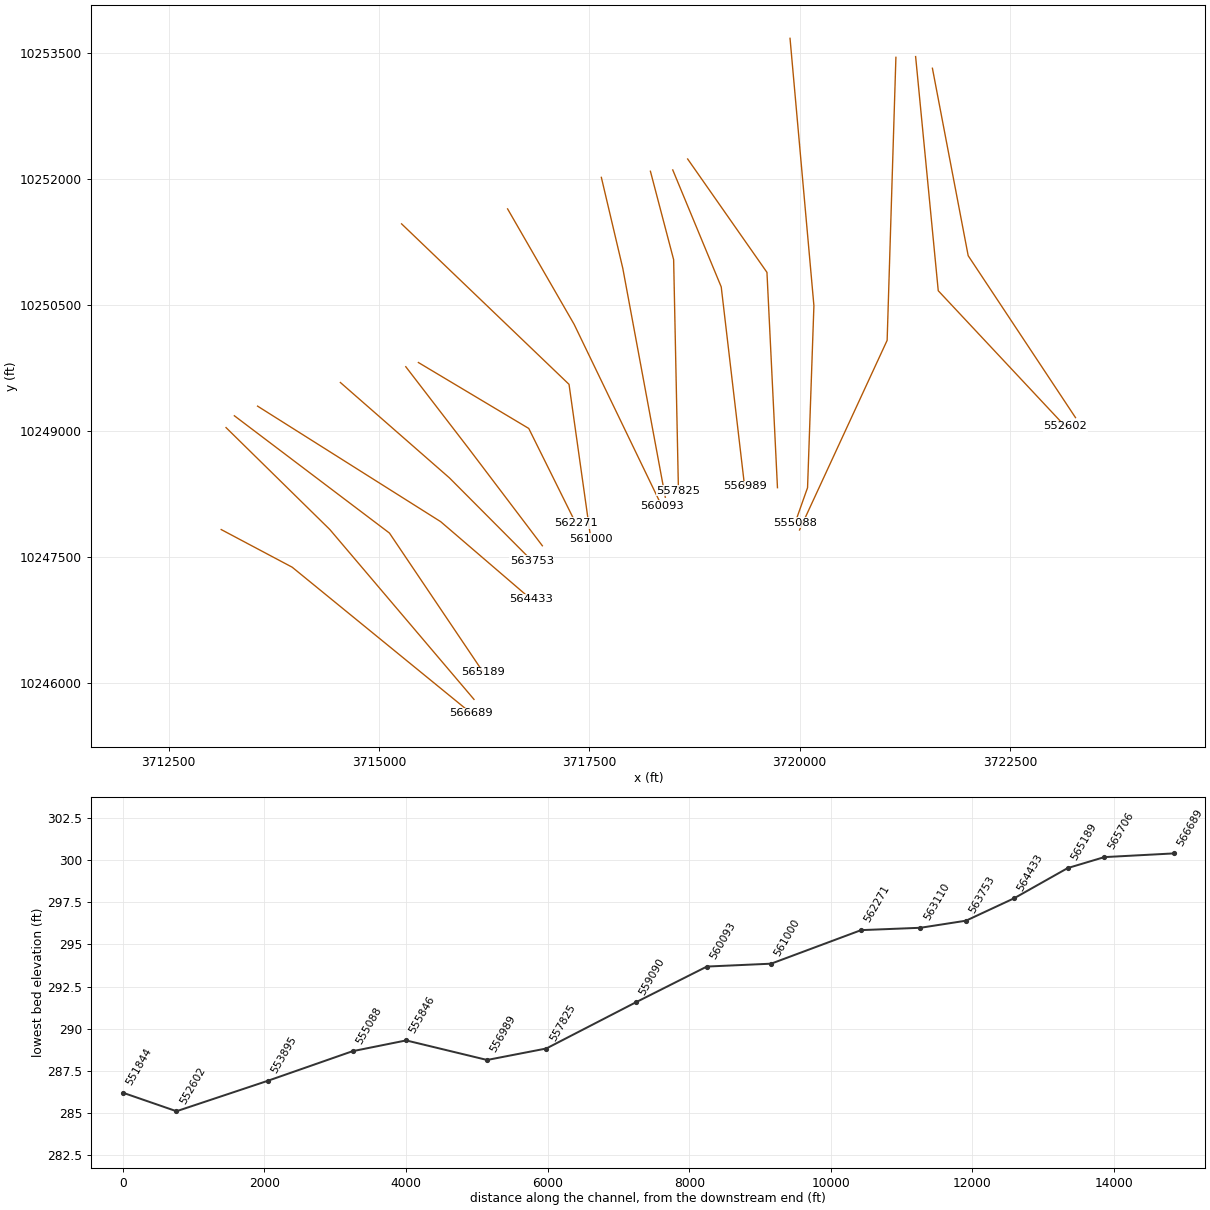
HEC-RAS study WFSJ Main.prj: WFSJ Main Base Level Engineering

--- WFSJ Main.g02 (geometry) --- (continued)

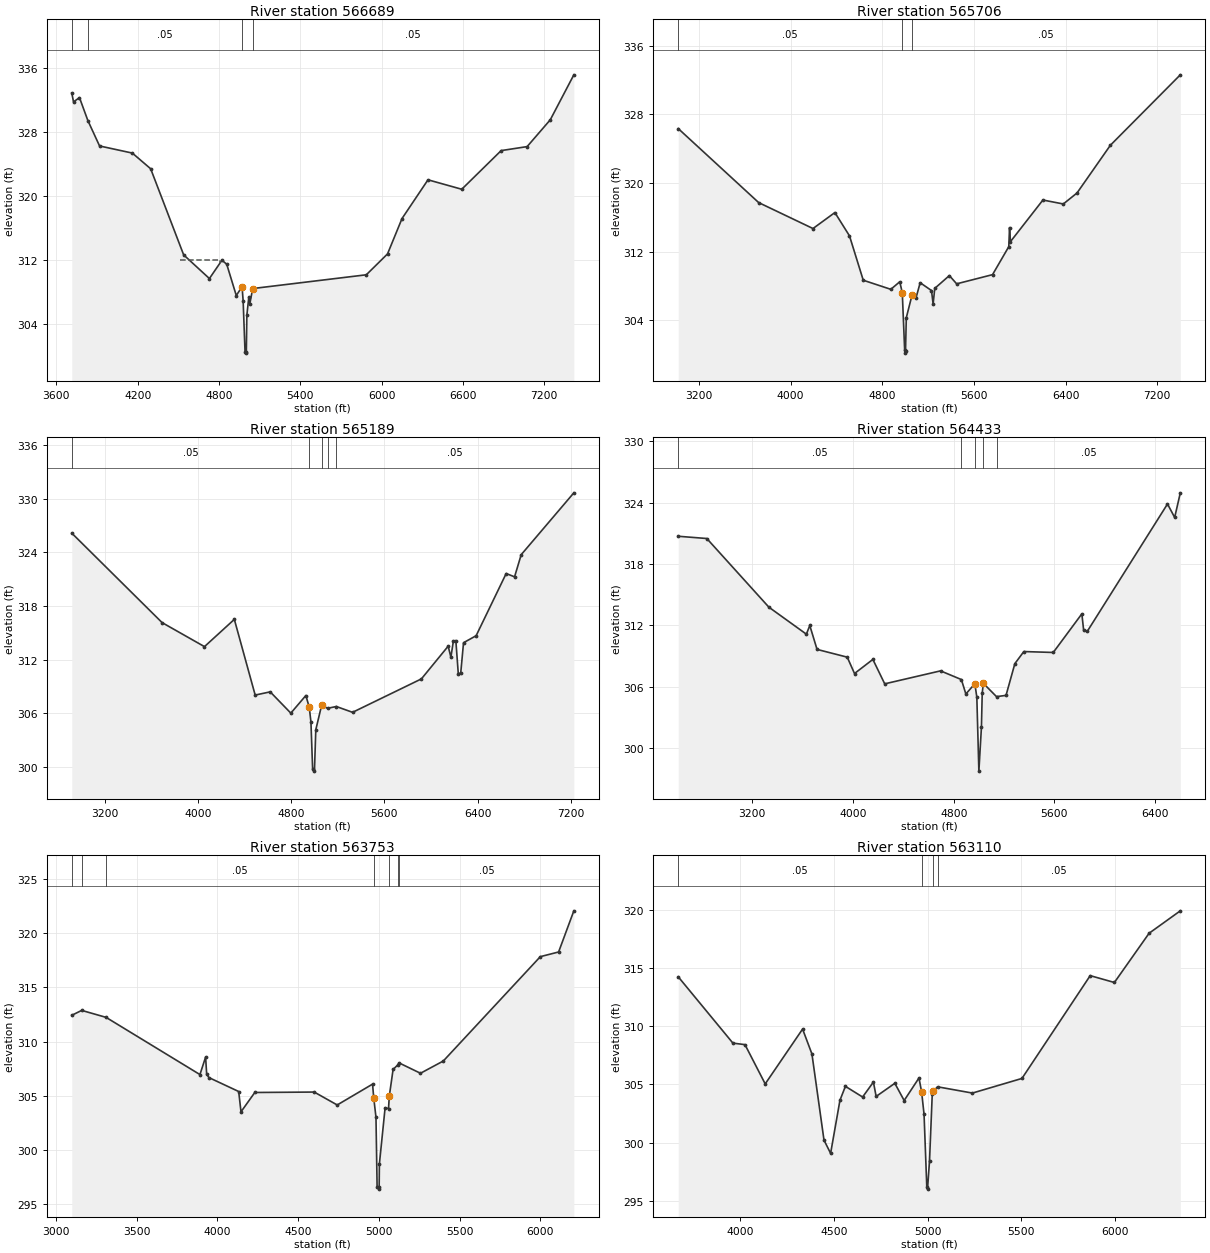
Type RM Length L Ch R = 1 ,566689  ,983,983,983
BEGIN DESCRIPTION:
WFSJ Main 557.0
END DESCRIPTION:
XS GIS Cut Line= 3
      3713123.63      10247823.3      3713967.38     10247375.38
      3716097.41     10245635.94
#Sta/Elev= 30
  3713.7  332.92  3726.6   331.8  3770.6  332.33  3832.6  329.46  3918.8  326.29
  4160.7   325.4  4295.9  323.44  4539.4  312.68  4729.4  309.72    4822  312.01
  4857.2  311.51  4927.8   307.6  4970.6   308.7  4978.5   306.9  4992.3   300.6
  4999.8   300.4    5002   300.6  5005.8  305.13  5020.2  307.38  5028.1  306.59
  5048.9  308.47  5887.4  310.19    6044   312.8  6150.9  317.22  6342.6  322.06
  6591.8  320.88  6882.5  325.71  7074.2  326.21  7245.1  329.56    7419  335.18
#Mann= 4 ,-1 , 0
  3713.7     .12       0  3832.6     .05       0  4970.6     .04       0
  5048.9     .05       0
#XS Ineff= 1 ,-1
    4510  4807.7   312.1
Permanent Ineff=
       F
Bank Sta=4970.6,5048.9
XS Rating Curve= 0 ,0
Exp/Cntr=0.3,0.1

Type RM Length L Ch R = 1 ,565706  ,517,517,517
BEGIN DESCRIPTION:
WFSJ Main 556.0
END DESCRIPTION:
XS GIS Cut Line= 3
      3713180.93     10249036.84       3714415.3      10247823.3
      3716128.82     10245802.48
#Sta/Elev= 30
  3019.9  326.33  3721.8  317.71  4195.6  314.69  4386.6  316.55  4513.9  313.84
  4634.1  308.67  4874.6  307.61  4952.6  308.49  4974.6  307.23  4995.4  300.54
  4999.8  300.18  5002.9  300.38  5009.7   304.3  5059.1  306.91  5094.7  306.62
  5130.6  308.38  5229.4  307.47  5243.7  305.91    5258  307.72  5385.4  309.21
  5449.1  308.25  5762.2  309.32  5903.9  312.58  5910.5   314.8  5918.2  313.16
  6201.6  318.01  6379.6  317.55  6499.2  318.83  6790.4  324.39  7400.4  332.59
#Mann= 3 , 0 , 0
  3019.9     .05       0  4974.6     .04       0  5059.1     .05       0
Bank Sta=4974.6,5059.1
XS Rating Curve= 0 ,0
Exp/Cntr=0.3,0.1

Type RM Length L Ch R = 1 ,565189  ,756,756,756
BEGIN DESCRIPTION:
WFSJ Main 555.0
END DESCRIPTION:
XS GIS Cut Line= 3
      3713279.87     10249177.47      3715123.63     10247781.63
      3716237.99     10246125.71
#Sta/Elev= 30
  2917.3  326.16  3692.2  316.15  4056.1  313.46  4312.3  316.51  4491.2  308.04
  4620.2   308.4  4797.1  306.02  4926.1  307.99  4955.2  306.68  4969.7  305.03
  4984.3  299.73  4999.8  299.53  5011.4  304.16  5061.3  306.89  5112.3  306.56
  5187.7  306.76  5326.9  306.11  5917.6  309.85  6147.3  313.51  6170.7  312.28
  6192.2   314.1  6213.2  314.13  6234.2  310.42  6255.2  310.52  6279.2   313.9
  6387.2  314.68  6645.1  321.64  6717.1  321.27  6774.1  323.75  7225.8  330.67
#Mann= 5 ,-1 , 0
  2917.3     .05       0  4955.2     .04       0  5061.3     .05       0
  5112.3      .1       0  5187.7     .05       0
Bank Sta=4955.2,5061.3
XS Rating Curve= 0 ,0
Exp/Cntr=0.3,0.1

Type RM Length L Ch R = 1 ,564433  ,680,680,680
BEGIN DESCRIPTION:
WFSJ Main 554.0
END DESCRIPTION:
XS GIS Cut Line= 3
      3713555.91     10249292.06        3715733.     10247917.05
      3716805.37     10246995.65
#Sta/Elev= 30
  2611.3  320.72  2838.3   320.5  3331.6  313.78  3629.3  311.14  3656.4  311.99
  3714.1  309.65  3954.1  308.89  4011.7  307.29  4157.6  308.67  4251.7  306.28
  4695.2  307.55  4860.8   306.7  4896.3  305.29  4967.9  306.29  4983.5  304.97
  4999.8  297.74    5020  302.02  5026.4  305.38  5035.3  306.33  5139.8  305.03
  5215.4  305.15  5285.7  308.26    5357  309.44  5590.7  309.35  5817.9  313.13
  5832.2  311.52  5860.7  311.41  6498.3  323.88  6555.3  322.56  6600.1  324.97
#Mann= 5 ,-1 , 0
  2611.3     .05       0  4860.8      .1       0  4967.9     .07       0
  5035.3      .1       0  5139.8     .05       0
Bank Sta=4967.9,5035.3
XS Rating Curve= 0 ,0
Exp/Cntr=0.3,0.1

Type RM Length L Ch R = 1 ,563753  ,643,643,643
BEGIN DESCRIPTION:
Mapping XS 66773f02
END DESCRIPTION:
XS GIS Cut Line= 3
      3714540.26     10249573.33      3715837.17     10248437.88
       3716815.1     10247454.76
#Sta/Elev= 30
  3097.7  312.42  3159.3  312.87    3310  312.23  3891.7  306.96  3926.8  308.57
  3933.5  306.99  3947.7  306.68  4131.8   305.4  4146.1  303.53  4231.5  305.31
  4599.7  305.35  4742.1  304.16  4961.1  306.08  4968.2  304.84  4982.3  303.03
  4989.3  296.61  4999.8  296.41    5002  296.61  5003.5  298.74  5038.9  303.91
  5060.1  303.82  5064.6  304.95  5088.3  307.43  5116.6  307.84  5125.9  308.03
    5258  307.08  5399.5  308.21  6000.5  317.82  6113.7  318.25  6208.1  322.04
#Mann= 7 ,-1 , 0
  3097.7      .1       0  3159.3     .12       0    3310     .05       0
  4968.2     .04       0  5064.6     .05       0  5116.6      .1       0
  5125.9     .05       0
Bank Sta=4968.2,5064.6
XS Rating Curve= 0 ,0
Exp/Cntr=0.3,0.1

Type RM Length L Ch R = 1 ,563110  ,839,839,839
BEGIN DESCRIPTION:
WFSJ Main 553.0
END DESCRIPTION:
XS GIS Cut Line= 3
      3715317.88     10249761.03      3716066.34     10248786.84
      3716941.32     10247630.61
#Sta/Elev= 30
    3670  314.27  3961.7  308.56  4026.1  308.43    4134  305.05  4333.4  309.77
  4383.2  307.63  4447.6  300.21  4482.9  299.07  4532.7  303.64  4561.8  304.84
  4653.6  303.92  4711.3  305.21  4725.8  303.97  4825.5   305.1  4875.3  303.62
  4954.3  305.56  4968.4  304.36  4981.4  302.43    4996  296.19  4999.8  295.99
  5010.5  298.39  5025.1  304.15  5031.4  304.43  5053.3   304.8  5239.4  304.26
  5503.7  305.52  5867.8  314.37  5996.8  313.78    6182  318.02  6348.5  319.95
#Mann= 4 ,-1 , 0
    3670     .05       0  4968.4     .05       0  5031.4      .1       0
  5053.3     .05       0
#XS Ineff= 1 ,-1
    3780  4333.4  309.77
Permanent Ineff=
       F
Bank Sta=4968.4,5031.4
XS Rating Curve= 0 ,0
Exp/Cntr=0.3,0.1

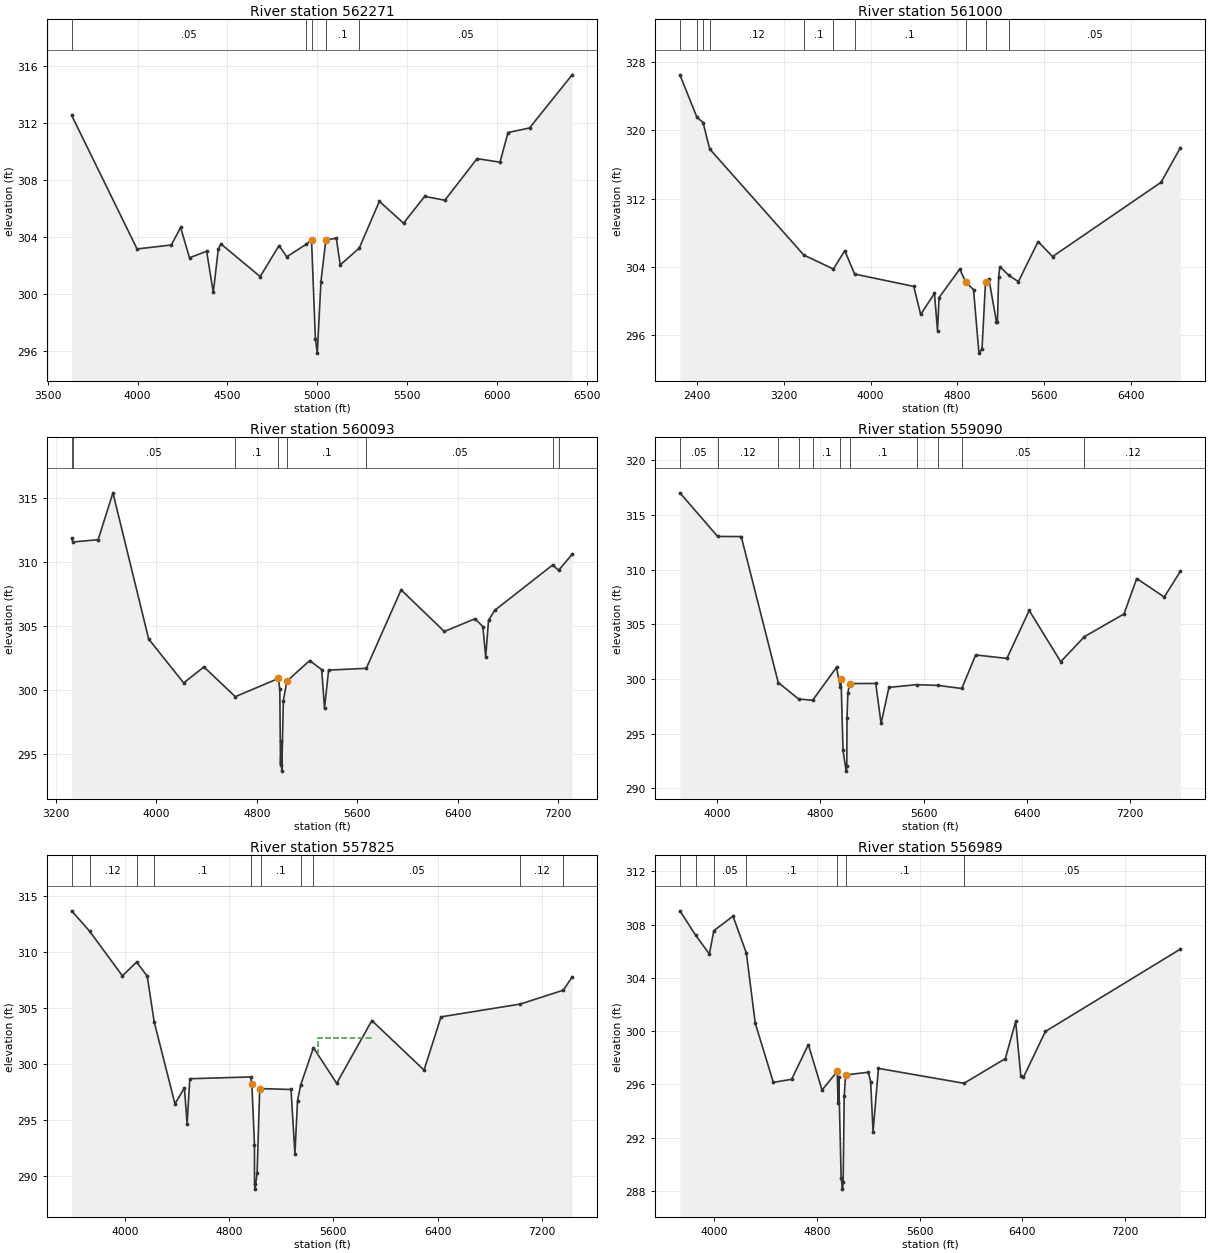
Type RM Length L Ch R = 1 ,562271  ,1271,1271,1271
BEGIN DESCRIPTION:
WFSJ Main 552.0
END DESCRIPTION:
XS GIS Cut Line= 3
      3715467.85     10249811.07      3716779.88     10249026.42
      3717337.16     10247901.45
#Sta/Elev= 30
  3633.3  312.53    3997  303.16  4187.7  303.44  4239.2  304.67  4288.8  302.54
  4384.1     303  4421.1  300.11  4448.9  303.15  4463.9  303.51    4682  301.22
  4786.8   303.4  4829.6  302.61  4938.3  303.49  4967.7  303.79  4989.1  296.87
  4999.8  295.85  5019.9  300.87  5047.4   303.8  5105.8  303.91  5127.2  302.04
    5233  303.22    5345   306.5  5479.5  304.97  5597.2  306.85  5709.4  306.58
  5888.7   309.5  6016.2  309.25  6060.8  311.33  6180.3  311.65  6417.5  315.38
#Mann= 5 ,-1 , 0
  3633.3     .05       0  4938.3      .1       0  4967.7     .07       0
  5047.4      .1       0    5233     .05       0
Bank Sta=4967.7,5047.4
XS Rating Curve= 0 ,0
Exp/Cntr=0.3,0.1

Type RM Length L Ch R = 1 ,561000  ,907,907,907
BEGIN DESCRIPTION:
WFSJ Main 551.0
END DESCRIPTION:
XS GIS Cut Line= 3
      3715267.86     10251461.06      3717258.56     10249551.35
      3717517.86     10247711.03
#Sta/Elev= 30
  2241.4  326.52  2397.6  321.55    2455  320.92  2515.8  317.82  3384.3  305.37
  3657.5  303.73  3762.1  305.89  3852.9  303.14  4398.6  301.69  4462.1   298.4
  4589.5  300.87  4617.8  296.51  4631.9  300.38  4822.8  303.72  4879.4  302.16
  4950.2  301.31  4999.8  293.86  5028.2  294.35  5060.9  302.26  5091.2  302.59
  5161.9  297.52  5170.5  297.56  5182.1  302.85  5192.2     304  5277.1  302.98
  5363.8  302.25  5545.6  306.95  5678.9  305.19  6680.5  313.91  6858.5  317.97
#Mann= 10 ,-1 , 0
  2241.4     .05       0  2397.6     .12       0    2455     .05       0
  2515.8     .12       0  3384.3      .1       0  3657.5     .05       0
  3852.9      .1       0  4879.4     .07       0  5060.9      .1       0
  5277.1     .05       0
#XS Ineff= 1 ,-1
    3185  3762.1  305.89
Permanent Ineff=
       F
Bank Sta=4879.4,5060.9
XS Rating Curve= 0 ,0
Exp/Cntr=0.3,0.1

Type RM Length L Ch R = 1 ,560093  ,1003,1003,1003
BEGIN DESCRIPTION:
WFSJ Main 550.0
END DESCRIPTION:
XS GIS Cut Line= 3
      3716528.14     10251639.27      3717319.81     10250264.27
       3718360.7     10248104.42
#Sta/Elev= 30
  3327.1  311.86    3336  311.54  3537.7  311.72  3655.5  315.37  3940.1  303.98
  4218.8  300.56  4379.8  301.81  4629.9  299.49  4972.8  300.91  4983.9  300.07
  4989.6  294.19  4995.2  296.04  4999.6  293.69  5012.2  299.19  5040.4   300.7
  5221.4   302.3  5317.4   301.6    5340   298.6  5372.4  301.56  5672.8   301.7
  5949.6  307.81  6293.8  304.57  6538.3  305.56  6600.6  304.95  6623.2   302.6
  6645.8  305.45  6696.6  306.23    7155  309.74  7203.7  309.34  7311.3  310.58
#Mann= 8 ,-1 , 0
  3327.1     .12       0    3336     .05       0  4629.9      .1       0
  4972.8     .07       0  5040.4      .1       0  5672.8     .05       0
    7155     .12       0  7203.7     .05       0
#XS Ineff= 1 ,-1
  5949.6    7050  307.81
Permanent Ineff=
       F
Bank Sta=4972.8,5040.4
XS Rating Curve= 0 ,0
Exp/Cntr=0.3,0.1

Type RM Length L Ch R = 1 ,559090  ,1265,1265,1265
BEGIN DESCRIPTION:
WFSJ Main 549.0
END DESCRIPTION:
XS GIS Cut Line= 3
      3717642.72     10252014.29      3717897.93     10250930.94
      3718402.99     10248207.78
#Sta/Elev= 30
  3710.1  317.03  4002.6  313.04  4185.6  313.03  4472.7  299.67  4630.7  298.17
  4739.2  298.05  4924.7  301.06  4954.9  299.23    4960  299.99  4975.5  293.47
  4999.5  291.57  5004.6  292.07    5006  296.39  5012.9  298.73  5026.4  299.58
  5229.3  299.59  5270.5  295.93  5331.5  299.23  5545.5  299.48  5714.2  299.41
  5896.4  299.13  6004.7   302.2  6246.8  301.88  6419.7  306.27  6664.3  301.58
  6847.9  303.87  7155.2  305.95  7253.7  309.19  7467.3   307.5  7592.7  309.85
#Mann= 11 ,-1 , 0
  3710.1     .05       0  4002.6     .12       0  4472.7      .1       0
  4630.7     .12       0  4739.2      .1       0  4954.9     .07       0
  5026.4      .1       0  5545.5     .05       0  5714.2      .1       0
  5896.4     .05       0  6847.9     .12       0
#XS Ineff= 1 ,-1
  6419.7    7210  306.27
Permanent Ineff=
       F
Bank Sta=4960,5026.4
XS Rating Curve= 0 ,0
Exp/Cntr=0.3,0.1

Type RM Length L Ch R = 1 ,557825  ,836,836,836
BEGIN DESCRIPTION:
WFSJ Main 548.0
END DESCRIPTION:
XS GIS Cut Line= 3
      3718226.05     10252087.22       3718502.1      10251035.1
      3718559.38     10248285.63
#Sta/Elev= 30
  3593.2  313.66  3730.3  311.85  3982.1  307.86  4091.4  309.09  4172.5  307.83
  4226.1  303.74  4385.3  296.44  4457.7  297.86  4478.3  294.66    4499  298.68
    4965  298.84    4975  298.18    4995  292.79  4995.2  289.33  4999.5  288.83
    5015  290.25    5035  297.73    5045   297.8  5275.1  297.72  5305.1  291.99
  5325.1  296.72  5349.1  298.12  5447.3  301.45  5625.2  298.27  5895.2  303.87
  6295.3  299.45  6425.3   304.2  7032.8  305.34  7363.6  306.58    7431  307.76
#Mann= 10 ,-1 , 0
  3593.2     .05       0  3730.3     .12       0  4091.4     .05       0
  4226.1      .1       0    4965     .07       0    5045      .1       0
  5349.1     .12       0  5447.3     .05       0  7032.8     .12       0
  7363.6     .05       0
#XS Ineff= 2 ,-1
  5485.1    5895  302.34  5895.2    6830  303.87
Permanent Ineff=
       F       F
Bank Sta=4975,5035
XS Rating Curve= 0 ,0
Exp/Cntr=0.3,0.1

Type RM Length L Ch R = 1 ,556989  ,1143,1143,1143
BEGIN DESCRIPTION:
WFSJ Main 547.0
END DESCRIPTION:
XS GIS Cut Line= 3
      3718491.67     10252102.85      3719067.85     10250711.07
      3719345.85     10248337.22
#Sta/Elev= 30
  3734.2  309.03  3855.7  307.21  3963.4  305.79  3998.1  307.54  4147.4  308.63
  4251.3  305.86  4320.6   300.6  4461.3  296.16  4603.7  296.39    4734  298.99
  4840.4  295.58  4959.1  296.99  4965.3  294.58  4970.7  296.55  4989.2  289.01
  4999.5  288.15  5004.9  288.65  5013.1   295.1  5024.1  296.72    5202  296.92
  5218.9  296.21  5237.8  292.46  5279.6  297.21  5945.7  296.09  6267.5  297.94
    6348  300.73  6388.3  296.63  6408.5  296.54  6579.6  299.98  7630.6  306.16
#Mann= 7 ,-1 , 0
  3734.2     .05       0  3855.7     .12       0  3998.1     .05       0
  4251.3      .1       0  4959.1     .07       0  5024.1      .1       0
  5945.7     .05       0
#XS Ineff= 1 ,-1
    6348    6900  300.73
Permanent Ineff=
       F
Bank Sta=4959.1,5024.1
XS Rating Curve= 0 ,0
Exp/Cntr=0.3,0.1

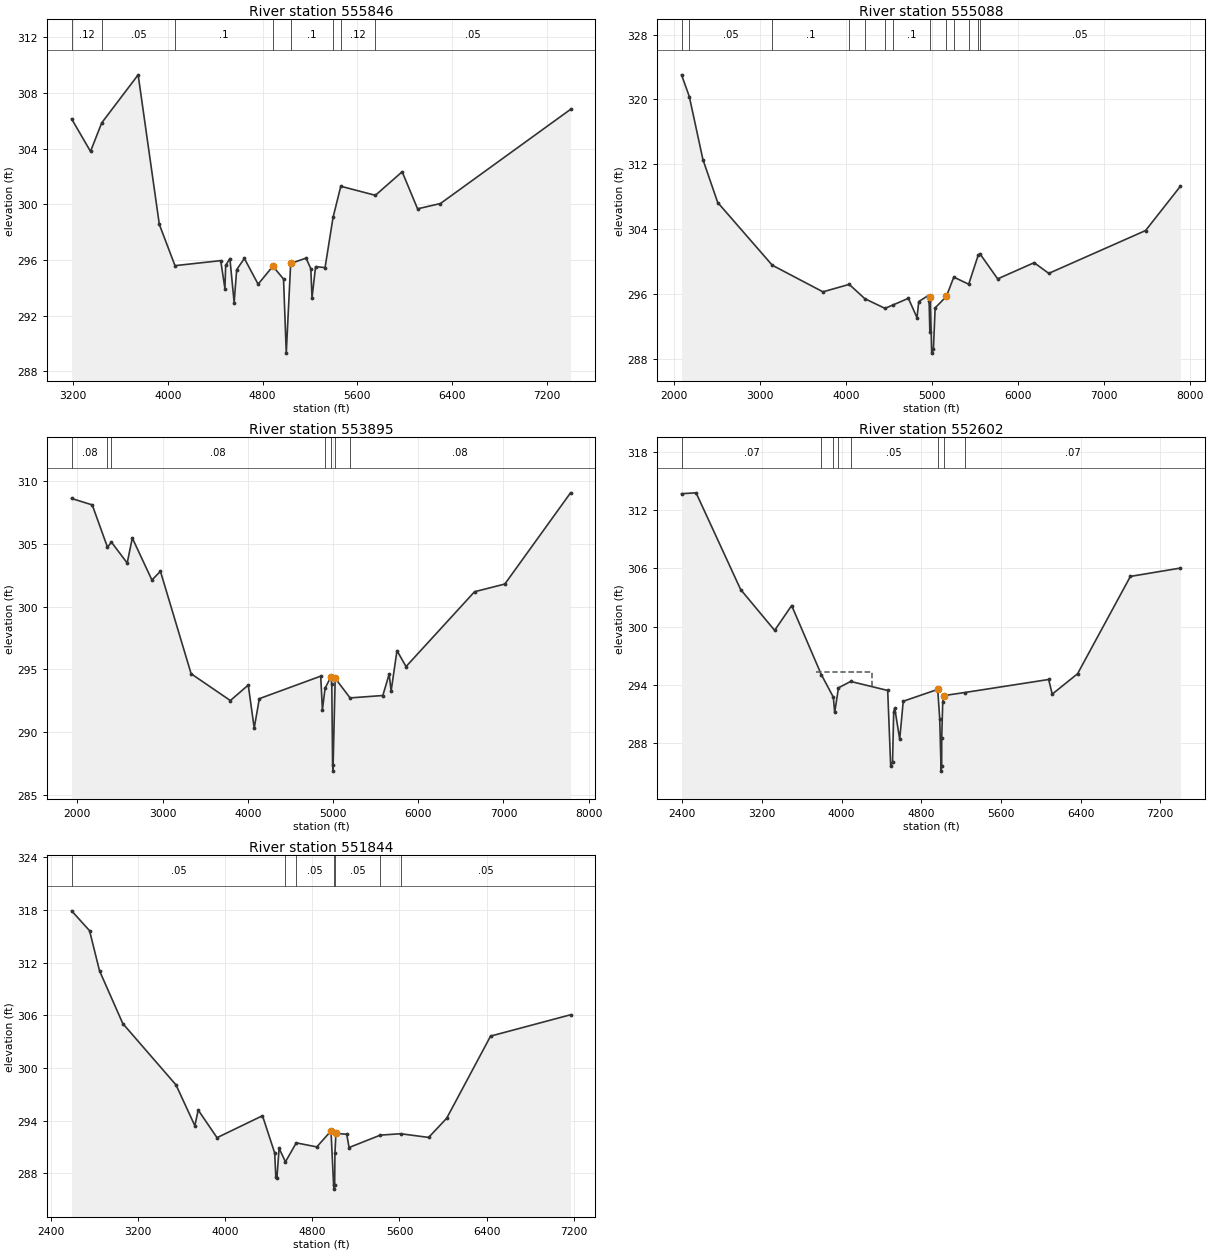
Type RM Length L Ch R = 1 ,555846  ,758,758,758
BEGIN DESCRIPTION:
WFSJ Main 546.0
END DESCRIPTION:
XS GIS Cut Line= 3
      3718668.75     10252233.04      3719611.48     10250884.06
      3719736.48     10248321.55
#Sta/Elev= 30
  3187.6  306.13  3347.2  303.79  3441.6  305.84  3749.2  309.29    3928  298.55
  4060.2  295.59  4446.1  295.95  4481.8  293.94  4487.9  295.61  4523.7   296.1
  4559.5  292.94  4580.8   295.3  4645.8  296.11  4761.8  294.26  4886.4  295.55
  4976.5  294.63  4999.5  289.31  5036.6  295.75  5166.7  296.13  5206.8  295.37
  5216.8  293.27  5246.8  295.52  5326.9  295.45  5394.2  299.05  5459.7  301.29
  5751.7  300.64  5977.7  302.33  6107.8  299.67  6300.7  300.05  7398.9  306.81
#Mann= 8 ,-1 , 0
  3187.6     .12       0  3441.6     .05       0  4060.2      .1       0
  4886.4     .07       0  5036.6      .1       0  5394.2     .05       0
  5459.7     .12       0  5751.7     .05       0
Bank Sta=4886.4,5036.6
XS Rating Curve= 0 ,0
Exp/Cntr=0.3,0.1

Type RM Length L Ch R = 1 ,555088  ,1193,1193,1193
BEGIN DESCRIPTION:
WFSJ Main 545.0
END DESCRIPTION:
XS GIS Cut Line= 4
      3719885.78     10253668.81      3720169.72     10250487.28
      3720094.11     10248321.56      3719946.76      10247905.5
#Sta/Elev= 30
  2090.3  323.04  2180.5  320.36    2339  312.57    2511  307.27  3145.1  299.53
  3734.6  296.24  4040.1  297.16  4222.4  295.39  4456.1   294.2  4554.4  294.64
  4728.5  295.44  4828.9  293.05    4849  295.04  4959.4  295.78  4969.4  295.07
  4978.3  291.24  4983.3  295.61  4999.5  288.67  5019.6  289.17  5039.7  294.26
  5170.2  295.67  5256.6  298.06  5429.9  297.18  5540.7  300.77  5560.7  300.94
    5767  297.84  6191.2  299.84  6361.3  298.52  7487.2  303.81  7892.9  309.29
#Mann= 13 ,-1 , 0
  2090.3     .12       0  2180.5     .05       0  3145.1      .1       0
  4040.1     .05       0  4222.4      .1       0  4456.1     .05       0
  4554.4      .1       0  4983.3     .07       0  5170.2      .1       0
  5256.6     .12       0  5429.9     .05       0  5540.7     .12       0
  5560.7     .05       0
Bank Sta=4983.3,5170.2
XS Rating Curve= 0 ,0
Exp/Cntr=0.3,0.1

Type RM Length L Ch R = 1 ,553895  ,1293,1293,1293
BEGIN DESCRIPTION:
WFSJ Main 544.0
END DESCRIPTION:
XS GIS Cut Line= 3
      3721144.46     10253443.04       3721040.3     10250075.04
      3719998.65     10247818.14
#Sta/Elev= 30
  1932.1  308.59  2174.2  308.08  2352.8  304.72  2399.5  305.12  2584.4  303.46
  2644.4  305.45  2874.5  302.11  2974.6   302.8  3334.7  294.66    3795  292.53
  4005.1  293.76  4075.1  290.34  4135.1  292.68  4855.5  294.47  4875.5   291.8
  4906.7  293.51  4975.5  294.42  4985.5  293.81    4995  287.42  4999.5  286.92
  5025.5   294.3  5200.2  292.74  5584.5  292.93  5658.8  294.63  5681.7  293.28
  5750.6   296.5  5856.8  295.23    6661  301.18  7016.2  301.79  7787.4  309.04
#Mann= 7 ,-1 , 0
  1932.1     .08       0  2352.8     .12       0  2399.5     .08       0
  4906.7      .1       0  4975.5     .07       0  5025.5      .1       0
  5200.2     .08       0
Bank Sta=4975.5,5025.5
XS Rating Curve= 0 ,0
Exp/Cntr=0.3,0.1

Type RM Length L Ch R = 1 ,552602  ,758,758,758
BEGIN DESCRIPTION:
WFSJ Main 543.0
END DESCRIPTION:
XS GIS Cut Line= 3
      3721378.84     10253451.73      3721647.93     10250665.31
      3723158.34     10249050.74
#Sta/Elev= 30
  2392.7  313.69  2538.7  313.78  2986.1  303.82  3327.7  299.61  3498.5  302.17
    3796  295.06  3917.2  292.73  3930.5  291.15  3968.6  293.69    4091  294.35
  4462.9  293.42  4493.1  285.61  4511.6  286.03  4523.2  291.21  4533.3   291.6
  4583.5   288.4  4618.9  292.31  4965.3  293.53  4985.4   290.5  4999.5  285.11
    5005  285.61  5005.5  288.57  5015.5  292.18  5025.6  292.89  5237.7  293.21
  6079.3  294.55    6115  293.04  6369.5  295.14    6900  305.17    7403  306.03
#Mann= 8 ,-1 , 0
  2392.7     .07       0    3796     .12       0  3917.2      .1       0
  3968.6     .12       0    4091     .05       0  4965.3     .03       0
  5025.6     .05       0  5237.7     .07       0
#XS Ineff= 1 ,-1
    3745  4302.1  295.28
Permanent Ineff=
       F
Bank Sta=4965.3,5025.6
XS Rating Curve= 0 ,0
Exp/Cntr=0.3,0.1

Type RM Length L Ch R = 1 ,551844  ,1794,1794,1794
BEGIN DESCRIPTION:
WFSJ Main 542.0
END DESCRIPTION:
XS GIS Cut Line= 3
      3721578.49     10253312.88      3722003.84     10251081.98
      3723279.47     10249155.52
#Sta/Elev= 30
  2589.3  317.91    2754  315.65  2845.6  311.08  3059.4  305.07  3548.1  298.08
  3721.1  293.43  3751.7  295.22  3924.7  292.07  4342.1  294.57  4454.1  290.33
  4464.3  287.63  4474.5  287.48  4494.8  290.86    4553  289.32  4652.2  291.48
  4840.9  291.02  4971.3  292.84    4995  286.71  4999.5  286.21    5005  286.71
  5007.4   290.3  5016.5  292.56  5115.8  292.46  5137.3  290.95  5423.7  292.36
  5610.2  292.52  5867.9   292.1  6033.4  294.28  6436.5  303.64  7170.9  306.07
#Mann= 7 ,-1 , 0
  2589.3     .05       0    4553     .12       0  4652.2     .05       0
    4995     .05       0    5005     .05       0  5423.7      .1       0
  5610.2     .05       0
#XS Ineff= 1 ,-1
    3630  4342.1  294.57
Permanent Ineff=
       F
Bank Sta=4971.3,5016.5
XS Rating Curve= 0 ,0
Exp/Cntr=0.3,0.1