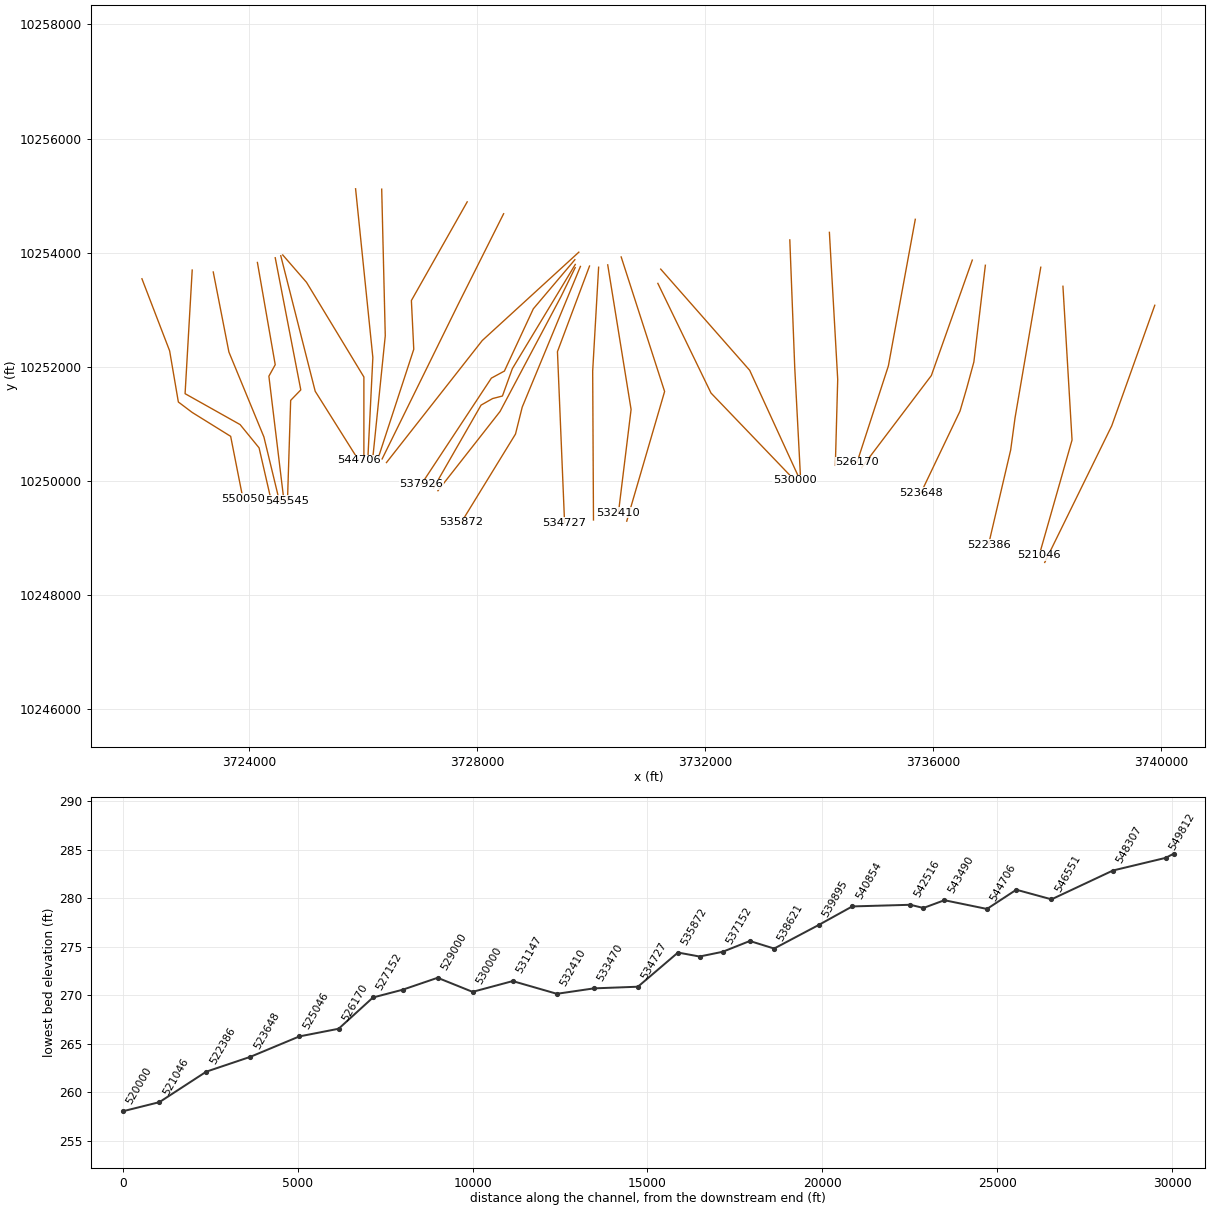
HEC-RAS study WFSJ Main.prj: WFSJ Main Base Level Engineering

--- WFSJ Main.g02 (geometry) --- (continued)

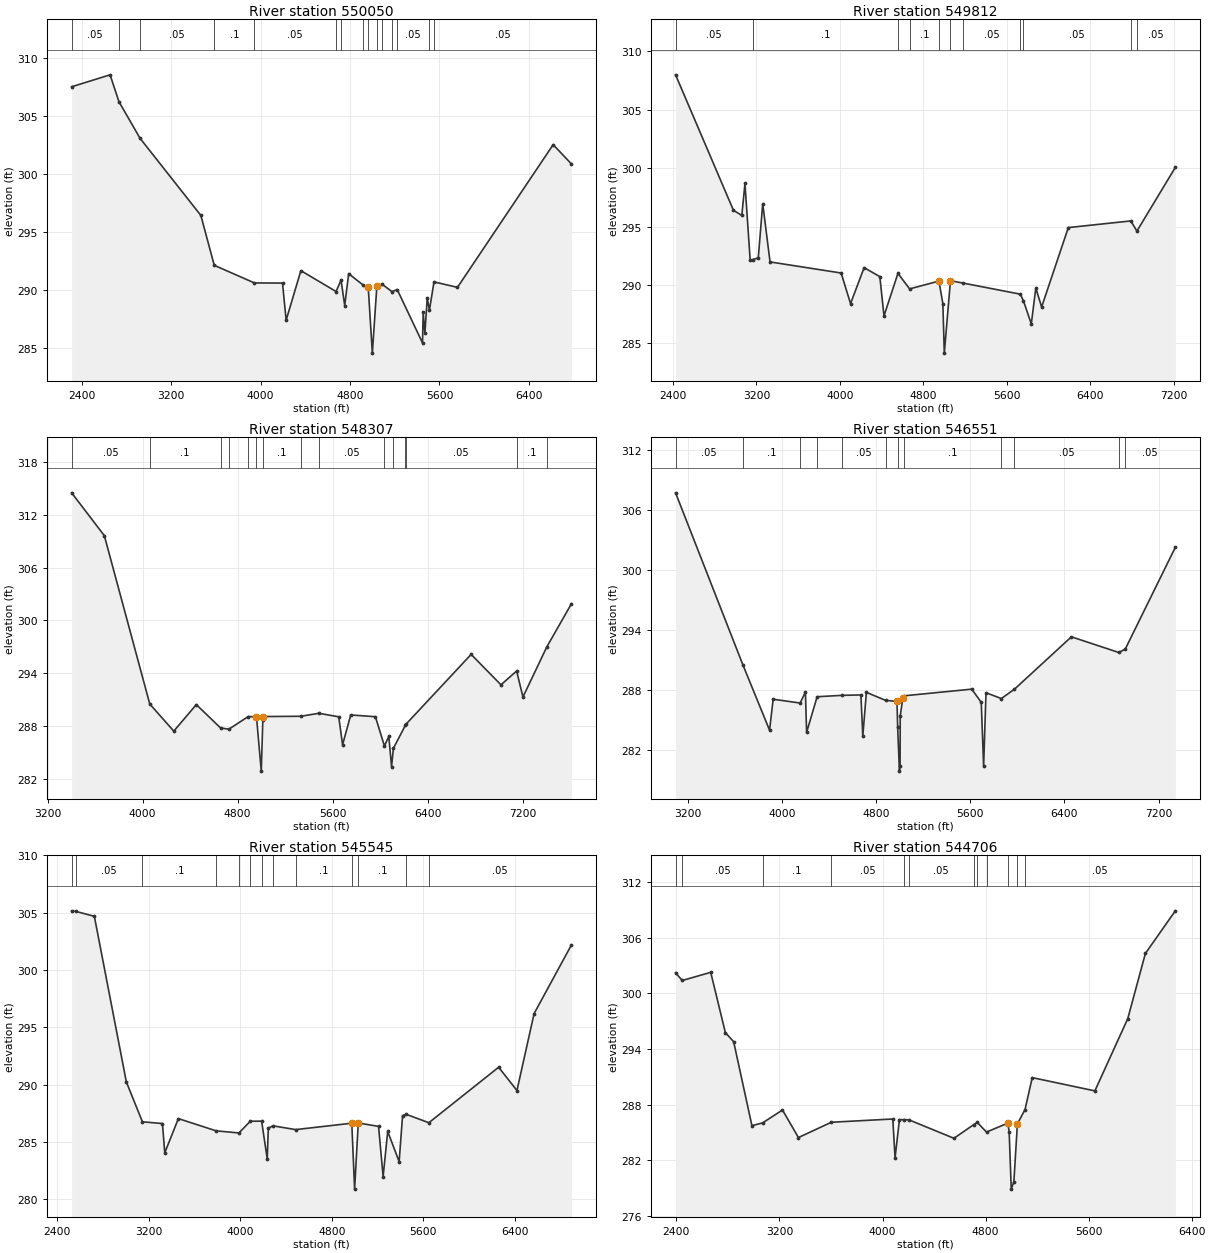
Type RM Length L Ch R = 1 ,550050  ,238,238,238
BEGIN DESCRIPTION:
WFSJ Main 541.0
END DESCRIPTION:
XS GIS Cut Line= 6
      3722116.67     10253542.08       3722602.8     10252278.16
      3722755.57     10251382.33      3722998.34     10251199.31
      3723673.25     10250780.48      3723888.31     10249690.88
#Sta/Elev= 30
  2308.9  307.56  2652.8  308.59  2731.8  306.28  2920.9  303.12    3465  296.47
  3584.9  292.17  3944.6  290.65  4195.7  290.64  4228.2  287.44  4360.1  291.71
    4675  289.91  4719.6  290.89  4752.3   288.7  4787.7  291.45  4918.2  290.46
  4962.9  290.26  4999.5   284.6  5040.1  290.39  5086.9  290.54  5175.1   289.9
  5222.1  290.08  5448.5  285.48  5454.4  288.11  5469.8  286.32    5491  289.37
  5510.1  288.29  5551.3  290.74  5761.3  290.27  6617.5  302.57  6780.8  300.91
#Mann= 15 ,-1 , 0
  2308.9     .05       0  2731.8     .12       0  2920.9     .05       0
  3584.9      .1       0  3944.6     .05       0    4675      .1       0
  4719.6     .05       0  4918.2      .1       0  4962.9     .07       0
  5040.1      .1       0  5086.9     .05       0  5175.1      .1       0
  5222.1     .05       0  5510.1      .1       0  5551.3     .05       0
Bank Sta=4962.9,5040.1
XS Rating Curve= 0 ,0
Exp/Cntr=0.3,0.1

Type RM Length L Ch R = 1 ,549812  ,1505,1505,1505
BEGIN DESCRIPTION:
WFSJ Main 540.0
END DESCRIPTION:
XS GIS Cut Line= 5
      3722998.63     10253694.79      3722873.63     10251528.16
      3723838.91     10250986.49      3724171.83     10250578.69
      3724392.55      10249619.1
#Sta/Elev= 30
  2424.7  307.99  2979.3  296.39  3059.5  295.95  3089.5  298.69  3139.6  292.11
    3164  292.17  3217.1  292.31  3259.8  296.96  3329.9  291.97  4011.1  291.02
  4101.2   288.4  4231.4  291.48  4381.7  290.71  4421.7  287.35  4555.4  290.99
  4667.3  289.66  4948.1  290.33  4985.7   288.4  4999.5  284.16  5058.5  290.36
  5177.7  290.16  5727.5  289.21    5758  288.64    5833  286.66  5876.1  289.73
  5932.1  288.11  6187.7  294.91  6786.3  295.48  6844.9  294.61  7212.9  300.06
#Mann= 11 ,-1 , 0
  2424.7     .05       0    3164      .1       0  4555.4     .05       0
  4667.3      .1       0  4948.1     .07       0  5058.5      .1       0
  5177.7     .05       0  5727.5      .1       0    5758     .05       0
  6786.3      .1       0  6844.9     .05       0
Bank Sta=4948.1,5058.5
XS Rating Curve= 0 ,0
Exp/Cntr=0.3,0.1

Type RM Length L Ch R = 1 ,548307  ,1756,1756,1756
BEGIN DESCRIPTION:
WFSJ Main 539.0
END DESCRIPTION:
XS GIS Cut Line= 4
      3723367.85     10253661.08      3723642.55     10252258.01
      3724256.38     10250770.16      3724531.07     10249634.52
#Sta/Elev= 30
  3403.1  314.52  3678.2  309.65  4060.7   290.5    4263  287.41  4452.7  290.43
  4656.9  287.77  4726.4  287.63  4890.3  289.07  4959.3  289.03  4999.5  282.86
  5012.6  288.64    5018  289.07  5332.6   289.1  5484.4  289.44  5651.7  289.04
  5684.1  285.86  5752.9  289.25  5960.5  289.05  6036.4  285.72  6073.5  286.81
  6096.4  283.38  6112.1  285.46  6213.5  288.09  6216.7  288.18  6766.5  296.14
  7017.5  292.68  7149.6  294.25  7202.7  291.29  7403.2  296.98  7610.7   301.9
#Mann= 15 ,-1 , 0
  3403.1     .05       0  4060.7      .1       0  4656.9     .12       0
  4726.4     .05       0  4890.3      .1       0  4959.3     .07       0
  5012.6      .1       0  5332.6     .12       0  5484.4     .05       0
  6036.4      .1       0  6112.1     .05       0  6213.5      .1       0
  6216.7     .05       0  7149.6      .1       0  7403.2     .05       0
Bank Sta=4959.3,5018
XS Rating Curve= 0 ,0
Exp/Cntr=0.3,0.1

Type RM Length L Ch R = 1 ,546551  ,1006,1006,1006
BEGIN DESCRIPTION:
WFSJ Main 538.0
END DESCRIPTION:
XS GIS Cut Line= 4
      3724142.54     10253827.47      3724455.05     10252035.79
      3724343.93      10251834.4      3724607.69     10249654.94
#Sta/Elev= 30
  3098.4  307.76  3671.2   290.5  3896.7  283.99  3927.1  287.09  4156.3  286.71
  4201.1   287.8  4211.4  283.78  4300.7  287.34  4514.6  287.48  4672.4  287.52
  4688.4  283.39  4718.9  287.78  4881.3  286.98  4978.8  286.87  4984.6  284.26
  4999.5  279.89    5005  280.39  5006.3  285.42  5028.1  287.17  5036.7  287.43
  5613.8   288.1  5694.4  286.78  5714.6  280.39  5734.7  287.74    5865  287.16
    5976  288.09    6460  293.34  6862.8  291.77  6917.3  292.11  7342.5   302.3
#Mann= 12 ,-1 , 0
  3098.4     .05       0  3671.2      .1       0  4156.3     .12       0
  4300.7      .1       0  4514.6     .05       0  4881.3      .1       0
  4984.6     .07       0  5036.7      .1       0    5865     .12       0
    5976     .05       0  6862.8      .1       0  6917.3     .05       0
Bank Sta=4978.8,5028.1
XS Rating Curve= 0 ,0
Exp/Cntr=0.3,0.1

Type RM Length L Ch R = 1 ,545545  ,839,839,839
BEGIN DESCRIPTION:
WFSJ Main 537.0
END DESCRIPTION:
XS GIS Cut Line= 4
      3724455.05     10253910.76      3724903.53     10251594.38
      3724725.88     10251410.79      3724670.36     10249654.93
#Sta/Elev= 30
  2524.4  305.15  2561.5   305.1    2723  304.67  3002.8  290.23  3143.4  286.75
  3318.6   286.6  3338.9  284.05  3457.9  287.03    3789  285.96  3987.7  285.78
    4087   286.8  4186.3  286.81  4235.3  283.51  4244.6   286.2  4285.7   286.4
  4484.3  286.07  4974.9  286.63  4999.5  280.88  5031.5  286.65    5209  286.35
    5249  281.97  5289.1  285.91  5389.1  283.28  5419.1  287.29  5452.1   287.4
  5648.9  286.67  6259.5  291.51  6419.6  289.48  6569.7  296.19    6896  302.17
#Mann= 13 ,-1 , 0
  2524.4     .12       0  2561.5     .05       0  3143.4      .1       0
    3789     .05       0  3987.7      .1       0    4087     .05       0
  4186.3      .1       0  4285.7     .05       0  4484.3      .1       0
  4974.9     .07       0  5031.5      .1       0  5452.1     .12       0
  5648.9     .05       0
Bank Sta=4974.9,5031.5
XS Rating Curve= 0 ,0
Exp/Cntr=0.3,0.1

Type RM Length L Ch R = 1 ,544706  ,1216,1216,1216
BEGIN DESCRIPTION:
WFSJ Main 536.0
END DESCRIPTION:
XS GIS Cut Line= 3
      3724552.26     10253945.56      3725156.43     10251570.51
      3725917.83     10250361.11
#Sta/Elev= 30
  2393.4  302.22  2445.3  301.39  2666.3  302.27  2779.8  295.78  2844.4  294.79
  2986.2  285.74  3069.2  286.04  3223.5  287.43  3347.3  284.46  3602.9  286.11
  4079.9  286.46  4097.4  282.28  4131.5  286.38  4163.1  286.39  4205.2  286.37
  4554.6  284.38  4707.1  285.84  4735.5  286.09  4807.5  285.05    4974  286.02
  4983.4  285.04  4999.5   278.9  5019.9   279.7    5047  285.92  5106.4  287.48
  5162.5  290.92  5648.7  289.49  5904.1  297.28  6040.7   304.3  6273.2   308.9
#Mann= 12 ,-1 , 0
  2393.4     .12       0  2445.3     .05       0  3069.2      .1       0
  3602.9     .05       0  4163.1      .1       0  4205.2     .05       0
  4707.1      .1       0  4735.5     .05       0  4807.5      .1       0
    4974     .07       0    5047      .1       0  5106.4     .05       0
Bank Sta=4974,5047
XS Rating Curve= 0 ,0
Exp/Cntr=0.3,0.1

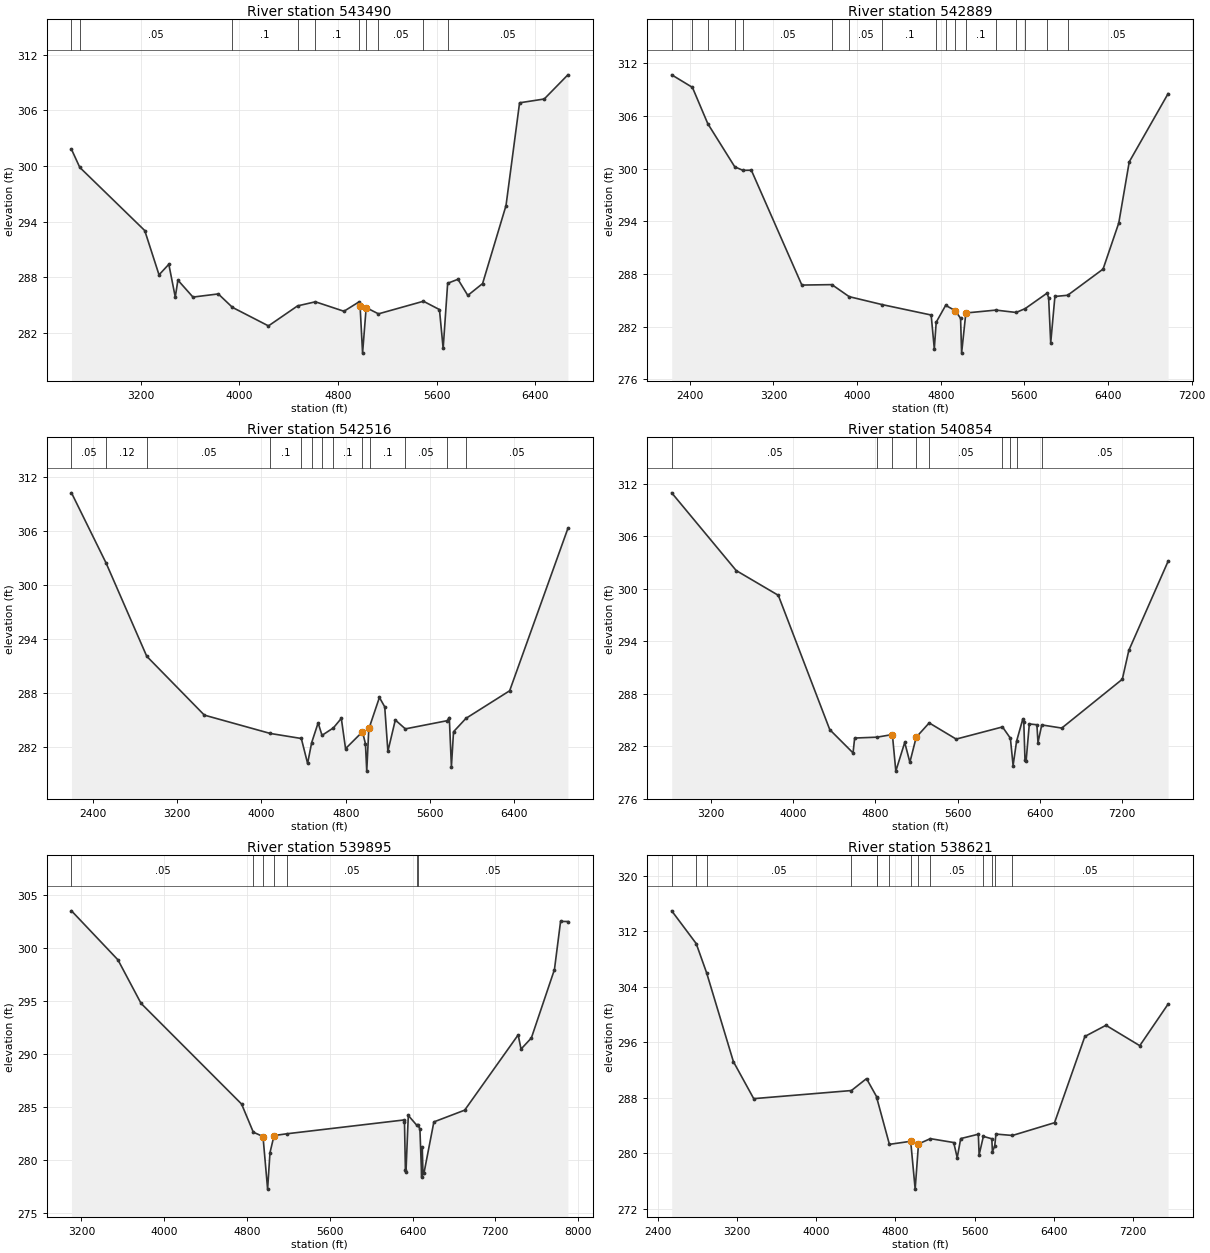
Type RM Length L Ch R = 1 ,543490  ,601,601,601
BEGIN DESCRIPTION:
WFSJ Main 535.0
END DESCRIPTION:
XS GIS Cut Line= 4
      3724586.99      10253959.4      3725003.66     10253480.24
       3726010.6     10251820.51       3726010.6     10250369.09
#Sta/Elev= 30
  2637.7   301.8  2704.9  299.85  3232.1  293.03    3348  288.25  3427.5  289.39
  3479.8  285.85  3501.1  287.68  3623.3  285.85  3828.8  286.19  3943.5  284.74
  4235.9  282.74  4472.2   284.9  4616.8  285.34  4848.5  284.32  4970.6  285.33
  4979.4  284.88  4999.5   279.8  5028.8  284.71  5128.5  284.04  5493.4   285.4
  5623.4   284.5  5653.4   280.3  5689.9  287.34  5773.4  287.77  5853.4  286.03
  5973.4  287.31  6163.4  295.73  6273.4  306.82  6473.4  307.23  6665.4  309.84
#Mann= 10 ,-1 , 0
  2637.7     .12       0  2704.9     .05       0  3943.5      .1       0
  4472.2     .05       0  4616.8      .1       0  4970.6     .07       0
  5028.8      .1       0  5128.5     .05       0  5493.4      .1       0
  5689.9     .05       0
Bank Sta=4979.4,5028.8
XS Rating Curve= 0 ,0
Exp/Cntr=0.3,0.1

Type RM Length L Ch R = 1 ,542889  ,373,373,373
BEGIN DESCRIPTION:
WFSJ Main 534.0
END DESCRIPTION:
XS GIS Cut Line= 3
      3725864.77     10255119.11      3726167.85     10252161.07
      3726080.05     10250389.97
#Sta/Elev= 30
  2227.3  310.69  2425.3  309.26  2572.3  305.13  2830.5  300.21  2909.1  299.81
  2988.8  299.83  3471.8  286.75  3759.1   286.8  3924.4  285.43  4241.6  284.52
  4708.3  283.34  4738.4   279.5  4756.6  282.52    4847  284.44  4939.5  283.83
  4989.7  282.96  4999.5     279    5040  283.57  5327.2   283.9    5521  283.63
  5607.4  284.07  5816.7  285.83  5831.6   285.3  5851.6  280.17  5891.7  285.45
  6013.8  285.59  6352.2  288.57  6502.4  293.82  6602.5  300.78  6974.1  308.55
#Mann= 17 ,-1 , 0
  2227.3     .05       0  2425.3     .12       0  2572.3     .05       0
  2830.5     .12       0  2909.1     .05       0  3759.1      .1       0
  3924.4     .05       0  4241.6      .1       0  4756.6     .05       0
    4847      .1       0  4939.5     .07       0    5040      .1       0
  5327.2     .05       0    5521      .1       0  5607.4     .05       0
  5816.7      .1       0  6013.8     .05       0
Bank Sta=4939.5,5040
XS Rating Curve= 0 ,0
Exp/Cntr=0.3,0.1

Type RM Length L Ch R = 1 ,542516  ,1662,1662,1662
BEGIN DESCRIPTION:
WFSJ Main 533.0
END DESCRIPTION:
XS GIS Cut Line= 3
       3726323.1     10255112.19       3726385.6     10252542.74
      3726167.85     10250411.04
#Sta/Elev= 30
  2196.1  310.29  2525.4  302.46  2910.5  292.11  3457.6  285.56  4083.8  283.52
  4378.3  282.96  4437.9  280.19  4476.5   282.5  4537.9   284.7  4574.7  283.31
  4682.7  284.14    4758   285.2  4798.3  281.83    4959  283.71  4987.1  282.37
  4999.5  279.33  5019.3  284.14  5029.3  284.38  5119.8  287.53  5170.1  286.48
  5200.2  281.53  5270.6  285.02  5365.9  284.03  5762.5  284.94  5783.2  285.29
  5803.3  279.83  5823.4  283.71  5941.3   285.2  6356.2  288.27  6909.1  306.33
#Mann= 13 ,-1 , 0
  2196.1     .05       0  2525.4     .12       0  2910.5     .05       0
  4083.8      .1       0  4378.3     .05       0  4476.5      .1       0
  4574.7     .05       0  4682.7      .1       0    4959     .07       0
  5029.3      .1       0  5365.9     .05       0  5762.5      .1       0
  5941.3     .05       0
Bank Sta=4959,5019.3
XS Rating Curve= 0 ,0
Exp/Cntr=0.3,0.1

Type RM Length L Ch R = 1 ,540854  ,959,959,959
BEGIN DESCRIPTION:
WFSJ Main 532.0
END DESCRIPTION:
XS GIS Cut Line= 4
      3727823.12     10254889.99      3726843.93     10253160.79
       3726885.6     10252306.63      3726267.55     10250417.74
#Sta/Elev= 30
  2818.9  310.96  3446.3  302.08  3856.1  299.25  4356.8   283.9  4583.4  281.24
  4598.9  282.94  4815.8  283.04    4966  283.34  4999.5  279.16  5086.1  282.44
  5136.2  280.17  5197.8  283.03  5324.2  284.67  5586.7  282.82  6037.4  284.21
  6114.1  282.92  6140.6   279.8  6174.1  282.56  6235.3  285.13  6244.7  284.72
  6256.3  280.39  6266.8  280.27  6298.4  284.55  6372.1  284.46  6382.7  282.42
  6419.3  284.44  6614.1  284.08  7203.3  289.66  7266.4  292.95  7648.7  303.14
#Mann= 9 ,-1 , 0
  2818.9     .05       0  4815.8      .1       0    4966     .07       0
  5197.8      .1       0  5324.2     .05       0  6037.4      .1       0
  6114.1     .05       0  6174.1      .1       0  6419.3     .05       0
Bank Sta=4966,5197.8
XS Rating Curve= 0 ,0
Exp/Cntr=0.3,0.1

Type RM Length L Ch R = 1 ,539895  ,1274,1274,1274
BEGIN DESCRIPTION:
WFSJ Main 531.0
END DESCRIPTION:
XS GIS Cut Line= 3
        3728462.     10254681.66      3727670.32     10253105.24
      3726330.81     10250384.56
#Sta/Elev= 30
  3104.4  303.54  3553.2  298.91  3776.5   294.8  4747.9  285.29  4861.3  282.63
    4955  282.22  4999.5  277.25  5022.4  280.69  5061.7  282.31  5186.1  282.48
  6314.1  283.78  6322.1  283.59    6331  279.03  6336.5  278.89    6359  284.21
  6442.1  283.27  6453.3  283.33  6471.3  282.89  6488.2   278.4  6493.8  281.22
  6500.5  278.79  6510.7  278.78  6606.1   283.6  6903.8  284.71  7420.5  291.82
  7448.5  290.48  7548.2  291.53  7771.1  297.99  7830.4  302.54    7901  302.53
#Mann= 7 ,-1 , 0
  3104.4     .05       0  4861.3      .1       0    4955     .07       0
  5061.7      .1       0  5186.1     .05       0  6442.1      .1       0
  6453.3     .05       0
Bank Sta=4955,5061.7
XS Rating Curve= 0 ,0
Exp/Cntr=0.3,0.1

Type RM Length L Ch R = 1 ,538621  ,695,695,695
BEGIN DESCRIPTION:
WFSJ Main 530.0
END DESCRIPTION:
XS GIS Cut Line= 3
      3729781.43     10254008.01      3728086.99      10252459.4
      3726406.45     10250320.53
#Sta/Elev= 30
  2539.6  314.96    2787  310.24  2892.8     306  3162.9  293.21  3368.3  287.87
  4355.4  289.04    4508  290.76  4609.3  288.17  4611.7  287.98  4739.3  281.28
  4954.4  281.72  4999.5  274.82  5033.1  281.34  5153.3   282.1  5389.1  281.54
  5424.4  279.35  5459.7  282.11  5637.7  282.74  5645.8  279.77  5688.6  282.43
  5774.1  282.08    5780  280.22  5803.3  281.03  5815.8  282.76  5982.7  282.56
  6407.7   284.4  6714.1  296.84  6927.4  298.45    7269  295.51  7555.2  301.51
#Mann= 14 ,-1 , 0
  2539.6     .05       0    2787     .12       0  2892.8     .05       0
  4355.4     .12       0  4609.3     .05       0  4611.7     .12       0
  4739.3      .1       0  4954.4     .07       0  5033.1      .1       0
  5153.3     .05       0  5688.6      .1       0    5780     .05       0
  5803.3      .1       0  5982.7     .05       0
Bank Sta=4954.4,5033.1
XS Rating Curve= 0 ,0
Exp/Cntr=0.3,0.1

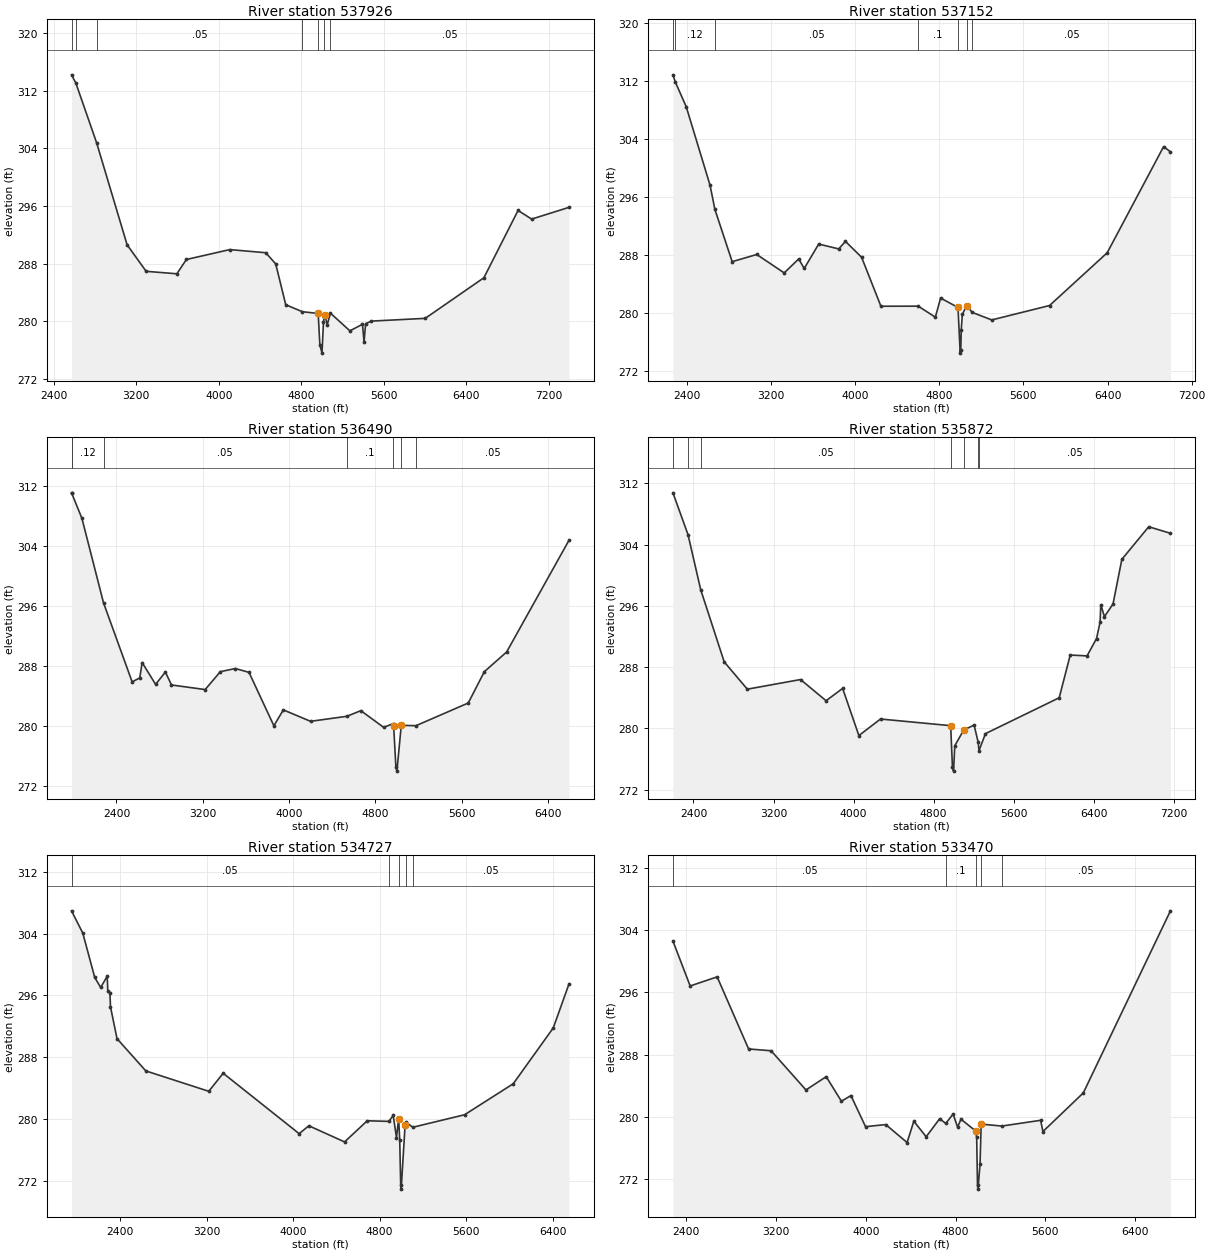
Type RM Length L Ch R = 1 ,537926  ,774,774,774
BEGIN DESCRIPTION:
WFSJ Main 529.0
END DESCRIPTION:
XS GIS Cut Line= 5
      3729711.99     10253876.07      3728982.82     10253014.96
      3728475.88     10251924.68       3728247.1     10251800.68
      3727017.53     10249938.55
#Sta/Elev= 30
  2571.7  314.18  2613.2  313.05  2814.5  304.77  3110.5  290.61    3295  286.94
  3592.7   286.6    3685  288.58    4105  289.95  4453.9  289.52  4550.9  287.97
    4648  282.31    4809  281.34  4962.6   281.1  4978.8  276.76  4999.5   275.6
  5013.9  279.95  5022.5  280.65  5028.2  280.88  5050.1  279.53  5081.6  281.14
    5270  278.69    5392   279.6  5407.1  277.12  5422.1  279.68  5479.3  280.04
  6000.1  280.42    6569  286.05  6900.1  295.38  7031.6  294.18  7394.1  295.81
#Mann= 7 ,-1 , 0
  2571.7     .05       0  2613.2     .12       0  2814.5     .05       0
    4809      .1       0  4962.6     .07       0  5022.5      .1       0
  5081.6     .05       0
Bank Sta=4962.6,5028.2
XS Rating Curve= 0 ,0
Exp/Cntr=0.3,0.1

Type RM Length L Ch R = 1 ,537152  ,662,662,662
BEGIN DESCRIPTION:
WFSJ Main 527.0
END DESCRIPTION:
XS GIS Cut Line= 6
      3729718.91      10253792.7      3728614.77     10251966.35
      3728441.16     10251487.18      3728268.47     10251442.55
      3728066.16     10251327.46      3727232.85     10249876.11
#Sta/Elev= 30
  2269.2  312.89  2292.2  311.88  2395.3  308.49  2621.7  297.66  2667.6  294.33
    2832  287.11  3065.7   288.1  3326.6  285.56  3464.4  287.49  3516.8  286.17
  3654.5  289.54  3844.7  288.87  3908.7  289.91    4062  287.72  4245.9  280.96
  4600.5  280.97  4763.3  279.45  4813.2  282.09  4978.4  280.79  4999.5  274.49
    5005  274.99  5009.4  277.73  5019.7  279.84    5061  281.05  5113.6  280.11
  5299.2  279.07  5848.8  281.06  6396.7  288.34    6933  302.99  6997.7  302.27
#Mann= 7 ,-1 , 0
  2269.2     .05       0  2292.2     .12       0  2667.6     .05       0
  4600.5      .1       0  4978.4     .07       0    5061      .1       0
  5113.6     .05       0
Bank Sta=4978.4,5061
XS Rating Curve= 0 ,0
Exp/Cntr=0.3,0.1

Type RM Length L Ch R = 1 ,536490  ,618,618,618
BEGIN DESCRIPTION:
WFSJ Main 528.0
END DESCRIPTION:
XS GIS Cut Line= 4
      3729717.84     10253737.43      3729468.93     10253230.24
      3728399.49     10251216.35      3727309.22     10249827.47
#Sta/Elev= 30
  1983.8  311.05  1984.6  311.03    2080  307.65  2280.1  296.41  2545.5  285.88
  2615.8  286.41  2638.4  288.45    2763  285.55  2853.5  287.19  2910.2  285.47
  3222.1  284.86  3363.1  287.24  3502.2  287.66  3628.5  287.15    3859  280.04
  3946.9  282.15  4199.4  280.63  4535.7   281.3  4665.1  282.05  4876.2  279.83
  4962.8   280.3  4969.3  280.01  4990.1   274.5  4999.5     274  5039.8  280.09
  5176.2  280.05  5660.7  283.07  5809.9  287.24  6016.8  289.87  6594.7  304.74
#Mann= 7 ,-1 , 0
  1983.8     .05       0  1984.6     .12       0  2280.1     .05       0
  4535.7      .1       0  4962.8     .07       0  5039.8      .1       0
  5176.2     .05       0
Bank Sta=4969.3,5039.8
XS Rating Curve= 0 ,0
Exp/Cntr=0.3,0.1

Type RM Length L Ch R = 1 ,535872  ,1145,1145,1145
BEGIN DESCRIPTION:
WFSJ Main 526.0
END DESCRIPTION:
XS GIS Cut Line= 4
      3729809.22     10253758.04      3728788.38     10251292.74
      3728670.32     10250820.51      3727718.92     10249271.87
#Sta/Elev= 30
    2195  310.78  2345.8   305.3  2472.1  298.13  2707.1  288.69  2938.3  285.12
  3470.3  286.38  3725.4  283.61    3891  285.22  4053.3  279.06  4269.8  281.22
  4970.9  280.35  4988.7  274.91  4999.5  274.41  5012.1  277.73  5102.1   279.8
  5205.2  280.42  5246.4  278.16  5253.7  277.08  5318.6  279.31  6055.8     284
  6165.9  289.58    6334  289.47  6428.7  291.73  6464.4  293.88  6471.3  296.15
    6508   294.6  6593.5  296.25    6682  302.09  6950.7  306.35  7167.6  305.49
#Mann= 7 ,-1 , 0
    2195     .05       0  2345.8     .12       0  2472.1     .05       0
  4970.9     .04       0  5102.1     .05       0  5246.4      .1       0
  5253.7     .05       0
Bank Sta=4970.9,5102.1
XS Rating Curve= 0 ,0
Exp/Cntr=0.3,0.1

Type RM Length L Ch R = 1 ,534727  ,1257,1257,1257
BEGIN DESCRIPTION:
WFSJ Main 525.0
END DESCRIPTION:
XS GIS Cut Line= 3
      3729968.92     10253764.93      3729406.43     10252264.96
      3729531.41     10249265.53
#Sta/Elev= 30
  1948.7  306.96  2052.9  304.07  2163.2  298.33  2218.4  297.03  2278.9  298.48
  2284.3  296.55  2303.8  296.37  2309.2  294.51  2369.7  290.39  2636.3  286.21
  3218.8  283.57  3351.9  285.91    4055  278.08  4145.1   279.1  4475.4  277.01
  4685.5  279.75  4885.7  279.67  4925.7  280.45  4955.8  277.58  4975.8  279.98
  4985.8   277.3    4995  271.39  4999.5  270.89  5035.8  279.25  5045.9  279.55
  5107.4  278.91  5586.3  280.53  6036.7  284.55    6407  291.79  6552.7   297.5
#Mann= 5 ,-1 , 0
  1948.7     .05       0  4885.7      .1       0  4975.8     .07       0
  5045.9      .1       0  5107.4     .05       0
Bank Sta=4975.8,5035.8
XS Rating Curve= 0 ,0
Exp/Cntr=0.3,0.1

Type RM Length L Ch R = 1 ,533470  ,1060,1060,1060
BEGIN DESCRIPTION:
WFSJ Main 524.0
END DESCRIPTION:
XS GIS Cut Line= 3
      3730128.66     10253744.11      3730024.49     10251924.68
      3730038.37     10249314.83
#Sta/Elev= 30
  2281.7  302.61    2435  296.84  2675.4  298.01  2955.8  288.74  3156.2  288.51
  3466.7  283.47    3647  285.18  3782.5  282.02  3867.3  282.75  3997.5  278.75
  4177.7  279.02  4367.7  276.71  4427.7  279.45  4537.7  277.45  4657.7  279.77
  4712.3  279.17  4777.7  280.37  4817.7  278.69  4847.7  279.71  4977.7  278.21
  4987.7  277.38    4995  271.22  4999.5  270.72  5017.7  273.94  5027.7  279.08
  5211.9  278.83  5557.7  279.57  5577.7  278.12  5937.7  283.09    6714   306.5
#Mann= 5 ,-1 , 0
  2281.7     .05       0  4712.3      .1       0  4977.7     .07       0
  5027.7      .1       0  5211.9     .05       0
Bank Sta=4977.7,5027.7
XS Rating Curve= 0 ,0
Exp/Cntr=0.3,0.1

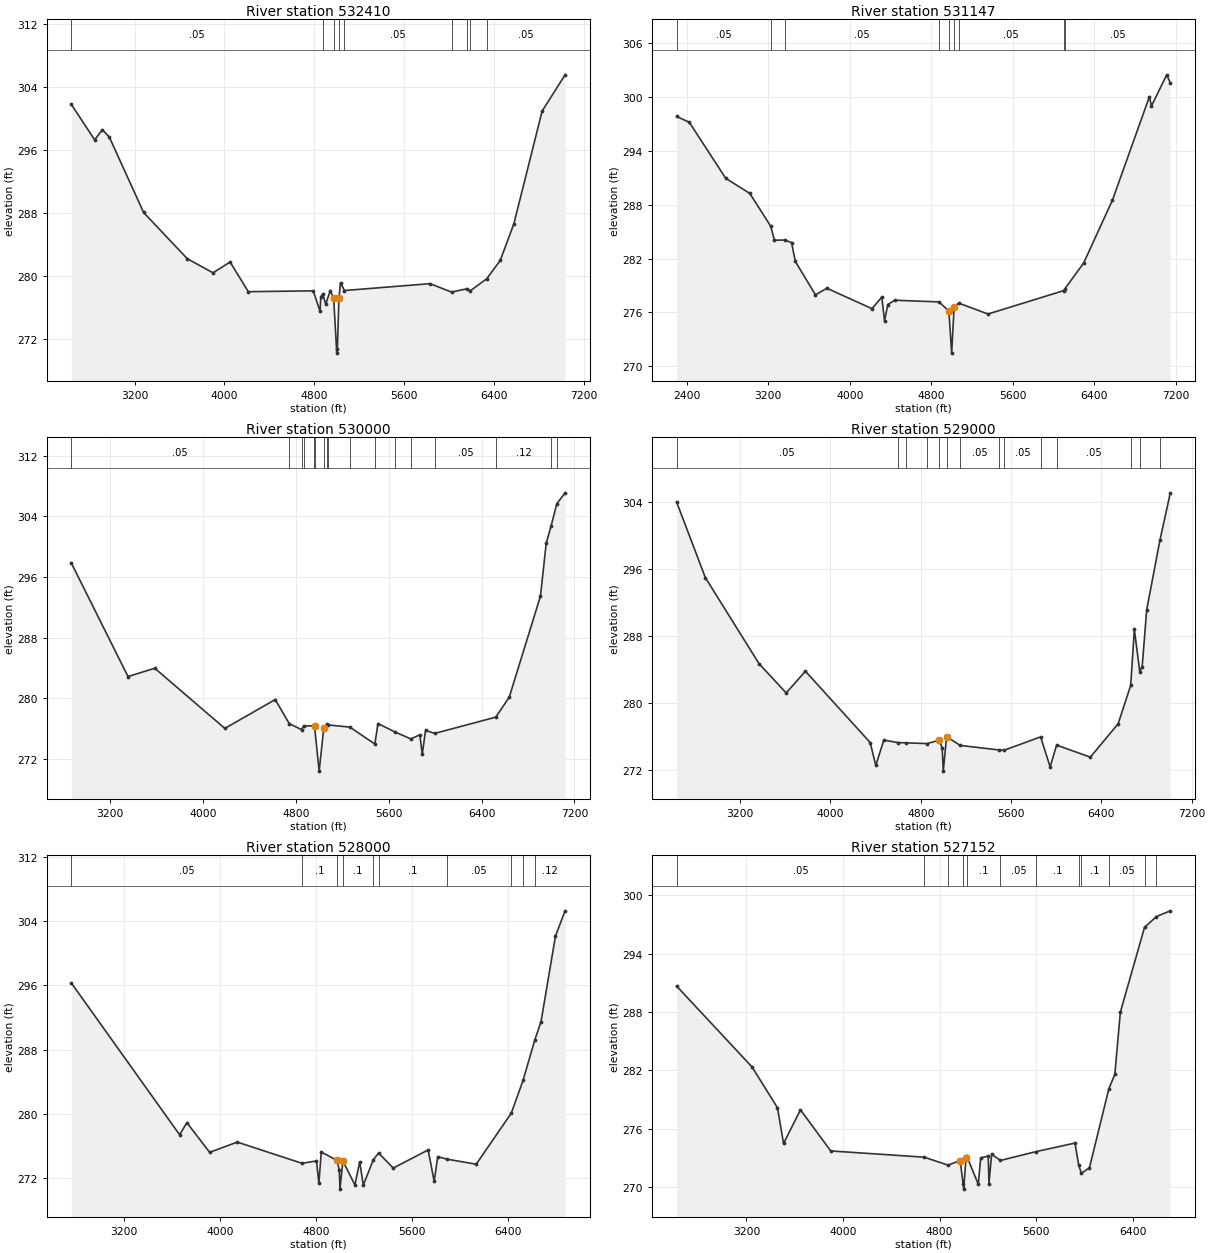
Type RM Length L Ch R = 1 ,532410  ,1263,1263,1263
BEGIN DESCRIPTION:
WFSJ Main 523.0
END DESCRIPTION:
XS GIS Cut Line= 3
      3730288.38      10253785.8       3730698.1     10251251.07
      3730475.88     10249438.58
#Sta/Elev= 30
  2637.7  301.78  2845.1  297.27  2913.7  298.57  2975.4  297.63  3280.7  288.04
  3669.5  282.16  3898.6  280.37  4050.5  281.74  4212.6  277.97    4790  278.08
  4850.8  275.49  4857.5  277.35  4875.9  277.64  4901.4  276.38    4942  278.12
  4972.3  277.12  4999.5  270.16    5005  270.66 5018.73  277.13  5033.1   279.1
  5068.3  278.12    5830  278.99  6021.2  277.92    6163  278.36  6185.5  278.06
  6335.4  279.63  6454.6  281.95  6575.5  286.59  6827.4  300.94  7031.4  305.54
#Mann= 9 ,-1 , 0
  2637.7     .05       0  4875.9      .1       0  4972.3     .07       0
 5018.73      .1       0  5068.3     .05       0  6021.2     .12       0
    6163     .05       0  6185.5     .12       0  6335.4     .05       0
Bank Sta=4972.3,5018.73
XS Rating Curve= 0 ,0
Exp/Cntr=0.3,0.1

Type RM Length L Ch R = 1 ,531147  ,1147,1147,1147
BEGIN DESCRIPTION:
WFSJ Main 522.0
END DESCRIPTION:
XS GIS Cut Line= 3
       3730524.5     10253924.64      3731286.24     10251566.31
      3730622.19     10249294.36
#Sta/Elev= 30
  2300.1  297.86  2424.8  297.21  2782.4  290.96  3018.4  289.28  3224.9   285.6
  3260.1  284.06  3360.8  284.08  3428.2   283.8  3465.5  281.69    3663  277.97
  3775.1   278.7    4218  276.43  4314.1  277.72  4340.9  275.06  4372.9  276.89
  4442.2  277.37  4875.4  277.18  4972.6  276.16  4999.5  271.47  5023.5  276.57
  5068.3  277.05  5356.2  275.83  6099.7  278.44  6107.9   278.6  6294.5  281.51
  6576.9  288.51  6940.5  300.07  6960.4  299.02  7109.9   302.5  7145.4  301.61
#Mann= 9 ,-1 , 0
  2300.1     .05       0  3224.9     .12       0  3360.8     .05       0
  4875.4     .12       0  4972.6     .07       0  5023.5     .12       0
  5068.3     .05       0  6099.7     .12       0  6107.9     .05       0
Bank Sta=4972.6,5023.5
XS Rating Curve= 0 ,0
Exp/Cntr=0.3,0.1

Type RM Length L Ch R = 1 ,530000  ,1000,1000,1000
BEGIN DESCRIPTION:
WFSJ Main 521.0
END DESCRIPTION:
XS GIS Cut Line= 3
      3731167.85     10253461.07      3732100.31     10251539.35
      3733567.85     10250011.07
#Sta/Elev= 30
    2864  297.83    3352  282.85  3583.2  283.94  4186.7     276  4621.1  279.81
  4741.4  276.64  4848.6  275.83  4865.7  276.32  4955.7  276.35  4959.6  276.26
  4999.5  270.36  5039.3  276.04  5067.3  276.61  5077.1  276.46  5264.1  276.17
  5479.7  273.94  5506.3  276.64    5655  275.52  5789.8  274.61    5867  275.16
  5888.1   272.6  5916.4  275.74  5996.4  275.34  6521.8  277.49  6637.8  280.13
  6906.7  293.46  6956.1  300.44  6998.1   302.7  7047.1  305.64  7118.8   307.1
#Mann= 17 ,-1 , 0
    2864     .05       0  4741.4     .12       0  4848.6      .1       0
  4865.7     .05       0  4955.7      .1       0  4959.6     .07       0
  5039.3      .1       0  5067.3     .05       0  5077.1      .1       0
  5264.1     .05       0  5479.7      .1       0    5655     .05       0
  5789.8      .1       0  5996.4     .05       0  6521.8     .12       0
  6998.1     .05       0  7047.1     .12       0
Bank Sta=4959.6,5039.3
XS Rating Curve= 0 ,0
Exp/Cntr=0.3,0.1

Type RM Length L Ch R = 1 ,529000  ,1000,1000,1000
BEGIN DESCRIPTION:
WFSJ Main 520.0
END DESCRIPTION:
XS GIS Cut Line= 3
      3731217.87     10253711.05      3732778.68     10251937.97
      3733617.85     10250111.08
#Sta/Elev= 30
  2637.8  303.97  2892.5  294.93  3367.8  284.65  3608.8  281.15  3778.6  283.75
  4352.6  275.22    4402  272.49  4473.1  275.52  4597.9  275.22  4668.1  275.19
  4857.5   275.1  4961.7   275.5  4990.2   274.6  4999.5  271.81    5029  275.93
  5149.6  274.88  5492.8  274.34  5541.1  274.32  5861.6   275.9  5946.4  272.31
  6003.1  274.92  6302.1  273.48  6548.5  277.47  6659.6  282.06  6691.9  288.74
  6739.8   283.7  6760.8  284.24  6801.3  291.09  6917.9  299.37  7010.4  305.06
#Mann= 14 ,-1 , 0
  2637.8     .05       0  4597.9     .12       0  4668.1     .05       0
  4857.5      .1       0  4961.7     .07       0    5029      .1       0
  5149.6     .05       0  5492.8      .1       0  5541.1     .05       0
  5861.6      .1       0  6003.1     .05       0  6659.6     .12       0
  6739.8     .05       0  6917.9     .12       0
Bank Sta=4961.7,5029
XS Rating Curve= 0 ,0
Exp/Cntr=0.3,0.1

Type RM Length L Ch R = 1 ,528000  ,848,848,848
BEGIN DESCRIPTION:
WFSJ Main 519.0
END DESCRIPTION:
XS GIS Cut Line= 3
      3733482.82     10254223.33       3733569.3       10251985.
      3733667.85     10250111.08
#Sta/Elev= 30
    2760   296.3  3662.9  277.36    3723  278.88  3913.1  275.17  4143.3  276.45
  4682.9   273.8  4803.8   274.1  4823.8  271.31  4843.8  275.21  4973.9  274.18
  4993.9  272.99  4999.5  270.58    5024  274.11  5124.1   271.1  5164.2  273.99
  5194.2  271.08  5278.3  274.26  5321.4  275.08    5444  273.21  5734.9  275.47
    5785  271.56    5815  274.64  5891.5  274.32  6135.5  273.69  6428.1  280.06
  6526.3  284.15  6624.4  289.21  6676.2  291.49  6796.4  302.15  6876.5  305.31
#Mann= 10 ,-1 , 0
    2760     .05       0  4682.9      .1       0  4973.9     .07       0
    5024      .1       0  5278.3     .05       0  5321.4      .1       0
  5891.5     .05       0  6428.1      .1       0  6526.3     .05       0
  6624.4     .12       0
Bank Sta=4973.9,5024
XS Rating Curve= 0 ,0
Exp/Cntr=0.3,0.1

Type RM Length L Ch R = 1 ,527152  ,982,982,982
BEGIN DESCRIPTION:
WFSJ Main 518.0
END DESCRIPTION:
XS GIS Cut Line= 3
      3734177.27     10254355.27       3734323.1     10251778.85
      3734281.43     10250271.87
#Sta/Elev= 30
  2622.1  290.68    3247  282.35  3457.6  278.15  3507.7  274.48  3647.9  277.94
  3898.3  273.71  4671.3  273.07  4869.4  272.25  4970.1  272.72    4995  270.28
  4999.5  269.78  5018.2  272.99  5023.2  273.22  5120.3  270.28  5140.3     273
  5202.6  273.18  5208.5  270.34  5230.4  273.37  5303.9  272.73  5601.3  273.65
  5920.7  274.52    5952  272.22  5974.1  271.41  6040.7  271.98  6201.4  280.11
  6250.8  281.59  6296.5  287.99  6496.5  296.71  6594.9  297.83  6710.2  298.42
#Mann= 12 ,-1 , 0
  2622.1     .05       0  4671.3      .1       0  4869.4     .05       0
    4995     .05       0  5023.2      .1       0  5303.9     .05       0
  5601.3      .1       0    5952     .05       0  5974.1      .1       0
  6201.4     .05       0  6496.5      .1       0  6594.9     .05       0
#XS Ineff= 1 ,-1
    3430  3647.9  277.94
Permanent Ineff=
       F
Bank Sta=4970.1,5018.2
XS Rating Curve= 0 ,0
Exp/Cntr=0.3,0.1

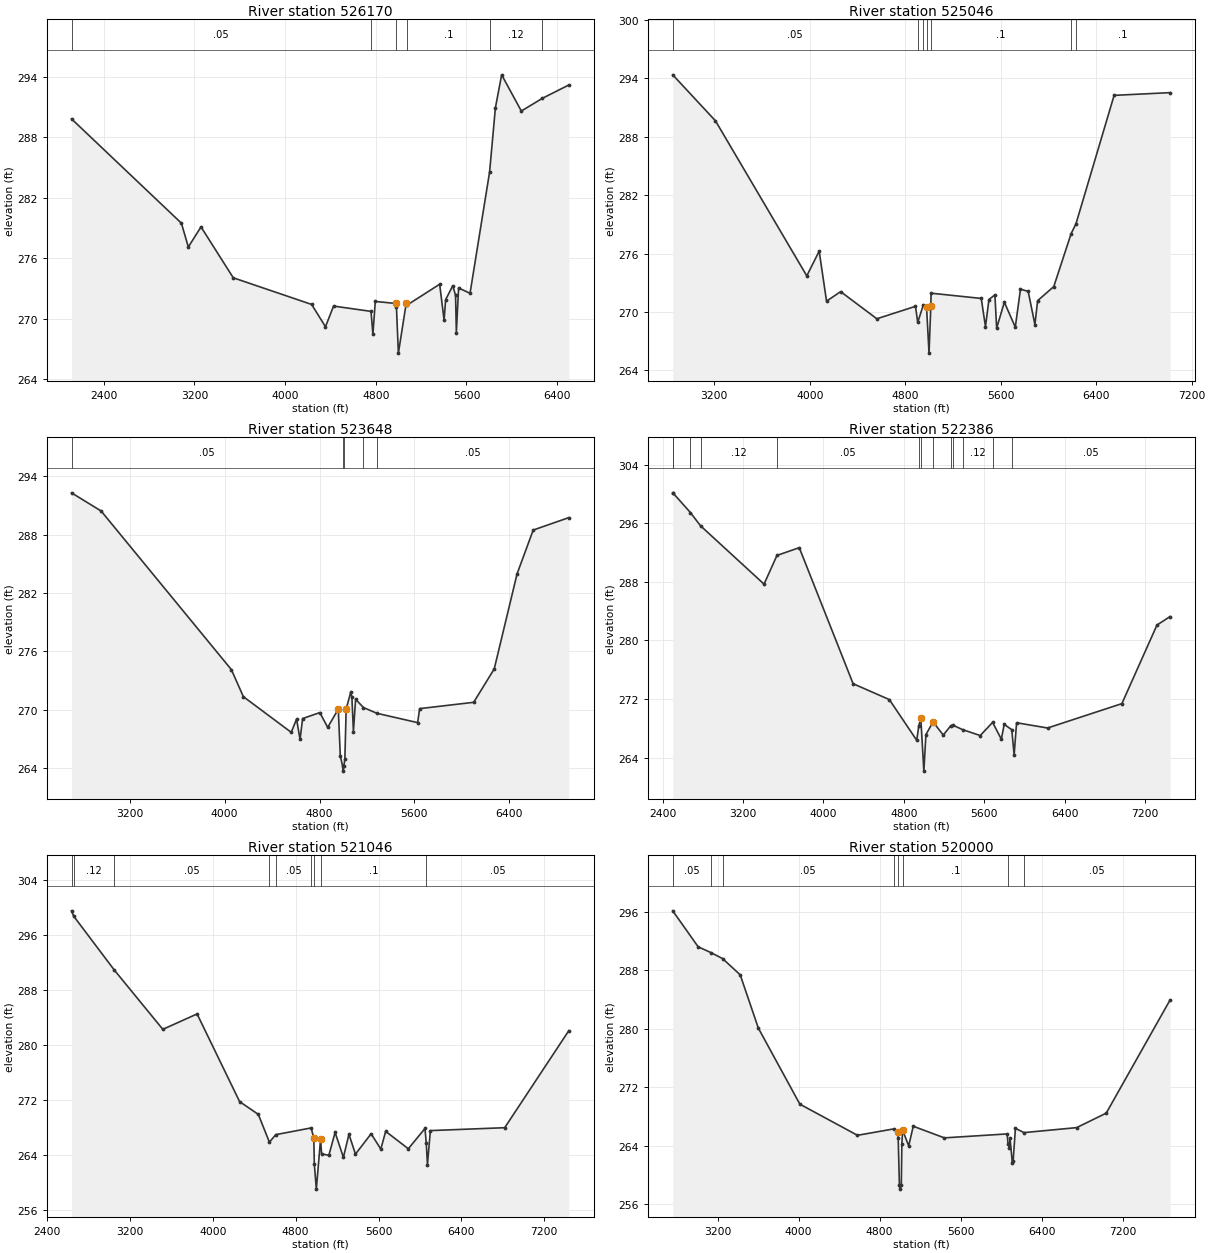
Type RM Length L Ch R = 1 ,526170  ,1124,1124,1124
BEGIN DESCRIPTION:
WFSJ Main 517.0
END DESCRIPTION:
XS GIS Cut Line= 3
      3735684.21     10254584.39      3735211.99     10252014.96
      3734663.38     10250327.46
#Sta/Elev= 30
  2116.1  289.85  3085.4  279.48  3146.4  277.11  3258.2  279.11  3542.9  274.05
  4234.3   271.4  4356.3  269.18  4427.5  271.24    4758  270.71  4774.7  268.43
  4795.7   271.7  4974.5   271.5  4982.1  271.19  4999.5  266.56  5069.1  271.56
    5078  271.35  5363.6  273.41  5402.7  269.83  5416.1  271.87  5479.2  273.26
  5503.8   272.3  5510.8   268.6  5530.5  273.04  5631.6  272.51  5804.1  284.57
  5855.2  290.95  5910.4  294.23    6084  290.63  6270.6   291.9    6503  293.22
#Mann= 6 ,-1 , 0
  2116.1     .05       0    4758      .1       0  4982.1     .05       0
    5078      .1       0  5804.1     .12       0  6270.6      .1       0
Bank Sta=4974.5,5069.1
XS Rating Curve= 0 ,0
Exp/Cntr=0.3,0.1

Type RM Length L Ch R = 1 ,525046  ,1398,1398,1398
BEGIN DESCRIPTION:
WFSJ Main 516.0
END DESCRIPTION:
XS GIS Cut Line= 3
      3736684.23     10253869.16      3735965.81     10251845.71
      3734746.72     10250237.19
#Sta/Elev= 30
  2852.8  294.37  3210.9  289.64  3975.6  273.71  4079.4  276.25  4141.1  271.11
  4259.2  272.09  4562.5   269.3  4886.1  270.58  4904.8  268.93  4951.3   270.7
  4978.7  270.53  4999.5  265.77 5014.59  270.58  5016.8  271.93    5437  271.39
  5472.4  268.49  5501.5  271.28  5551.4  271.76    5566  268.34  5630.5     271
  5722.1  268.44  5765.7  272.35  5830.2  272.11  5886.4  268.71  5909.2  271.16
  6044.5  272.61  6190.2  278.06  6230.4  279.06    6550  292.26  7018.3  292.54
#Mann= 7 ,-1 , 0
  2852.8     .05       0  4904.8     .12       0  4951.3      .1       0
  4978.7     .07       0 5014.59      .1       0  6190.2     .05       0
  6230.4      .1       0
Bank Sta=4978.7,5014.59
XS Rating Curve= 0 ,0
Exp/Cntr=0.3,0.1

Type RM Length L Ch R = 1 ,523648  ,1262,1262,1262
BEGIN DESCRIPTION:
WFSJ Main 515.0
END DESCRIPTION:
XS GIS Cut Line= 5
      3736913.37     10253778.82      3736711.99      10252084.4
      3736586.99     10251626.07      3736468.93     10251223.29
       3735782.2      10249787.4
#Sta/Elev= 30
  2708.9   292.3  2958.4  290.43  4056.1  274.12  4157.8  271.33  4561.3  267.66
  4606.2  269.02  4635.6  266.93  4657.1  269.08  4802.2  269.69  4868.8  268.17
    4958  270.05  4974.9  265.24    4995  264.17  4999.5  263.67    5005  264.17
  5013.5  264.96 5024.47  270.07  5062.3  271.76  5072.7   271.3  5085.5  267.74
  5103.9  271.06  5170.5  270.21  5283.5  269.62  5626.9  268.66  5644.1   270.1
  6099.5  270.75  6272.9  274.19  6465.3  283.96  6601.4  288.47  6901.7  289.75
#Mann= 5 ,-1 , 0
  2708.9     .05       0    4995     .05       0    5005     .05       0
  5170.5      .1       0  5283.5     .05       0
Bank Sta=4958,5024.47
XS Rating Curve= 0 ,0
Exp/Cntr=0.3,0.1

Type RM Length L Ch R = 1 ,522386  ,1340,1340,1340
BEGIN DESCRIPTION:
WFSJ Main 514.0
END DESCRIPTION:
XS GIS Cut Line= 4
       3737885.6     10253744.14      3737434.21     10251105.24
      3737357.82     10250542.74      3736969.29     10248884.54
#Sta/Elev= 30
  2500.9  300.15  2502.1  300.15  2677.1  297.45  2777.4  295.65  3409.4  287.68
    3538   291.6  3759.8  292.66  4295.6  274.08  4656.1  271.91  4928.7  266.35
    4949  268.33  4969.3  269.34  4999.5  262.14    5020  267.14    5091  268.85
  5192.9  267.07  5265.3  268.31    5285  268.44  5384.6  267.81  5560.3     267
  5683.6   268.8  5770.4   266.5  5798.9  268.53    5874   267.8  5897.8  264.37
  5922.1  268.75  6230.2  268.03  6969.7  271.36  7318.9  282.09  7448.9  283.25
#Mann= 13 ,-1 , 0
  2500.9     .05       0  2502.1     .12       0  2677.1     .05       0
  2777.4     .12       0    3538     .05       0    4949     .12       0
  4969.3     .07       0    5091     .12       0  5265.3     .12       0
    5285     .05       0  5384.6     .12       0  5683.6      .1       0
    5874     .05       0
Bank Sta=4969.3,5091
XS Rating Curve= 0 ,0
Exp/Cntr=0.3,0.1

Type RM Length L Ch R = 1 ,521046  ,1046,1046,1046
BEGIN DESCRIPTION:
WFSJ Main 513.0
END DESCRIPTION:
XS GIS Cut Line= 3
      3738274.49      10253410.8      3738434.21     10250716.35
      3737857.91     10248695.81
#Sta/Elev= 30
  2636.5  299.46  2657.1  298.69  3049.9  290.84  3517.8  282.23  3848.4  284.47
  4259.1  271.72  4439.4  269.87  4546.4  265.83  4608.1  266.92  4949.9   267.9
    4975  266.41  4980.3  262.62  4999.5     259  5040.4  266.27  5050.5  264.11
  5120.6  263.93  5180.7  267.24  5260.8  263.62  5314.3  266.97  5377.3  264.09
  5528.4  267.05  5621.9  264.82  5668.8   267.4  5887.3  264.87  6048.3  267.82
  6060.6  265.72  6072.1  262.57  6100.3  267.51  6817.8  267.93  7436.8  282.04
#Mann= 9 ,-1 , 0
  2636.5     .05       0  2657.1     .12       0  3049.9     .05       0
  4546.4      .1       0  4608.1     .05       0  4949.9      .1       0
    4975     .07       0  5040.4      .1       0  6060.6     .05       0
Bank Sta=4975,5040.4
XS Rating Curve= 0 ,0
Exp/Cntr=0.3,0.1

Type RM Length L Ch R = 1 ,520000  ,1000,1000,1000
BEGIN DESCRIPTION:
WFSJ Main 512.0
END DESCRIPTION:
XS GIS Cut Line= 3
      3739885.59     10253077.44      3739130.44     10250964.74
      3737955.04      10248570.5
#Sta/Elev= 30
  2756.4  296.12  3007.5   291.2  3131.7  290.42  3248.6  289.59  3422.5  287.37
  3602.1  280.07  4011.7  269.68  4580.7  265.42  4940.2   266.3  4977.9  265.87
  4982.7   265.1    4995  258.56  4999.5  258.06  5013.4  258.56    5019  264.24
  5026.4  266.14  5086.5  263.97  5131.4  266.66  5438.6  265.07  6058.9  265.61
  6067.2   264.3  6081.4  263.66    6087  265.09  6109.5  261.68  6118.1  261.96
  6140.4  266.38  6224.4  265.79  6744.7  266.47    7037  268.45  7667.2  283.92
#Mann= 8 ,-1 , 0
  2756.4     .05       0  3131.7     .12       0  3248.6     .05       0
  4940.2      .1       0  4977.9     .07       0  5026.4      .1       0
  6067.2     .12       0  6224.4     .05       0
Bank Sta=4977.9,5026.4
XS Rating Curve= 0 ,0
Exp/Cntr=0.3,0.1