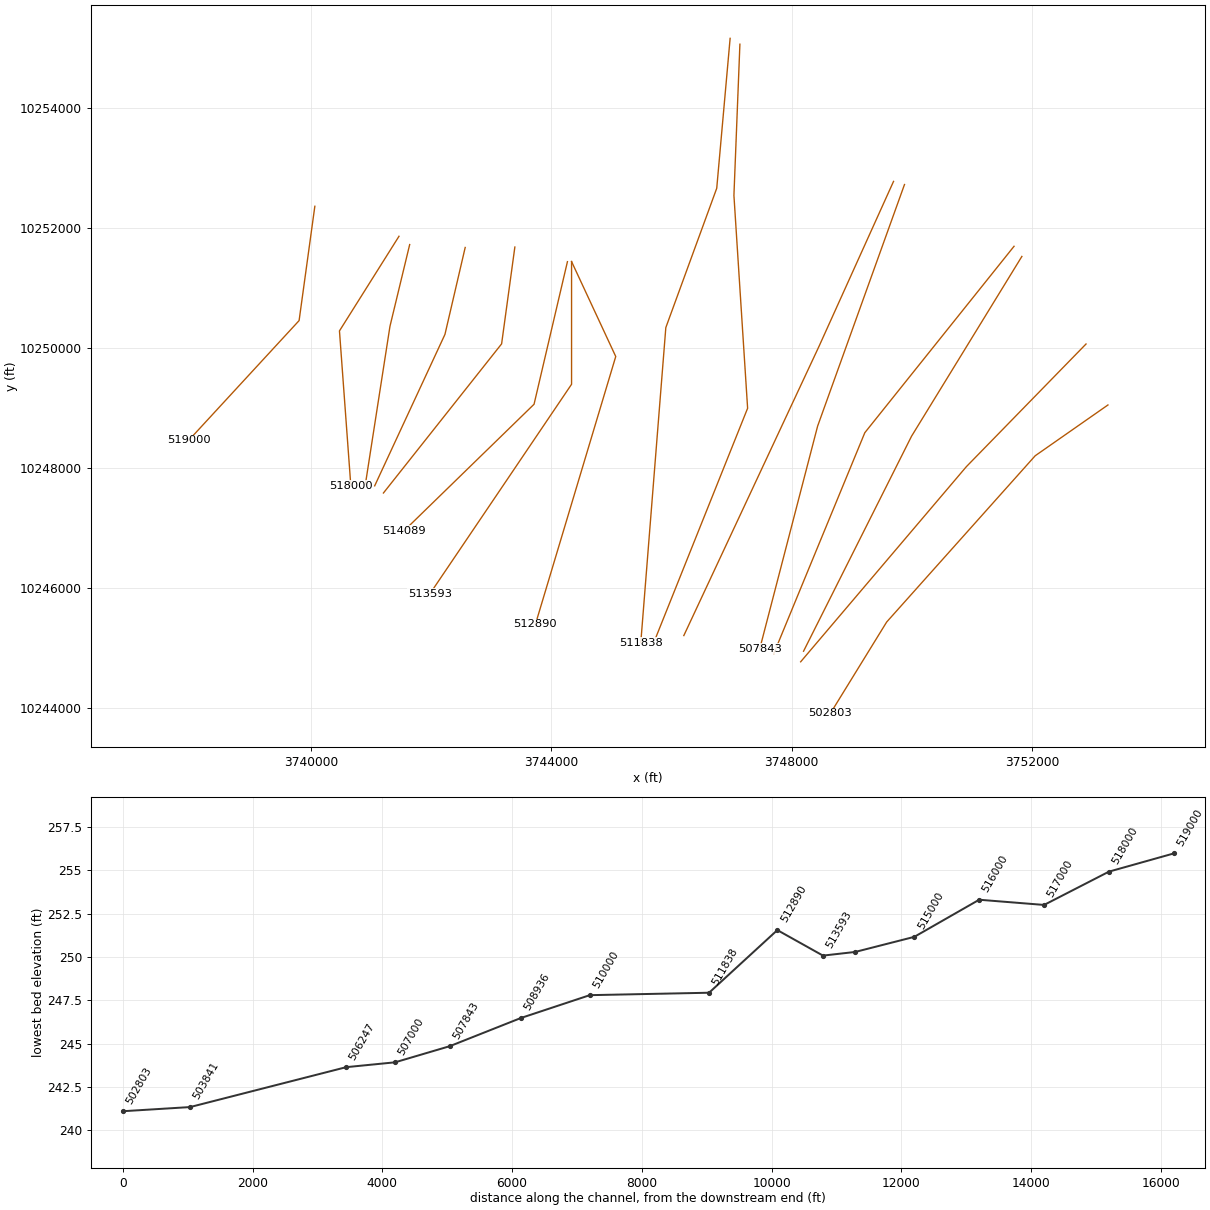
HEC-RAS study WFSJ Main.prj: WFSJ Main Base Level Engineering

--- WFSJ Main.g02 (geometry) --- (continued)

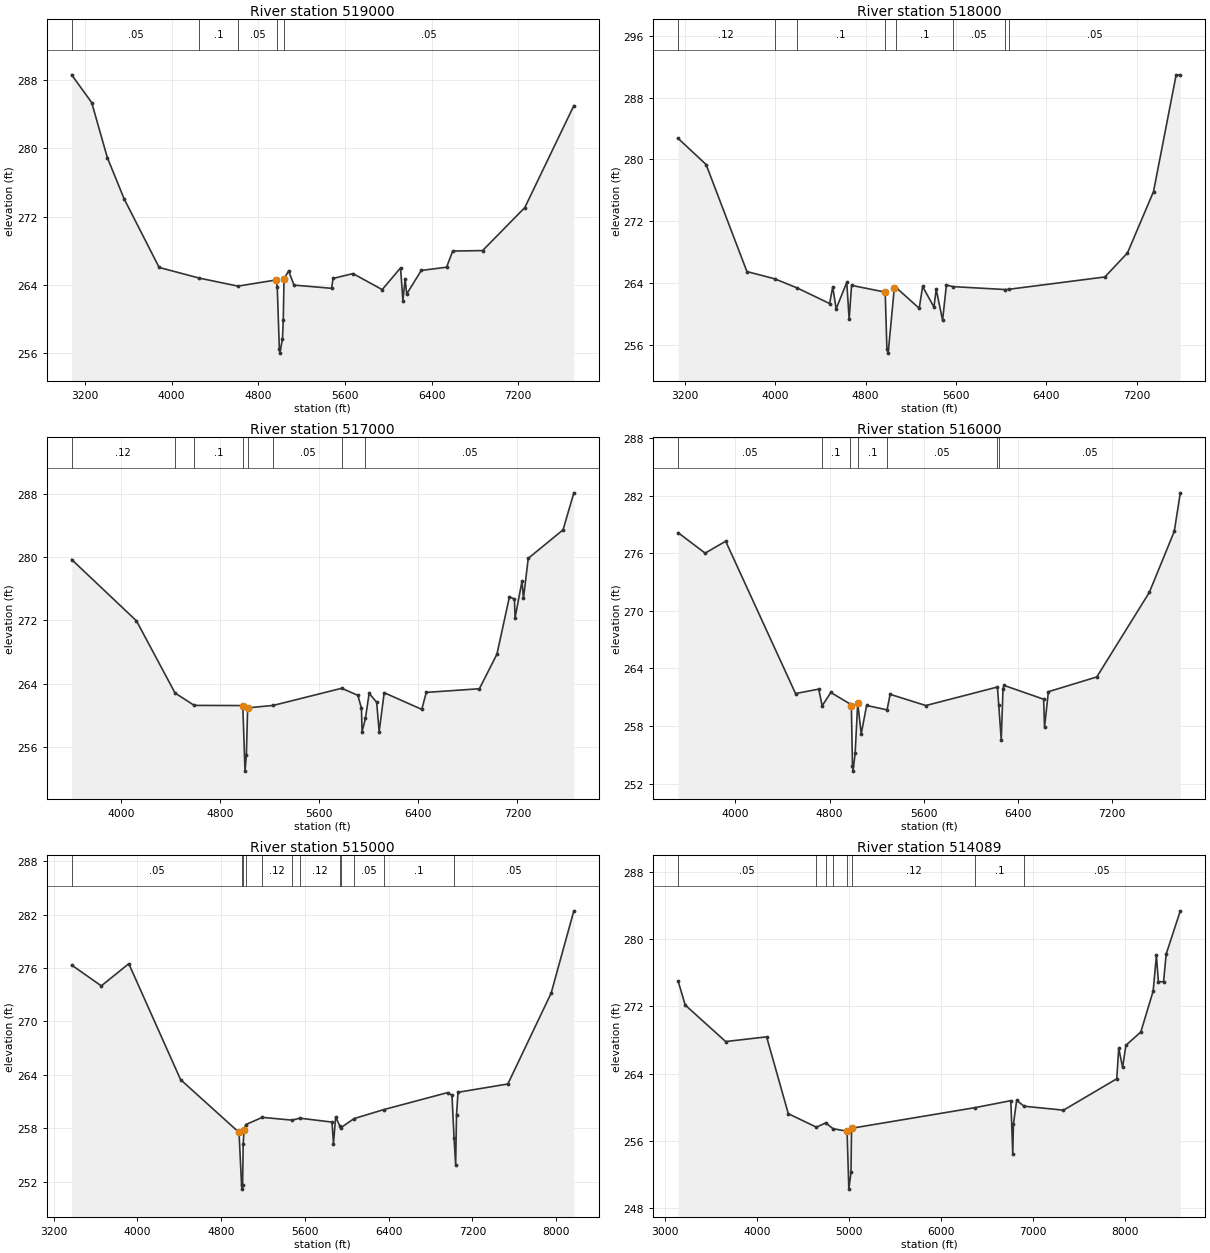
Type RM Length L Ch R = 1 ,519000  ,1000,1000,1000
BEGIN DESCRIPTION:
WFSJ Main 511.0
END DESCRIPTION:
XS GIS Cut Line= 3
      3740067.86     10252361.11      3739805.86     10250456.85
      3737967.85     10248461.07
#Sta/Elev= 30
  3077.8  288.65  3262.9  285.39    3407  278.94  3562.4  274.08  3885.4  266.03
  4256.3  264.78  4612.6  263.84  4965.5  264.56  4975.6  263.75    4995  256.47
  4999.5  255.97  5023.7  257.65  5031.1  259.88  5037.9  264.69  5080.4  265.63
  5130.2  263.96  5476.8  263.58    5491  264.74  5674.8  265.31  5944.1  263.43
  6113.7  265.98  6135.3  262.14  6156.2  264.69  6170.4  262.91  6304.8  265.68
  6538.5  266.06  6595.2  267.96  6870.8  268.01  7260.4  273.06  7713.2  285.03
#Mann= 5 ,-1 , 0
  3077.8     .05       0  4256.3      .1       0  4612.6     .05       0
  4975.6     .03       0  5037.9     .05       0
Bank Sta=4965.5,5037.9
XS Rating Curve= 0 ,0
Exp/Cntr=0.3,0.1

Type RM Length L Ch R = 1 ,518000  ,1000,1000,1000
BEGIN DESCRIPTION:
WFSJ Main 510.0
END DESCRIPTION:
XS GIS Cut Line= 3
      3741467.84     10251861.05      3740477.53     10250285.18
      3740666.72     10247704.31
#Sta/Elev= 30
  3138.8  282.72  3386.7  279.34  3748.3  265.48  3992.7  264.55  4193.7  263.36
  4480.9  261.34  4508.8   263.5  4538.6  260.66  4632.9  264.07  4654.1  259.32
  4675.3  263.69  4973.3  262.82  4988.6  255.42  4999.5  254.92  5054.3  263.39
    5071   263.4  5274.8  260.72  5304.9  263.55  5405.2  260.88  5425.2  263.18
  5481.8  259.18  5515.5  263.73  5574.7  263.53  6038.9  263.15  6066.3  263.18
  6919.2  264.78  7119.7  267.89  7350.4  275.83  7550.9  290.94  7587.8  290.95
#Mann= 8 ,-1 , 0
  3138.8     .12       0  3992.7     .05       0  4193.7      .1       0
  4973.3     .07       0    5071      .1       0  5574.7     .05       0
  6038.9      .1       0  6066.3     .05       0
Bank Sta=4973.3,5054.3
XS Rating Curve= 0 ,0
Exp/Cntr=0.3,0.1

Type RM Length L Ch R = 1 ,517000  ,1000,1000,1000
BEGIN DESCRIPTION:
WFSJ Main 509.0
END DESCRIPTION:
XS GIS Cut Line= 3
      3741646.03     10251723.33      3741317.81     10250361.53
       3740909.9     10247737.14
#Sta/Elev= 30
  3599.2  279.69  4122.9  271.95  4434.6  262.85  4589.6  261.29  4981.8  261.27
  4999.5     253  5010.6  254.99  5020.7  260.98  5228.4  261.29  5780.7  263.45
  5911.3  262.56  5940.2  260.92  5945.3  257.96  5972.4  259.65  6002.3  262.81
  6063.1  261.69  6083.3  257.98  6123.8  262.89  6427.4  260.79  6463.8  262.93
  6892.9  263.39  7034.6  267.75  7135.8     275  7176.1  274.69  7181.1  272.32
    7237  276.95  7249.1  274.82  7287.6  279.84  7568.7  283.43  7655.9   288.1
#Mann= 8 ,-1 , 0
  3599.2     .12       0  4434.6     .05       0  4589.6      .1       0
  4981.8     .07       0  5020.7      .1       0  5228.4     .05       0
  5780.7     .12       0  5972.4     .05       0
Bank Sta=4981.8,5020.7
XS Rating Curve= 0 ,0
Exp/Cntr=0.3,0.1

Type RM Length L Ch R = 1 ,516000  ,1000,1000,1000
BEGIN DESCRIPTION:
WFSJ Main 508.0
END DESCRIPTION:
XS GIS Cut Line= 3
      3742569.64     10251674.71      3742232.85     10250226.86
      3741063.62     10247704.48
#Sta/Elev= 30
  3513.5  278.13  3743.1     276  3917.6  277.24  4511.2  261.38  4708.2  261.84
  4737.2   260.1  4810.9  261.49  4975.1  260.29  4985.4  260.06    4995   253.8
  4999.5   253.3  5017.4  255.14  5039.4   260.4  5069.2  257.18    5115  260.14
  5288.7  259.68    5315   261.3  5618.2  260.13  6226.5  262.06  6237.7  260.18
  6258.8  256.56  6273.9  261.88  6281.7  262.23    6619  260.79  6626.6  257.87
  6659.3  261.57  7070.9  263.11  7517.2  271.92  7728.8  278.26  7780.2  282.28
#Mann= 7 ,-1 , 0
  3513.5     .05       0  4737.2      .1       0  4975.1     .07       0
  5039.4      .1       0  5288.7     .05       0  6226.5      .1       0
  6237.7     .05       0
Bank Sta=4985.4,5039.4
XS Rating Curve= 0 ,0
Exp/Cntr=0.3,0.1

Type RM Length L Ch R = 1 ,515000  ,911,911,911
BEGIN DESCRIPTION:
WFSJ Main 507.0
END DESCRIPTION:
XS GIS Cut Line= 3
      3743396.02     10251681.64      3743175.62     10250069.24
       3741209.2     10247585.27
#Sta/Elev= 30
  3372.6  276.33  3655.8  273.99  3918.2  276.48  4412.8  263.46 4970.93  257.53
    4995  251.66  4999.5  251.16    5005  251.66  5010.6   256.2  5018.7  257.79
  5035.1  258.41  5192.8  259.22  5477.2  258.91  5552.1  259.13  5858.5  258.69
  5872.9  256.28  5893.7  259.28  5932.2  258.28  5939.9  258.03  6069.1  259.08
    6352  260.09  6961.8     262  7004.3  261.71  7024.5  256.85  7039.6  253.88
  7047.6  259.49  7062.1  262.04    7538  262.97  7951.5  273.18  8168.1  282.42
#Mann= 12 ,-1 , 0
  3372.6     .05       0    4995     .05       0    5005     .05       0
  5035.1      .1       0  5192.8     .12       0  5477.2      .1       0
  5552.1     .12       0  5932.2     .05       0  5939.9     .12       0
  6069.1     .05       0    6352      .1       0  7024.5     .05       0
Bank Sta=4970.93,5018.7
XS Rating Curve= 0 ,0
Exp/Cntr=0.3,0.1

Type RM Length L Ch R = 1 ,514089  ,496,496,496
BEGIN DESCRIPTION:
WFSJ Main 506.0
END DESCRIPTION:
XS GIS Cut Line= 3
      3744271.02      10251438.6      3743715.46     10249063.57
      3741548.83     10246952.49
#Sta/Elev= 30
    3142  275.01  3219.1  272.16  3659.5  267.82  4104.9  268.38    4341  259.25
  4646.8  257.65  4748.6  258.16  4827.3  257.47  4980.4  257.17  4999.5  250.29
  5022.9  252.27  5029.1  257.52  6377.5  259.98  6762.2   260.8  6783.4  254.43
  6790.5  258.02  6825.8  260.84  6906.1  260.14  7335.1  259.67  7914.8   263.4
  7936.2  267.03  7978.6  264.75  8013.9  267.37  8176.5  268.96  8310.9  273.82
  8346.2  278.05  8367.5  274.94  8424.1  274.92  8452.4  278.21  8606.2  283.35
#Mann= 8 ,-1 , 0
    3142     .05       0  4646.8      .1       0  4748.6     .05       0
  4827.3     .12       0  4980.4     .04       0  5029.1     .12       0
  6377.5      .1       0  6906.1     .05       0
Bank Sta=4980.4,5029.1
XS Rating Curve= 0 ,0
Exp/Cntr=0.3,0.1

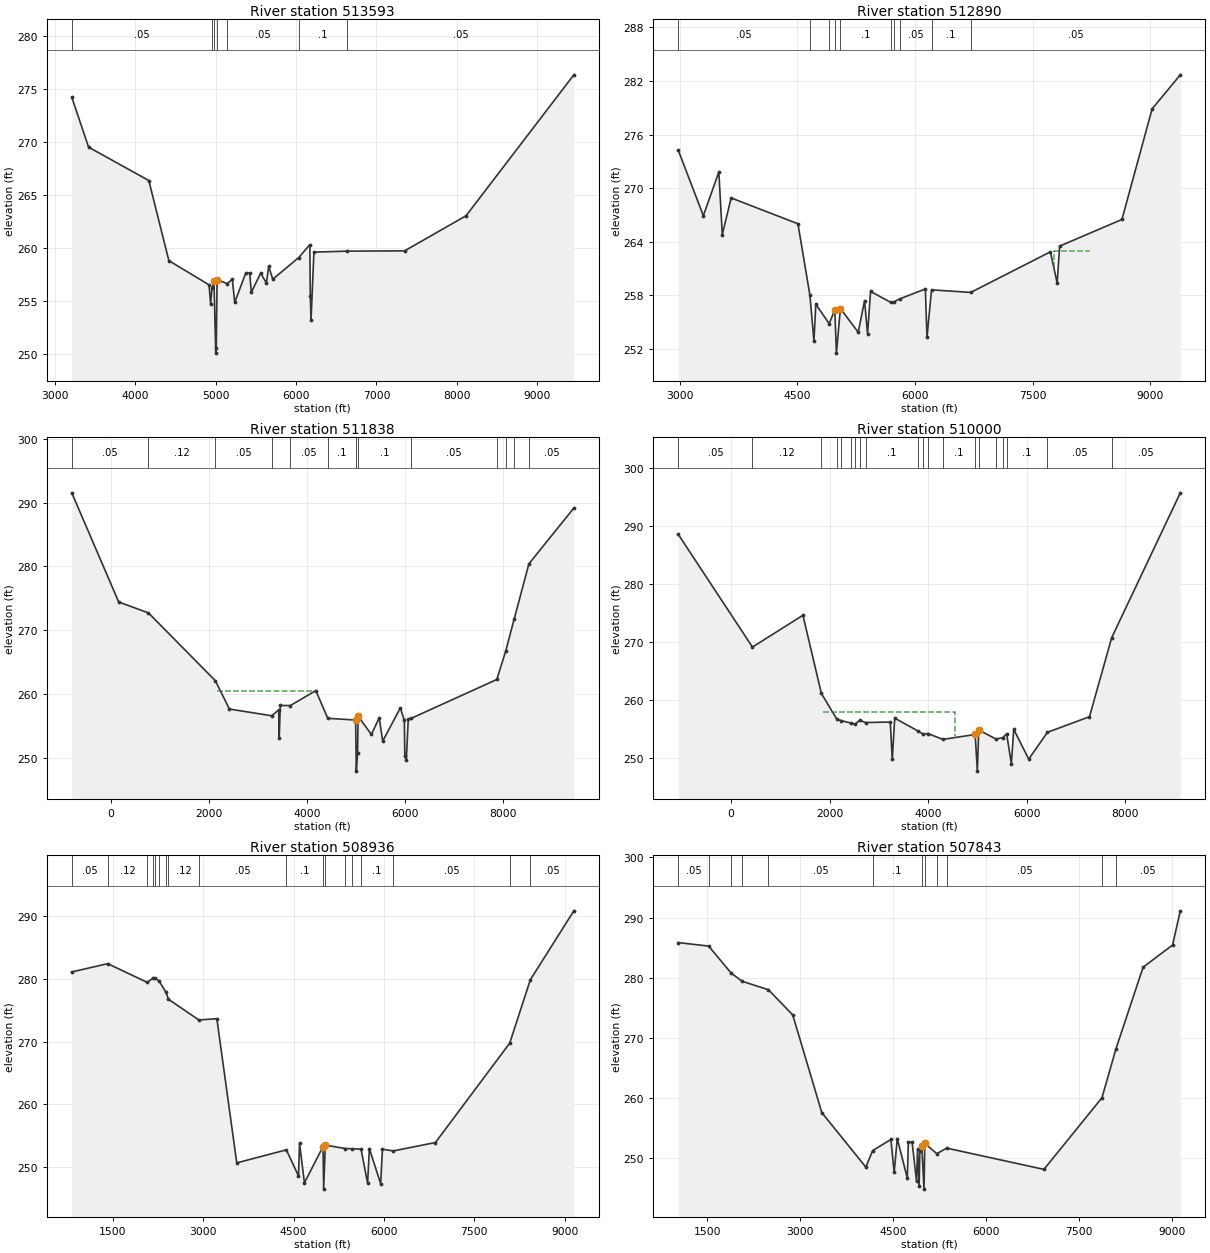
Type RM Length L Ch R = 1 ,513593  ,703,703,703
BEGIN DESCRIPTION:
WFSJ Main 505.0
END DESCRIPTION:
XS GIS Cut Line= 3
      3744339.59     10251440.33      3744339.59     10249396.04
      3741984.53     10245909.02
#Sta/Elev= 30
  3206.5  274.25  3415.8  269.53  4165.8  266.38  4415.8  258.81  4915.8  256.53
  4935.8  254.73  4952.4   256.2 4977.46  256.91  4999.5  250.08  5005.8   250.6
  5015.8     257  5142.9  256.65  5205.8  257.05  5235.8  254.87  5370.7   257.6
  5421.7  257.65  5442.7  255.82  5558.5  257.63  5630.9   256.7  5658.5  258.28
  5709.4  257.06  6030.5  259.09    6171  260.32    6177  255.45  6185.9  253.21
  6221.9  259.62  6635.8  259.71  7351.9  259.74  8116.1  263.05  9458.6  276.36
#Mann= 7 ,-1 , 0
  3206.5     .05       0  4952.4      .1       0 4977.46     .07       0
  5015.8      .1       0  5142.9     .05       0  6030.5      .1       0
  6635.8     .05       0
Bank Sta=4977.46,5015.8
XS Rating Curve= 0 ,0
Exp/Cntr=0.3,0.1

Type RM Length L Ch R = 1 ,512890  ,1052,1052,1052
BEGIN DESCRIPTION:
WFSJ Main 504.0
END DESCRIPTION:
XS GIS Cut Line= 3
      3744339.58     10251440.34      3745074.84     10249858.71
      3743738.04     10245396.94
#Sta/Elev= 30
  2982.5  274.25  3302.8  266.92    3500  271.81  3544.1  264.81  3657.2  268.91
  4508.7  266.02    4661  258.05    4713   252.9  4736.7  257.03  4907.3  254.84
  4978.7   256.4  4999.5  251.55  5050.1  256.54  5277.5  253.89  5358.3  257.42
  5396.6   253.7  5434.9  258.45  5694.2  257.22  5732.4  257.28    5804  257.61
  6133.5  258.73  6154.4  253.33  6212.1  258.63    6712  258.34  7727.8  262.88
  7814.2  259.39  7845.5  263.52    8640   266.5  9025.2  278.88  9384.4  282.68
#Mann= 10 ,-1 , 0
  2982.5     .05       0    4661     .12       0  4907.3      .1       0
  4978.7     .07       0  5050.1      .1       0  5694.2     .05       0
  5732.4      .1       0    5804     .05       0  6212.1      .1       0
    6712     .05       0
#XS Ineff= 1 ,-1
    7772    8230  262.92
Permanent Ineff=
       F
Bank Sta=4978.7,5050.1
XS Rating Curve= 0 ,0
Exp/Cntr=0.3,0.1

Type RM Length L Ch R = 1 ,511838  ,1838,1838,1838
BEGIN DESCRIPTION:
WFSJ Main 503.0
END DESCRIPTION:
XS GIS Cut Line= 4
      3746978.05     10255158.19      3746755.23     10252660.69
      3745908.17     10250340.48      3745491.62      10245094.6
#Sta/Elev= 30
  -803.8  291.52   153.5  274.42   759.8  272.72  2126.9  262.08  2410.8  257.66
  3275.6  256.61  3417.1  257.53  3426.7  253.07  3449.1  258.22  3653.7  258.21
  4173.6  260.55  4417.5  256.21  4985.6  255.94  4999.5  247.94  5025.7  250.84
  5035.7  256.56  5306.6  253.68  5467.1   256.3  5537.3  252.64  5898.4  257.85
  5978.7  255.88  5988.7  250.31  6018.8  249.66  6058.9  256.05  6122.5  256.22
    7865  262.29    8046  266.73  8217.2   271.7  8519.3   280.4    9436  289.14
#Mann= 13 ,-1 , 0
  -803.8     .05       0   759.8     .12       0  2126.9     .05       0
  3275.6      .1       0  3653.7     .05       0  4417.5      .1       0
  4985.6     .07       0  5035.7      .1       0  6122.5     .05       0
    7865      .1       0    8046     .05       0  8217.2     .12       0
  8519.3     .05       0
#XS Ineff= 1 ,-1
    2150  4163.8  260.54
Permanent Ineff=
       F
Bank Sta=4985.6,5035.7
XS Rating Curve= 0 ,0
Exp/Cntr=0.3,0.1

Type RM Length L Ch R = 1 ,510000  ,1064,1064,1064
BEGIN DESCRIPTION:
WFSJ Main 502.0
END DESCRIPTION:
XS GIS Cut Line= 4
      3747140.81     10255060.56      3747041.26     10252542.35
      3747269.09     10248996.74       3745738.9     10245171.22
#Sta/Elev= 30
 -1073.1  288.59   433.9  269.17  1458.4  274.65  1832.8  261.19  2149.1  256.71
  2232.2  256.52  2424.9  256.09  2520.2  255.88  2608.3  256.56  2730.2  256.17
    3232  256.26  3272.1  249.81  3322.2  256.93  3797.3   254.7    3895  254.18
  3993.2  254.27  4300.6  253.27  4955.6  254.11  4999.5   247.8  5027.6  254.88
  5376.5  253.34  5513.7  253.55  5594.5  254.24    5690  249.06  5738.4  254.99
  6042.7  249.87  6422.6  254.49  7275.9  257.17  7727.8   270.8  9120.2  295.74
#Mann= 20 ,-1 , 0
 -1073.1     .05       0   433.9     .12       0  1832.8     .05       0
  2149.1     .12       0  2232.2     .05       0  2424.9     .12       0
  2520.2      .1       0  2608.3     .05       0  2730.2      .1       0
  3797.3     .12       0    3895      .1       0  3993.2     .12       0
  4300.6      .1       0  4955.6     .07       0  5027.6      .1       0
  5376.5      .1       0  5513.7     .05       0  5594.5      .1       0
  6422.6     .05       0  7727.8     .05       0
#XS Ineff= 1 ,-1
    1870  4544.7  257.98
Permanent Ineff=
       F
Bank Sta=4955.6,5027.6
XS Rating Curve= 0 ,0
Exp/Cntr=0.3,0.1

Type RM Length L Ch R = 1 ,508936  ,1093,1093,1093
BEGIN DESCRIPTION:
WFSJ Main 501.0
END DESCRIPTION:
XS GIS Cut Line= 3
      3749697.24      10252775.4      3748460.03     10250034.17
      3746207.66      10245210.3
#Sta/Elev= 30
   819.7  281.09  1415.7  282.41  2073.9  279.42  2161.1  280.08  2202.8  280.14
    2274  279.57  2383.7  277.83    2424  276.74  2927.6  273.44  3227.2  273.64
  3557.4  250.66  4380.4  252.74  4581.8  248.58  4599.1  253.79  4680.4  247.49
  4989.4  253.27  4999.5  246.48    5027   253.5  5355.4  252.95  5477.4  252.91
  5619.3  252.86  5728.9  247.43  5757.6  252.95  5945.9  247.33  5974.3  252.83
  6156.5  252.57  6854.6  253.91  8086.6  269.74  8429.5  279.85    9151  290.83
#Mann= 18 ,-1 , 0
   819.7     .05       0  1415.7     .12       0  2073.9     .05       0
  2161.1     .12       0  2202.8     .05       0    2274     .12       0
  2383.7     .05       0    2424     .12       0  2927.6     .05       0
  4380.4      .1       0  4989.4     .07       0    5027      .1       0
  5355.4     .05       0  5477.4     .12       0  5619.3      .1       0
  6156.5     .05       0  8086.6     .12       0  8429.5     .05       0
Bank Sta=4989.4,5027
XS Rating Curve= 0 ,0
Exp/Cntr=0.3,0.1

Type RM Length L Ch R = 1 ,507843  ,843,843,843
BEGIN DESCRIPTION:
WFSJ Main 500.0
END DESCRIPTION:
XS GIS Cut Line= 3
      3749879.51     10252723.26      3748434.21     10248699.85
      3747470.67     10244988.93
#Sta/Elev= 30
  1029.9  285.84  1521.1  285.26    1885  280.77  2059.5  279.42  2487.2     278
  2879.6  273.81  3348.6  257.58  4060.5  248.51  4169.1  251.26  4464.3  253.11
  4517.4  247.63  4567.4  253.27  4729.9  246.68  4746.5  252.74  4807.9  252.64
  4878.7  246.15  4894.8  251.46  4920.2  245.36  4931.8  251.12  4963.7  252.06
  4999.5  244.86  5012.4  252.46  5207.1  250.75  5365.3  251.68  6936.2  248.14
  7873.6  260.05  8100.9  268.22  8538.1  281.75  9014.5  285.44    9139  291.12
#Mann= 12 ,-1 , 0
  1029.9     .05       0  1521.1     .12       0    1885     .05       0
  2059.5     .12       0  2487.2     .05       0  4169.1      .1       0
  4963.7     .07       0  5012.4      .1       0  5207.1     .12       0
  5365.3     .05       0  7873.6      .1       0  8100.9     .05       0
Bank Sta=4963.7,5012.4
XS Rating Curve= 0 ,0
Exp/Cntr=0.3,0.1

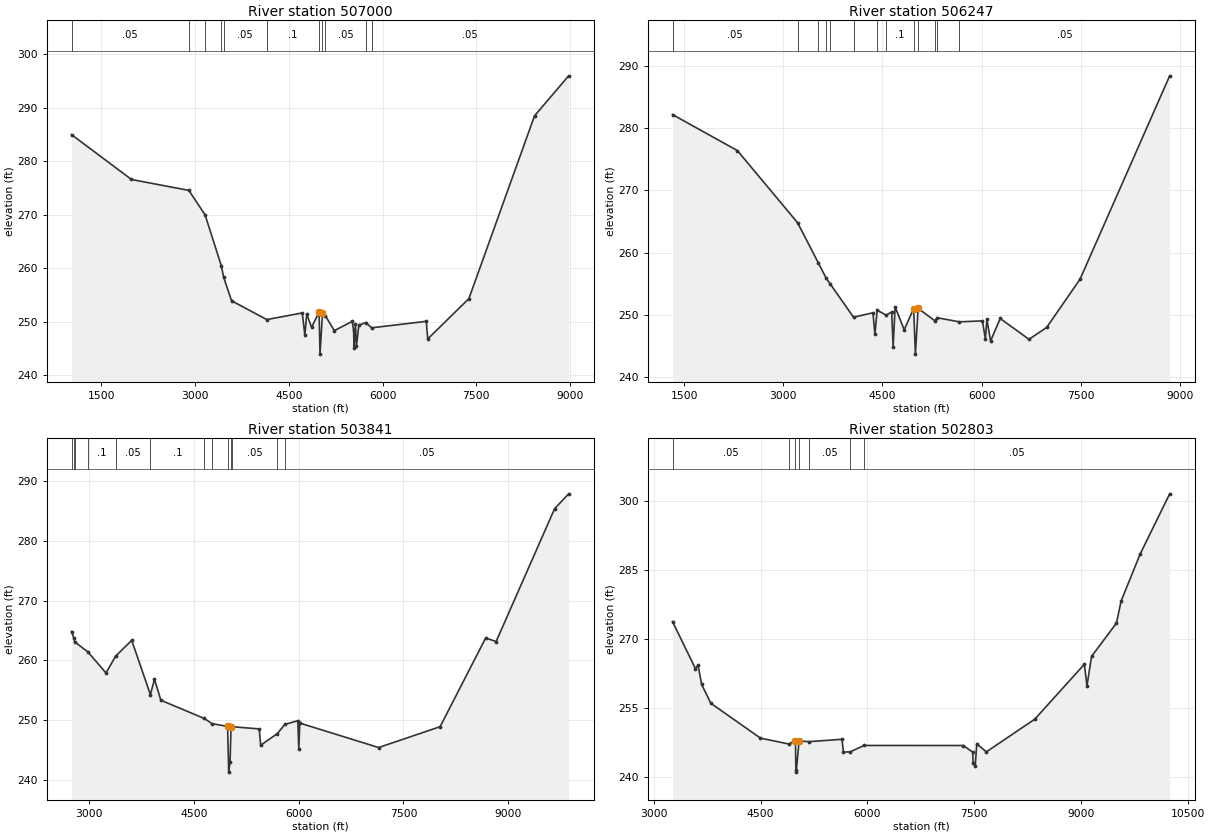
Type RM Length L Ch R = 1 ,507000  ,753,753,753
BEGIN DESCRIPTION:
WFSJ Main 499.0
END DESCRIPTION:
XS GIS Cut Line= 3
      3751702.42     10251694.63       3749219.1     10248589.13
      3747705.03     10244910.75
#Sta/Elev= 30
  1023.7  284.97  1982.9  276.58  2901.8  274.54  3161.4  269.95    3421  260.43
  3458.4  258.27  3583.8  253.91  4147.7  250.39  4715.6  251.63  4757.2  247.47
    4786  251.43  4864.5  248.94  4984.7  251.79  4999.5  243.93  5039.2   251.6
  5086.6  251.09  5228.5  248.32  5513.6  250.04  5537.5  248.44  5542.9  245.05
  5566.9   249.5  5581.9  245.37  5620.2  249.32  5730.3  249.83  5824.6  248.85
  6699.5  250.06  6723.4  246.77  7381.7  254.31  8431.6  288.48  8977.8  295.96
#Mann= 11 ,-1 , 0
  1023.7     .05       0  2901.8     .12       0  3161.4     .05       0
    3421     .12       0  3458.4     .05       0  4147.7      .1       0
  4984.7     .07       0  5039.2      .1       0  5086.6     .05       0
  5730.3      .1       0  5824.6     .05       0
Bank Sta=4984.7,5039.2
XS Rating Curve= 0 ,0
Exp/Cntr=0.3,0.1

Type RM Length L Ch R = 1 ,506247  ,2406,2406,2406
BEGIN DESCRIPTION:
WFSJ Main 498.0
END DESCRIPTION:
XS GIS Cut Line= 3
      3751832.63     10251525.34      3749996.71     10248530.58
      3748199.84     10244949.86
#Sta/Elev= 30
  1326.4  282.21  2306.3  276.42  3217.6   264.8    3533   258.3    3651  255.85
  3707.2  255.01  4063.5  249.59  4357.6  250.31  4387.1  246.84  4420.5  250.72
  4557.2  249.93  4640.5  250.44  4662.6  244.86  4692.7  251.27    4830  247.57
  4972.8  250.97  4999.5  243.65    5040  251.02  5292.7  249.02  5327.6  249.51
  5662.8  248.85  6013.4     249  6058.1  246.05  6080.5  249.29  6135.9  245.75
  6281.9  249.39  6716.6  246.04  6984.6  247.94  7490.2  255.73  8845.4  288.45
#Mann= 13 ,-1 , 0
  1326.4     .05       0  3217.6     .12       0    3533     .05       0
    3651      .1       0  3707.2     .05       0  4063.5      .1       0
  4420.5     .12       0  4557.2      .1       0  4972.8     .07       0
    5040      .1       0  5292.7     .05       0  5327.6      .1       0
  5662.8     .05       0
Bank Sta=4972.8,5040
XS Rating Curve= 0 ,0
Exp/Cntr=0.3,0.1

Type RM Length L Ch R = 1 ,503841  ,1038,1038,1038
BEGIN DESCRIPTION:
WFSJ Main 497.0
END DESCRIPTION:
XS GIS Cut Line= 3
      3752900.37     10250067.05      3750908.17     10248022.77
      3748151.83     10244773.56
#Sta/Elev= 30
  2749.7  264.84  2785.4  263.68  2793.9  263.14  2986.9  261.39  3243.7  257.91
  3381.5  260.74  3611.3  263.36  3878.5  254.29  3936.7  256.87  4028.7  253.36
  4648.5  250.32  4761.3  249.45  4983.3  248.99  4999.5  241.35  5018.7  243.04
  5032.9  248.95  5053.5  248.93  5435.9  248.57    5457  245.84  5696.9   247.8
  5802.8  249.32  5988.3  249.94  6002.6  245.21  6016.9  249.54    7145  245.46
  8024.9  248.94  8677.3  263.76  8826.7  263.16  9663.7  285.35    9865  287.84
#Mann= 13 ,-1 , 0
  2749.7     .05       0  2785.4      .1       0  2793.9     .05       0
  2986.9      .1       0  3381.5     .05       0  3878.5      .1       0
  4648.5     .05       0  4761.3      .1       0  4983.3     .07       0
  5032.9      .1       0  5053.5     .05       0  5696.9      .1       0
  5802.8     .05       0
Bank Sta=4983.3,5032.9
XS Rating Curve= 0 ,0
Exp/Cntr=0.3,0.1

Type RM Length L Ch R = 1 ,502803  ,803,803,803
BEGIN DESCRIPTION:
WFSJ Main 496.0
END DESCRIPTION:
XS GIS Cut Line= 4
      3753264.91      10249051.4        3752054.     10248205.06
      3749583.08      10245436.4      3748646.56     10243914.56
#Sta/Elev= 30
  3264.8  273.79  3586.4  263.55  3622.2  264.38  3672.8  260.16    3801  256.07
  4497.8   248.5  4892.9  247.22  4989.8  247.87    4995  241.61  4999.5  241.11
    5040  247.87  5181.2  247.73  5641.9  248.24  5662.8  245.45  5757.4  245.52
  5952.9   246.9  7341.6  246.89  7476.2  245.46  7482.9  243.05  7511.3  242.36
    7533  247.26  7667.6  245.51  8347.3  252.61  9042.8  264.53  9079.5  259.85
  9143.3  266.23  9492.6  273.44  9558.7  278.27  9827.3  288.51   10240  301.53
#Mann= 7 ,-1 , 0
  3264.8     .05       0  4892.9      .1       0  4989.8     .07       0
    5040      .1       0  5181.2     .05       0  5757.4      .1       0
  5952.9     .05       0
Bank Sta=4989.8,5040
XS Rating Curve= 0 ,0
Exp/Cntr=0.3,0.1