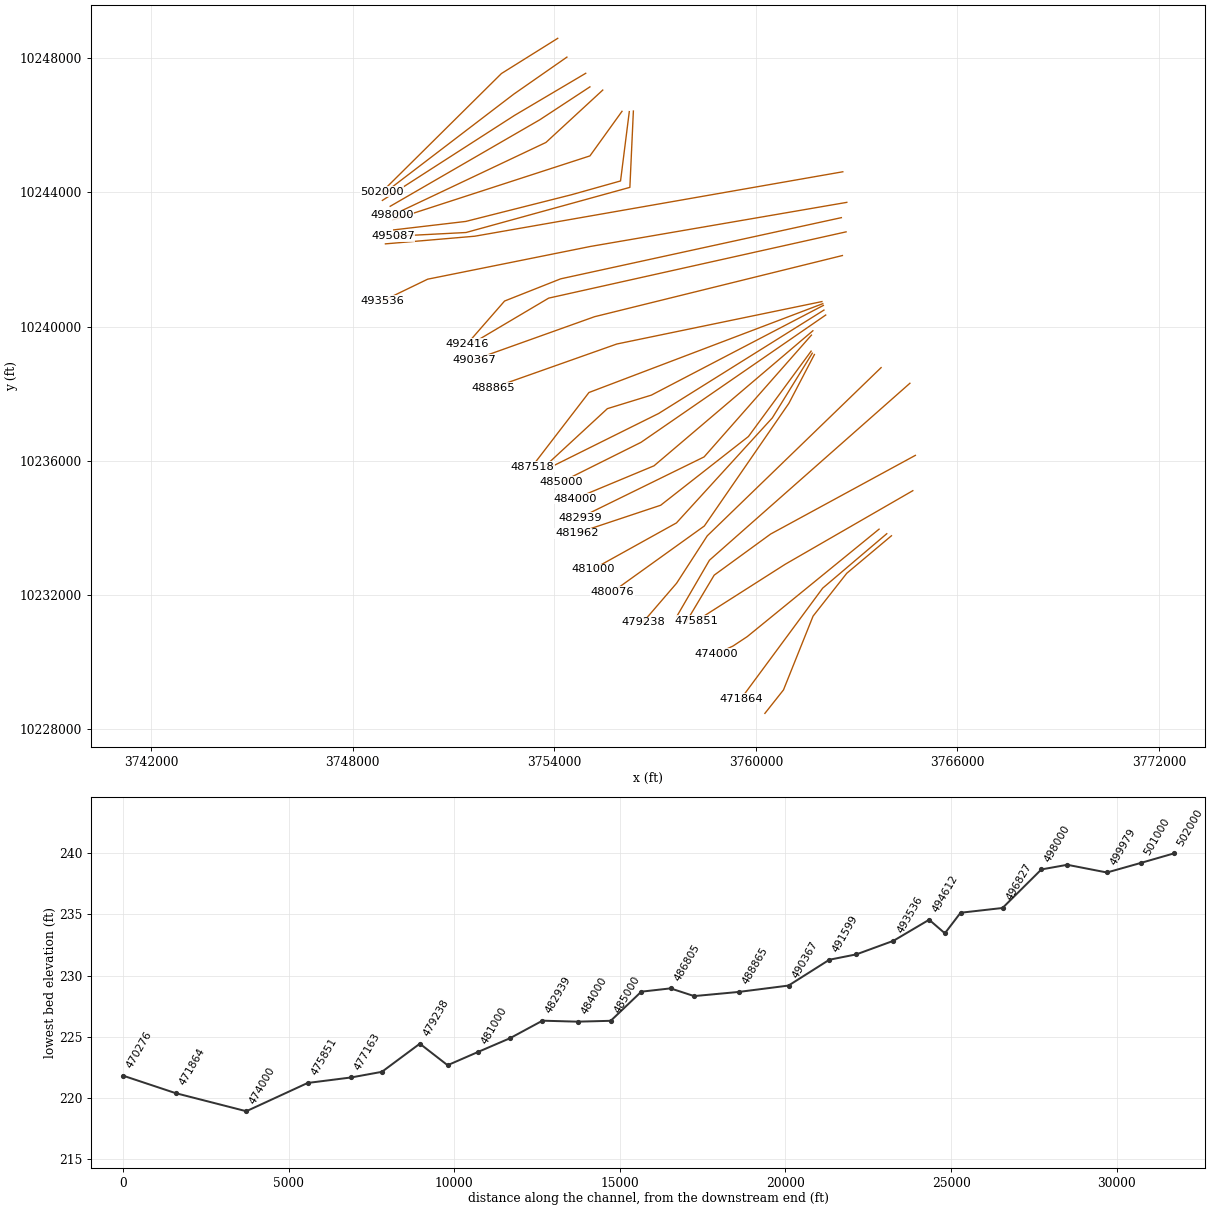
HEC-RAS study WFSJ Main.prj: WFSJ Main Base Level Engineering

--- WFSJ Main.g02 (geometry) --- (continued)

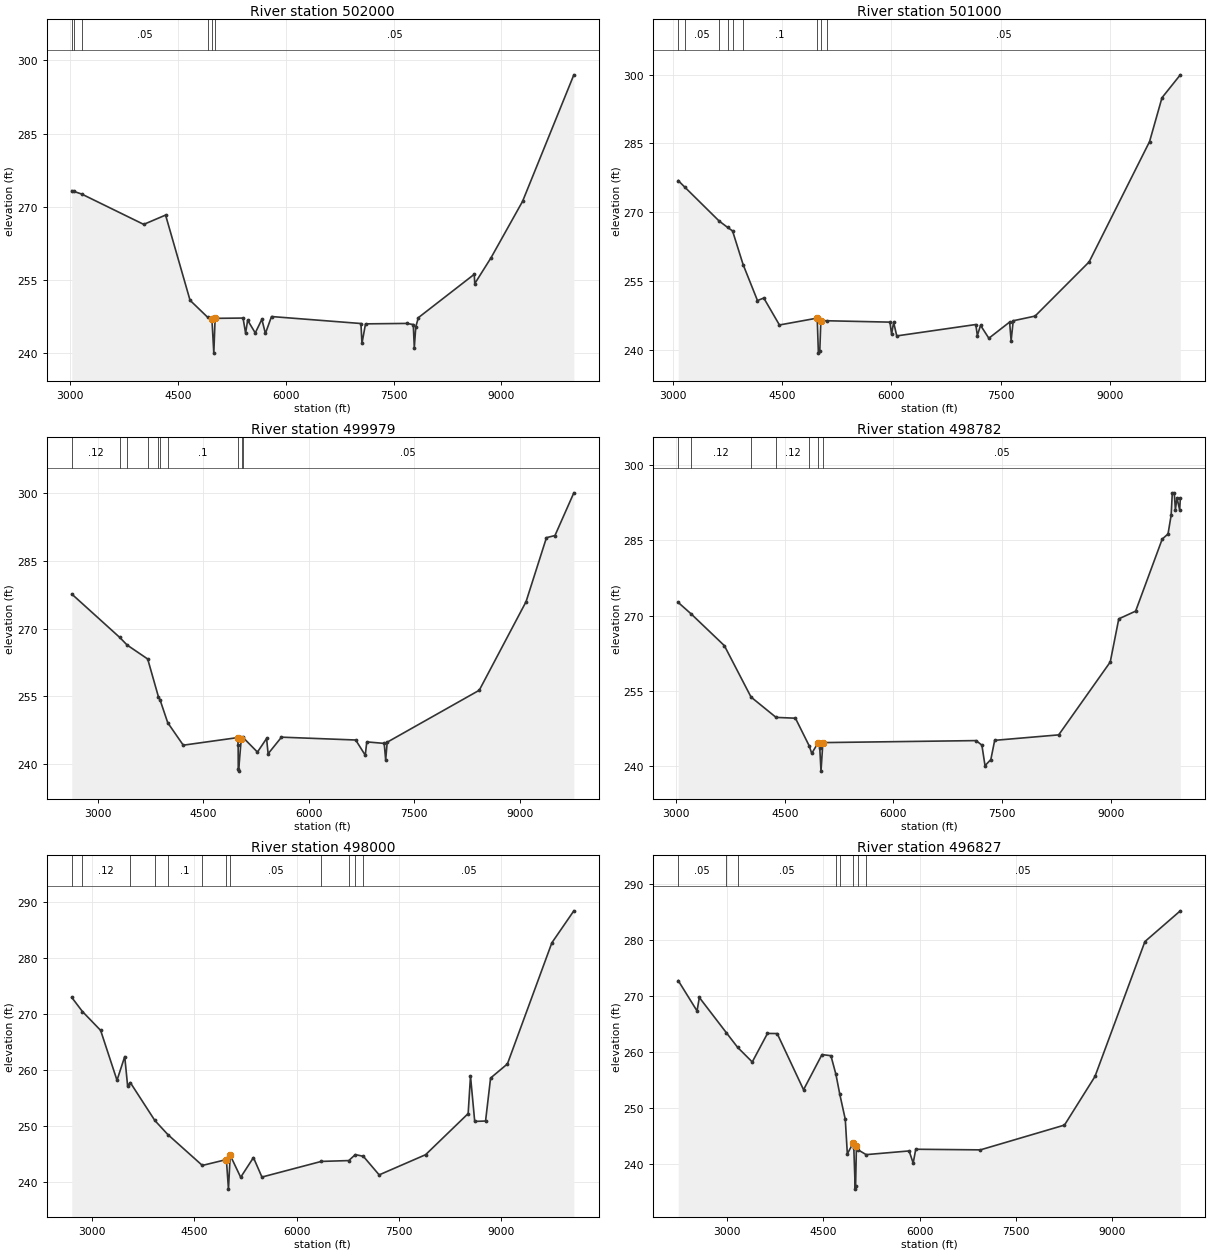
Type RM Length L Ch R = 1 ,502000  ,1000,1000,1000
BEGIN DESCRIPTION:
WFSJ Main 495.0
END DESCRIPTION:
XS GIS Cut Line= 3
      3754101.32     10248587.45      3752425.24     10247538.42
      3748867.86     10244011.08
#Sta/Elev= 30
  3022.7  273.29  3048.6  273.16  3162.3  272.59    4024  266.38  4328.1  268.29
  4668.8  250.82  4915.2  247.32  4973.3  246.91  4999.5  239.99  5017.5  247.12
  5406.4  247.18  5441.8  244.07    5470  246.74  5576.1  244.13    5668  246.92
  5717.5  244.02  5802.4  247.49  7046.9  246.06  7061.1  241.98  7110.5  245.99
  7683.3  246.08  7775.2  245.85  7789.4  241.12  7810.6  245.41  7845.9  247.26
  8623.8  256.15  8630.8  254.24  8857.1  259.54  9295.5  271.09 10009.7  297.04
#Mann= 6 ,-1 , 0
  3022.7     .05       0  3048.6     .12       0  3162.3     .05       0
  4915.2     .05       0  4973.3     .04       0  5017.5     .05       0
Bank Sta=4973.3,5017.5
XS Rating Curve= 0 ,0
Exp/Cntr=0.3,0.1

Type RM Length L Ch R = 1 ,501000  ,1021,1021,1021
BEGIN DESCRIPTION:
WFSJ Main 494.0
END DESCRIPTION:
XS GIS Cut Line= 3
      3754374.75     10248027.55      3752797.21     10246927.87
      3748853.91     10243912.96
#Sta/Elev= 30
    3077   276.9  3168.2  275.45  3637.1  268.08  3754.3  266.67  3821.8  265.91
  3966.7  258.56    4164  250.69  4250.4  251.25    4465  245.36  4983.3  246.86
  4999.5  239.21  5018.8  239.75  5033.3  246.31  5120.8  246.28  5981.1  245.98
  6003.6  243.34  6031.4  245.95  6074.3  242.97  7158.9  245.46  7179.7  243.04
  7223.3  245.29  7337.6  242.46  7622.3  245.99  7643.1  241.93  7672.1  246.28
  7971.4   247.3  8713.2  259.14  9542.1  285.42  9712.5     295  9963.8     300
#Mann= 9 ,-1 , 0
    3077     .12       0  3168.2     .05       0  3637.1     .12       0
  3754.3      .1       0  3821.8     .12       0  3966.7      .1       0
  4983.3     .07       0  5033.3      .1       0  5120.8     .05       0
Bank Sta=4983.3,5033.3
XS Rating Curve= 0 ,0
Exp/Cntr=0.3,0.1

Type RM Length L Ch R = 1 ,499979  ,1197,1197,1197
BEGIN DESCRIPTION:
WFSJ Main 493.0
END DESCRIPTION:
XS GIS Cut Line= 3
      3754934.61     10247545.75      3752821.65     10246295.05
      3748881.44     10243757.67
#Sta/Elev= 30
  2626.8  277.69  3308.5  268.08  3414.7  266.38  3706.8  263.29  3858.9  254.94
  3883.4  254.19    3992  249.16  4212.8  244.18  4984.9  245.86  4993.6   244.2
    4995  238.93  4999.5  238.43  5037.6  245.64  5043.4  245.43  5055.8     246
    5268  242.65  5398.1  245.67  5419.7  242.28    5610  245.96  6665.7  245.33
  6801.7  241.95  6823.2  244.91    7071  244.58  7092.2  240.88  7113.3  244.84
  8423.2  256.36  9088.7  275.99  9379.1  290.19    9500  290.66  9768.7  300.13
#Mann= 10 ,-1 , 0
  2626.8     .12       0  3308.5     .05       0  3414.7     .12       0
  3706.8      .1       0  3858.9     .05       0  3883.4     .12       0
    3992      .1       0  4984.9     .07       0  5043.4      .1       0
  5055.8     .05       0
Bank Sta=4984.9,5037.6
XS Rating Curve= 0 ,0
Exp/Cntr=0.3,0.1

Type RM Length L Ch R = 1 ,498782  ,782,782,782
BEGIN DESCRIPTION:
WFSJ Main 492.0
END DESCRIPTION:
XS GIS Cut Line= 3
      3755060.07      10247141.4      3753567.02      10246160.5
      3749113.91     10243582.38
#Sta/Elev= 30
  3028.4  272.65  3205.7  270.38  3665.2  264.05  4033.6  253.81  4379.1  249.76
  4646.5   249.6  4836.1  244.11  4871.6  242.59  4960.8  244.73  4982.4  243.75
  4999.5  239.06  5025.4  244.74  7140.5  245.14  7220.9  244.23    7264  240.15
  7344.4  241.37  7397.4  245.19  8281.3  246.28    8993  260.79  9110.7  269.38
  9343.4  270.92  9710.5  285.27  9790.8  286.29  9833.9  290.02  9849.7  294.44
    9877  294.48  9892.7  291.13  9914.3  293.48  9951.6  291.07  9960.4  293.36
#Mann= 7 ,-1 , 0
  3028.4     .05       0  3205.7     .12       0  4033.6     .05       0
  4379.1     .12       0  4836.1     .05       0  4960.8     .04       0
  5025.4     .05       0
Bank Sta=4960.8,5025.4
XS Rating Curve= 0 ,0
Exp/Cntr=0.3,0.1

Type RM Length L Ch R = 1 ,498000  ,1173,1173,1173
BEGIN DESCRIPTION:
WFSJ Main 491.0
END DESCRIPTION:
XS GIS Cut Line= 3
      3755442.02     10247045.92      3753750.25     10245484.65
      3749165.99     10243313.28
#Sta/Elev= 30
  2697.9  272.99  2854.3  270.47  3121.9  267.09  3362.4  258.16  3475.8  262.41
  3518.3  257.14  3557.4  257.76  3917.8  250.97  4110.5  248.43  4615.6  242.92
  4968.8  243.97  4999.5  238.68  5025.2  244.74  5178.9   240.8  5366.4  244.33
  5491.1  240.84  6363.4  243.64  6766.2  243.79  6863.1  244.86  6980.8  244.55
    7213  241.23  7894.8  244.84    8520   252.2  8554.5  258.91  8616.5   250.8
  8775.7  250.87  8849.5  258.56  9096.7  261.09  9749.6  282.77 10072.5  288.49
#Mann= 12 ,-1 , 0
  2697.9     .05       0  2854.3     .12       0  3557.4      .1       0
  3917.8     .05       0  4110.5      .1       0  4615.6     .05       0
  4968.8     .04       0  5025.2     .05       0  6363.4      .1       0
  6766.2     .05       0  6863.1      .1       0  6980.8     .05       0
Bank Sta=4968.8,5025.2
XS Rating Curve= 0 ,0
Exp/Cntr=0.3,0.1

Type RM Length L Ch R = 1 ,496827  ,1267,1267,1267
BEGIN DESCRIPTION:
WFSJ Main 490.0
END DESCRIPTION:
XS GIS Cut Line= 3
      3756014.95     10246412.25      3755060.08     10245084.11
      3749183.35     10243174.39
#Sta/Elev= 30
  2244.4  272.71  2537.2   267.3  2572.9   269.7  2992.5  263.43  3169.4   260.8
  3396.6   258.2  3633.5  263.29  3784.5  263.27    4195  253.25  4481.8  259.52
  4620.9  259.32  4699.1  255.98  4759.1  252.44  4844.6  247.97  4876.5  241.82
  4965.5  243.72  4977.6   242.8  4999.5  235.53    5005  236.03  5018.1  243.29
  5041.5  242.55  5169.2  241.68  5838.2  242.34  5901.3  240.17  5941.4  242.64
  6947.6  242.53  8256.6  246.95  8731.2  255.62  9508.5  279.67 10059.4  285.15
#Mann= 8 ,-1 , 0
  2244.4     .05       0  2992.5     .12       0  3169.4     .05       0
  4699.1     .12       0  4759.1      .1       0  4965.5     .07       0
  5041.5      .1       0  5169.2     .05       0
Bank Sta=4965.5,5018.1
XS Rating Curve= 0 ,0
Exp/Cntr=0.3,0.1

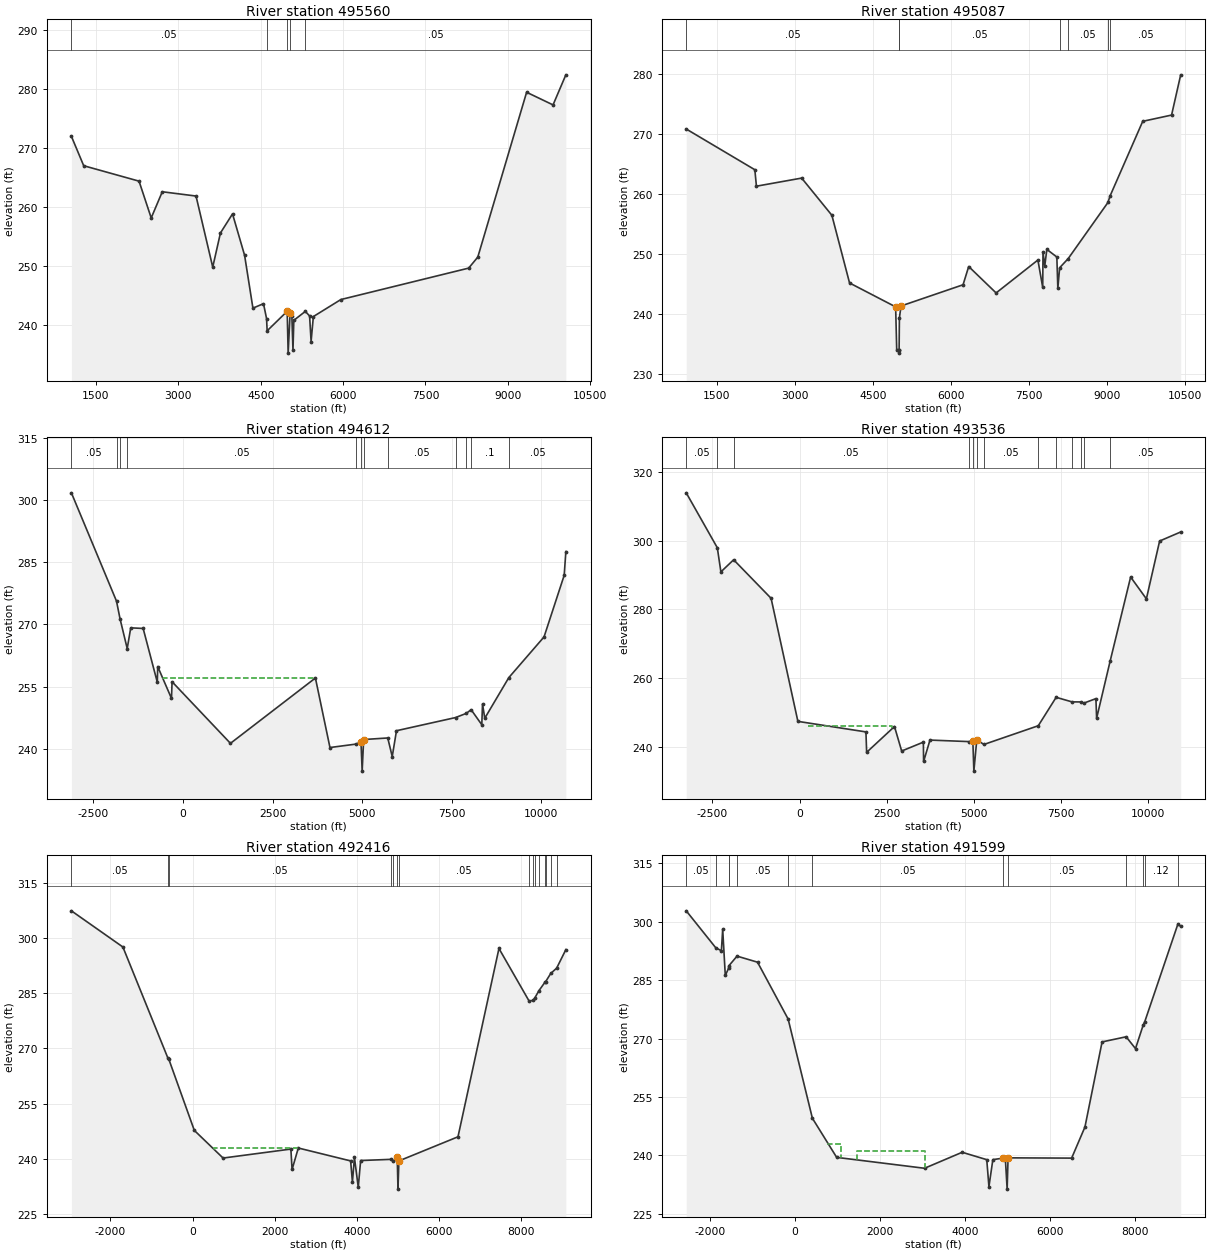
Type RM Length L Ch R = 1 ,495560  ,473,473,473
BEGIN DESCRIPTION:
WFSJ Main 489.0
END DESCRIPTION:
XS GIS Cut Line= 5
      3756231.95     10246403.55      3755971.54     10244337.59
      3754521.89      10243929.6      3751362.16     10243130.99
      3749218.06     10242879.25
#Sta/Elev= 30
  1051.5  271.97  1275.7  266.97  2283.7  264.35  2505.4   258.1    2707  262.55
  3321.7  261.82  3625.9  249.75  3766.5  255.55  3986.3  258.79  4206.2  251.76
  4357.9  242.78  4550.5  243.54  4606.4  241.01  4616.9  238.93 4982.08  242.25
  4999.5  235.14  5035.9  242.04  5067.1  241.45  5087.5  235.64    5103  240.71
  5312.6  242.23  5390.2  241.45  5417.5  237.11  5458.8  241.35  5959.6  244.24
  8287.5  249.58  8453.8  251.45    9343  279.45  9824.5   277.3 10057.7  282.41
#Mann= 5 ,-1 , 0
  1051.5     .05       0  4606.4      .1       0 4982.08     .07       0
  5035.9      .1       0  5312.6     .05       0
Bank Sta=4982.08,5035.9
XS Rating Curve= 0 ,0
Exp/Cntr=0.3,0.1

Type RM Length L Ch R = 1 ,495087  ,475,475,475
BEGIN DESCRIPTION:
WFSJ Main 488.0
END DESCRIPTION:
XS GIS Cut Line= 4
      3756353.48     10246420.92      3756249.32     10244146.61
      3751370.84     10242801.13      3749192.47      10242688.3
#Sta/Elev= 30
   907.4  270.77  2228.1  263.99  2258.7  261.25  3129.6   262.6  3711.1  256.41
  4051.5  245.14  4938.7  241.16  4959.5  233.96  4994.7  233.96  4999.5  233.46
  5005.3  233.96  5011.3  239.34  5042.4  241.31  6236.6  244.84  6344.9  247.88
  6872.7  243.48  7677.3  248.96  7770.1  244.39  7775.3  250.26  7809.7  247.99
  7849.2  250.73  8041.8  249.46  8061.1  244.24  8095.7  247.67  8260.7   249.2
  9025.6  258.54  9065.1   259.6  9695.2  272.05 10250.4  273.09   10426  279.79
#Mann= 7 ,-1 , 0
   907.4     .05       0  4994.7     .05       0  5005.3     .05       0
  8095.7      .1       0  8260.7     .05       0  9025.6      .1       0
  9065.1     .05       0
#XS Ineff= 1 ,-1
  6344.9    8375  247.88
Permanent Ineff=
       F
Bank Sta=4938.7,5042.4
XS Rating Curve= 0 ,0
Exp/Cntr=0.3,0.1

Type RM Length L Ch R = 1 ,494612  ,1076,1076,1076
BEGIN DESCRIPTION:
WFSJ Main 487.0
END DESCRIPTION:
XS GIS Cut Line= 3
      3762588.29     10244611.02      3751629.09     10242690.45
      3748971.75     10242462.68
#Sta/Elev= 30
 -3111.8  301.79 -1853.4  275.63 -1753.9  271.33 -1554.8  264.18 -1456.2  269.18
 -1109.8  269.03  -715.4  256.05    -704  259.83  -319.4  252.13  -303.3  256.16
  1325.2  241.28  3695.4  257.06  4101.2  240.27  4837.2  241.11  4967.1  241.59
  4999.5  234.57    5041   242.2  5713.3  242.58  5838.2  238.09    5957  244.33
    7605  247.51  7903.7  248.52  8039.1  249.41  8336.8  245.78  8356.9   250.8
  8419.6  247.34  9089.8  257.15 10073.2  266.99 10635.2  281.87 10681.5  287.59
#Mann= 12 ,-1 , 0
 -3111.8     .05       0 -1853.4     .12       0 -1753.9      .1       0
 -1554.8     .05       0  4837.2      .1       0  4967.1     .07       0
    5041      .1       0  5713.3     .05       0    7605      .1       0
  7903.7     .12       0  8039.1      .1       0  9089.8     .05       0
#XS Ineff= 1 ,-1
    -550  3695.4  257.06
Permanent Ineff=
       F
Bank Sta=4967.1,5041
XS Rating Curve= 0 ,0
Exp/Cntr=0.3,0.1

Type RM Length L Ch R = 1 ,493536  ,1120,1120,1120
BEGIN DESCRIPTION:
WFSJ Main 486.0
END DESCRIPTION:
XS GIS Cut Line= 4
      3762707.69     10243699.57      3755079.61     10242386.63
      3750229.35     10241410.07      3748883.83     10240759.01
#Sta/Elev= 30
 -3250.7  313.96   -2359  297.95 -2256.5  290.92 -1890.7  294.45  -816.8  283.22
     -48  247.35  1903.9  244.28  1924.1  238.33  2722.5  245.85  2928.7  238.71
  3551.2   241.3  3557.8  235.66  3740.5   241.9  4852.5  241.46  4970.8  241.55
  4999.5  232.85    5083  241.92  5290.4  240.63  6847.1  246.08  7359.6  254.36
  7815.3  253.03  8070.8  253.02  8159.3  252.69  8500.2  253.98  8520.6  248.26
  8908.9  264.95  9496.1  289.42  9947.8  283.06 10327.5  299.91 10931.9  302.55
#Mann= 13 ,-1 , 0
 -3250.7     .05       0   -2359     .12       0 -1890.7     .05       0
  4852.5      .1       0  4970.8     .07       0    5083      .1       0
  5290.4     .05       0  6847.1     .12       0  7359.6     .05       0
  7815.3      .1       0  8070.8     .12       0  8159.3      .1       0
  8908.9     .05       0
#XS Ineff= 1 ,-1
     230  2662.5  246.01
Permanent Ineff=
       F
Bank Sta=4970.8,5083
XS Rating Curve= 0 ,0
Exp/Cntr=0.3,0.1

Type RM Length L Ch R = 1 ,492416  ,817,817,817
BEGIN DESCRIPTION:
WFSJ Main 485.0
END DESCRIPTION:
XS GIS Cut Line= 4
      3762544.91     10243243.84      3754189.85     10241420.92
      3752518.85     10240759.03      3751412.45     10239489.92
#Sta/Elev= 30
 -2947.8  307.41 -1694.3  297.57  -595.9  267.28  -576.1  267.04    43.5  247.71
   743.4  240.19  2393.4  242.63  2422.7  237.08  2574.2  242.92  3847.2  239.41
  3891.1  233.69  3940.2  240.34  4033.2  232.24    4091  239.51  4835.2  239.84
    4887   239.3  4981.5  240.47  4999.5  231.74  5022.5  239.41  6459.9  245.97
    7457  297.17  8188.9  282.91  8285.6  283.04  8323.8  283.62  8429.5   285.7
  8573.3  287.95  8593.5  288.16  8717.2  290.38  8861.1  291.83  9084.8  296.86
#Mann= 15 ,-1 , 0
 -2947.8     .05       0  -595.9      .1       0  -576.1     .05       0
  4835.2      .1       0    4887     .05       0  4981.5     .04       0
  5022.5     .05       0  8188.9     .12       0  8285.6     .05       0
  8323.8     .12       0  8429.5     .05       0  8573.3     .12       0
  8593.5     .05       0  8717.2     .12       0  8861.1     .05       0
#XS Ineff= 1 ,-1
     530  2574.2  242.92
Permanent Ineff=
       F
Bank Sta=4981.5,5022.5
XS Rating Curve= 0 ,0
Exp/Cntr=0.3,0.1

Type RM Length L Ch R = 1 ,491599  ,1232,1232,1232
BEGIN DESCRIPTION:
WFSJ Main 484.0
END DESCRIPTION:
XS GIS Cut Line= 3
      3762685.94     10242820.66      3753831.78     10240845.83
      3751618.28     10239532.92
#Sta/Elev= 30
 -2558.4  302.82 -1863.3  293.33 -1730.5  292.56 -1699.7  298.06 -1638.2   286.2
 -1562.4  288.02 -1554.7  288.69 -1361.8  291.18  -879.3  289.62  -158.3  275.01
   412.6  249.52   984.7  239.46  3054.3  236.66  3940.2  240.77  4519.4  238.87
  4570.7  231.93  4662.9  238.88  4898.5  239.26    4960  238.67  4999.5   231.3
  5021.5  239.34  6518.5  239.27  6832.1  247.27  7235.5  269.13  7801.6  270.45
  8022.9  267.41  8204.2  273.48  8240.6  274.33  9021.5  299.43  9086.9  298.83
#Mann= 13 ,-1 , 0
 -2558.4     .05       0 -1863.3     .12       0 -1562.4     .05       0
 -1554.7     .12       0 -1361.8     .05       0  -158.3     .12       0
   412.6     .05       0  4898.5     .04       0  5021.5     .05       0
  7801.6     .12       0  8204.2     .05       0  8240.6     .12       0
  9021.5     .05       0
#XS Ineff= 2 ,-1
    1475  3068.3  241.22     765    1092   242.9
Permanent Ineff=
       F       F
Bank Sta=4898.5,5021.5
XS Rating Curve= 0 ,0
Exp/Cntr=0.3,0.1

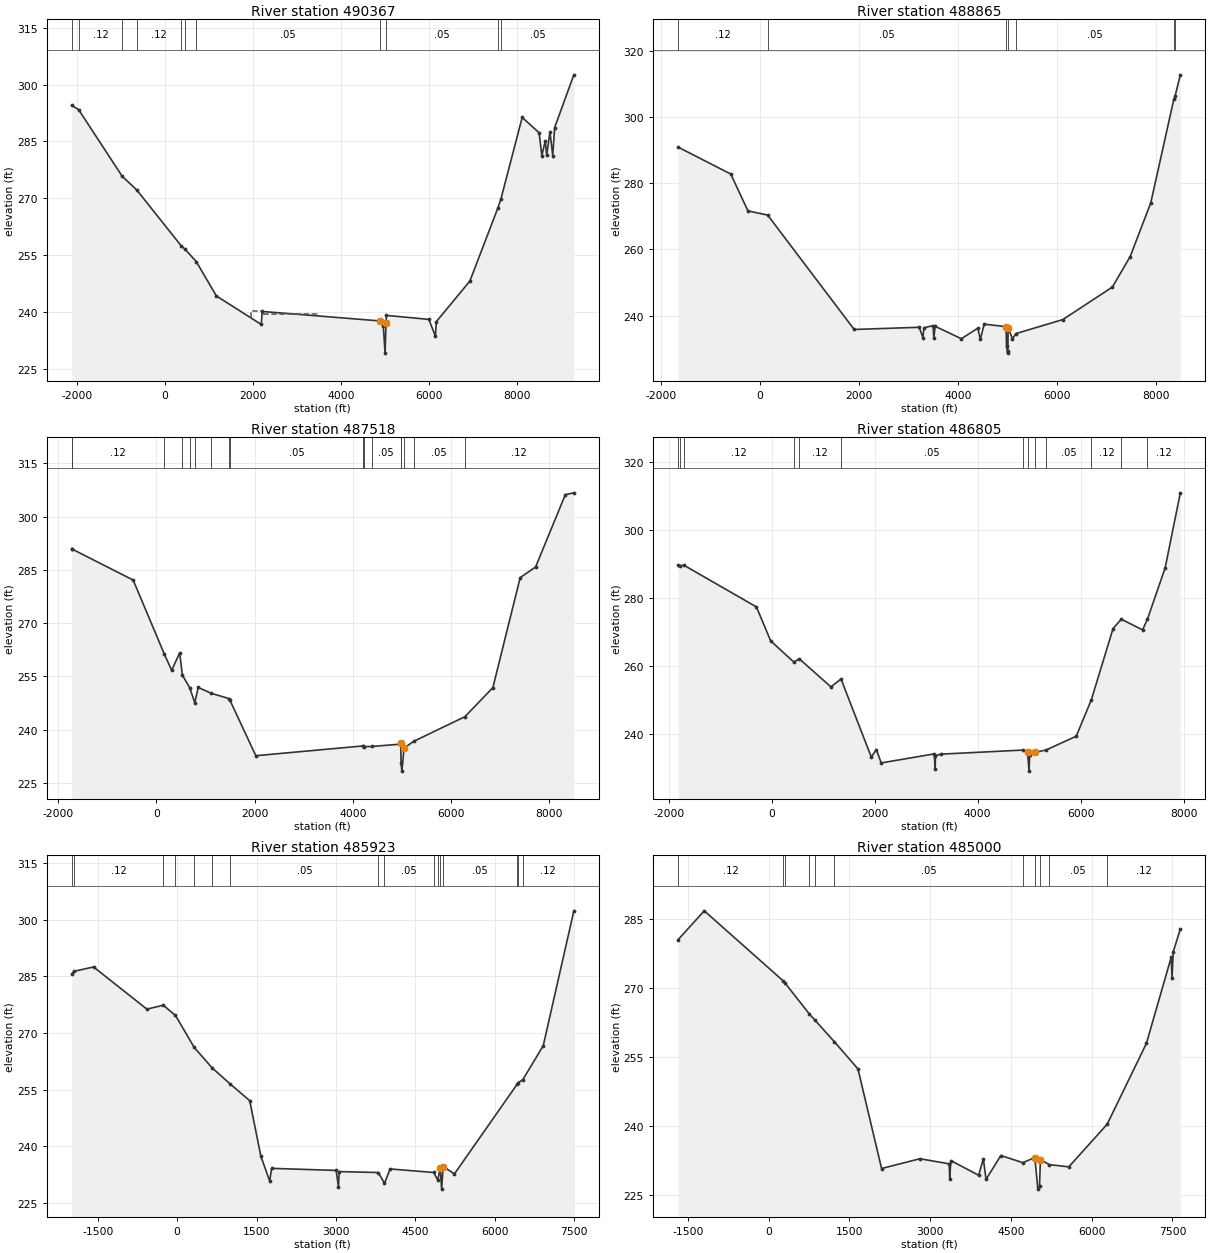
Type RM Length L Ch R = 1 ,490367  ,1502,1502,1502
BEGIN DESCRIPTION:
WFSJ Main 483.0
END DESCRIPTION:
XS GIS Cut Line= 3
      3762576.13     10242114.97       3755197.7     10240292.06
      3751617.01     10239011.69
#Sta/Elev= 30
 -2116.8  294.52 -1961.3   293.4    -971  275.82  -643.3  272.25   367.6   257.5
     453  256.63   710.9  253.33  1167.3  244.27  2187.1  236.75  2207.7  240.18
  4881.9  237.68    4958  236.39  4999.5  229.19  5019.8  237.06  5030.1  239.14
  5993.1  238.09  6141.8  233.67    6163   237.5  6924.6  248.19  7559.9  267.44
  7629.4  269.82  8113.3  291.35  8497.6   287.3  8559.1  281.25  8637.5  285.17
  8669.3  281.43  8743.8   287.5  8807.4   281.3  8849.9  288.67  9286.2  302.58
#Mann= 11 ,-1 , 0
 -2116.8     .05       0 -1961.3     .12       0    -971     .05       0
  -643.3     .12       0   367.6     .05       0     453     .12       0
   710.9     .05       0  4881.9     .04       0  5030.1     .05       0
  7559.9     .12       0  7629.4     .05       0
#XS Ineff= 2 ,-1
    2215  3462.4  239.55    1964  2207.7  240.18
Permanent Ineff=
       F       F
Bank Sta=4881.9,5019.8
XS Rating Curve= 0 ,0
Exp/Cntr=0.3,0.1

Type RM Length L Ch R = 1 ,488865  ,1347,1347,1347
BEGIN DESCRIPTION:
WFSJ Main 482.0
END DESCRIPTION:
XS GIS Cut Line= 3
      3761966.06     10240742.57       3755859.6     10239478.26
      3752182.08     10238176.48
#Sta/Elev= 30
 -1649.6  290.82  -589.4  282.72  -242.2   271.6   155.8  270.33  1902.4  235.81
  3215.4  236.47  3291.2  233.36  3310.7  236.32  3495.5  236.97  3511.4  233.13
  3536.3  236.78  4067.3  233.01  4399.6  236.21  4449.8  232.79  4526.9  237.42
  4970.1  236.66    4979  230.68  4999.5  228.67  5006.3  229.17  5009.9  235.55
  5015.2  236.31  5097.2  232.99  5168.4  234.56  6115.8   238.8  7114.2  248.59
  7474.4  257.78    7891  274.02  8358.4  305.41  8384.2  306.36  8487.5  312.66
#Mann= 7 ,-1 , 0
 -1649.6     .12       0   155.8     .05       0  4970.1     .05       0
  5015.2      .1       0  5168.4     .05       0  8358.4     .12       0
  8384.2     .05       0
Bank Sta=4970.1,5015.2
XS Rating Curve= 0 ,0
Exp/Cntr=0.3,0.1

Type RM Length L Ch R = 1 ,487518  ,713,713,713
BEGIN DESCRIPTION:
WFSJ Main 481.0
END DESCRIPTION:
XS GIS Cut Line= 3
      3761992.39     10240680.51       3755030.6     10238032.95
       3753337.9      10235828.1
#Sta/Elev= 30
 -1725.2  290.94 -1717.7  290.84  -474.4  282.12   156.2  261.41   309.9  256.71
   472.9  261.63   528.5  255.34   676.7  251.84   780.8  247.58     850  251.89
  1113.3  250.26  1478.8  248.75    1497  248.29  2023.9  232.67  4213.7  235.43
  4216.2  235.33  4218.9  235.22  4384.3  235.27  4973.3  235.93  4977.1  236.16
  4982.6  230.63  4999.5  228.33  5042.8  234.78  5237.6  236.71  6283.1  243.65
  6853.1  251.83  7409.6  282.81  7723.2   285.8  8329.6  306.17  8502.7  306.68
#Mann= 18 ,-1 , 0
 -1725.2     .05       0 -1717.7     .12       0   156.2     .05       0
   528.5     .12       0   676.7     .05       0   780.8     .12       0
  1113.3     .05       0  1478.8     .12       0    1497     .05       0
  4213.7      .1       0  4216.2     .05       0  4218.9      .1       0
  4384.3     .05       0  4973.3      .1       0  4977.1     .07       0
  5042.8      .1       0  5237.6     .05       0  6283.1     .12       0
Bank Sta=4977.1,5042.8
XS Rating Curve= 0 ,0
Exp/Cntr=0.3,0.1

Type RM Length L Ch R = 1 ,486805  ,882,882,882
BEGIN DESCRIPTION:
WFSJ Main 480.0
END DESCRIPTION:
XS GIS Cut Line= 4
      3762009.78     10240628.44      3756888.24     10237954.82
      3755579.72     10237552.43      3753668.53      10235785.4
#Sta/Elev= 30
 -1813.2   289.6 -1788.3  289.32 -1702.2   289.5  -294.6  277.24   -18.8  267.27
   431.1  261.03   538.1  261.98  1151.2  253.74    1348  256.05    1935  233.11
  2034.2  235.26  2128.1  231.37    3160  234.04    3175  229.46  3182.1  233.51
  3286.9  233.95  4888.2  235.16    4969  234.65  4999.5  228.96  5010.1  233.74
  5118.7  234.49  5331.6  235.18  5915.8  239.24  6209.6  249.98  6630.2  270.89
  6791.2  273.63  7203.5  270.48  7296.9   273.6  7642.4  288.76  7936.1  310.79
#Mann= 13 ,-1 , 0
 -1813.2     .12       0 -1788.3     .05       0 -1702.2     .12       0
   431.1     .05       0   538.1     .12       0    1348     .05       0
  4888.2      .1       0    4969     .07       0  5118.7      .1       0
  5331.6     .05       0  6209.6     .12       0  6791.2     .05       0
  7296.9     .12       0
Bank Sta=4969,5118.7
XS Rating Curve= 0 ,0
Exp/Cntr=0.3,0.1

Type RM Length L Ch R = 1 ,485923  ,923,923,923
BEGIN DESCRIPTION:
WFSJ Main 479.0
END DESCRIPTION:
XS GIS Cut Line= 3
       3762027.1     10240489.52      3757105.26     10237407.95
      3753806.67     10235767.34
#Sta/Elev= 30
 -1992.2  285.62 -1952.5  286.35 -1580.1  287.51  -571.9  276.34  -261.9  277.38
     -32  274.67   322.4  266.21   663.6  260.76  1004.9   256.5  1371.9  252.11
  1581.8  237.44  1749.2  230.82  1785.7  234.19  3005.7  233.64  3048.2  229.35
  3063.5  233.33  3803.3  233.09  3919.4  230.23  4025.3  234.03  4849.4   233.1
  4926.9   231.1  4973.4  234.27  4999.5  228.69  5027.6  234.67  5241.4  232.72
  6429.7  256.51  6446.3  256.89  6533.3  257.66  6920.1  266.65  7498.8  302.37
#Mann= 16 ,-1 , 0
 -1992.2     .05       0 -1952.5     .12       0  -261.9     .05       0
     -32     .12       0   322.4     .05       0   663.6     .12       0
  1004.9     .05       0  3803.3      .1       0  3919.4     .05       0
  4849.4      .1       0  4926.9     .05       0  4973.4     .04       0
  5027.6     .05       0  6429.7     .12       0  6446.3     .05       0
  6533.3     .12       0
Bank Sta=4973.4,5027.6
XS Rating Curve= 0 ,0
Exp/Cntr=0.3,0.1

Type RM Length L Ch R = 1 ,485000  ,1000,1000,1000
BEGIN DESCRIPTION:
WFSJ Main 478.0
END DESCRIPTION:
XS GIS Cut Line= 3
      3762079.24     10240341.99      3756581.76       10236549.
      3754214.61     10235368.01
#Sta/Elev= 30
   -1679  280.46 -1195.3  286.68     270  271.49   302.4  271.04   753.7  264.34
   858.5  262.98  1221.1  258.28  1658.6  252.39  2097.4  230.78  2807.9   232.9
  3354.2   231.8    3363  228.57    3384   232.5  3900.5  229.32  3987.1  232.89
  4037.8  228.43  4312.2   233.6  4721.5  232.05    4944  233.17  4999.5  226.31
  5030.6  226.99  5047.4   232.7  5214.4  231.62  5574.3  231.14  6287.3  240.39
    7016  257.93  7475.1  276.56  7491.9  272.13  7514.3  277.79  7645.4  282.74
#Mann= 11 ,-1 , 0
   -1679     .12       0     270     .05       0   302.4     .12       0
   753.7     .05       0   858.5     .12       0  1221.1     .05       0
  4721.5      .1       0    4944     .07       0  5047.4      .1       0
  5214.4     .05       0  6287.3     .12       0
Bank Sta=4944,5047.4
XS Rating Curve= 0 ,0
Exp/Cntr=0.3,0.1

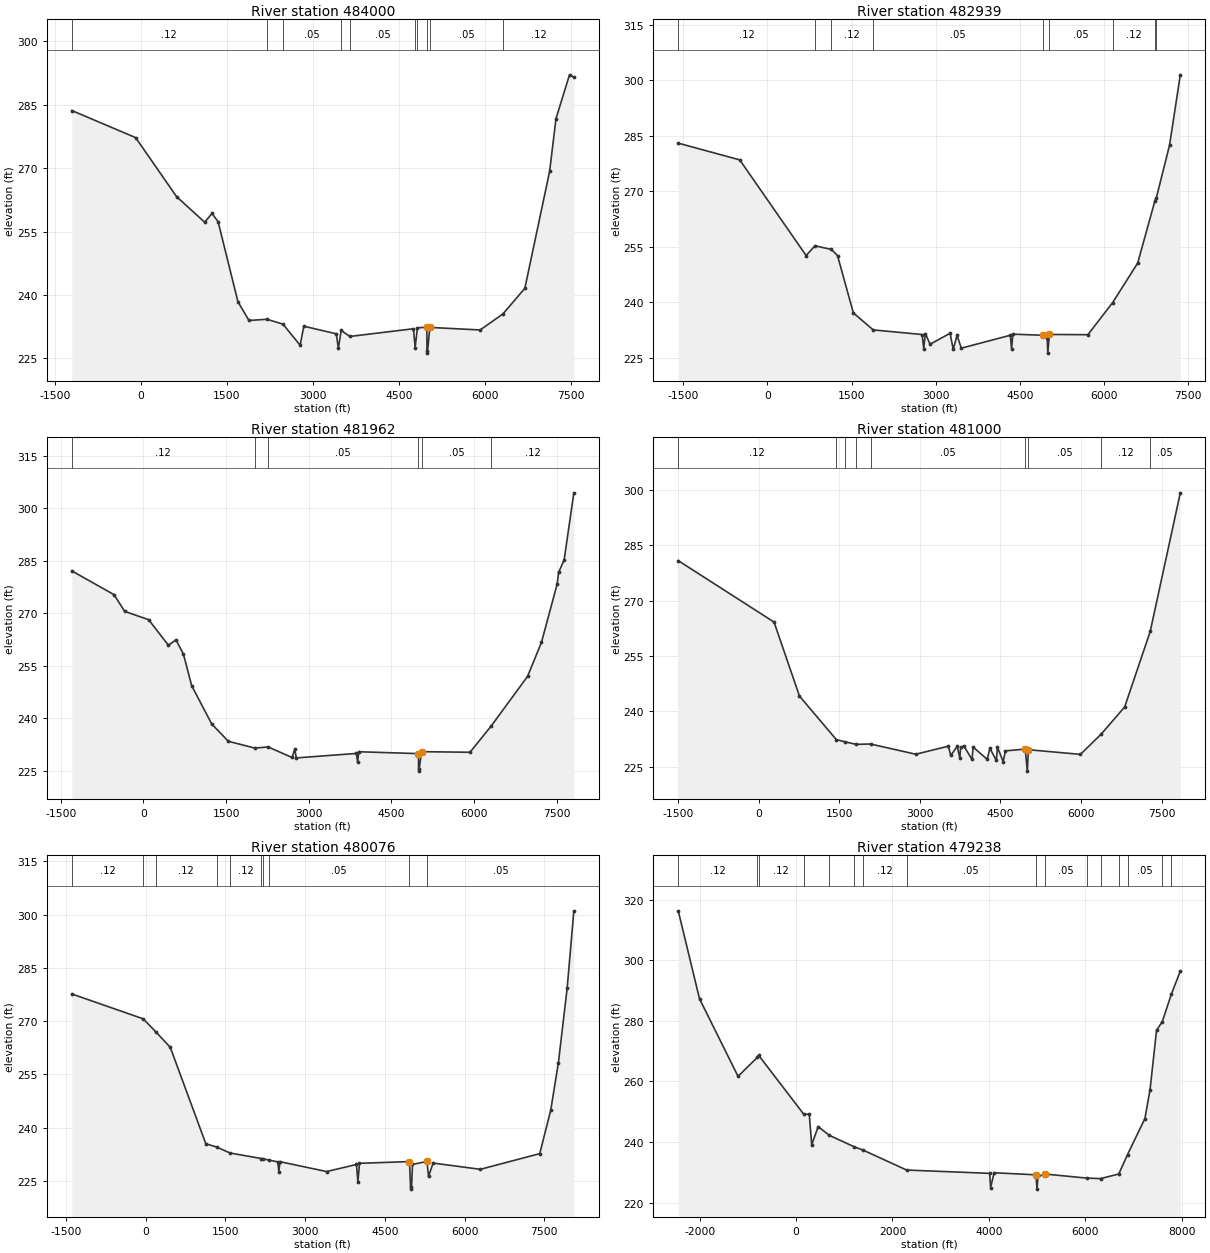
Type RM Length L Ch R = 1 ,484000  ,1061,1061,1061
BEGIN DESCRIPTION:
WFSJ Main 477.0
END DESCRIPTION:
XS GIS Cut Line= 3
      3761697.26     10239873.22      3756968.13     10235848.99
      3754607.05     10234865.29
#Sta/Elev= 30
 -1209.6  283.61   -94.3   277.2   621.8  263.22  1111.6   257.2    1239  259.27
  1345.5  257.32  1692.5  238.37  1884.7  233.96  2198.5  234.25  2478.6  233.09
  2778.6  228.11  2842.3  232.61  3410.1   230.8  3445.2   227.4  3495.2  231.62
  3644.8  230.18  4757.5  232.01  4786.5  227.55    4826  232.23  4991.4  232.36
  4993.6  226.74  4999.5  226.24  5043.6  232.32  5922.1  231.72  6319.4  235.51
  6702.1  241.56  7134.4  269.19    7246  281.68  7482.1  292.05  7557.8  291.49
#Mann= 10 ,-1 , 0
 -1209.6     .12       0  2198.5      .1       0  2478.6     .05       0
  3495.2      .1       0  3644.8     .05       0  4786.5      .1       0
    4826     .05       0  4991.4     .04       0  5043.6     .05       0
  6319.4     .12       0
Bank Sta=4991.4,5043.6
XS Rating Curve= 0 ,0
Exp/Cntr=0.3,0.1

Type RM Length L Ch R = 1 ,482939  ,977,977,977
BEGIN DESCRIPTION:
WFSJ Main 476.0
END DESCRIPTION:
XS GIS Cut Line= 3
       3761653.9     10239743.05      3758459.42     10236114.55
      3754762.15     10234300.62
#Sta/Elev= 30
 -1590.1  282.98  -493.6  278.47   690.4  252.66   848.7  255.29  1140.6   254.3
  1250.1  252.64  1532.9  237.17  1885.5  232.59  2758.7  231.34  2787.1  227.53
  2815.6  231.61    2901  228.72  3257.1  231.68  3313.6  227.33  3381.1  231.11
  3457.6  227.66  4331.3  231.14  4353.8  227.47  4376.3  231.44 4912.75  231.14
  4989.1  230.45  4999.5  226.32  5028.2  231.36  5714.3  231.29  6157.1  239.98
  6602.6  250.63  6910.5  267.45  6936.7  268.31  7170.4  282.43  7362.5  301.42
#Mann= 9 ,-1 , 0
 -1590.1     .12       0   848.7     .05       0  1140.6     .12       0
  1885.5     .05       0 4912.75     .04       0  5028.2     .05       0
  6157.1     .12       0  6910.5     .05       0  6936.7     .12       0
Bank Sta=4912.75,5028.2
XS Rating Curve= 0 ,0
Exp/Cntr=0.3,0.1

Type RM Length L Ch R = 1 ,481962  ,962,962,962
BEGIN DESCRIPTION:
WFSJ Main 475.0
END DESCRIPTION:
XS GIS Cut Line= 4
      3761645.17     10239265.56      3759778.87     10236722.18
      3757166.02     10234673.57      3754666.01     10233840.24
#Sta/Elev= 30
 -1299.8   282.1  -533.3  275.31  -339.2  270.53    95.7  268.15   454.6  260.83
   591.1  262.42   726.9  258.29   876.4  249.27  1240.9  238.34  1541.9  233.41
  2023.3  231.47  2262.4   231.8  2696.2   228.8    2746  231.11  2774.9  228.67
  3864.2  229.94  3886.8  227.43  3907.6  230.43  4990.6  229.89  4993.5  225.39
  4999.5  224.89  5046.7  230.45  5926.5  230.28    6314  237.85    6970  251.95
    7223  261.69  7507.6  278.33  7533.9  281.69  7634.1  285.21  7810.3   304.4
#Mann= 6 ,-1 , 0
 -1299.8     .12       0  2023.3      .1       0  2262.4     .05       0
  4990.6     .04       0  5046.7     .05       0    6314     .12       0
Bank Sta=4990.6,5046.7
XS Rating Curve= 0 ,0
Exp/Cntr=0.3,0.1

Type RM Length L Ch R = 1 ,481000  ,924,924,924
BEGIN DESCRIPTION:
WFSJ Main 474.0
END DESCRIPTION:
XS GIS Cut Line= 4
      3761679.89     10239204.79      3760490.67     10237277.74
      3757635.68     10234147.26      3755145.58     10232763.83
#Sta/Elev= 30
 -1501.3  280.83   283.1  264.17   756.2  244.12  1443.4   232.3    1600  231.73
  1811.4  231.03  2079.8  231.12    2922  228.35  3530.7  230.54  3573.3  228.01
  3693.5  230.49  3742.9   227.3    3757  230.18  3820.6  230.53  3969.2  226.93
  3990.8  230.29  4252.3  226.96  4302.3  229.98  4422.5  226.66  4443.5  230.24
  4549.6  226.35  4592.1  229.26  4960.3  229.75  4999.5  223.77  5018.9  229.58
  5988.9  228.31  6376.9  233.83  6812.6  241.17  7287.9  261.62  7848.6  299.21
#Mann= 9 ,-1 , 0
 -1501.3     .12       0  1443.4      .1       0    1600     .12       0
  1811.4      .1       0  2079.8     .05       0  4960.3     .04       0
  5018.9     .05       0  6376.9     .12       0  7287.9     .05       0
Bank Sta=4960.3,5018.9
XS Rating Curve= 0 ,0
Exp/Cntr=0.3,0.1

Type RM Length L Ch R = 1 ,480076  ,838,838,838
BEGIN DESCRIPTION:
WFSJ Main 473.0
END DESCRIPTION:
XS GIS Cut Line= 4
      3761742.84     10239165.76      3760983.29     10237711.77
      3758465.93     10234055.08      3755732.17     10232091.55
#Sta/Elev= 30
 -1391.7  277.65   -48.9  270.65   188.1  267.01   461.6  262.61  1130.5  235.45
  1332.2  234.55  1584.2  232.86  2172.3   231.3  2196.9  231.23  2313.4  230.88
  2483.3  230.36  2504.2  227.58  2525.2  230.41  3403.1  227.63  3964.5  229.62
  3991.6  224.67  4021.3  229.95  4961.8  230.44  4982.7  223.18  4999.5  222.68
  5018.3  229.64  5290.8  230.48  5320.3  226.24  5406.2  230.02  6295.2  228.26
  7412.5  232.68    7620  244.96  7763.8  258.34  7928.1  279.25    8054  301.06
#Mann= 10 ,-1 , 0
 -1391.7     .12       0   -48.9     .05       0   188.1     .12       0
  1332.2      .1       0  1584.2     .12       0  2172.3      .1       0
  2196.9     .12       0  2313.4     .05       0  4961.8     .04       0
  5290.8     .05       0
Bank Sta=4961.8,5290.8
XS Rating Curve= 0 ,0
Exp/Cntr=0.3,0.1

Type RM Length L Ch R = 1 ,479238  ,1145,1145,1145
BEGIN DESCRIPTION:
WFSJ Main 472.0
END DESCRIPTION:
XS GIS Cut Line= 4
      3763728.49      10238775.1      3758552.74     10233762.11
      3757641.28     10232351.52      3756642.99     10231190.47
#Sta/Elev= 30
 -2444.1  316.31 -2002.3  287.26 -1203.3  261.68  -801.3  267.95  -776.2  268.61
   156.3  249.25   274.8  249.11   324.4  239.04   458.7  245.08   688.8  242.21
    1203  238.44  1391.6  237.32    2294  230.74    4016  229.65  4037.1  224.95
  4107.9  229.85  4976.6  229.16  4999.5  224.44  5018.8  228.63  5169.9  229.41
  6028.8  228.09  6317.6  227.91  6695.1  229.44  6877.8  235.87  7237.6  247.74
  7344.1  257.28    7479  276.87  7597.8   279.7  7784.9  288.74    7972  296.42
#Mann= 16 ,-1 , 0
 -2444.1     .12       0  -801.3     .05       0  -776.2     .12       0
   156.3      .1       0   688.8     .12       0    1203     .05       0
  1391.6     .12       0    2294     .05       0  4976.6     .04       0
  5169.9     .05       0  6028.8     .12       0  6317.6      .1       0
  6695.1     .12       0  6877.8     .05       0  7597.8     .12       0
  7784.9     .05       0
Bank Sta=4976.6,5169.9
XS Rating Curve= 0 ,0
Exp/Cntr=0.3,0.1

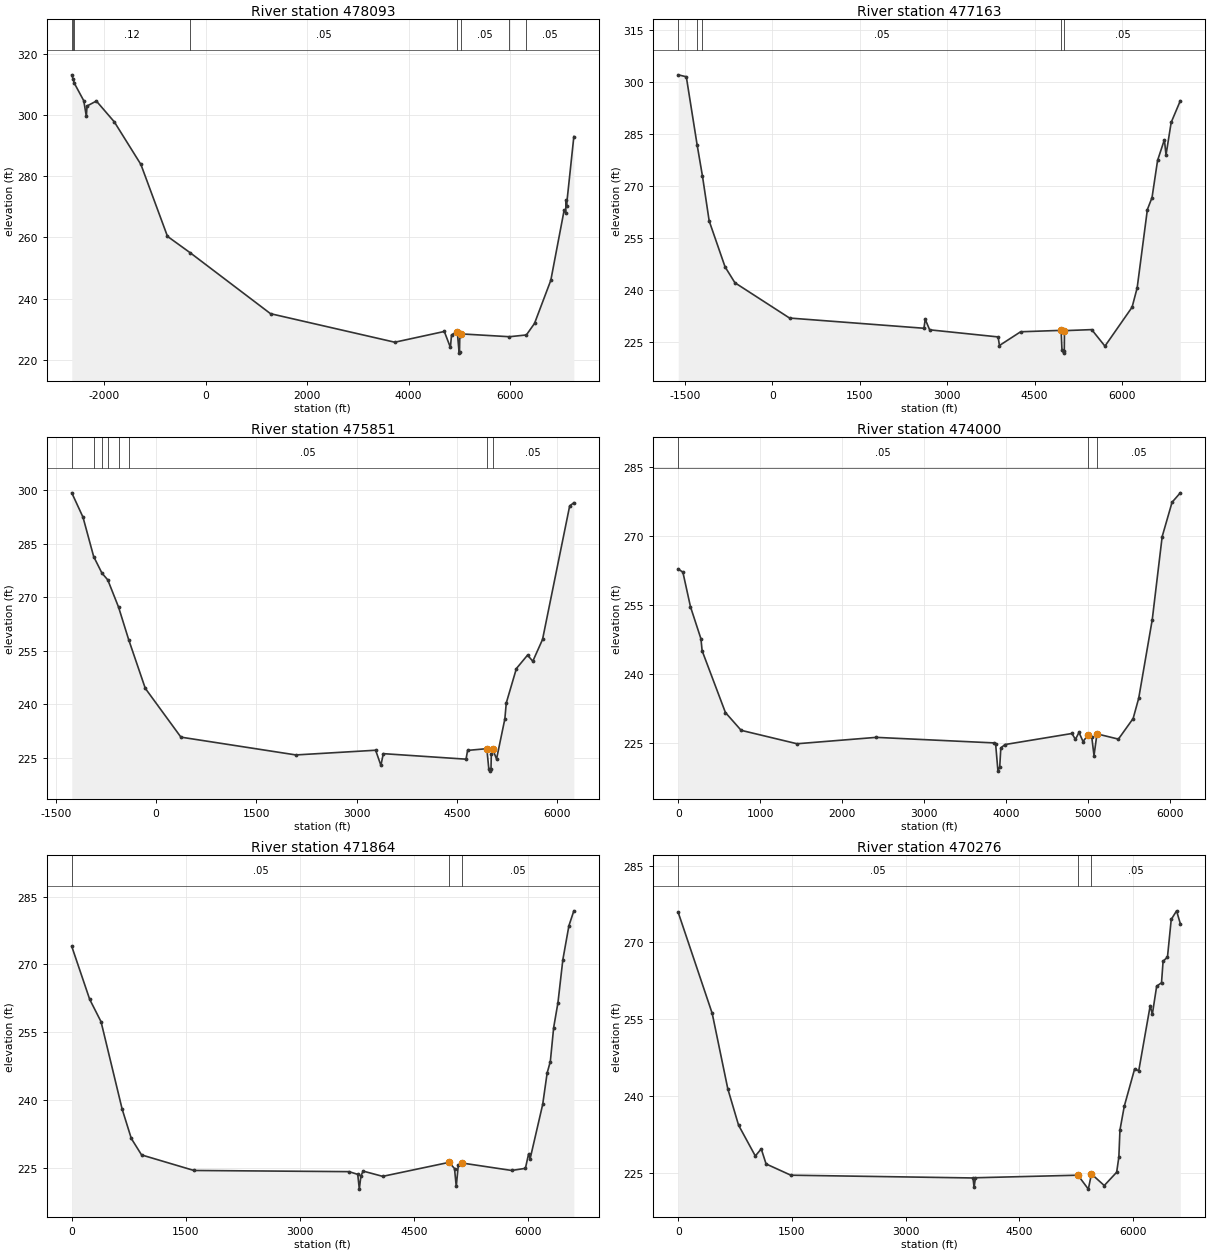
Type RM Length L Ch R = 1 ,478093  ,930,930,930
BEGIN DESCRIPTION:
WFSJ Main 471.0
END DESCRIPTION:
XS GIS Cut Line= 3
       3764585.7     10238308.54      3758617.84     10233035.12
      3757642.87     10231355.99
#Sta/Elev= 30
 -2643.5  313.24   -2617  311.82 -2590.5  310.41 -2406.2  304.74 -2356.1  299.63
 -2341.9  303.04 -2157.9  304.66 -1804.1  297.84 -1279.6   283.9  -755.1  260.36
  -307.4     255  1277.7  235.05  3729.5  225.71  4706.6  229.23    4827  223.99
  4848.8   228.1  4961.7  229.21  4999.5  222.14  5006.6  222.64  5011.9  227.71
  5026.1  228.45  5990.8  227.51  6325.8  228.09  6486.3  231.87  6807.6  245.98
  7071.2  268.97  7101.5  268.14  7107.2  272.25  7117.2  270.41  7262.1  293.03
#Mann= 8 ,-1 , 0
 -2643.5     .12       0   -2617     .05       0 -2590.5     .12       0
  -307.4     .05       0  4961.7     .04       0  5026.1     .05       0
  5990.8      .1       0  6325.8     .05       0
Bank Sta=4961.7,5026.1
XS Rating Curve= 0 ,0
Exp/Cntr=0.3,0.1

Type RM Length L Ch R = 1 ,477163  ,1312,1312,1312
BEGIN DESCRIPTION:
WFSJ Main 470.0
END DESCRIPTION:
XS GIS Cut Line= 4
      3764748.52     10236160.14      3760440.76     10233816.37
       3758758.9     10232590.24      3757923.39     10231190.48
#Sta/Elev= 30
 -1614.7  302.04 -1476.1  301.48 -1290.5  281.81 -1198.4  272.74 -1083.8  259.85
  -811.2  246.59  -642.1     242   295.4  231.81  2601.7  228.86  2623.6  231.46
  2699.6  228.41  3874.6  226.36  3897.1  223.88    4261  227.85  4955.5  228.25
  4970.1  222.58  4999.4  221.68    5010  222.18  5013.2  228.17  5480.3  228.47
  5707.5   223.7  6173.3  234.94  6260.6  240.53  6435.8  263.15  6515.5  266.59
  6610.9  277.33  6727.7  283.31  6755.6  278.91  6844.4  288.31  7000.9  294.55
#Mann= 5 ,-1 , 0
 -1614.7     .05       0 -1290.5     .12       0 -1198.4     .05       0
  4955.5     .04       0  5013.2     .05       0
Bank Sta=4955.5,5013.2
XS Rating Curve= 0 ,0
Exp/Cntr=0.3,0.1

Type RM Length L Ch R = 1 ,475851  ,1851,1851,1851
BEGIN DESCRIPTION:
WFSJ Main 469.0
END DESCRIPTION:
XS GIS Cut Line= 3
      3764672.49     10235107.58      3760874.79     10232915.76
      3758238.04     10231233.88
#Sta/Elev= 30
 -1262.7  299.28 -1094.8  292.45  -934.8  281.39  -811.2  276.76  -724.2  274.87
  -562.4  267.21  -411.7  258.13  -162.8  244.45   370.6  230.76    2091  225.77
  3283.8  227.09  3362.5  222.85  3398.8  226.13  4636.7  224.58  4659.7  227.04
  4947.4  227.53  4977.9  221.73  4999.4  221.23    5010  221.73  5014.3  225.99
  5035.5  227.38    5093  224.63  5217.4  235.88  5238.5  240.34    5390     250
  5556.7  253.76  5635.4  252.05    5781  258.15  6187.2  295.61  6249.6   296.5
#Mann= 8 ,-1 , 0
 -1262.7     .12       0  -934.8     .05       0  -811.2     .12       0
  -724.2     .05       0  -562.4     .12       0  -411.7     .05       0
  4947.4     .04       0  5035.5     .05       0
Bank Sta=4947.4,5035.5
XS Rating Curve= 0 ,0
Exp/Cntr=0.3,0.1

Type RM Length L Ch R = 1 ,474000  ,2136,2136,2136
BEGIN DESCRIPTION:
WFSJ Main 468.0
END DESCRIPTION:
XS GIS Cut Line= 4
      3763667.85     10233961.07      3759741.84     10230757.72
      3759318.49     10230477.65       3758816.8     10230245.86
#Sta/Elev= 30
       0  262.86    56.7  262.17   149.3  254.66   277.2  247.68   291.5  245.09
   575.8  231.66   767.6  227.79  1449.7  224.87  2416.1  226.26    3859  225.05
  3872.9   224.9  3901.7  218.92  3923.5  219.88  3936.8  223.97  3987.8   224.7
  4804.2   227.1  4847.3  225.82  4890.4  227.34  4939.9  225.36  5003.8  226.83
  5046.4  226.36  5073.9  222.29    5110  227.02  5371.6  225.88  5551.4  230.36
  5619.4  234.77  5784.7  251.85  5905.8  269.91  6026.5  277.37  6127.1  279.42
#Mann= 3 , 0 , 0
       0     .05       0  5003.8     .04       0    5110     .05       0
Bank Sta=5003.8,5110
XS Rating Curve= 0 ,0
Exp/Cntr=0.3,0.1

Type RM Length L Ch R = 1 ,471864  ,1588,1588,1588
BEGIN DESCRIPTION:
WFSJ Main 467.0
END DESCRIPTION:
XS GIS Cut Line= 3
      3763896.66     10233824.85      3761988.67     10232202.46
      3759558.12     10228909.06
#Sta/Elev= 30
       0  273.98   235.5   262.3   384.9  257.35   661.6  238.09   782.4  231.58
   917.3  227.95    1605  224.52    3643  224.26  3757.9  223.66  3778.7   220.4
  3799.6  223.34  3828.9  224.38  4085.7  223.22  4958.5  226.31  5029.5  224.95
  5052.5  220.99  5079.6  225.74  5129.7  226.16  5781.2  224.52  5960.9  224.99
  6002.6  228.13  6023.5  227.12  6188.4  239.11  6246.9  246.05  6288.6  248.56
  6332.5  256.07  6388.9  261.57  6453.6  271.09    6533  278.55  6597.7  281.84
#Mann= 3 , 0 , 0
       0     .05       0  4958.5     .04       0  5129.7     .05       0
Bank Sta=4958.5,5129.7
XS Rating Curve= 0 ,0
Exp/Cntr=0.3,0.1

Type RM Length L Ch R = 1 ,470276  ,254,254,254
BEGIN DESCRIPTION:
WFSJ Main 466.0
END DESCRIPTION:
XS GIS Cut Line= 5
      3764036.41     10233764.09      3762705.68     10232646.04
      3761703.08     10231369.99        3760822.     10229170.34
      3760269.05     10228471.56
#Sta/Elev= 30
       0  275.85   448.2  256.13   653.8  241.41   795.6  234.32  1016.6   228.3
  1094.7  229.69  1158.4  226.75  1484.9  224.55  3887.6  224.01  3901.5  222.16
  3919.9  224.05  5271.4  224.55  5408.6  221.83  5449.6  224.79  5618.5  222.53
  5782.1  225.13    5811  228.09  5825.4  233.36  5882.5  238.02  6017.8  245.23
  6073.8  244.97  6224.5  257.67  6252.3  255.95  6309.5  261.44  6373.6  262.14
  6394.4  266.33  6452.1  267.14  6501.8  274.49  6572.3  276.17  6621.5  273.66
#Mann= 3 , 0 , 0
       0     .05       0  5271.4     .04       0  5449.6     .05       0
Bank Sta=5271.4,5449.6
XS Rating Curve= 0 ,0
Exp/Cntr=0.3,0.1