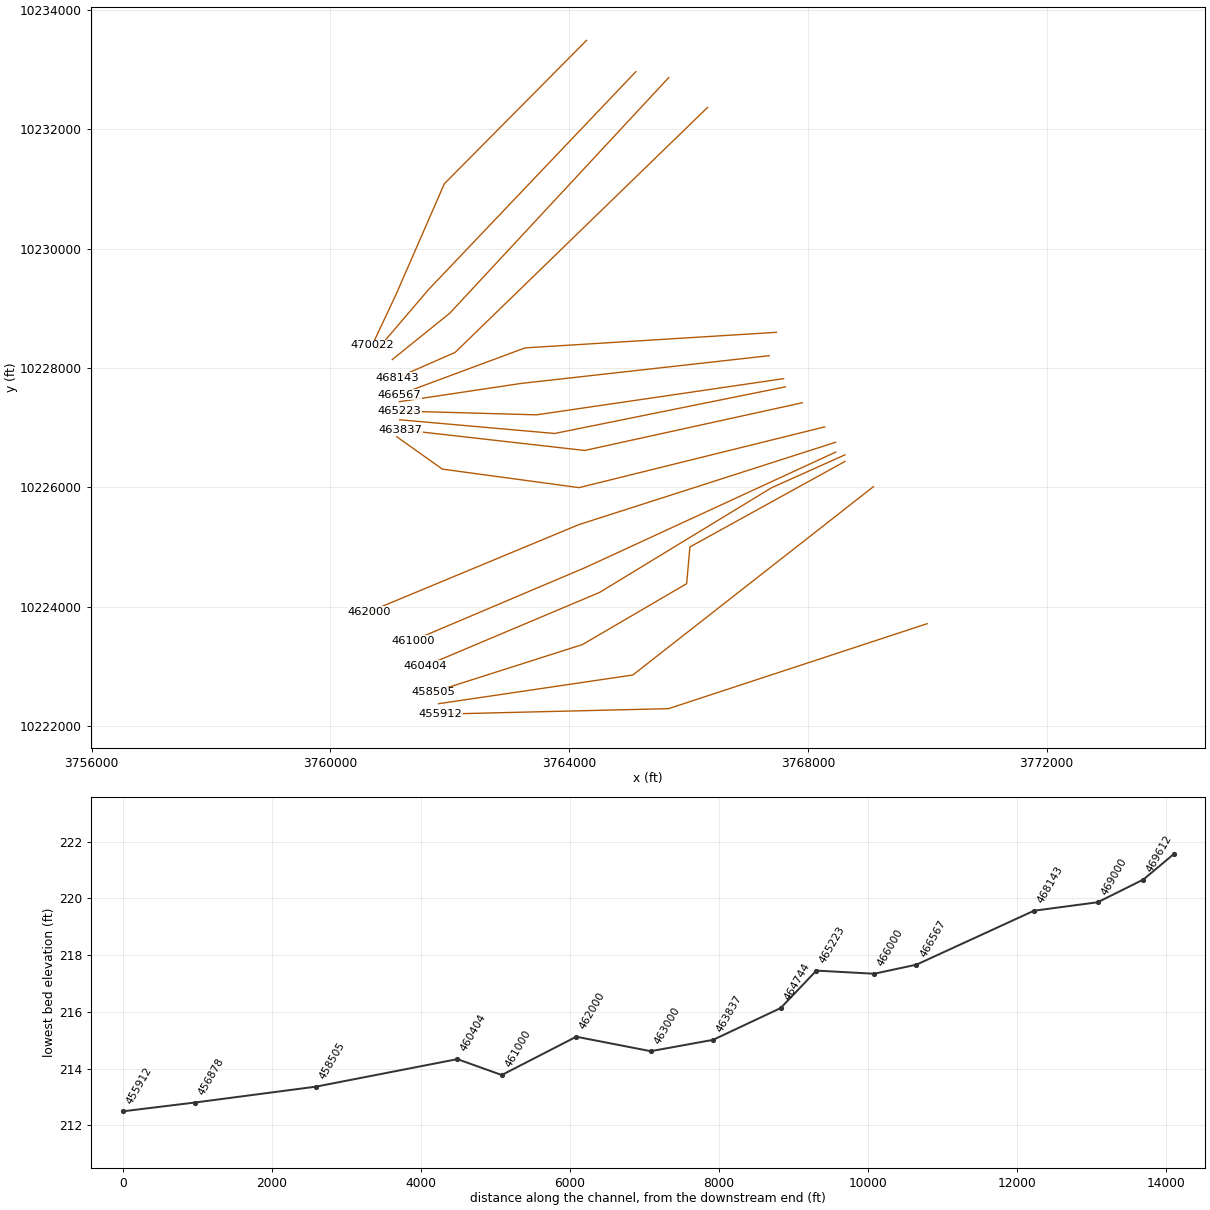
HEC-RAS study WFSJ Main.prj: WFSJ Main Base Level Engineering

--- WFSJ Main.g02 (geometry) --- (continued)

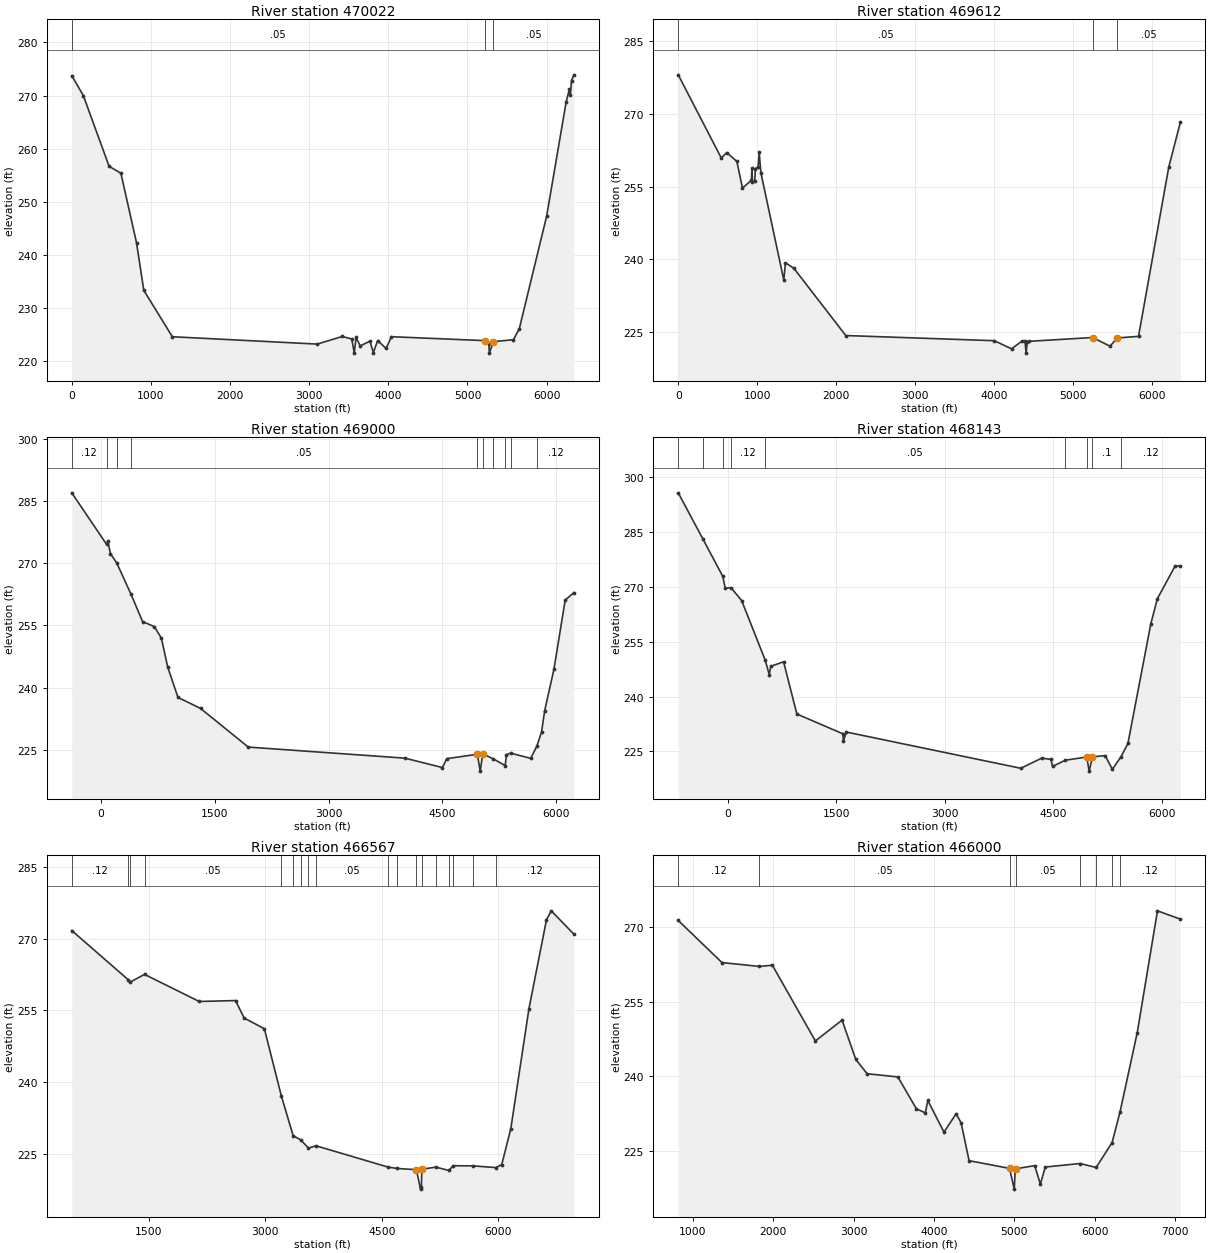
Type RM Length L Ch R = 1 ,470022  ,410,410,410
BEGIN DESCRIPTION:
WFSJ Main 465.0
END DESCRIPTION:
XS GIS Cut Line= 4
      3764291.62     10233484.58      3761909.68      10231084.4
      3761095.44     10229218.95      3760700.48     10228380.41
#Sta/Elev= 30
       0  273.75   146.5  269.98   471.8  256.69   620.3   255.4   818.3  242.31
   910.2  233.36  1270.9  224.64  3102.3  223.26  3417.9  224.69  3537.9  224.22
  3569.4  221.58  3592.4   224.5    3645  222.92    3767  223.81  3810.7  221.66
  3865.2  223.93  3971.2  222.44  4039.8  224.65  5218.1  223.91  5270.3  223.37
  5275.8  221.56  5328.1  223.72  5580.4  224.08  5654.9  226.16  6000.4  247.34
  6246.7   268.8  6286.8  271.16  6298.9  270.02  6315.1  272.83  6343.8   273.9
#Mann= 3 , 0 , 0
       0     .05       0  5218.1     .04       0  5328.1     .05       0
Bank Sta=5218.1,5328.1
XS Rating Curve= 0 ,0
Exp/Cntr=0.3,0.1

Type RM Length L Ch R = 1 ,469612  ,612,612,612
BEGIN DESCRIPTION:
WFSJ Main 464.0
END DESCRIPTION:
XS GIS Cut Line= 3
      3765117.85     10232961.07      3761648.39     10229316.17
      3760785.55     10228307.49
#Sta/Elev= 30
       0  278.05   544.6  260.91   615.4  262.01   742.8  260.18   813.6  254.69
   926.5  256.31   933.7  258.83   940.6  255.85   968.9   256.1   976.2   258.7
  1011.4  259.02  1025.5  262.04  1046.9  257.86    1337  235.73    1358  239.29
    1464  238.17    2122  224.29  4003.6  223.22  4222.8  221.54  4357.1  223.19
  4392.3  223.09  4406.5  220.66  4420.7  222.91    4449   223.1  5249.4  223.88
    5469  222.09  5561.2  223.79  5830.1  224.12  6213.2  259.02  6359.5  268.24
#Mann= 3 , 0 , 0
       0     .05       0  5249.4     .04       0  5561.2     .05       0
Bank Sta=5249.4,5561.2
XS Rating Curve= 0 ,0
Exp/Cntr=0.3,0.1

Type RM Length L Ch R = 1 ,469000  ,857,857,857
BEGIN DESCRIPTION:
WFSJ Main 463.0
END DESCRIPTION:
XS GIS Cut Line= 3
      3765667.87     10232861.09      3761999.08     10228915.41
      3761037.57     10228141.47
#Sta/Elev= 30
  -387.8  286.99    71.7  274.55    86.4  275.39   121.6  272.34   204.8  270.09
   392.3  262.59   546.2  255.93     702  254.71   793.9  251.95   878.9  244.86
  1013.3  237.64  1310.3  234.99  1940.1  225.66  4006.4  222.99  4501.3  220.72
    4558  222.86  4961.6  223.93  4999.3  219.86  5032.3  224.04  5169.9  222.84
  5328.8   221.2  5345.8  223.83  5401.1   224.2  5665.7  222.94  5747.7  225.94
  5808.1  229.28  5849.7  234.46  5971.3  244.38  6120.1  261.11  6234.3  262.91
#Mann= 10 ,-1 , 0
  -387.8     .12       0    71.7     .05       0   204.8     .12       0
   392.3     .05       0  4961.6     .04       0  5032.3     .05       0
  5169.9      .1       0  5328.8     .05       0  5401.1      .1       0
  5747.7     .12       0
Bank Sta=4961.6,5032.3
XS Rating Curve= 0 ,0
Exp/Cntr=0.3,0.1

Type RM Length L Ch R = 1 ,468143  ,1576,1576,1576
BEGIN DESCRIPTION:
WFSJ Main 462.0
END DESCRIPTION:
XS GIS Cut Line= 3
      3766317.86     10232361.08      3762090.06     10228260.81
      3761124.34     10227837.63
#Sta/Elev= 30
  -683.8   295.8  -340.3  283.06   -67.8  272.92   -33.1  269.62      45  269.83
   193.2  266.29   519.3  249.95     575  246.02   596.3  248.28     773  249.51
     957   235.2  1593.4  229.79  1600.5  227.85  1642.8  230.26  4054.3  220.34
  4344.4  223.13  4471.5  222.77  4492.9  220.84  4669.6  222.55  4966.7  223.43
  4999.3  219.56  5044.4  223.49    5221  223.81    5320  220.06  5441.8  223.55
  5535.7  227.15  5852.3  259.92  5942.6  266.79  6187.3  275.73  6260.1   275.8
#Mann= 9 ,-1 , 0
  -683.8     .05       0  -340.3     .12       0   -67.8     .05       0
      45     .12       0   519.3     .05       0  4669.6      .1       0
  4966.7     .07       0  5044.4      .1       0  5441.8     .12       0
Bank Sta=4966.7,5044.4
XS Rating Curve= 0 ,0
Exp/Cntr=0.3,0.1

Type RM Length L Ch R = 1 ,466567  ,567,567,567
BEGIN DESCRIPTION:
WFSJ Main 461.0
END DESCRIPTION:
XS GIS Cut Line= 3
      3767472.03     10228597.19      3763261.94     10228336.77
      3761157.63     10227555.79
#Sta/Elev= 30
   509.9  271.69    1234  261.45  1258.4  260.88  1446.1  262.53    2150  256.87
  2618.1  257.06  2728.3  253.41  2988.8  251.18  3207.3  237.15  3358.9  228.85
  3457.5  227.94  3556.2  226.24  3654.9  226.71  4580.1  222.27  4695.5  221.98
  4945.7  221.72  4999.2  217.66    5010  218.16  5016.3  221.83  5197.6  222.25
  5363.9  221.56  5420.4  222.55  5675.3  222.52  5968.6  222.16  6044.4   222.8
  6161.7  230.32    6394   255.3  6620.4  273.94  6681.7  275.81  6972.6  270.95
#Mann= 18 ,-1 , 0
   509.9     .12       0    1234     .05       0  1258.4     .12       0
  1446.1     .05       0  3207.3     .12       0  3358.9      .1       0
  3457.5     .05       0  3556.2      .1       0  3654.9     .05       0
  4580.1      .1       0  4695.5     .05       0  4945.7     .07       0
  5016.3      .1       0  5197.6     .05       0  5363.9      .1       0
  5420.4     .05       0  5675.3      .1       0  5968.6     .12       0
Bank Sta=4945.7,5016.3
XS Rating Curve= 0 ,0
Exp/Cntr=0.3,0.1

Type RM Length L Ch R = 1 ,466000  ,777,777,777
BEGIN DESCRIPTION:
WFSJ Main 460.0
END DESCRIPTION:
XS GIS Cut Line= 3
      3767352.66     10228206.56      3763198.24     10227742.16
      3761156.95     10227436.17
#Sta/Elev= 30
   819.7  271.33  1363.5  262.87  1828.9   262.1  1990.5  262.33  2525.1  247.12
  2857.1   251.3  3028.2   243.4  3169.3  240.53  3551.4  239.89  3782.9  233.46
  3893.5  232.68  3923.7  235.16    4125  228.79  4275.9  232.49    4338  230.66
  4436.9  223.06    4940  221.51  4999.2  217.34  5010.5  221.25  5020.6  221.44
  5253.2  222.06    5324  218.34  5384.6  221.78  5818.6  222.49  6017.1  221.69
  6215.6  226.69  6314.8  232.89  6528.7  248.81  6780.1  273.27  7064.1   271.6
#Mann= 8 ,-1 , 0
   819.7     .12       0  1828.9     .05       0    4940     .04       0
  5020.6     .05       0  5818.6      .1       0  6017.1     .12       0
  6215.6     .05       0  6314.8     .12       0
Bank Sta=4940,5020.6
XS Rating Curve= 0 ,0
Exp/Cntr=0.3,0.1

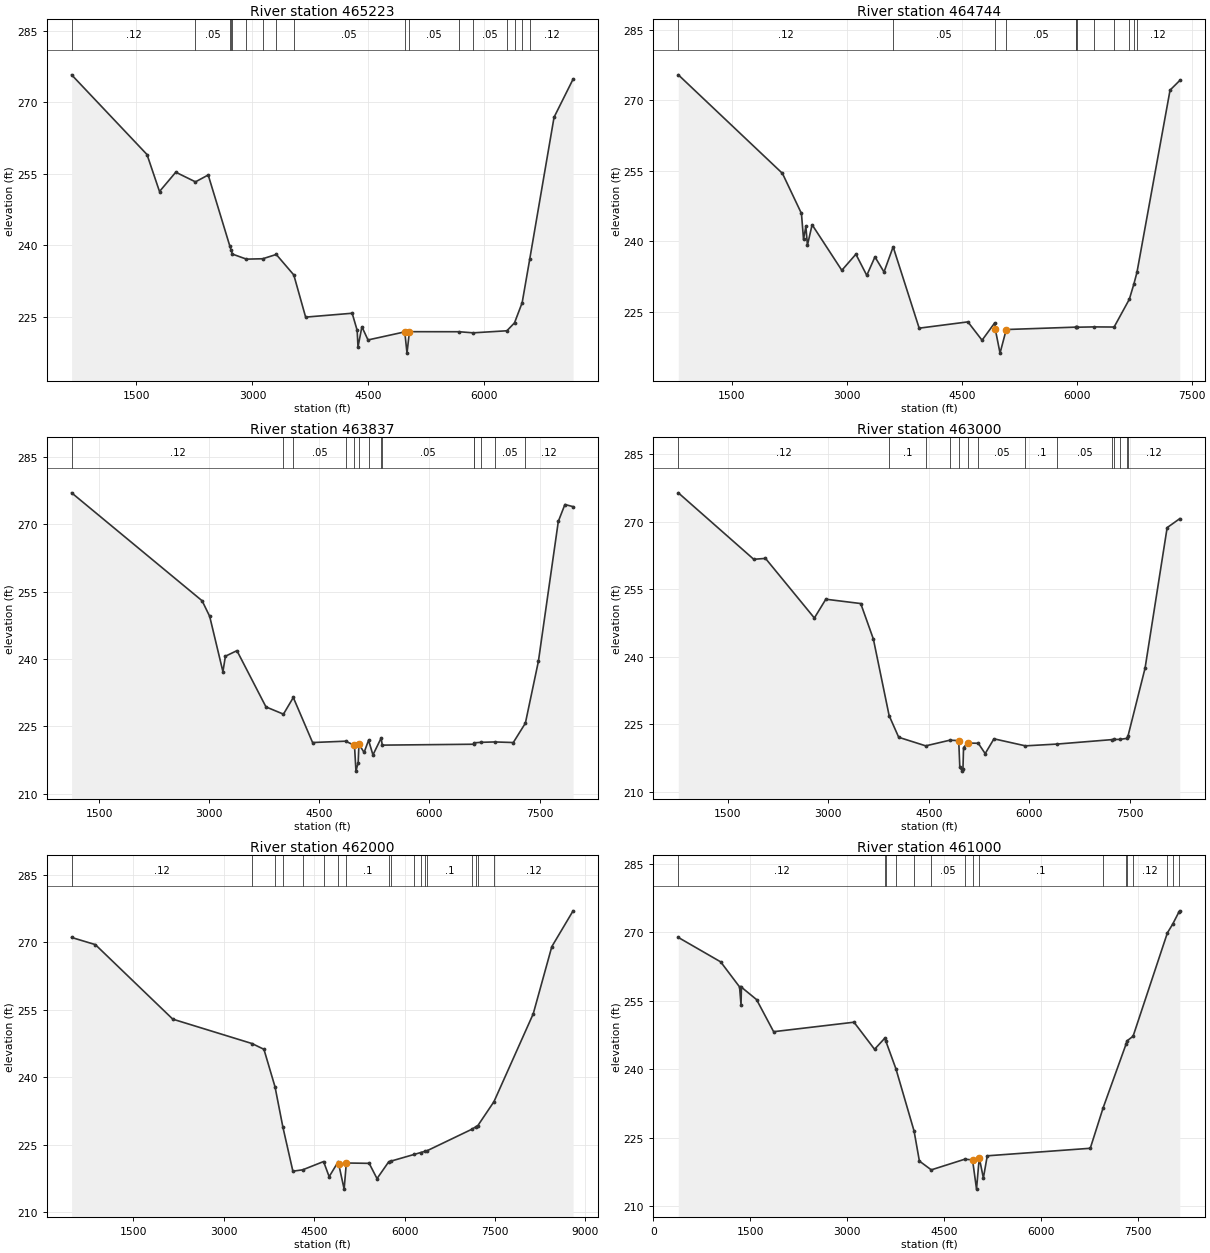
Type RM Length L Ch R = 1 ,465223  ,479,479,479
BEGIN DESCRIPTION:
WFSJ Main 459.0
END DESCRIPTION:
XS GIS Cut Line= 3
      3767592.66     10227821.58      3763454.05     10227215.93
      3761151.84     10227280.14
#Sta/Elev= 30
   661.5  275.72  1636.6  259.03  1798.3  251.29  2008.6  255.33  2263.3  253.31
    2428  254.75  2705.8  239.97  2723.4  239.07  2740.6  238.19  2922.8  237.13
  3133.6  237.21  3308.2  238.11  3535.1  233.82  3688.2  224.99  4290.1   225.8
    4355   222.2  4365.3  218.74  4415.9  222.97  4494.8  220.21  4970.4   221.9
  4999.2  217.45  5030.5  221.94  5671.7  221.93  5854.9   221.7    6291  222.13
  6389.8  223.79  6488.7  228.01  6587.6  237.22  6901.2  266.84  7147.3  274.82
#Mann= 17 ,-1 , 0
   661.5     .12       0  2263.3     .05       0  2705.8     .12       0
  2723.4     .05       0  2740.6     .12       0  2922.8      .1       0
  3133.6     .05       0  3308.2     .12       0  3535.1     .05       0
  4970.4     .04       0  5030.5     .05       0  5671.7      .1       0
  5854.9     .05       0    6291      .1       0  6389.8     .12       0
  6488.7     .05       0  6587.6     .12       0
Bank Sta=4970.4,5030.5
XS Rating Curve= 0 ,0
Exp/Cntr=0.3,0.1

Type RM Length L Ch R = 1 ,464744  ,907,907,907
BEGIN DESCRIPTION:
WFSJ Main 458.0
END DESCRIPTION:
XS GIS Cut Line= 3
       3767620.2     10227683.94      3763756.88     10226903.93
      3761161.37     10227133.22
#Sta/Elev= 30
   798.9  275.44  2158.1  254.44  2406.6  245.89  2433.6   240.4  2464.2  243.15
  2484.6  239.12  2545.8  243.49  2933.5  233.78  3117.3  237.21  3259.4   232.7
  3366.1  236.64  3484.4  233.42  3603.6  238.78  3943.4  221.45  4579.4  222.79
  4764.4  218.88  4929.9  222.58 4937.64  221.19  4999.1  216.13  5080.5  221.16
  5987.2  221.67  5991.9  221.66    5999  221.65  6223.3  221.72  6488.4  221.69
  6687.3  227.62  6746.1  230.84  6786.7  233.34  7218.8  272.18  7345.8  274.24
#Mann= 12 ,-1 , 0
   798.9     .12       0  3603.6     .05       0  4929.9     .04       0
  5080.5     .05       0  5987.2      .1       0  5991.9     .05       0
    5999      .1       0  6223.3     .05       0  6488.4      .1       0
  6687.3     .12       0  6746.1     .05       0  6786.7     .12       0
Bank Sta=4937.64,5080.5
XS Rating Curve= 0 ,0
Exp/Cntr=0.3,0.1

Type RM Length L Ch R = 1 ,463837  ,837,837,837
BEGIN DESCRIPTION:
Mapping XS ab5dca74
END DESCRIPTION:
XS GIS Cut Line= 3
      3767904.68     10227417.82      3764261.59     10226619.46
      3761178.29     10226968.16
#Sta/Elev= 30
    1125  276.99    2903  252.95  3006.1  249.48  3186.6  237.16  3220.4   240.6
  3377.3  241.84  3773.2  229.31  4011.2   227.7  4145.5  231.41  4408.1  221.38
  4858.9  221.68  4979.1  220.74  4999.1  215.01  5029.4  216.92  5039.5  221.04
  5109.9  219.16  5170.9  221.89  5230.7  218.62  5341.8  222.36  5357.8   220.8
  6605.7     221  6608.9  221.31  6708.7  221.43    6890  221.51  7142.9  221.38
  7307.4  225.69  7484.9  239.47  7756.3  270.63  7846.1  274.39  7957.5  273.91
#Mann= 14 ,-1 , 0
    1125     .12       0  4011.2      .1       0  4145.5     .05       0
  4858.9      .1       0  4979.1     .07       0  5039.5      .1       0
  5170.9     .05       0  5341.8      .1       0  5357.8     .05       0
  6605.7      .1       0  6608.9     .05       0  6708.7      .1       0
    6890     .05       0  7307.4     .12       0
Bank Sta=4979.1,5039.5
XS Rating Curve= 0 ,0
Exp/Cntr=0.3,0.1

Type RM Length L Ch R = 1 ,463000  ,1000,1000,1000
BEGIN DESCRIPTION:
WFSJ Main 457.0
END DESCRIPTION:
XS GIS Cut Line= 4
      3768280.92     10227014.04      3764166.29     10225997.25
      3761875.68     10226307.45      3761114.02     10226848.87
#Sta/Elev= 30
   761.6  276.37  1887.5  261.62  2062.7  261.82  2792.3  248.59  2963.2  252.76
  3484.2   251.8  3672.9  243.92  3908.2  226.92    4051  222.12  4454.1  220.22
    4813  221.47  4946.9  221.39  4962.8  215.52  4999.1  214.61    5010  215.11
  5018.6  219.85  5079.2  220.85  5238.7  220.79  5341.5   218.5  5472.7  221.78
    5942  220.22    6419  220.62  7240.6  221.61  7261.9  221.64  7347.9  221.65
  7458.4  221.88  7472.4  222.35  7727.8  237.46  8057.4  268.65    8246  270.64
#Mann= 14 ,-1 , 0
   761.6     .12       0  3908.2      .1       0  4454.1     .05       0
    4813      .1       0  4946.9     .07       0  5079.2      .1       0
  5238.7     .05       0    5942      .1       0    6419     .05       0
  7240.6     .12       0  7261.9     .05       0  7347.9     .12       0
  7458.4     .05       0  7472.4     .12       0
Bank Sta=4946.9,5079.2
XS Rating Curve= 0 ,0
Exp/Cntr=0.3,0.1

Type RM Length L Ch R = 1 ,462000  ,1000,1000,1000
BEGIN DESCRIPTION:
WFSJ Main 456.0
END DESCRIPTION:
XS GIS Cut Line= 3
      3768464.51     10226757.12      3764160.49     10225376.93
      3760655.22     10223921.55
#Sta/Elev= 30
   480.1  271.06   873.5  269.47  2157.9   252.9  3471.4  247.48  3669.1   246.2
  3852.7  237.87  3983.5   228.9  4149.1  219.11  4311.2  219.41    4658  221.25
  4750.7  217.89  4897.8  221.14    4909  220.68    4999  215.12  5035.3  220.93
  5414.2  220.85  5544.2  217.46  5738.6   221.2  5768.7  221.32  6165.1  222.85
  6270.3  223.26  6333.5   223.5  6375.5  223.66    7112   228.4  7180.8  228.96
  7217.2  229.26  7483.7  234.57  8134.6  254.09  8442.6  269.02  8795.4  276.98
#Mann= 18 ,-1 , 0
   480.1     .12       0  3471.4     .05       0  3852.7     .12       0
  3983.5      .1       0  4311.2     .05       0    4658      .1       0
  4897.8     .07       0  5035.3      .1       0  5738.6     .05       0
  5768.7      .1       0  6165.1     .12       0  6270.3      .1       0
  6333.5     .12       0  6375.5      .1       0    7112     .05       0
  7180.8     .12       0  7217.2     .05       0  7483.7     .12       0
Bank Sta=4909,5035.3
XS Rating Curve= 0 ,0
Exp/Cntr=0.3,0.1

Type RM Length L Ch R = 1 ,461000  ,596,596,596
BEGIN DESCRIPTION:
WFSJ Main 455.0
END DESCRIPTION:
XS GIS Cut Line= 3
      3768464.43     10226591.91      3764274.25     10224660.71
      3761380.13     10223435.18
#Sta/Elev= 30
   386.2  268.91  1041.4  263.56  1333.4  258.08  1356.3  254.16  1362.4  258.01
  1596.9  255.29  1860.4  248.26  3103.7  250.34  3421.5  244.41  3577.3   246.8
  3597.8  246.13  3752.2  240.13  4033.1  226.49  4115.2  219.92    4299  217.99
  4818.5  220.33  4937.4  220.17    4999  213.77  5041.2  220.68  5104.7   216.2
  5165.1  221.07  6758.3  222.72  6956.3  231.54  7312.9  245.58  7324.9  246.23
  7420.6  247.27  7951.5  269.92  8032.1   271.8  8130.3  274.51  8142.9  274.74
#Mann= 16 ,-1 , 0
   386.2     .12       0  3577.3     .05       0  3597.8     .12       0
  3752.2     .05       0  4033.1      .1       0    4299     .05       0
  4818.5      .1       0  4937.4     .07       0  5041.2      .1       0
  6956.3     .05       0  7312.9     .12       0  7324.9     .05       0
  7420.6     .12       0  7951.5     .05       0  8032.1     .12       0
  8130.3     .05       0
Bank Sta=4937.4,5041.2
XS Rating Curve= 0 ,0
Exp/Cntr=0.3,0.1

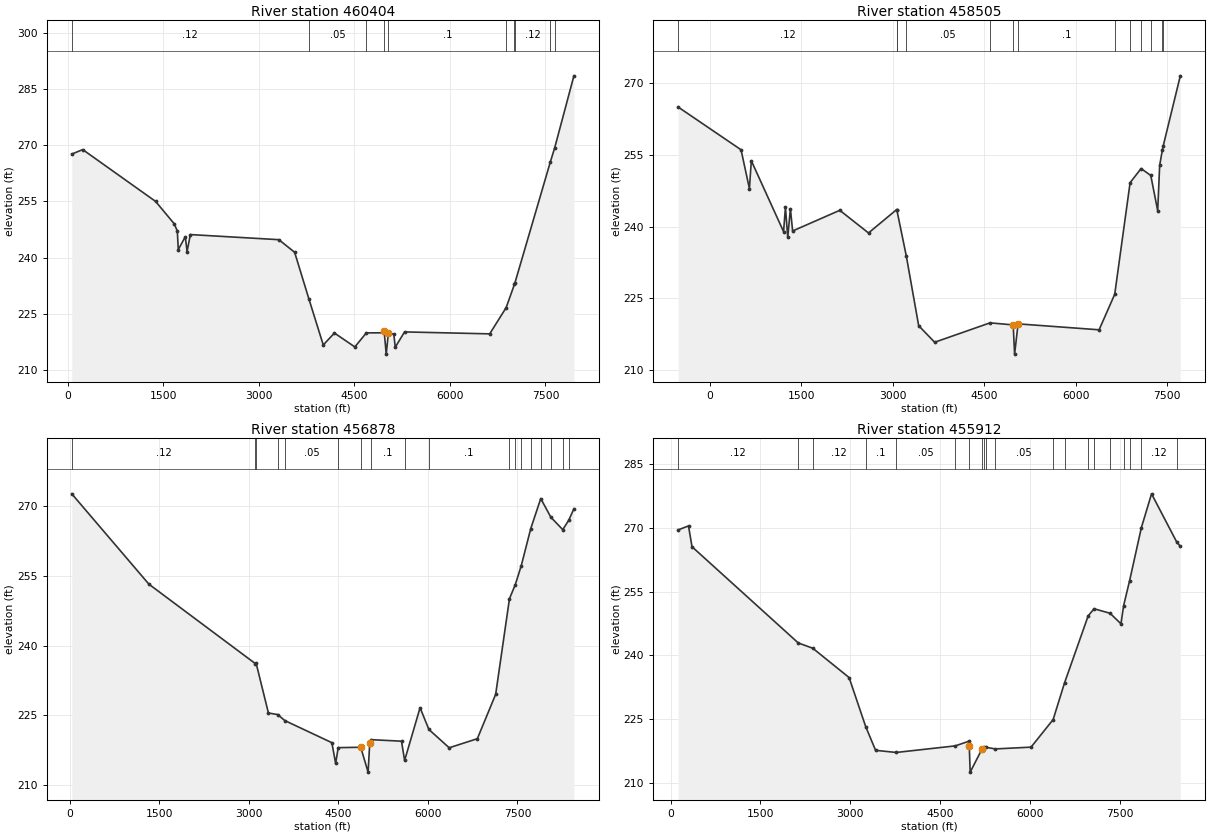
Type RM Length L Ch R = 1 ,460404  ,1899,1899,1899
BEGIN DESCRIPTION:
WFSJ Main 454.0
END DESCRIPTION:
XS GIS Cut Line= 4
      3768620.45     10226546.03      3767390.81     10225995.45
      3764509.36     10224242.72      3761592.03      10223013.4
#Sta/Elev= 30
    60.7  267.62   232.6  268.82  1377.4  255.01  1668.9  249.07  1718.1  247.15
  1733.6  242.19    1844  245.61  1871.2  241.66  1923.5  246.18  3312.6  244.82
  3560.6  241.46  3783.2  229.11  4010.1  216.77  4185.5  219.95  4506.1  216.25
  4686.9  219.99  4956.8  220.01  4966.8  220.36    4999  214.33  5033.4  220.03
  5118.7  219.59  5140.4  216.17    5287  220.25  6623.9  219.73  6882.3  226.71
  7011.9  232.89    7020   233.3    7577  265.57  7644.4  269.27  7946.4  288.47
#Mann= 10 ,-1 , 0
    60.7     .12       0  3783.2     .05       0  4686.9      .1       0
  4956.8     .07       0  5033.4      .1       0  6882.3     .12       0
  7011.9     .05       0    7020     .12       0    7577     .05       0
  7644.4     .12       0
Bank Sta=4966.8,5033.4
XS Rating Curve= 0 ,0
Exp/Cntr=0.3,0.1

Type RM Length L Ch R = 1 ,458505  ,1627,1627,1627
BEGIN DESCRIPTION:
WFSJ Main 453.0
END DESCRIPTION:
XS GIS Cut Line= 5
      3768620.45     10226435.91       3766023.5     10225004.38
      3765968.44     10224389.55      3764224.89     10223370.94
      3761721.29      10222573.1
#Sta/Elev= 30
  -514.7  264.95   515.5  256.03     653  247.92     684  253.74  1212.5  238.94
  1243.4     244    1281  237.74  1324.8  243.73  1360.9  239.07  2134.1  243.39
  2604.6  238.66  3064.9  243.53  3068.3  243.51  3223.6  233.89  3426.8   219.3
  3688.8  215.84  4596.5  219.89  4975.9  219.46    4999  213.36  5056.1  219.68
    6384  218.44    6640  225.86  6892.1  249.16  7071.9  252.11  7231.1  250.66
  7344.4  243.29  7376.6  252.77  7420.5  255.96  7435.8  256.89  7714.9  271.47
#Mann= 13 ,-1 , 0
  -514.7     .12       0  3064.9     .05       0  3068.3     .12       0
  3223.6     .05       0  4596.5      .1       0  4975.9     .07       0
  5056.1      .1       0    6640     .05       0  6892.1      .1       0
  7071.9     .12       0  7231.1     .05       0  7420.5     .12       0
  7435.8     .05       0
Bank Sta=4975.9,5056.1
XS Rating Curve= 0 ,0
Exp/Cntr=0.3,0.1

Type RM Length L Ch R = 1 ,456878  ,966,966,966
BEGIN DESCRIPTION:
WFSJ Main 452.0
END DESCRIPTION:
XS GIS Cut Line= 3
      3769097.67     10226013.81      3765067.85     10222861.07
      3761812.17     10222379.98
#Sta/Elev= 30
    37.4  272.71    1329  253.26  3109.1  236.18  3124.1  236.25  3330.1  225.53
  3485.1  225.19  3604.6   223.9  4392.2  219.14  4455.6  214.68  4498.4  218.07
  4875.5  218.15    4999   212.8  5026.4  218.99  5047.3  219.79  5558.3  219.46
  5610.3  215.31  5869.4  226.67  6016.4  221.99  6356.9  218.04  6828.4     220
  7135.2  229.56  7366.1  250.13  7464.5  253.19  7563.7  257.25  7722.4  265.22
  7889.8  271.69  8059.9  267.66  8258.3     265  8357.5     267    8445  269.48
#Mann= 18 ,-1 , 0
    37.4     .12       0  3109.1     .05       0  3124.1     .12       0
  3485.1      .1       0  3604.6     .05       0  4498.4      .1       0
  4875.5     .07       0  5047.3      .1       0  5610.3     .05       0
  6016.4      .1       0  7366.1     .05       0  7464.5      .1       0
  7563.7     .05       0  7722.4     .12       0  7889.8     .05       0
  8059.9     .12       0  8258.3     .05       0  8357.5     .12       0
Bank Sta=4875.5,5026.4
XS Rating Curve= 0 ,0
Exp/Cntr=0.3,0.1

Type RM Length L Ch R = 1 ,455912  ,912,912,912
BEGIN DESCRIPTION:
WFSJ Main 451.0
END DESCRIPTION:
XS GIS Cut Line= 3
      3769997.01     10223719.67      3765665.61     10222297.28
      3761848.18     10222205.52
#Sta/Elev= 30
   127.4   269.5   299.7  270.44   358.1  265.54  2131.1  242.89  2372.8  241.65
  2978.9  234.75  3256.9  223.17    3421  217.62  3765.5  217.12  4751.5  218.67
  4974.2  219.75  4984.2  218.61    4999  212.49  5194.3  217.86  5221.9  218.43
    5266  218.33  5417.7  217.95  6014.5  218.37  6383.2  224.86  6572.8  233.47
  6967.4  249.26    7066  250.94  7333.1  249.88  7514.9   247.4  7559.3  251.68
    7658  257.49  7855.3  270.03  8025.1  277.99  8447.2  266.59  8504.9  265.64
#Mann= 20 ,-1 , 0
   127.4     .12       0  2131.1     .05       0  2372.8     .12       0
  3256.9      .1       0  3765.5     .05       0  4751.5      .1       0
  4974.2     .07       0  5194.3      .1       0  5221.9     .05       0
    5266      .1       0  5417.7     .05       0  6383.2     .12       0
  6572.8     .05       0  6967.4      .1       0    7066     .05       0
  7333.1     .05       0  7559.3     .12       0    7658     .05       0
  7855.3     .12       0  8447.2     .05       0
Bank Sta=4984.2,5194.3
XS Rating Curve= 0 ,0
Exp/Cntr=0.3,0.1