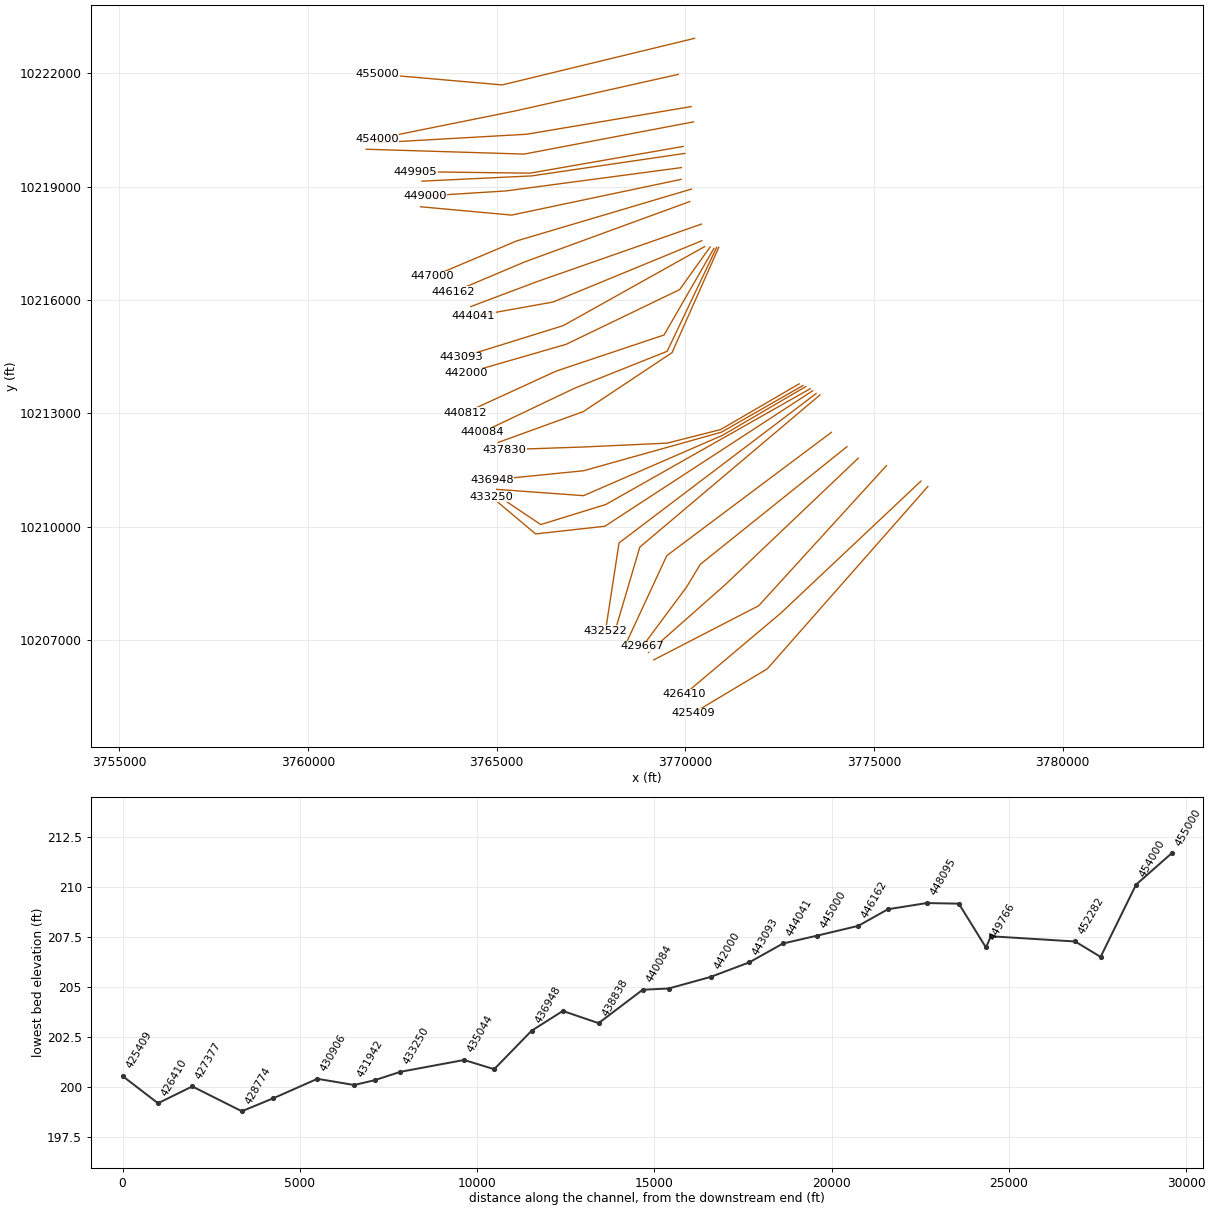
HEC-RAS study WFSJ Main.prj: WFSJ Main Base Level Engineering

--- WFSJ Main.g02 (geometry) --- (continued)

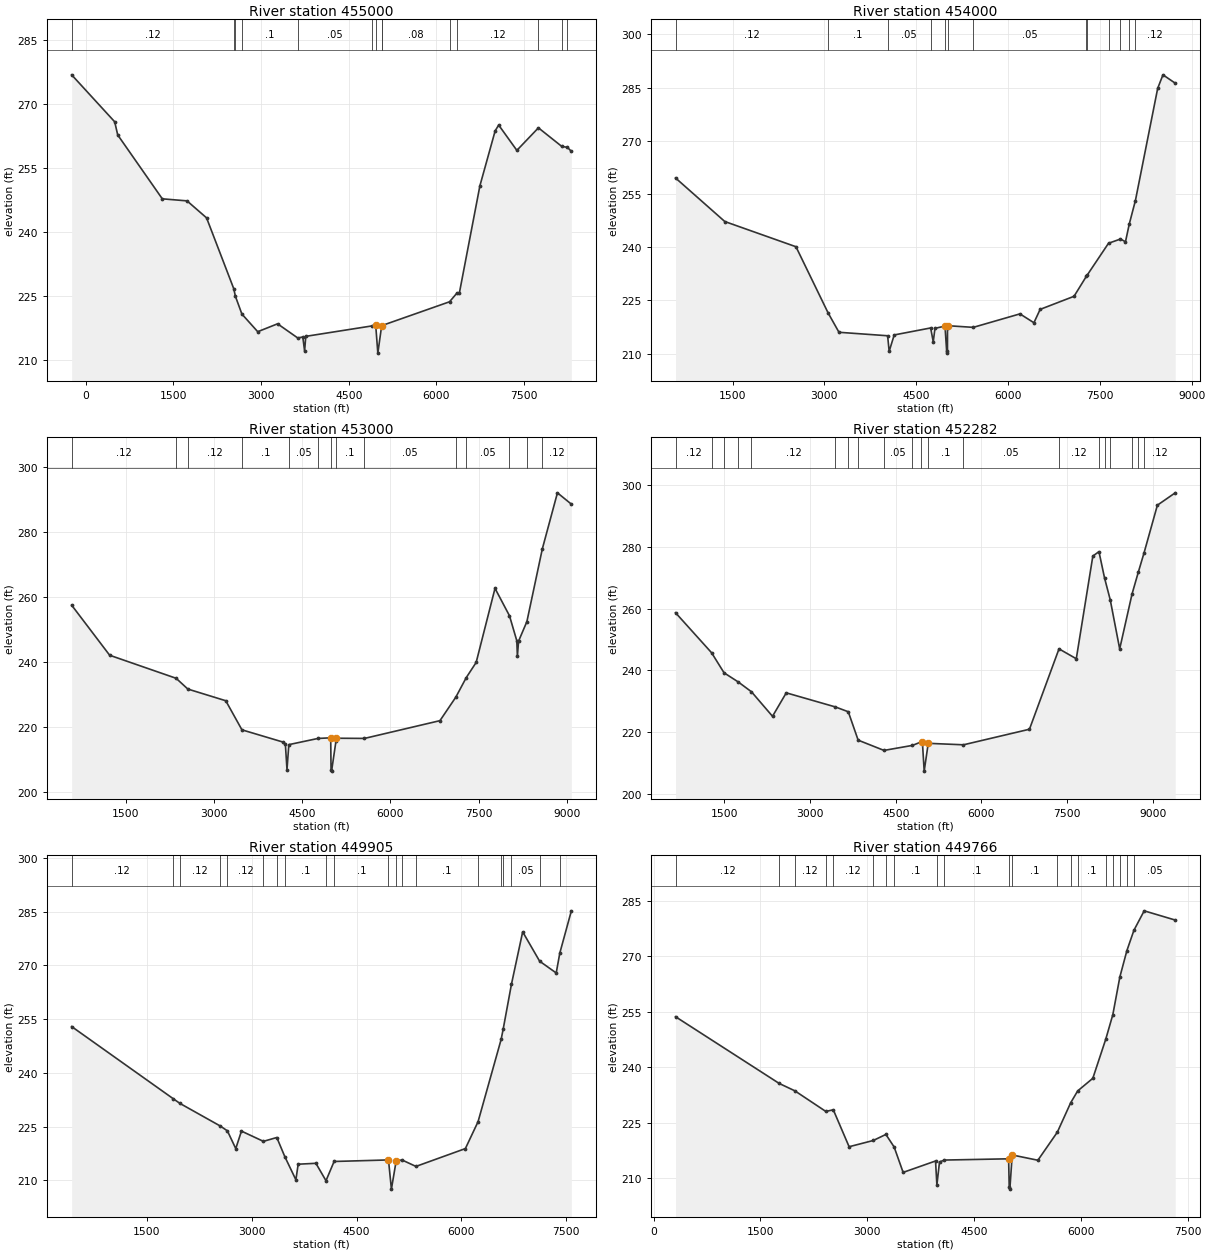
Type RM Length L Ch R = 1 ,455000  ,1000,1000,1000
BEGIN DESCRIPTION:
WFSJ Main 450.0
END DESCRIPTION:
XS GIS Cut Line= 3
      3770244.71     10222930.46      3765148.24     10221696.63
      3761848.14     10221985.28
#Sta/Elev= 30
  -243.7  276.88   493.1  265.88   545.3  262.79  1308.4  247.83  1731.8  247.35
  2066.4  243.37  2531.8  226.78  2560.6  224.98  2671.5  220.83  2942.6   216.7
  3282.2  218.55  3627.8  215.23  3714.3  215.46  3745.2  212.18  3765.2  215.61
  4900.7  218.06  4962.1   218.3    4999  211.68  5064.8  218.12  6226.8  223.71
  6356.8   225.8  6395.7  225.81    6747  250.91    7008  263.76  7068.3  265.11
  7379.4  259.18  7748.8  264.46  8146.6  260.13    8246  259.88  8312.7  258.95
#Mann= 14 ,-1 , 0
  -243.7     .12       0  2531.8      .1       0  2560.6     .12       0
  2671.5      .1       0  3627.8     .05       0  4900.7      .1       0
  4962.1     .07       0  5064.8      .1       0  5064.8     .08       0
  6226.8      .1       0  6356.8     .12       0  7748.8     .05       0
  8146.6     .12       0    8246     .05       0
Bank Sta=4962.1,5064.8
XS Rating Curve= 0 ,0
Exp/Cntr=0.3,0.1

Type RM Length L Ch R = 1 ,454000  ,1000,1000,1000
BEGIN DESCRIPTION:
WFSJ Main 449.0
END DESCRIPTION:
XS GIS Cut Line= 3
      3769813.43      10221976.1      3765488.37     10221007.01
      3761831.28     10220269.56
#Sta/Elev= 30
   567.7  259.53  1372.8  247.24  2535.2  240.13  3061.2  221.43  3237.9     216
  4032.5  215.02  4057.7  210.62  4140.1  215.25  4735.2  217.22  4777.9  213.32
  4805.8  217.11  4969.8  217.75    4999  210.12    5010  210.62  5010.7  217.86
  5431.7  217.39  6194.1  221.19  6422.4  218.69    6524  222.46  7077.7  226.15
  7280.7  231.83  7290.1  232.06    7641  241.11  7836.4   242.3  7918.1  241.53
  7980.2  246.55  8080.2  253.15  8444.1   284.8  8530.2  288.62  8730.7  286.26
#Mann= 13 ,-1 , 0
   567.7     .12       0  3061.2      .1       0  4032.5     .05       0
  4735.2      .1       0  4969.8     .07       0  5010.7      .1       0
  5431.7     .05       0  7280.7      .1       0  7290.1     .05       0
    7641      .1       0  7836.4     .12       0  7980.2     .05       0
  8080.2     .12       0
Bank Sta=4969.8,5010.7
XS Rating Curve= 0 ,0
Exp/Cntr=0.3,0.1

Type RM Length L Ch R = 1 ,453000  ,718,718,718
BEGIN DESCRIPTION:
WFSJ Main 448.0
END DESCRIPTION:
XS GIS Cut Line= 3
      3770152.92     10221122.67      3765792.04     10220390.66
      3761721.31     10220159.23
#Sta/Elev= 30
   578.1  257.51  1224.6  242.12    2355  235.04  2554.3  231.73  3199.3  228.14
  3474.3   219.2  4179.9   215.4  4213.3  214.74  4240.6  207.01  4271.9  214.65
  4767.2  216.55    4984  216.75    4990  207.01    4999  206.51  5074.3  215.82
  5080.1  216.62  5558.3  216.56  6842.4  222.02  7112.8  229.26  7289.1  235.23
  7458.1  239.91  7778.7  262.68  8024.9  254.25  8149.3  246.58  8159.3  241.77
  8179.3  246.45  8320.9  252.46  8583.8  274.83  8840.4  292.03  9077.3  288.55
#Mann= 14 ,-1 , 0
   578.1     .12       0    2355     .05       0  2554.3     .12       0
  3474.3      .1       0  4271.9     .05       0  4767.2      .1       0
    4984     .07       0  5074.3      .1       0  5558.3     .05       0
  7112.8     .12       0  7289.1     .05       0  8024.9      .1       0
  8320.9     .05       0  8583.8     .12       0
Bank Sta=4984,5080.1
XS Rating Curve= 0 ,0
Exp/Cntr=0.3,0.1

Type RM Length L Ch R = 1 ,452282  ,2377,2377,2377
BEGIN DESCRIPTION:
WFSJ Main 447.0
END DESCRIPTION:
XS GIS Cut Line= 3
      3770217.15      10220718.9      3765729.85     10219865.49
      3761545.35     10219993.96
#Sta/Elev= 30
   642.6  258.68  1275.1  245.67  1492.8  239.18  1741.5  236.21  1973.4  233.02
  2341.8  225.07  2582.8  232.68  3442.4  228.11  3669.2  226.54    3842  217.33
    4295     214  4793.8  215.63  4947.7  216.77  4968.1  216.58    4999  207.28
  5069.9   216.3  5687.4  215.82  6843.1  220.87  7360.8  246.95  7663.5  243.74
  7953.6  277.05  8060.5  278.49  8159.4  269.88  8258.3  262.86  8423.8  246.93
    8640  264.73  8751.2   271.9  8851.6  278.15  9084.2  293.56  9396.8  297.57
#Mann= 20 ,-1 , 0
   642.6     .12       0  1275.1     .05       0  1492.8     .12       0
  1741.5      .1       0  1973.4     .12       0  3442.4     .05       0
  3669.2     .12       0    3842      .1       0    4295     .05       0
  4793.8      .1       0  4947.7     .07       0  5069.9      .1       0
  5687.4     .05       0  7360.8     .12       0  8060.5      .1       0
  8159.4     .05       0  8258.3      .1       0    8640     .12       0
  8751.2     .05       0  8851.6     .12       0
Bank Sta=4968.1,5069.9
XS Rating Curve= 0 ,0
Exp/Cntr=0.3,0.1

Type RM Length L Ch R = 1 ,449905  ,139,139,139
BEGIN DESCRIPTION:
WFSJ Main 446.0
END DESCRIPTION:
XS GIS Cut Line= 3
      3769941.89     10220067.37      3765885.85     10219360.78
      3762851.11     10219398.87
#Sta/Elev= 30
   422.5  252.93  1872.9  232.83  1972.4  231.47  2550.6  225.15  2651.5  223.81
  2771.4  218.85  2852.6  223.74  3166.9  220.88  3358.7  221.95  3473.4  216.61
  3631.9  210.14  3664.6   214.5  3918.4  214.75  4062.7  209.89  4178.7  215.26
  4957.1  215.69    4999  207.54  5067.7  215.48  5152.9  215.66  5350.4  213.88
  6057.7  218.86  6239.4  226.38  6569.3  249.32  6600.2  252.36  6717.8  264.81
  6877.8  279.37  7120.5  271.18  7357.8  267.89  7409.4  273.46  7574.6  285.24
#Mann= 20 ,-1 , 0
   422.5     .12       0  1872.9     .05       0  1972.4     .12       0
  2550.6     .05       0  2651.5     .12       0  3166.9     .05       0
  3358.7     .12       0  3473.4      .1       0  4062.7     .05       0
  4178.7      .1       0  4957.1     .07       0  5067.7      .1       0
  5152.9     .05       0  5350.4      .1       0  6239.4     .12       0
  6569.3      .1       0  6600.2     .12       0  6717.8     .05       0
  7120.5     .12       0  7409.4     .05       0
Bank Sta=4957.1,5067.7
XS Rating Curve= 0 ,0
Exp/Cntr=0.3,0.1

Type RM Length L Ch R = 1 ,449766  ,766,766,766
BEGIN DESCRIPTION:
WFSJ Main 445.0
END DESCRIPTION:
XS GIS Cut Line= 3
      3769987.82     10219883.85      3765922.55     10219287.36
      3763022.84     10219148.99
#Sta/Elev= 30
   307.7  253.67  1763.2  235.59  1981.2  233.61  2416.6  228.02  2521.6  228.46
  2743.5  218.46  3082.2  220.15  3259.6  221.79  3375.5  218.38  3501.5  211.51
  3956.3   214.6  3975.2  208.13    4012  214.33  4079.7  214.85  4981.8  215.19
    4990  207.48    4999  206.98  5031.9  216.23  5392.3   214.8  5665.5  222.41
    5852  230.34  5950.6  233.57  6163.2  236.99  6345.2  247.61  6443.9  254.22
  6542.5  264.43  6641.2  271.56  6739.8  277.07    6884  282.34  7319.5  279.84
#Mann= 20 ,-1 , 0
   307.7     .12       0  1763.2     .12       0  1981.2     .12       0
  2416.6     .05       0  2521.6     .12       0  3082.2     .05       0
  3259.6     .12       0  3375.5      .1       0  3975.2     .05       0
  4079.7      .1       0  4981.8     .07       0  5031.9      .1       0
  5665.5      .1       0    5852     .05       0  5950.6      .1       0
  6345.2     .05       0  6443.9     .12       0  6542.5      .1       0
  6641.2     .12       0  6739.8     .05       0
Bank Sta=4981.8,5031.9
XS Rating Curve= 0 ,0
Exp/Cntr=0.3,0.1

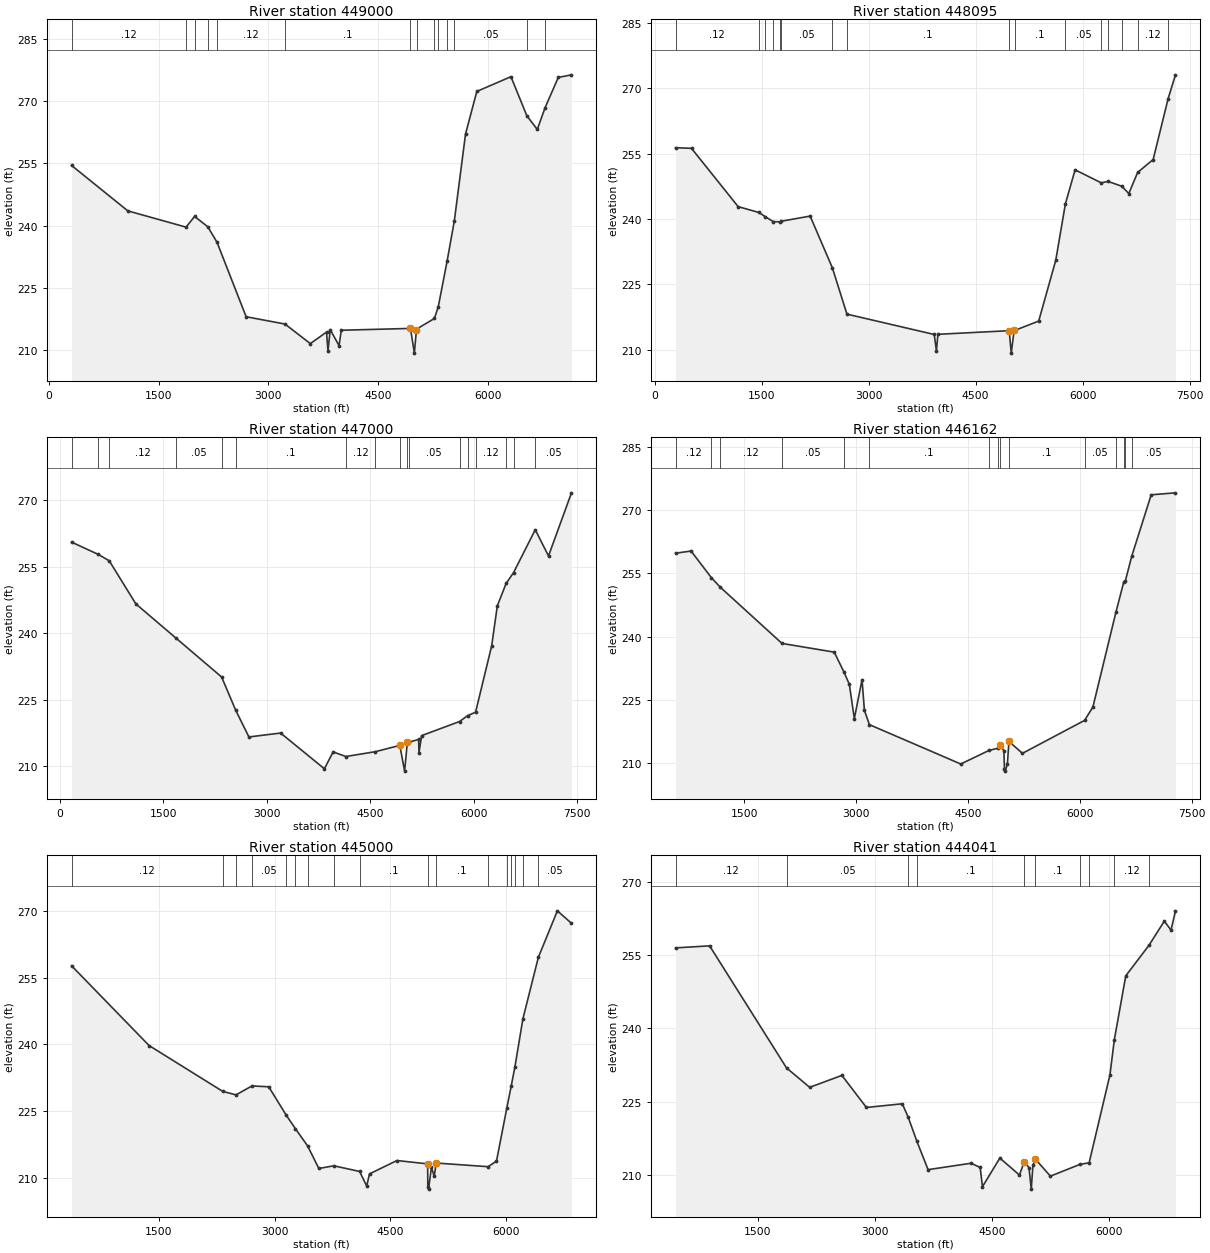
Type RM Length L Ch R = 1 ,449000  ,905,905,905
BEGIN DESCRIPTION:
WFSJ Main 444.0
END DESCRIPTION:
XS GIS Cut Line= 3
      3769895.97     10219507.59      3765245.56     10218889.51
      3763100.99     10218754.84
#Sta/Elev= 30
   308.7  254.52  1078.9  243.54  1875.7  239.61  1992.3   242.2  2173.4  239.69
  2298.9  235.96  2697.6  217.96  3228.8   216.2  3575.3  211.47  3797.2  214.25
  3817.4  209.67  3847.7  214.85  3968.7  210.98    3999   214.7  4946.2  215.14
    4999  209.17  5027.8  214.85  5037.8  215.07  5273.5  217.54  5326.8  220.41
  5447.9  231.47  5546.5  241.19  5699.1   262.1  5853.5   272.4  6320.3  275.96
  6538.6   266.5    6681  263.21  6786.8  268.44  6968.1  275.78  7148.8  276.41
#Mann= 14 ,-1 , 0
   308.7     .12       0  1875.7     .05       0  1992.3     .12       0
  2173.4     .05       0  2298.9     .12       0  3228.8      .1       0
  4946.2     .07       0  5037.8      .1       0  5273.5     .05       0
  5326.8      .1       0  5447.9     .12       0  5546.5     .05       0
  6538.6     .12       0  6786.8     .05       0
Bank Sta=4946.2,5027.8
XS Rating Curve= 0 ,0
Exp/Cntr=0.3,0.1

Type RM Length L Ch R = 1 ,448095  ,1095,1095,1095
BEGIN DESCRIPTION:
WFSJ Main 443.0
END DESCRIPTION:
XS GIS Cut Line= 3
      3769886.88     10219195.61      3765399.49     10218250.41
      3762986.07     10218470.64
#Sta/Elev= 30
   292.3  256.35   516.1   256.2  1170.2  242.82  1461.2  241.48    1549  240.53
  1660.8  239.39  1760.8  239.32  1775.1  239.47  2179.5  240.65    2491  228.78
  2695.2  218.15  3919.2  213.48  3949.9   209.7  3970.3  213.52  4970.2  214.35
    4999   209.2  5040.5   214.6    5048  214.41  5383.8  216.56  5622.9   230.5
  5758.5  243.49    5894  251.27  6260.9  248.28  6355.3  248.61  6549.3   247.5
  6647.1  245.82  6771.1  250.67  6988.5  253.63  7198.9  267.63  7301.6  273.07
#Mann= 16 ,-1 , 0
   292.3     .12       0  1461.2     .05       0    1549     .12       0
  1660.8     .05       0  1760.8     .12       0  1775.1     .05       0
    2491     .12       0  2695.2      .1       0  4970.2     .07       0
    5048      .1       0  5758.5     .05       0  6260.9     .12       0
  6355.3     .05       0  6549.3      .1       0  6771.1     .12       0
  7198.9     .05       0
Bank Sta=4970.2,5040.5
XS Rating Curve= 0 ,0
Exp/Cntr=0.3,0.1

Type RM Length L Ch R = 1 ,447000  ,838,838,838
BEGIN DESCRIPTION:
WFSJ Main 442.0
END DESCRIPTION:
XS GIS Cut Line= 3
      3770162.12     10218938.65      3765533.78     10217566.71
      3763307.19     10216626.14
#Sta/Elev= 30
   172.6  260.59   559.9  257.81   718.6  256.37  1105.3  246.63  1687.2   238.9
  2347.4  230.14    2551  222.65  2742.9   216.6  3201.8  217.49  3836.9  209.42
  3963.2  213.23  4147.6  212.19  4575.3  213.28  4929.9   214.7    4999  208.89
    5039  215.47  5057.3  215.41  5201.8  216.04  5207.2  213.05  5245.3   216.9
  5795.3  220.09  5911.6  221.41  6027.4  222.19  6260.6  237.18  6342.5  246.21
  6470.3  251.26  6576.9  253.68  6892.1  263.38  7084.2  257.46  7417.1  271.71
#Mann= 17 ,-1 , 0
   172.6     .12       0   559.9     .05       0   718.6     .12       0
  1687.2     .05       0  2347.4     .12       0    2551      .1       0
  4147.6     .12       0  4575.3      .1       0  4929.9     .07       0
    5039      .1       0  5057.3     .05       0  5795.3     .12       0
  5911.6     .05       0  6027.4     .12       0  6470.3     .05       0
  6576.9     .12       0  6892.1     .05       0
Bank Sta=4929.9,5039
XS Rating Curve= 0 ,0
Exp/Cntr=0.3,0.1

Type RM Length L Ch R = 1 ,446162  ,1162,1162,1162
BEGIN DESCRIPTION:
WFSJ Main 441.0
END DESCRIPTION:
XS GIS Cut Line= 3
      3770116.25     10218608.29       3765748.2     10217011.57
      3763857.82      10216213.2
#Sta/Elev= 30
   580.5  259.78   788.6   260.3  1061.7  253.96  1178.5  251.74  2007.7  238.37
  2708.1   236.3  2836.9  231.64  2910.5  228.67  2977.6  220.52  3080.9  229.78
  3112.8  222.47  3180.1  219.09  4404.5  209.75  4782.8  212.97    4900  213.49
  4927.5  214.24  4983.3  212.95    4990  208.56    4999  208.06  5029.3  209.67
  5050.6  215.11  5231.2  212.28  6064.2   220.1  6176.1  223.27    6486  245.86
  6591.4  253.05  6610.8  253.17  6696.9  259.07  6957.6  273.64  7283.3  274.11
#Mann= 15 ,-1 , 0
   580.5     .12       0  1061.7     .05       0  1178.5     .12       0
  2007.7     .05       0  2836.9     .12       0  3180.1      .1       0
  4782.8     .12       0    4900      .1       0  4927.5     .07       0
  5050.6      .1       0  6064.2     .05       0    6486      .1       0
  6591.4     .05       0  6610.8     .12       0  6696.9     .05       0
#XS Ineff= 1 ,-1
    2820  3080.9  229.78
Permanent Ineff=
       F
Bank Sta=4927.5,5050.6
XS Rating Curve= 0 ,0
Exp/Cntr=0.3,0.1

Type RM Length L Ch R = 1 ,445000  ,959,959,959
BEGIN DESCRIPTION:
WFSJ Main 440.0
END DESCRIPTION:
XS GIS Cut Line= 3
      3770428.22      10218011.8      3766052.66     10216481.36
      3764316.61     10215827.77
#Sta/Elev= 30
   364.5  257.64  1371.3  239.75    2328  229.47  2500.4   228.7  2706.8   230.7
  2924.7  230.51  3152.5  224.12  3270.3  221.13  3429.1  217.26  3574.9   212.2
  3769.8   212.8  4104.4  211.53  4196.4  208.27  4232.8  210.99  4589.3  213.98
  4987.5  213.23    4990  208.07    4999  207.57  5037.2   212.5  5073.2  210.41
  5098.1  213.42  5772.3   212.6  5881.3  213.84  6016.6  225.84  6071.5   230.6
  6120.6  234.97  6224.5  245.76  6425.3  259.55    6672  269.95    6855  267.16
#Mann= 17 ,-1 , 0
   364.5     .12       0    2328     .05       0  2500.4     .12       0
  2706.8     .05       0  3152.5     .12       0  3270.3     .05       0
  3429.1      .1       0  3769.8     .12       0  4104.4      .1       0
  4987.5     .07       0  5098.1      .1       0  5772.3     .12       0
  6016.6      .1       0  6071.5     .05       0  6120.6      .1       0
  6224.5     .12       0  6425.3     .05       0
Bank Sta=4987.5,5098.1
XS Rating Curve= 0 ,0
Exp/Cntr=0.3,0.1

Type RM Length L Ch R = 1 ,444041  ,948,948,948
BEGIN DESCRIPTION:
WFSJ Main 439.0
END DESCRIPTION:
XS GIS Cut Line= 3
      3770437.45     10217571.35       3766491.5     10215947.09
      3764391.46     10215571.09
#Sta/Elev= 30
   444.8  256.45   880.7  256.87  1865.5  231.94  2162.3  227.97  2574.7  230.41
  2888.3  223.86  3348.2  224.61  3424.7  221.82  3535.7  216.91  3677.8  211.16
  4229.3  212.47  4344.8   211.6  4374.2  207.68    4597  213.52  4847.7  210.06
  4908.7  212.76  4969.6  211.58    4999  207.18  5020.4  212.05  5050.9  213.33
  5243.9  209.83  5621.8  212.23    5740  212.56  6005.9  230.48  6062.9  237.73
    6209  250.75  6506.2  256.98  6702.7  261.92  6788.1  260.08  6845.4  264.02
#Mann= 10 ,-1 , 0
   444.8     .12       0  1865.5     .05       0  3424.7     .12       0
  3535.7      .1       0  4908.7     .07       0  5050.9      .1       0
  5621.8     .12       0    5740     .05       0  6062.9     .12       0
  6506.2     .05       0
Bank Sta=4908.7,5050.9
XS Rating Curve= 0 ,0
Exp/Cntr=0.3,0.1

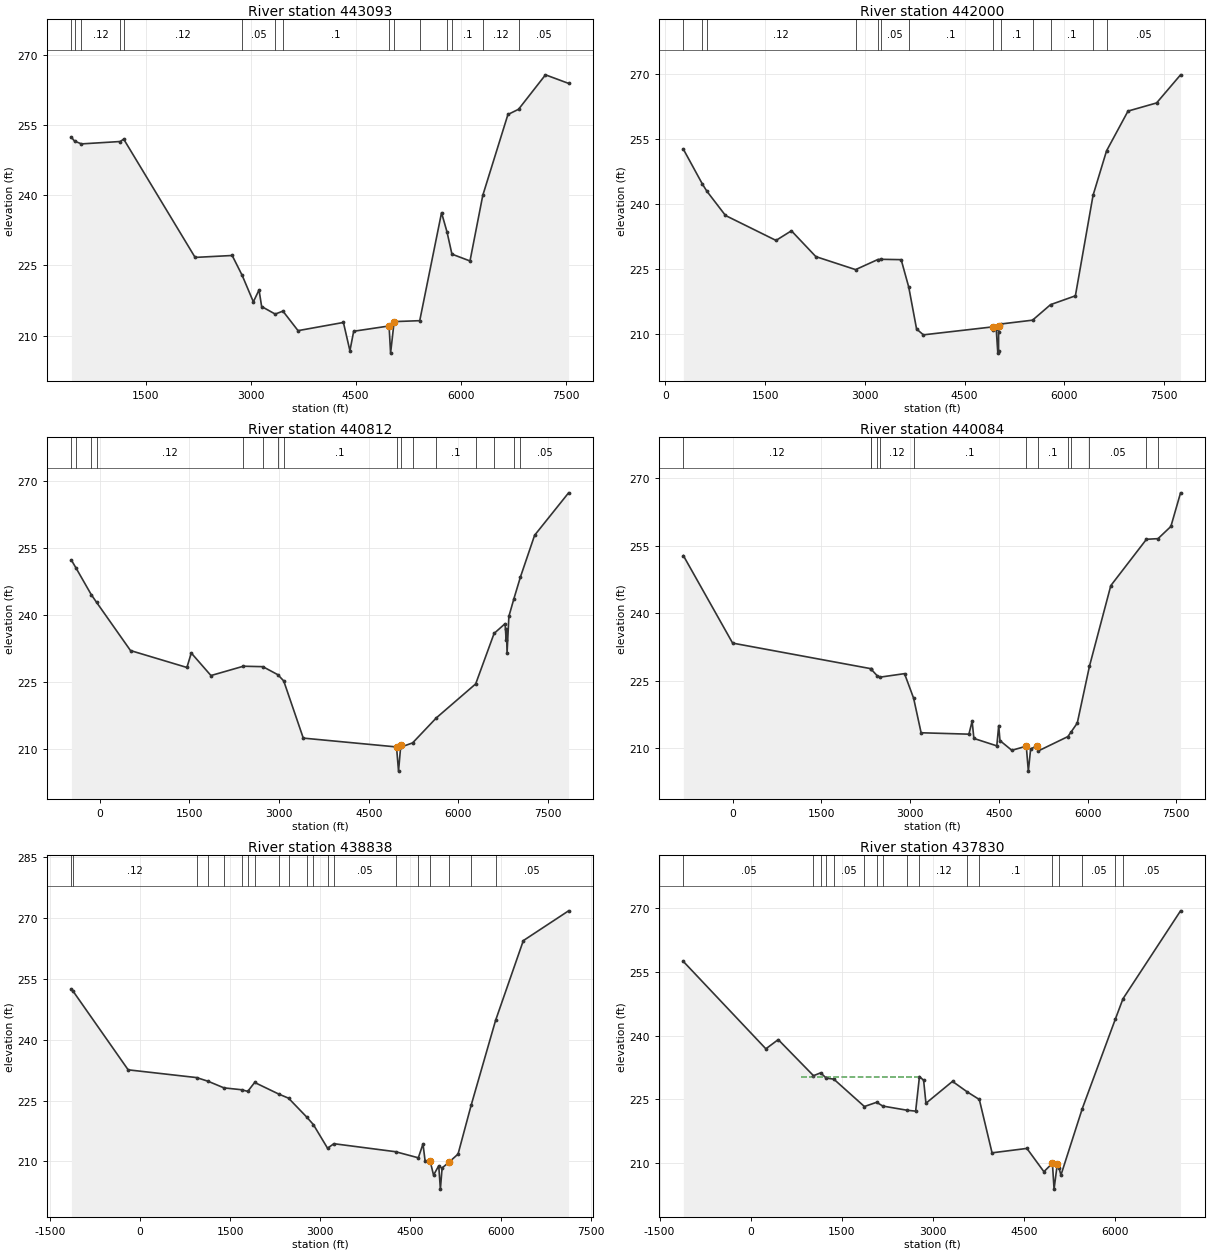
Type RM Length L Ch R = 1 ,443093  ,1093,1093,1093
BEGIN DESCRIPTION:
WFSJ Main 438.0
END DESCRIPTION:
XS GIS Cut Line= 3
      3770510.87     10217415.35       3766766.8     10215323.08
      3764078.11     10214488.02
#Sta/Elev= 30
     438  252.34   483.3  251.51   582.2  250.92  1135.8  251.43  1185.1  251.94
  2205.6  226.68  2735.4  227.09    2878  222.85    3038  217.19  3119.1  219.74
  3156.4  216.19  3349.9  214.58  3460.6  215.21  3676.5  211.04  4324.9  212.79
  4417.8  206.74  4471.5  210.91  4977.2  212.04    4999  206.24  5049.7  212.97
  5415.3  213.17  5727.1  236.23  5805.7  232.08  5875.4  227.38  6133.6  225.92
  6316.5  239.94  6675.6   257.2  6827.2  258.31  7212.3  265.67  7542.4  263.84
#Mann= 15 ,-1 , 0
     438     .12       0   483.3     .05       0   582.2     .12       0
  1135.8     .05       0  1185.1     .12       0    2878     .05       0
  3349.9     .12       0  3460.6      .1       0  4977.2     .07       0
  5049.7      .1       0  5415.3     .05       0  5805.7     .12       0
  5875.4      .1       0  6316.5     .12       0  6827.2     .05       0
#XS Ineff= 1 ,-1
  5727.1    6320  236.23
Permanent Ineff=
       F
Bank Sta=4977.2,5049.7
XS Rating Curve= 0 ,0
Exp/Cntr=0.3,0.1

Type RM Length L Ch R = 1 ,442000  ,1188,1188,1188
BEGIN DESCRIPTION:
WFSJ Main 437.0
END DESCRIPTION:
XS GIS Cut Line= 4
      3770657.69     10217406.19      3769850.13     10216277.44
        3766838.     10214826.65      3764197.69     10214065.98
#Sta/Elev= 30
   268.8  252.59   556.5   244.5   622.9  242.88   902.2  237.29  1662.3  231.53
  1894.1  233.75  2261.6  227.79  2859.5  224.79  3192.7  227.11    3245  227.17
    3545  227.09  3659.2  220.74  3776.8  211.08  3879.1  209.73  4922.5  211.57
  4930.1  210.93  4975.4  211.02    4999  205.51    5010  206.01  5010.6  210.31
    5021  211.84  5052.2  212.25  5521.6  213.12  5791.9   216.7  6165.7  218.74
  6431.5  241.95  6634.7  252.22  6957.3  261.39  7387.3  263.27  7747.7  269.76
#Mann= 13 ,-1 , 0
   268.8     .12       0   556.5     .05       0   622.9     .12       0
  2859.5     .05       0  3192.7     .12       0    3245     .05       0
  3659.2      .1       0  4930.1     .07       0  5052.2      .1       0
  5521.6     .12       0  5791.9      .1       0  6431.5     .12       0
  6634.7     .05       0
Bank Sta=4922.5,5021
XS Rating Curve= 0 ,0
Exp/Cntr=0.3,0.1

Type RM Length L Ch R = 1 ,440812  ,728,728,728
BEGIN DESCRIPTION:
WFSJ Main 436.0
END DESCRIPTION:
XS GIS Cut Line= 4
      3770758.63     10217369.48      3769437.19     10215075.31
      3766583.27     10214120.94      3764161.79      10213011.1
#Sta/Elev= 30
  -475.5  252.22  -400.6  250.51  -142.7  244.47   -52.7  242.73   513.6  231.95
  1457.6  228.16  1530.7   231.4  1859.9  226.35  2402.9  228.44  2728.5  228.34
  2979.1  226.54  3077.6  225.15    3405  212.33  4965.6  210.35    4999  204.93
  5036.6  210.69  5041.8  210.33  5234.8  211.26    5633  216.88  6290.2  224.48
  6598.4  235.79  6782.4  237.98  6799.9  234.31  6805.4  236.82  6815.3   231.4
  6845.9  239.62  6930.3  243.59  7040.1  248.48  7276.4  257.79    7845   267.3
#Mann= 16 ,-1 , 0
  -475.5     .05       0  -400.6     .12       0  -142.7     .05       0
   -52.7     .12       0  2402.9     .05       0  2728.5     .12       0
  2979.1     .05       0  3077.6      .1       0  4965.6     .07       0
  5041.8      .1       0  5234.8     .12       0    5633      .1       0
  6290.2     .12       0  6598.4      .1       0  6930.3     .12       0
  7040.1     .05       0
Bank Sta=4965.6,5036.6
XS Rating Curve= 0 ,0
Exp/Cntr=0.3,0.1

Type RM Length L Ch R = 1 ,440084  ,1246,1246,1246
BEGIN DESCRIPTION:
WFSJ Main 435.0
END DESCRIPTION:
XS GIS Cut Line= 4
      3770832.02     10217396.97      3769519.78     10214644.01
       3767078.8     10213671.29      3764611.55     10212497.28
#Sta/Elev= 30
  -836.2   252.8    -2.9  233.34  2329.2  227.67  2337.5  227.57  2442.1  226.09
  2496.4  225.78  2904.5  226.55  3058.3  221.09  3185.1   213.4    3994  213.09
  4047.9  215.99  4077.9  212.14  4465.4  210.49  4497.7     215  4519.2  211.66
  4719.3   209.5    4964  210.42    4999  204.87  5037.8  209.81  5151.3  210.51
  5163.4  209.34  5667.5  212.55  5724.6  213.62  5826.5  215.56  6032.9  228.21
  6393.8  246.13  6996.7  256.43  7192.4  256.57  7409.7  259.28  7573.5  266.76
#Mann= 13 ,-1 , 0
  -836.2     .12       0  2329.2     .05       0  2337.5     .12       0
  2442.1      .1       0  2496.4     .12       0  3058.3      .1       0
    4964     .07       0  5163.4      .1       0  5667.5     .05       0
  5724.6      .1       0  6032.9     .05       0  6996.7      .1       0
  7192.4     .05       0
Bank Sta=4964,5151.3
XS Rating Curve= 0 ,0
Exp/Cntr=0.3,0.1

Type RM Length L Ch R = 1 ,438838  ,1008,1008,1008
BEGIN DESCRIPTION:
WFSJ Main 434.0
END DESCRIPTION:
XS GIS Cut Line= 4
      3770887.07     10217396.95      3769648.25      10214607.3
      3767299.04     10213047.28      3765042.25      10212230.8
#Sta/Elev= 30
 -1140.1  252.42 -1116.2     252  -195.8  232.56   943.4  230.65  1137.1  229.73
    1398  228.12  1690.2  227.66    1794  227.26    1909  229.45  2313.4  226.57
  2472.2  225.59  2775.6  220.93  2885.6  219.09  3122.2  213.26  3226.4  214.38
  4252.4  212.41  4632.1  210.91  4709.7  214.33  4744.1  210.23  4829.3  210.08
  4885.2  206.66  4971.9  208.94    4999   203.2  5027.9  208.41  5145.1  209.86
  5293.1  211.83  5510.2   223.8  5917.4  244.72  6379.2  264.36  7132.2  271.69
#Mann= 20 ,-1 , 0
 -1140.1     .05       0 -1116.2     .12       0   943.4     .05       0
  1137.1     .12       0    1398     .12       0  1690.2     .05       0
    1794     .12       0    1909     .05       0  2313.4     .12       0
  2472.2     .05       0  2775.6     .12       0  2885.6      .1       0
  3122.2     .12       0  3226.4     .05       0  4252.4     .05       0
  4632.1      .1       0  4829.3     .07       0  5145.1      .1       0
  5510.2     .12       0  5917.4     .05       0
Bank Sta=4829.3,5145.1
XS Rating Curve= 0 ,0
Exp/Cntr=0.3,0.1

Type RM Length L Ch R = 1 ,437830  ,882,882,882
BEGIN DESCRIPTION:
WFSJ Main 433.0
END DESCRIPTION:
XS GIS Cut Line= 5
      3773015.27      10213781.1      3770932.97      10212570.1
      3769519.78     10212212.21      3767279.49      10212109.1
      3765197.61     10212037.86
#Sta/Elev= 30
 -1109.3   257.5   250.1   236.9   453.7  239.07  1034.8  230.56  1153.6  231.24
  1244.1  229.99  1369.5  229.75  1873.7  223.29  2075.4  224.29  2176.3   223.4
  2578.7  222.41  2718.1   222.2  2780.8  230.35  2849.4  229.49  2887.7  224.06
  3325.4  229.22    3570  226.72  3767.3  224.95    3977  212.37  4551.2  213.41
  4831.5  207.92  4971.6  209.91    4999  203.81  5051.7  209.72  5081.7  208.78
  5111.7   207.1  5463.8   222.8  6010.2  243.97  6134.7  248.71  7083.1  269.44
#Mann= 17 ,-1 , 0
 -1109.3     .05       0  1034.8     .12       0  1153.6     .05       0
  1244.1     .12       0  1369.5     .05       0  1873.7     .12       0
  2075.4     .05       0  2176.3     .12       0  2578.7     .05       0
  2780.8     .12       0    3570     .05       0  3767.3      .1       0
  4971.6     .07       0  5081.7      .1       0  5463.8     .05       0
  6010.2     .12       0  6134.7     .05       0
#XS Ineff= 1 ,-1
     835  2779.3  230.36
Permanent Ineff=
       F
Bank Sta=4971.6,5051.7
XS Rating Curve= 0 ,0
Exp/Cntr=0.3,0.1

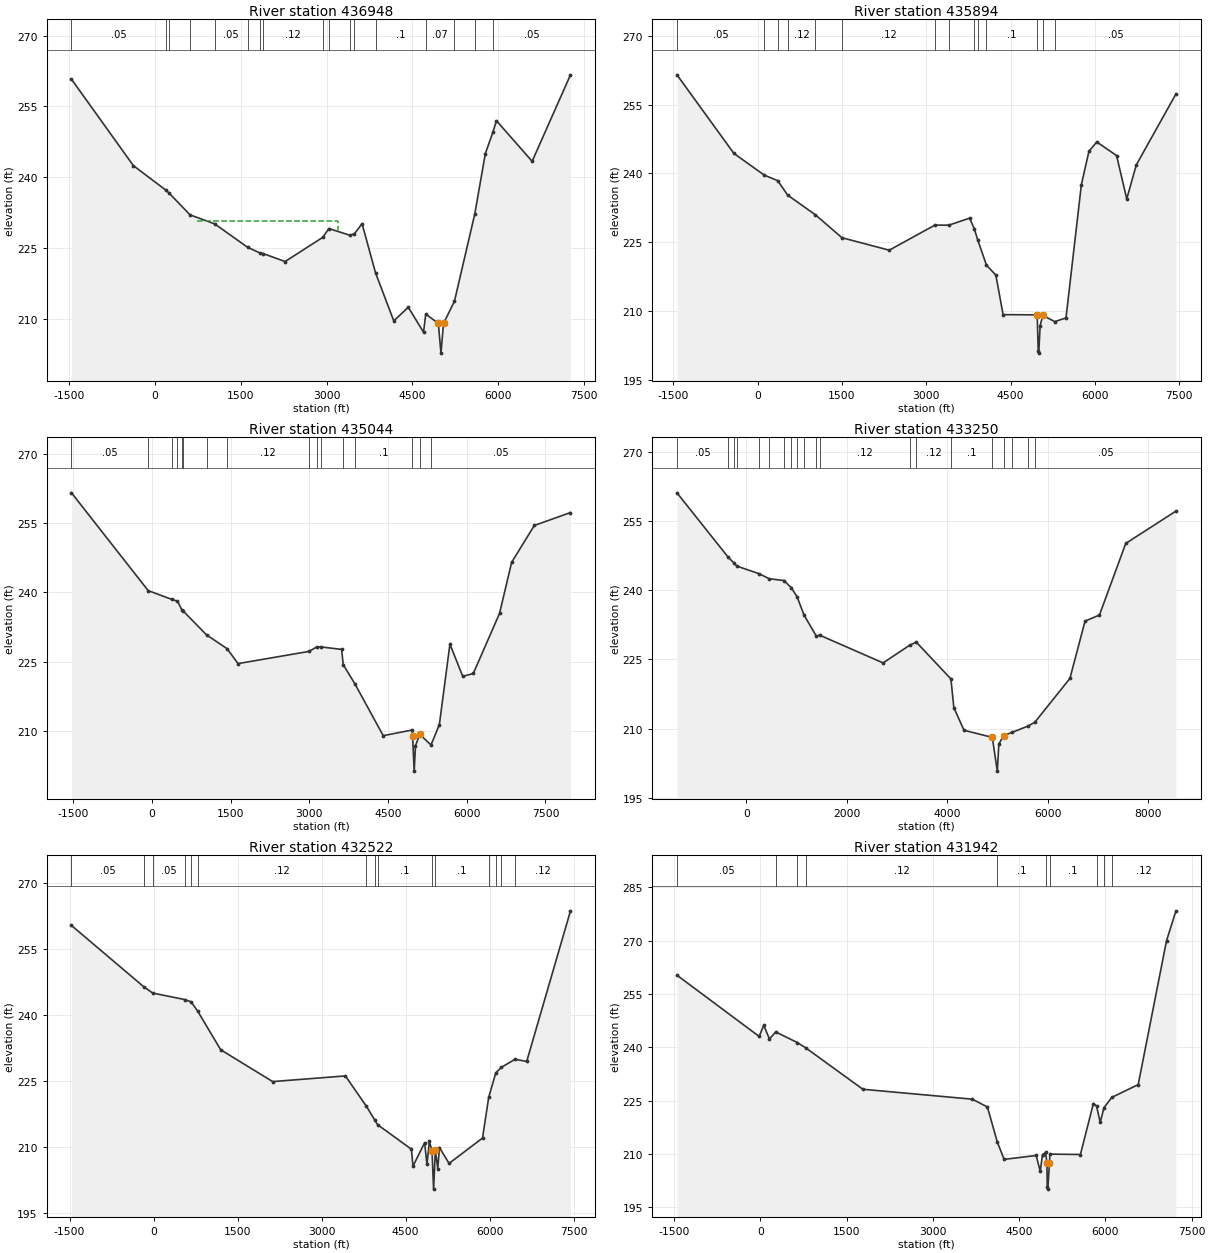
Type RM Length L Ch R = 1 ,436948  ,1054,1054,1054
BEGIN DESCRIPTION:
WFSJ Main 432.0
END DESCRIPTION:
XS GIS Cut Line= 4
      3773115.98     10213737.71      3770956.23     10212501.58
      3767303.45     10211480.75      3764881.32     10211237.84
#Sta/Elev= 30
   -1454  260.76  -373.1  242.49   192.3  237.32   244.6  236.76   616.5  232.07
  1046.7  230.17  1620.7  225.22  1835.8  224.02  1893.3  223.88  2277.3   222.2
  2934.9  227.32  3041.6  229.18  3406.8  227.76  3487.7  228.06    3621  230.21
    3856  219.82  4174.8  209.64  4428.1  212.52  4694.4  207.26  4733.8  211.08
  4953.4  209.11    4999  202.82  5043.9   209.1  5234.9   213.8  5589.1  232.22
  5774.3  245.04  5906.9  249.58  5968.5  251.99  6591.6   243.4  7261.5   261.7
#Mann= 17 ,-1 , 0
   -1454     .05       0   192.3     .12       0   244.6     .05       0
   616.5     .12       0  1046.7     .05       0  1620.7     .12       0
  1835.8     .05       0  1893.3     .12       0  2934.9     .05       0
  3041.6     .12       0  3406.8     .05       0  3487.7     .12       0
    3856      .1       0  4733.8     .07       0  5234.9      .1       0
  5589.1     .12       0  5906.9     .05       0
#XS Ineff= 1 ,-1
     735  3202.9   230.8
Permanent Ineff=
       F
Bank Sta=4953.4,5043.9
XS Rating Curve= 0 ,0
Exp/Cntr=0.3,0.1

Type RM Length L Ch R = 1 ,435894  ,850,850,850
BEGIN DESCRIPTION:
WFSJ Main 431.0
END DESCRIPTION:
XS GIS Cut Line= 4
      3773192.36     10213709.92        3770984.     10212418.25
      3767303.45     10210821.02      3765004.84     10210987.69
#Sta/Elev= 30
 -1435.5  261.46    -423  244.36   116.7  239.64   356.9  238.43   533.3  235.29
  1027.9  230.99  1499.9  226.01  2339.6   223.3  3152.4  228.76  3400.1  228.75
  3769.5  230.27  3854.4  227.93    3913  225.56    4070  220.04  4236.4  217.88
  4365.3  209.28  4971.9  209.23    4990   201.4    4999   200.9  5024.3  206.88
 5071.06  209.12  5284.9  207.75    5484  208.57  5757.6  237.56  5891.9  244.81
  6031.3  246.85  6383.9  243.89  6564.4  234.46  6734.8  241.87  7439.7   257.3
#Mann= 14 ,-1 , 0
 -1435.5     .05       0   116.7     .12       0   356.9     .05       0
   533.3     .12       0  1027.9     .05       0  1499.9     .12       0
  3152.4     .05       0  3400.1     .12       0  3854.4     .05       0
    3913     .12       0    4070      .1       0  4971.9     .07       0
 5071.06      .1       0  5284.9     .05       0
#XS Ineff= 1 ,-1
    1010  3769.5  230.27
Permanent Ineff=
       F
Bank Sta=4971.9,5071.06
XS Rating Curve= 0 ,0
Exp/Cntr=0.3,0.1

Type RM Length L Ch R = 1 ,435044  ,1794,1794,1794
BEGIN DESCRIPTION:
WFSJ Main 430.0
END DESCRIPTION:
XS GIS Cut Line= 4
      3773309.68     10213652.92      3767895.52     10210587.96
      3766170.32     10210055.72      3764941.75     10210880.88
#Sta/Elev= 30
 -1529.9  261.53   -69.4  240.39   378.7   238.5   489.7   238.1   572.6  236.23
   600.7  235.95  1044.8   230.8  1431.7  227.86  1643.8  224.61  2998.1  227.25
  3143.6  228.22  3223.2  228.21    3617  227.68  3646.6  224.39  3867.5  220.27
  4409.3  209.03  4961.3  210.25  4967.9  209.06    4999  201.36    5024  206.85
  5103.8  209.31  5319.6  207.02  5478.7  211.41  5679.9  228.81  5924.2  221.85
  6125.4  222.47  6624.9  235.45  6855.9  246.51  7287.9  254.47    7977  257.27
#Mann= 16 ,-1 , 0
 -1529.9     .05       0   -69.4     .12       0   378.7     .05       0
   489.7     .12       0   572.6     .05       0   600.7     .12       0
  1044.8     .05       0  1431.7     .12       0  2998.1     .05       0
  3143.6     .12       0  3223.2     .05       0  3646.6     .12       0
  3867.5      .1       0  4961.3     .07       0  5103.8      .1       0
  5319.6     .05       0
#XS Ineff= 1 ,-1
  5679.9    6460  228.81
Permanent Ineff=
       F
Bank Sta=4967.9,5103.8
XS Rating Curve= 0 ,0
Exp/Cntr=0.3,0.1

Type RM Length L Ch R = 1 ,433250  ,728,728,728
BEGIN DESCRIPTION:
WFSJ Main 429.0
END DESCRIPTION:
XS GIS Cut Line= 4
      3773373.96     10213597.89      3767867.85     10210011.07
      3766032.67     10209807.95      3764867.28     10210789.82
#Sta/Elev= 30
 -1383.2  261.08  -369.3  247.22  -254.4  245.93  -189.4   245.2   254.1  243.55
   455.1  242.46   752.2  242.07     895   240.5  1009.9  238.56  1149.8  234.57
  1394.6     230  1457.3  230.25  2723.8  224.22  3254.3  228.06  3384.4  228.73
  4075.1  220.75  4133.3  214.53  4335.5  209.63  4899.9  208.08    4999  200.77
  5029.7  206.64  5123.3  208.46  5299.2   209.2  5602.7  210.49  5746.5  211.36
  6445.8  220.86  6747.6  233.28  7034.4   234.6  7558.3  250.12  8558.4  257.12
#Mann= 20 ,-1 , 0
 -1383.2     .05       0  -369.3     .12       0  -254.4     .05       0
  -189.4     .12       0   254.1     .05       0   455.1     .12       0
   752.2     .05       0     895     .12       0  1009.9     .12       0
  1149.8     .12       0  1394.6     .05       0  1457.3     .12       0
  3254.3     .05       0  3384.4     .12       0  4075.1      .1       0
  4899.9     .07       0  5123.3      .1       0  5299.2     .05       0
  5602.7      .1       0  5746.5     .05       0
Bank Sta=4899.9,5123.3
XS Rating Curve= 0 ,0
Exp/Cntr=0.3,0.1

Type RM Length L Ch R = 1 ,432522  ,580,580,580
BEGIN DESCRIPTION:
WFSJ Main 428.0
END DESCRIPTION:
XS GIS Cut Line= 3
      3773465.68     10213524.44      3768244.23     10209569.36
      3767886.34     10207238.46
#Sta/Elev= 30
 -1465.5  260.24  -175.3  246.32   -15.7  244.89   561.7   243.4   670.1  242.89
   787.4  240.78  1197.9  232.01  2125.8  224.78  3424.3  226.07  3800.4  219.16
  3944.5  216.14  3999.6  214.99  4603.5  209.41  4630.7  205.56  4838.7  210.89
  4880.4  206.03    4924  211.18 4970.89  209.03    4999  200.35  5030.2  209.16
  5073.8  205.02  5103.3   209.8  5275.3  206.19  5872.2  211.95  5982.5  221.18
  6109.9  226.79  6209.9  228.02  6453.5  229.85  6661.3  229.36    7443  263.57
#Mann= 15 ,-1 , 0
 -1465.5     .05       0  -175.3     .12       0   -15.7     .05       0
   561.7     .12       0   670.1     .05       0   787.4     .12       0
  3800.4      .1       0  3944.5     .12       0  3999.6      .1       0
 4970.89     .07       0  5030.2      .1       0  5982.5     .12       0
  6109.9      .1       0  6209.9     .05       0  6453.5     .12       0
Bank Sta=4970.89,5030.2
XS Rating Curve= 0 ,0
Exp/Cntr=0.3,0.1

Type RM Length L Ch R = 1 ,431942  ,1036,1036,1036
BEGIN DESCRIPTION:
WFSJ Main 427.0
END DESCRIPTION:
XS GIS Cut Line= 3
      3773566.65     10213487.76      3768794.83     10209459.24
      3768106.58     10207128.37
#Sta/Elev= 30
 -1447.8  260.28   -17.7  243.05    60.3  246.18   160.3  242.37   270.3  244.32
   645.7  241.33   793.5  239.82  1784.4   228.2  3686.6  225.41  3949.3  223.22
  4122.5  213.32  4240.5  208.48  4797.1  209.57  4868.2  205.12  4907.4  209.81
  4962.1  210.43  4984.4   207.5    4990  200.61    4999  200.11    5029  207.53
    5035  209.96  5566.8  209.85  5791.9  224.18  5846.6  223.52  5910.9  218.88
  5976.1  223.02  6112.7  225.92  6571.4  229.51  7063.6  269.99  7227.5  278.39
#Mann= 10 ,-1 , 0
 -1447.8     .05       0   270.3     .12       0   645.7     .05       0
   793.5     .12       0  4122.5      .1       0  4962.1     .07       0
    5035      .1       0  5846.6     .05       0  5976.1      .1       0
  6112.7     .12       0
Bank Sta=4984.4,5029
XS Rating Curve= 0 ,0
Exp/Cntr=0.3,0.1

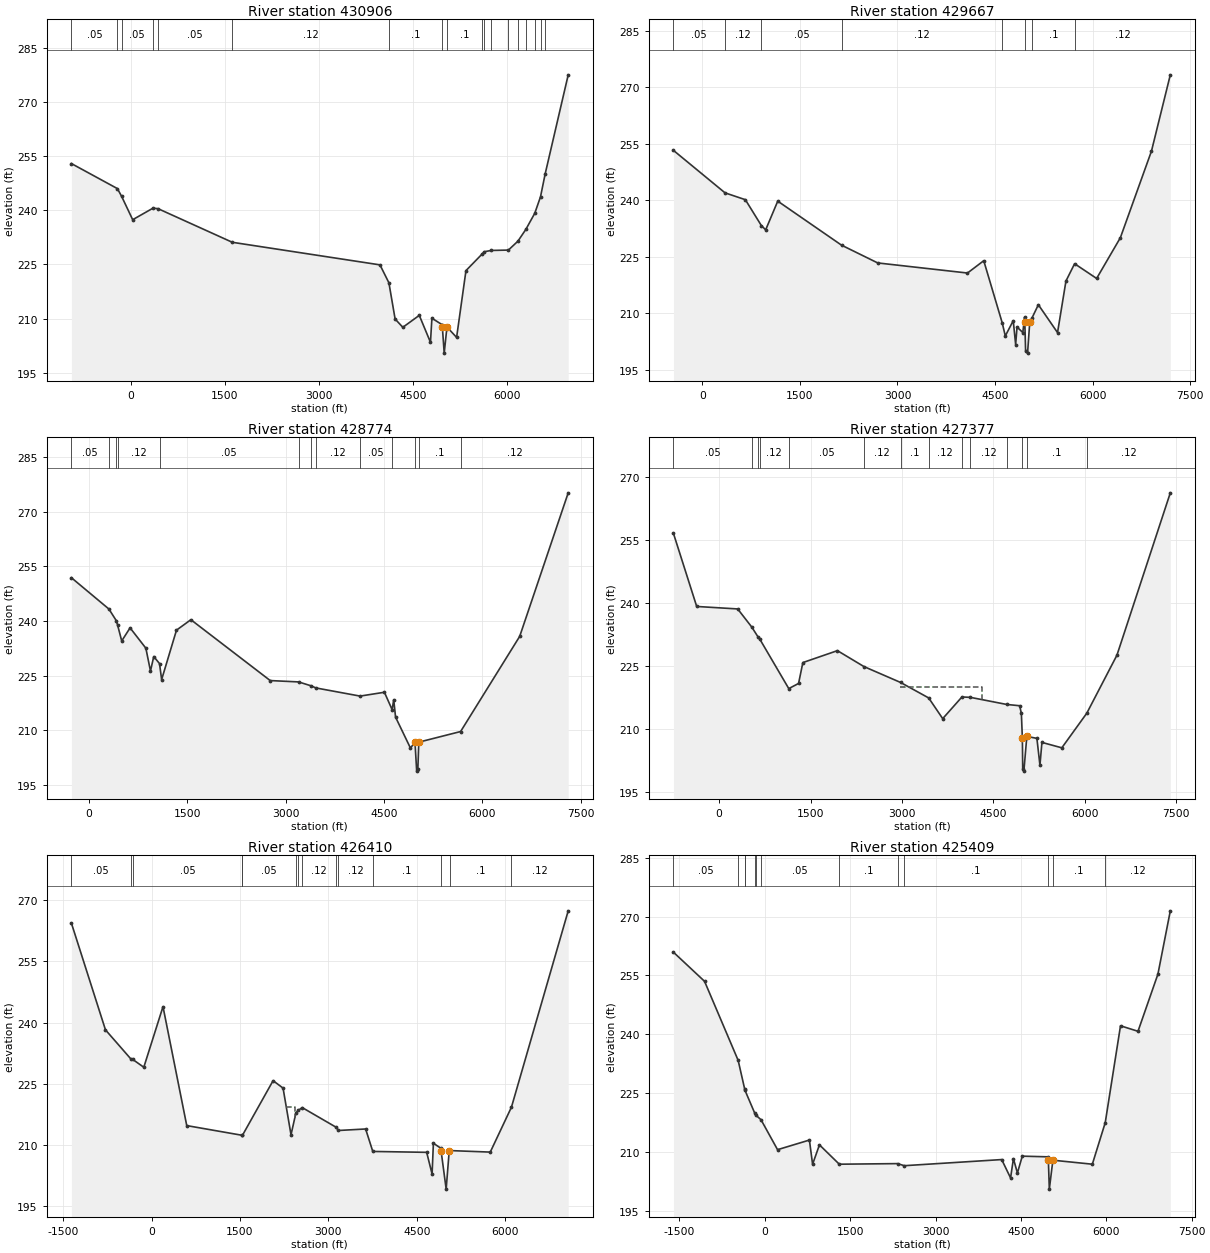
Type RM Length L Ch R = 1 ,430906  ,1239,1239,1239
BEGIN DESCRIPTION:
WFSJ Main 426.0
END DESCRIPTION:
XS GIS Cut Line= 3
      3773870.55     10212498.09      3769508.61     10209232.05
      3768466.97     10206986.02
#Sta/Elev= 30
  -947.9  252.98  -214.3  246.04  -147.2  243.91    29.9  237.41   353.6  240.61
   434.4  240.47    1619  231.15  3974.3  224.89  4116.9  219.92    4216  209.88
    4339  207.58  4601.6  210.89  4779.9  203.42  4802.8   210.1  4963.2  208.33
 4969.89  207.57    4999  200.42  5042.9  207.66  5196.8  204.78  5346.2   223.3
  5608.3  227.98  5639.7  228.54    5750  228.89  6022.9  228.99  6174.3  231.45
  6301.5  234.73  6443.7   239.2  6535.1  243.76  6609.7  250.13  6977.1  277.58
#Mann= 18 ,-1 , 0
  -947.9     .05       0  -214.3     .12       0  -147.2     .05       0
   353.6     .12       0   434.4     .05       0    1619     .12       0
  4116.9      .1       0  4963.2     .07       0  5042.9      .1       0
  5608.3     .12       0  5639.7      .1       0    5750     .12       0
  6022.9     .05       0  6174.3     .12       0  6301.5     .05       0
  6443.7     .12       0  6535.1     .05       0  6609.7     .12       0
Bank Sta=4969.89,5042.9
XS Rating Curve= 0 ,0
Exp/Cntr=0.3,0.1

Type RM Length L Ch R = 1 ,429667  ,893,893,893
BEGIN DESCRIPTION:
WFSJ Main 425.0
END DESCRIPTION:
XS GIS Cut Line= 4
      3774282.92     10212118.35      3770398.36     10209004.19
      3770029.44     10208396.55      3768869.15     10206835.04
#Sta/Elev= 30
  -442.2  253.28   349.9  242.01   662.4  240.19   907.6  233.34   974.4  232.18
  1160.1  239.81  2140.1  228.12  2696.5   223.4    4076  220.72  4325.7  223.99
  4608.9  207.54    4657  204.01  4779.2  208.07    4816  201.73  4837.3  206.38
  4926.2  204.92  4953.6     209 4957.01   207.7  4969.1  199.95    4999  199.45
  5033.1  207.76  5069.9  208.88  5164.9   212.3  5459.7   204.9  5589.1   218.6
  5722.1  223.19  6060.5  219.28  6425.3   230.1  6903.3   253.1  7192.8  273.35
#Mann= 8 ,-1 , 0
  -442.2     .05       0   349.9     .12       0   907.6     .05       0
  2140.1     .12       0  4608.9      .1       0  4953.6     .07       0
  5069.9      .1       0  5722.1     .12       0
Bank Sta=4957.01,5033.1
XS Rating Curve= 0 ,0
Exp/Cntr=0.3,0.1

Type RM Length L Ch R = 1 ,428774  ,1397,1397,1397
BEGIN DESCRIPTION:
WFSJ Main 424.0
END DESCRIPTION:
XS GIS Cut Line= 3
      3774580.82     10211812.64      3771065.22     10208470.65
      3769025.32     10206669.46
#Sta/Elev= 30
  -263.6   251.9   308.4   243.3   420.1  240.13   439.8  238.96   503.5  234.54
   630.9  238.13   871.5  232.55   941.9  226.28   991.6  230.25  1079.8  228.32
  1111.8  223.93  1338.3   237.5  1557.5  240.37  2766.9  223.66  3199.2  223.29
  3392.7   222.2    3462  221.64  4135.9   219.4    4507  220.45  4624.8  215.67
  4648.9  218.42  4676.9  213.63  4903.7  205.14 4973.04  206.71    4999   198.8
    5017  199.48 5031.14  206.75  5668.2  209.67  6568.8  235.79  7308.3   275.2
#Mann= 13 ,-1 , 0
  -263.6     .05       0   308.4     .12       0   420.1     .05       0
   439.8     .12       0  1079.8     .05       0  3199.2     .12       0
  3392.7     .05       0    3462     .12       0  4135.9     .05       0
  4624.8      .1       0 4973.04     .07       0 5031.14      .1       0
  5668.2     .12       0
Bank Sta=4973.04,5031.14
XS Rating Curve= 0 ,0
Exp/Cntr=0.3,0.1

Type RM Length L Ch R = 1 ,427377  ,967,967,967
BEGIN DESCRIPTION:
WFSJ Main 423.0
END DESCRIPTION:
XS GIS Cut Line= 3
      3775329.56     10211617.37      3771944.12     10207906.41
      3769166.33     10206474.11
#Sta/Elev= 30
  -747.6  256.63  -366.8  239.25   305.5  238.66   537.1  234.33   638.5  232.01
   664.8  231.55  1143.4  219.69    1304  220.92  1374.3  225.89  1941.1  228.73
    2376  224.94  2977.7  221.15  3437.9  217.47    3668  212.54  3983.3   217.7
  4121.1  217.61  4716.7  215.92  4930.3  215.61    4958  213.77  4974.6  207.83
  4980.2  200.54    4999  200.04  5047.7  208.31  5212.7  207.84  5262.7  201.44
  5295.2  206.88  5621.5  205.59  6031.3  213.84  6525.5  227.65  7400.9  266.31
#Mann= 14 ,-1 , 0
  -747.6     .05       0   537.1     .12       0   638.5     .05       0
   664.8     .12       0  1143.4     .05       0    2376     .12       0
  2977.7      .1       0  3437.9     .12       0  3983.3      .1       0
  4121.1     .12       0  4716.7      .1       0  4974.6     .07       0
  5047.7      .1       0  6031.3     .12       0
#XS Ineff= 2 ,-1
    2960  4315.4  220.07     750  1941.1  228.73
Permanent Ineff=
       F       F
Bank Sta=4974.6,5047.7
XS Rating Curve= 0 ,0
Exp/Cntr=0.3,0.1

Type RM Length L Ch R = 1 ,426410  ,1001,1001,1001
BEGIN DESCRIPTION:
WFSJ Main 422.0
END DESCRIPTION:
XS GIS Cut Line= 3
        3776241.     10211205.02      3772530.06      10207711.1
       3769981.5      10205563.8
#Sta/Elev= 30
 -1359.7  264.36  -781.5  238.21  -348.4  231.05  -321.4  230.99    -131  229.05
   194.7  243.89   597.7  214.76  1539.5  212.38  1543.1  212.39  2062.3  225.76
  2231.8  223.94  2366.6  212.52  2450.8  217.92  2491.2   218.5  2557.2  219.17
  3136.2  214.32    3169  213.56  3632.5  213.93    3754  208.43  4668.5  208.21
  4760.2  202.89  4782.3  210.44  4909.7  209.21 4914.13  208.45    4999   199.2
 5050.68  208.55  5065.8  208.64  5747.2  208.27  6106.9  219.28  7069.8  267.36
#Mann= 14 ,-1 , 0
 -1359.7     .05       0  -348.4     .12       0  -321.4     .05       0
  1539.5      .1       0  1543.1     .05       0  2450.8     .12       0
  2491.2     .05       0  2557.2     .12       0  3136.2      .1       0
    3169     .12       0    3754      .1       0  4909.7     .07       0
  5065.8      .1       0  6106.9     .12       0
#XS Ineff= 2 ,-1
     350  2062.3  225.76    2280  2430.1  219.33
Permanent Ineff=
       F       F
Bank Sta=4914.13,5050.68
XS Rating Curve= 0 ,0
Exp/Cntr=0.3,0.1

Type RM Length L Ch R = 1 ,425409  ,948,948,948
BEGIN DESCRIPTION:
WFSJ Main 421.0
END DESCRIPTION:
XS GIS Cut Line= 3
      3776425.49     10211063.99      3772171.99      10206235.4
      3770202.04     10205056.55
#Sta/Elev= 30
 -1605.6  260.91 -1059.5   253.5    -469  233.36  -353.6     226  -350.5  225.78
  -179.7  219.98  -164.3  219.49   -67.4  218.24   223.1  210.61   782.9  213.06
   838.9   206.9   959.4  211.84    1308  206.91  2331.7  207.06  2450.1  206.53
  4162.2  208.09  4317.8  203.41    4368  208.32  4438.3  204.67  4523.6  208.96
  4973.9  208.79  4981.8  208.03    4999  200.56  5061.5  207.93  5754.7  206.91
  5981.5   217.5  6249.8  242.17  6557.1  240.77  6907.2  255.33    7125  271.46
#Mann= 13 ,-1 , 0
 -1605.6     .05       0    -469     .12       0  -353.6     .05       0
  -350.5     .12       0  -179.7     .05       0  -164.3     .12       0
   -67.4     .05       0    1308      .1       0  2331.7     .12       0
  2450.1      .1       0  4973.9     .07       0  5061.5      .1       0
  5981.5     .12       0
Bank Sta=4981.8,5061.5
XS Rating Curve= 0 ,0
Exp/Cntr=0.3,0.1