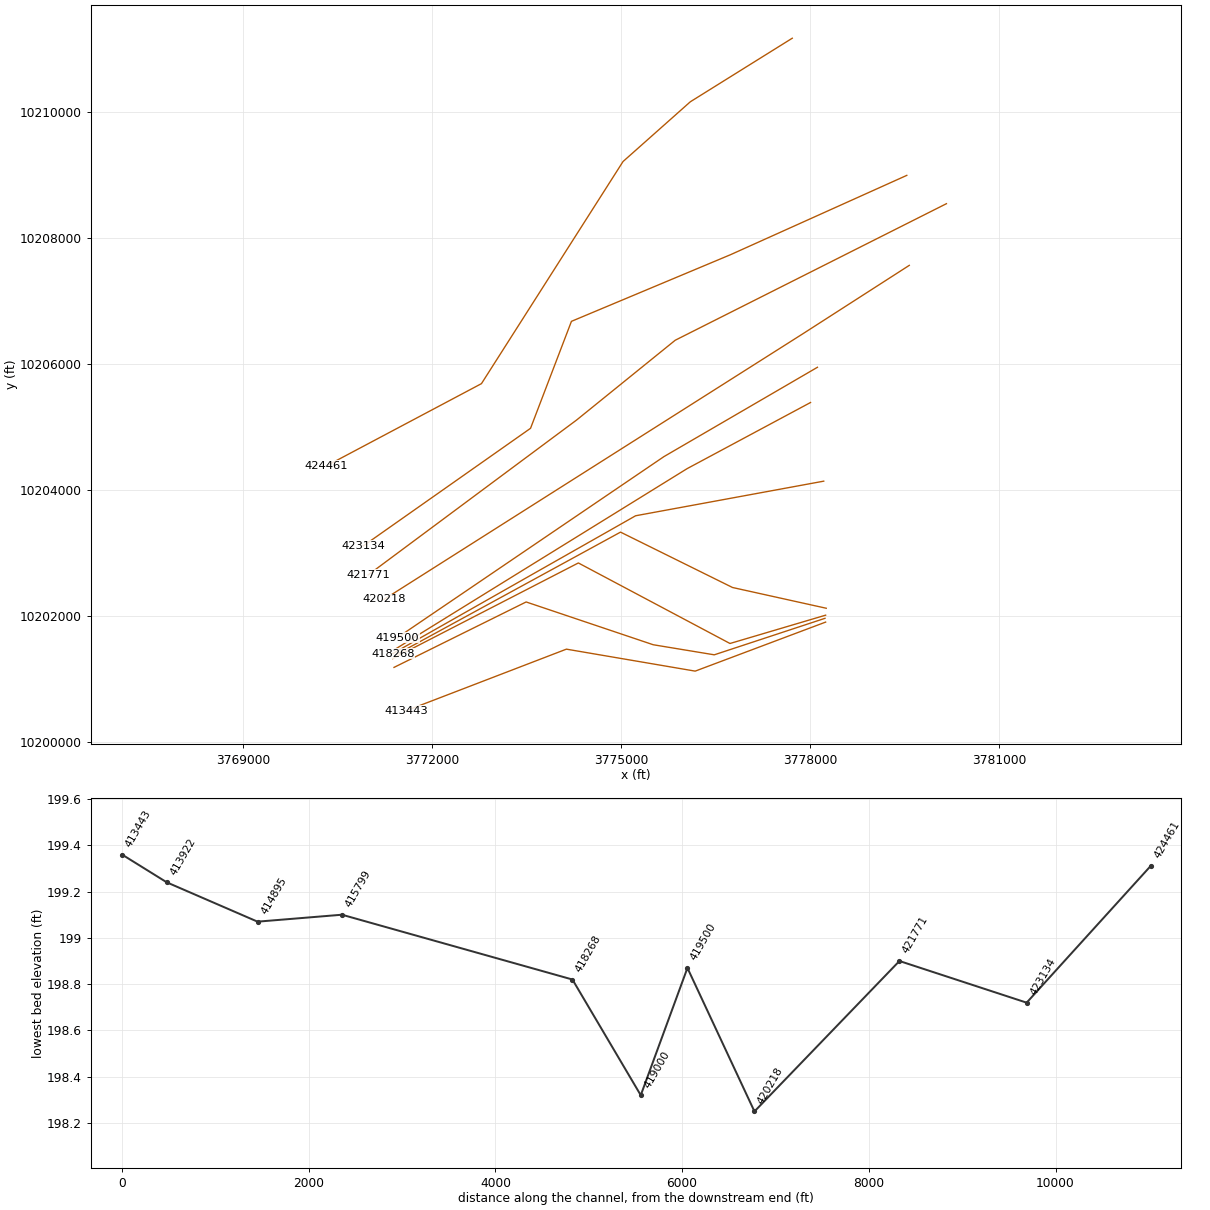
HEC-RAS study WFSJ Main.prj: WFSJ Main Base Level Engineering

--- WFSJ Main.g02 (geometry) --- (continued)

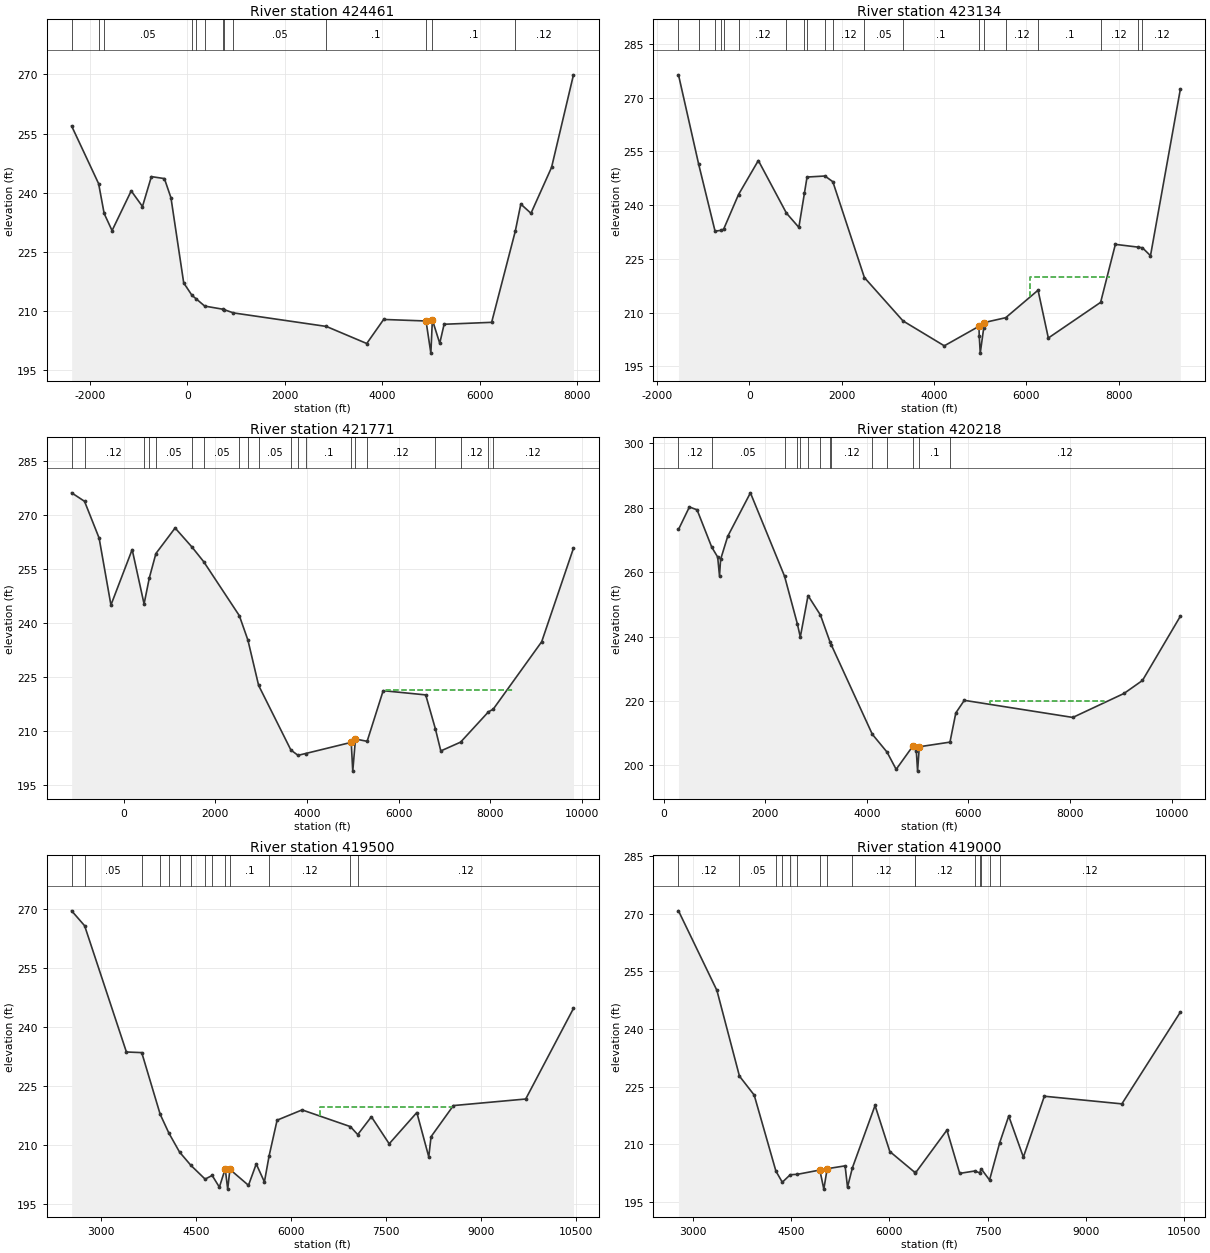
Type RM Length L Ch R = 1 ,424461  ,1327,1327,1327
BEGIN DESCRIPTION:
WFSJ Main 420.0
END DESCRIPTION:
XS GIS Cut Line= 5
      3777717.54     10211165.08      3776100.37     10210156.84
      3775032.23     10209208.49      3772786.14     10205684.62
      3770321.64     10204377.54
#Sta/Elev= 30
   -2376   256.9 -1821.9  242.28 -1708.3  234.72 -1545.9  230.38   -1153  240.45
  -921.7  236.49  -738.8  244.07  -471.7  243.57  -336.7   238.7     -75  217.11
    93.7  213.98   181.1  213.07     356  211.24   731.1  210.44     747  210.37
   946.1  209.51    2853  206.08  3682.5  201.75  4029.6  207.85  4899.6  207.46
    4999  199.31    5030  207.74  5181.2   201.8  5270.8  206.63  6246.8  207.12
  6731.2  230.18  6845.6   237.1  7054.2  234.77    7477  246.41  7926.6  269.88
#Mann= 13 ,-1 , 0
   -2376     .05       0 -1821.9      .1       0 -1708.3     .05       0
    93.7     .12       0   181.1     .05       0     356     .12       0
   731.1     .05       0     747     .12       0   946.1     .05       0
    2853      .1       0  4899.6     .07       0    5030      .1       0
  6731.2     .12       0
Bank Sta=4899.6,5030
XS Rating Curve= 0 ,0
Exp/Cntr=0.3,0.1

Type RM Length L Ch R = 1 ,423134  ,1363,1363,1363
BEGIN DESCRIPTION:
WFSJ Main 419.0
END DESCRIPTION:
XS GIS Cut Line= 5
      3779534.43     10208988.89      3776739.26     10207731.06
      3774213.65      10206672.9      3773564.78     10204975.85
      3770909.42     10203109.11
#Sta/Elev= 30
 -1535.1   276.4 -1098.6  251.48  -743.7  232.78  -620.4  232.97  -557.2  233.32
  -235.4  242.98   193.8  252.48   802.1   237.8    1071  233.82    1192  243.37
  1248.6  247.87  1636.3  248.16  1807.2  246.56  2489.9  219.82  3326.7  207.71
  4220.4  200.76  4971.1  206.21  4976.9  203.62    4999  198.72  5073.3  205.69
  5080.6  207.24  5549.8  208.61  6250.4  216.28  6473.1  202.94  7605.2  212.89
  7924.6  229.08  8410.3  228.32  8511.5  228.12  8685.2  225.91  9331.1  272.35
#Mann= 20 ,-1 , 0
 -1535.1     .05       0 -1098.6     .12       0  -743.7      .1       0
  -620.4     .12       0  -557.2      .1       0  -235.4     .12       0
   802.1     .12       0    1192     .05       0  1248.6     .12       0
  1636.3     .05       0  1807.2     .12       0  2489.9     .05       0
  3326.7      .1       0  4976.9     .07       0  5073.3      .1       0
  5549.8     .12       0  6250.4      .1       0  7605.2     .12       0
  8410.3      .1       0  8511.5     .12       0
#XS Ineff= 1 ,-1
  6085.1    7800  220.01
Permanent Ineff=
       F
Bank Sta=4971.1,5080.6
XS Rating Curve= 0 ,0
Exp/Cntr=0.3,0.1

Type RM Length L Ch R = 1 ,421771  ,1553,1553,1553
BEGIN DESCRIPTION:
WFSJ Main 418.0
END DESCRIPTION:
XS GIS Cut Line= 4
      3780163.27     10208539.64      3775860.79     10206373.42
      3774293.51     10205105.63      3770989.23     10202649.88
#Sta/Elev= 30
 -1135.1  276.08  -853.9  273.73  -535.6  263.54  -277.4  244.96   185.7  260.34
   445.6  245.26   559.9  252.48   703.9  259.25  1122.9  266.33    1493  261.01
  1747.9  256.96  2523.7  242.02  2711.1  235.24  2945.1  222.67  3649.3  204.75
  3804.5  203.28  3968.6  203.78  4965.6  206.88    4999   198.9  5058.3   207.8
  5312.6  207.17  5662.7  221.21  6590.6  220.04  6800.6  210.68  6920.2   204.5
  7351.9  206.94  7958.5  215.33  8063.2  216.07    9121  234.78  9814.7  260.72
#Mann= 20 ,-1 , 0
 -1135.1     .05       0  -853.9     .12       0   445.6      .1       0
   559.9      .1       0   703.9     .05       0    1493     .05       0
  1747.9     .05       0  2523.7     .05       0  2711.1     .12       0
  2945.1     .05       0  3649.3     .05       0  3804.5     .12       0
  3968.6      .1       0  4965.6     .07       0  5058.3      .1       0
  5312.6     .12       0  6800.6      .1       0  7351.9     .12       0
  7958.5      .1       0  8063.2     .12       0
#XS Ineff= 1 ,-1
  5727.1    8500  221.28
Permanent Ineff=
       F
Bank Sta=4965.6,5058.3
XS Rating Curve= 0 ,0
Exp/Cntr=0.3,0.1

Type RM Length L Ch R = 1 ,420218  ,718,718,718
BEGIN DESCRIPTION:
WFSJ Main 417.0
END DESCRIPTION:
XS GIS Cut Line= 3
       3779574.3     10207561.34      3777897.25     10206483.23
      3771238.82     10202260.57
#Sta/Elev= 30
   292.8  273.23   507.2  280.22   658.5  279.34   945.8  267.81    1064  264.68
  1100.3  258.81  1121.4  263.93  1260.8  271.07  1708.6  284.61  2381.4   258.7
  2631.9     244  2690.5  239.85    2843  252.72  3086.7   246.7  3276.5   238.3
  3299.5  237.48  4107.6   209.7  4397.9  204.15  4577.5   198.8  4911.3  206.14
  4974.8   204.4    4999  198.25    5033  205.81  5636.7  207.25  5751.8  216.31
  5918.7  220.22  8054.6  214.91    9062  222.35  9426.1  226.39   10171   246.3
#Mann= 14 ,-1 , 0
   292.8     .12       0   945.8     .05       0  2381.4     .12       0
  2631.9     .05       0  2690.5     .12       0    2843     .05       0
  3086.7     .12       0  3276.5     .05       0  3299.5     .12       0
  4107.6     .05       0  4397.9      .1       0  4911.3     .07       0
    5033      .1       0  5636.7     .12       0
#XS Ineff= 1 ,-1
  6425.3    8660   220.1
Permanent Ineff=
       F
Bank Sta=4911.3,5033
XS Rating Curve= 0 ,0
Exp/Cntr=0.3,0.1

Type RM Length L Ch R = 1 ,419500  ,500,500,500
BEGIN DESCRIPTION:
WFSJ Main 416.0
END DESCRIPTION:
XS GIS Cut Line= 3
       3778116.9     10205944.19       3775681.1     10204526.63
      3771448.45     10201651.63
#Sta/Elev= 30
  2531.3  269.65  2736.6  265.86  3397.3  233.75  3639.9  233.59  3931.7  217.89
  4069.4  213.11    4238  208.29  4418.5  204.89  4641.9  201.42  4753.6  202.35
  4867.4  199.37  4959.9  204.05    4999  198.87  5033.9  203.89  5327.6  199.84
  5450.2  205.27  5579.5  200.71  5653.9  207.34  5780.2  216.41  6175.5  219.02
  6938.8  214.77  7055.1  212.74  7271.1  217.28  7552.5   210.4  7989.7  218.35
  8178.3  207.08  8214.2   212.2  8567.5  220.12  9711.2  221.79 10466.3  244.83
#Mann= 14 ,-1 , 0
  2531.3     .12       0  2736.6     .05       0  3639.9     .12       0
  3931.7     .05       0  4069.4     .12       0    4238     .05       0
  4418.5     .12       0  4641.9     .05       0  4753.6      .1       0
  4959.9     .07       0  5033.9      .1       0  5653.9     .12       0
  6938.8      .1       0  7055.1     .12       0
#XS Ineff= 1 ,-1
  6465.7    8565  219.64
Permanent Ineff=
       F
Bank Sta=4959.9,5033.9
XS Rating Curve= 0 ,0
Exp/Cntr=0.3,0.1

Type RM Length L Ch R = 1 ,419000  ,732,732,732
BEGIN DESCRIPTION:
WFSJ Main 415.0
END DESCRIPTION:
XS GIS Cut Line= 3
      3778007.07     10205385.15      3776049.24     10204336.04
      3771418.49     10201471.93
#Sta/Elev= 30
  2778.8  270.79  3365.9  250.06  3709.9  227.75  3935.1  222.82  4267.1  203.01
  4364.6  200.12  4486.5  202.07  4596.3  202.18  4937.8  203.29    4999  198.32
 5050.35  203.64  5324.1  204.38  5360.7  198.83  5435.2  203.86  5781.5   220.1
  6007.2  208.11  6385.8  202.73  6396.8  202.49  6879.5  213.69  7074.5  202.42
  7303.8  203.04  7378.5  202.57  7405.1  203.56  7530.5  200.69  7685.3  210.38
  7823.6  217.35  8047.3  206.65  8367.6  222.51    9552  220.52 10444.9   244.4
#Mann= 16 ,-1 , 0
  2778.8     .12       0  3709.9     .05       0  4267.1     .12       0
  4364.6     .05       0  4486.5     .12       0  4596.3      .1       0
  4937.8     .07       0 5050.35      .1       0  5435.2     .12       0
  6385.8      .1       0  6396.8     .12       0  7303.8     .05       0
  7378.5     .12       0  7405.1      .1       0  7530.5     .05       0
  7685.3     .12       0
#XS Ineff= 1 ,-1
  5781.5    8420   220.1
Permanent Ineff=
       F
Bank Sta=4937.8,5050.35
XS Rating Curve= 0 ,0
Exp/Cntr=0.3,0.1

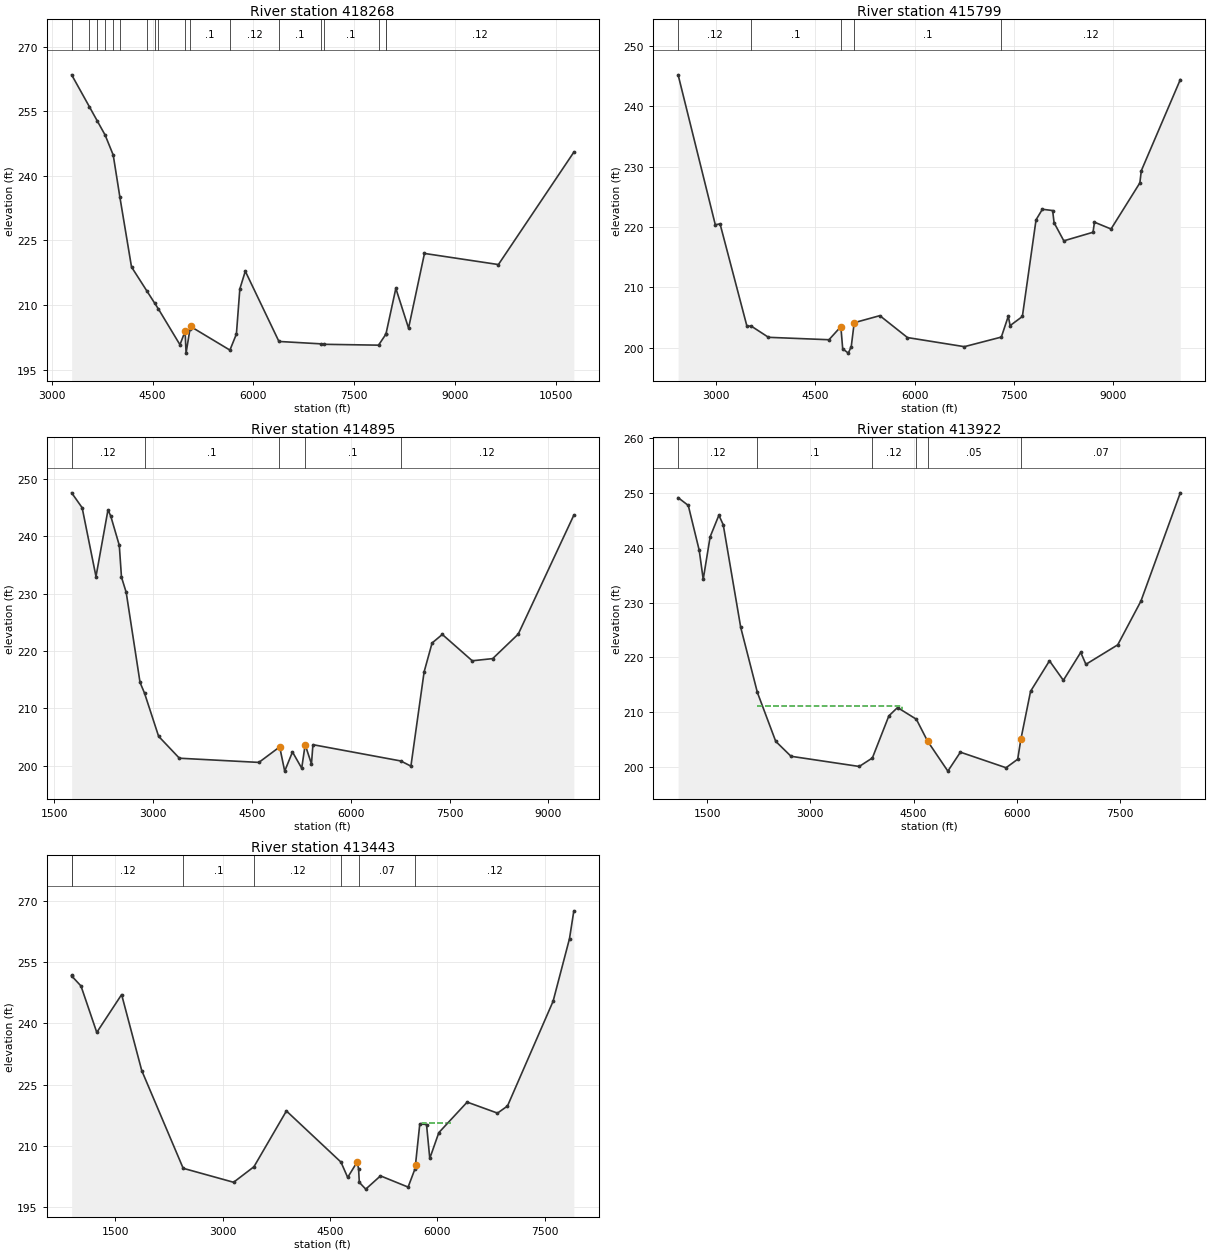
Type RM Length L Ch R = 1 ,418268  ,2469,2469,2469
BEGIN DESCRIPTION:
WFSJ Main 414.0
END DESCRIPTION:
XS GIS Cut Line= 3
      3778216.66     10204137.31      3775231.88     10203588.27
      3771378.62     10201402.09
#Sta/Elev= 30
  3298.1  263.45  3561.1  256.06  3678.3  252.76  3795.8  249.46  3916.1  244.82
  4015.8  234.98    4188  218.83  4414.4   213.3  4534.5  210.37  4589.1  209.04
  4908.2  200.77  4984.7  203.91    4999  198.82  5055.9  204.32  5066.1  205.01
  5650.8  199.52  5747.3  203.26  5798.2  213.73  5879.5  217.85  6379.3  201.53
  6997.5  200.98  7047.9  200.87  7860.1  200.67  7967.2  203.17  7971.8  203.37
  8117.3  213.86  8306.2  204.62  8542.8  221.97  9641.8  219.39 10763.2  245.49
#Mann= 18 ,-1 , 0
  3298.1     .05       0  3561.1     .12       0  3678.3     .05       0
  3795.8     .12       0  3916.1     .05       0  4015.8     .12       0
  4414.4      .1       0  4534.5     .05       0  4589.1      .1       0
  4984.7     .07       0  5055.9      .1       0  5650.8     .12       0
  6379.3      .1       0  6997.5     .12       0  7047.9      .1       0
  7860.1     .05       0  7967.2      .1       0  7971.8     .12       0
#XS Ineff= 1 ,-1
  5879.5    8570  217.85
Permanent Ineff=
       F
Bank Sta=4984.7,5066.1
XS Rating Curve= 0 ,0
Exp/Cntr=0.3,0.1

Type RM Length L Ch R = 1 ,415799  ,904,904,904
BEGIN DESCRIPTION:
Mapping XS 037cd638
END DESCRIPTION:
XS GIS Cut Line= 4
      3778256.67     10202120.81      3776769.21     10202450.25
       3774992.3     10203328.72      3771408.53     10201372.12
#Sta/Elev= 30
  2427.2  245.22  2989.3  220.37    3061  220.52  3467.3  203.56  3530.7  203.59
    3793  201.72  4706.8  201.32  4886.3  203.49  4914.3  199.82    4999   199.1
  5043.4  200.17  5088.3  204.14  5475.3  205.31  5893.2  201.68  6752.4  200.17
  7311.5  201.76  7416.7  205.22  7444.3  203.66  7629.3  205.17  7836.2   221.2
  7931.8  222.94  8086.7  222.73  8108.6  220.71  8255.7  217.71  8696.9  219.13
  8718.8   220.8  8969.3  219.67  9404.9  227.31  9426.7  229.33   10016  244.43
#Mann= 5 ,-1 , 0
  2427.2     .12       0  3530.7      .1       0  4886.3     .07       0
  5088.3      .1       0  7311.5     .12       0
Bank Sta=4886.3,5088.3
XS Rating Curve= 0 ,0
Exp/Cntr=0.3,0.1

Type RM Length L Ch R = 1 ,414895  ,973,973,973
BEGIN DESCRIPTION:
WFSJ Main 413.0
END DESCRIPTION:
XS GIS Cut Line= 4
      3778246.65     10202011.01      3776729.28     10201561.79
      3774323.46     10202839.57      3771378.56     10201322.19
#Sta/Elev= 30
  1766.6  247.57    1926  244.97  2135.9  232.98  2318.1  244.61  2359.8  243.52
  2489.4  238.42  2522.6  232.88  2594.3  230.22  2804.3  214.52    2872  212.67
    3086  205.14  3401.2  201.32  4607.5  200.59  4916.7  203.24  4924.6   203.2
    4999  199.07  5117.1  202.41  5257.1  199.58  5309.6  203.67  5405.3  200.33
  5427.3  203.68  6760.9  200.84    6914  199.94  7114.4  216.37  7235.2   221.4
  7390.4  222.89  7844.6   218.3  8154.9  218.68  8542.7  222.95    9386  243.68
#Mann= 5 ,-1 , 0
  1766.6     .12       0    2872      .1       0  4916.7     .07       0
  5309.6      .1       0  6760.9     .12       0
Bank Sta=4924.6,5309.6
XS Rating Curve= 0 ,0
Exp/Cntr=0.3,0.1

Type RM Length L Ch R = 1 ,413922  ,479,479,479
BEGIN DESCRIPTION:
WFSJ Main 412.0
END DESCRIPTION:
XS GIS Cut Line= 5
      3778236.66      10201961.1      3776479.71      10201382.1
       3775511.4     10201541.83       3773494.9     10202220.65
      3771398.57     10201182.46
#Sta/Elev= 30
  1078.8  249.17  1226.4  247.75  1385.3  239.57  1443.6  234.26  1544.1  242.02
  1671.2  245.96  1734.7  244.21  1988.9  225.47  2230.8   213.6  2497.2  204.68
  2719.6  201.95    3711  200.09  3901.9  201.64  4141.8  209.33  4267.7  210.85
  4541.3  208.71  4703.5  204.73    4999  199.24  5181.2   202.7  5844.7  199.86
  6013.6  201.41 6061.07  205.12  6201.1  213.82  6475.7  219.38  6677.6  215.82
  6929.8  220.92  7005.3  218.74    7468   222.3  7804.4  230.27  8377.1  250.05
#Mann= 6 ,-1 , 0
  1078.8     .12       0  2230.8      .1       0  3901.9     .12       0
  4541.3     .07       0  4703.5     .05       0 6061.07     .07       0
#XS Ineff= 1 ,-1
    2230  4330.7  211.05
Permanent Ineff=
       F
Bank Sta=4703.5,6061.07
XS Rating Curve= 0 ,0
Exp/Cntr=0.3,0.1

Type RM Length L Ch R = 1 ,413443  ,690,690,690
BEGIN DESCRIPTION:
WFSJ Main 411.0
END DESCRIPTION:
XS GIS Cut Line= 4
      3778246.63      10201901.2      3776176.97     10201123.37
      3774133.79     10201471.95      3771588.21     10200493.64
#Sta/Elev= 30
   893.3  251.76   900.4  251.51  1023.6  249.18  1244.1  237.79  1590.9  247.07
  1871.9  228.43  2450.2  204.47  3154.1  201.04  3438.3  204.85  3891.5  218.53
    4653  205.99  4746.8  202.23  4878.7  206.01    4899  204.36  4909.2  201.02
    4999  199.36  5204.8  202.61  5590.5  199.86  5686.9  204.36  5693.7  205.38
  5753.7  215.38  5847.6  215.19    5893  206.89    6019  213.21    6415   220.7
  6838.3     218  6977.6  219.74  7614.2  245.42  7843.6   260.8  7904.1  267.61
#Mann= 7 ,-1 , 0
   893.3     .05       0   900.4     .12       0  2450.2      .1       0
  3438.3     .12       0    4653      .1       0    4899     .07       0
  5686.9     .12       0
#XS Ineff= 2 ,-1
    2025  3891.5  218.53  5778.4    6190  215.54
Permanent Ineff=
       F       F
Bank Sta=4878.7,5693.7
XS Rating Curve= 0 ,0
Exp/Cntr=0.3,0.1