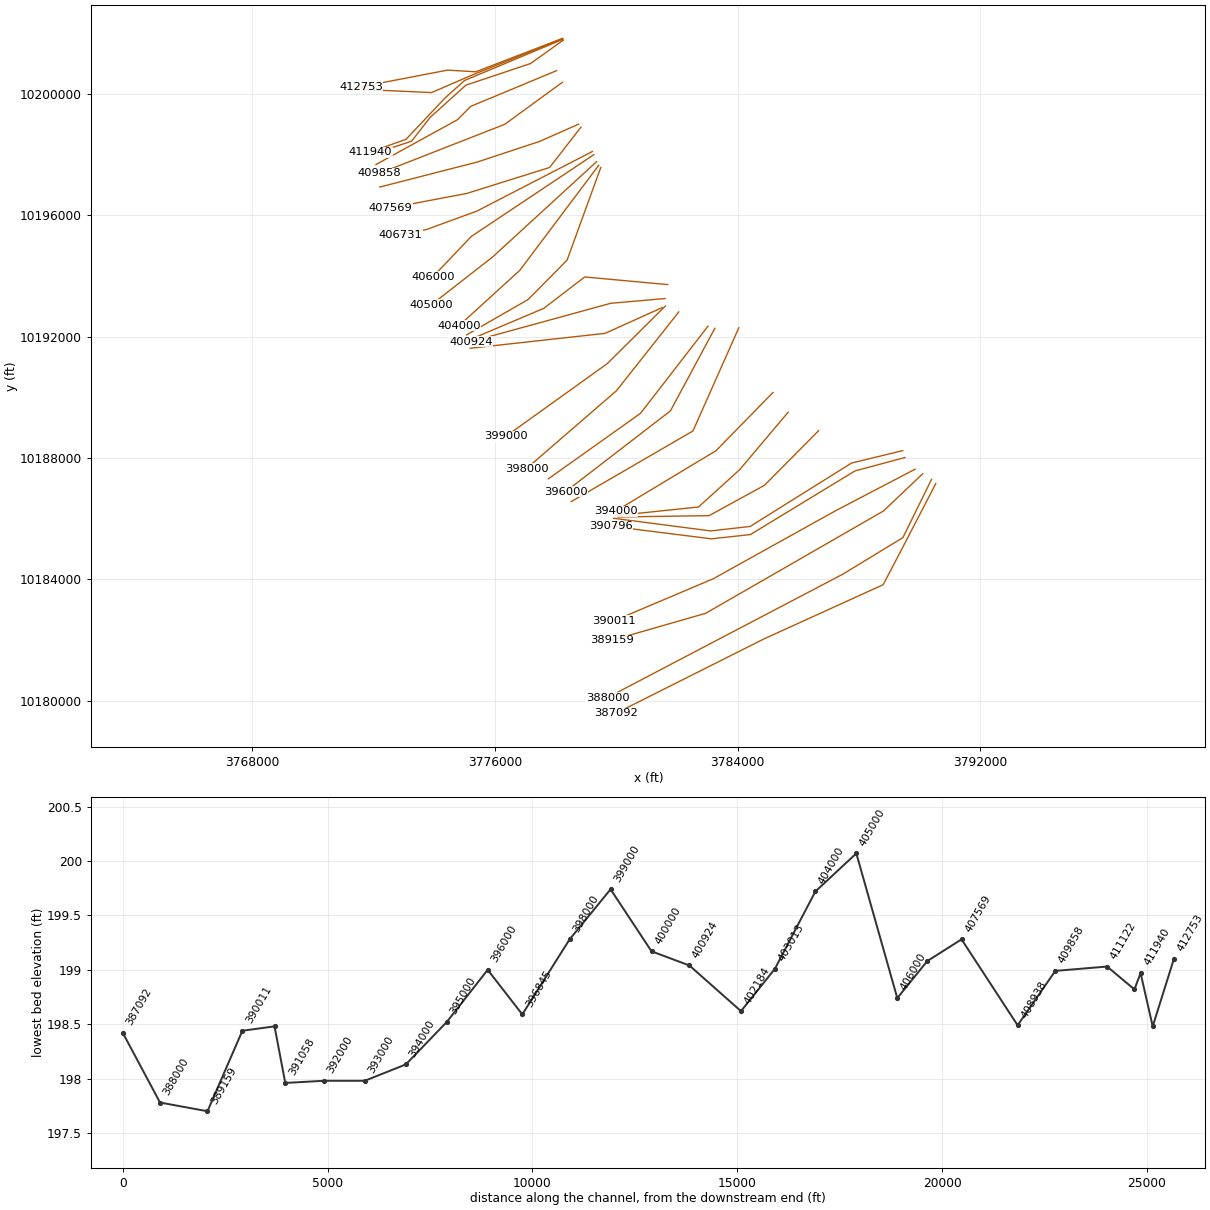
HEC-RAS study WFSJ Main.prj: WFSJ Main Base Level Engineering

--- WFSJ Main.g02 (geometry) --- (continued)

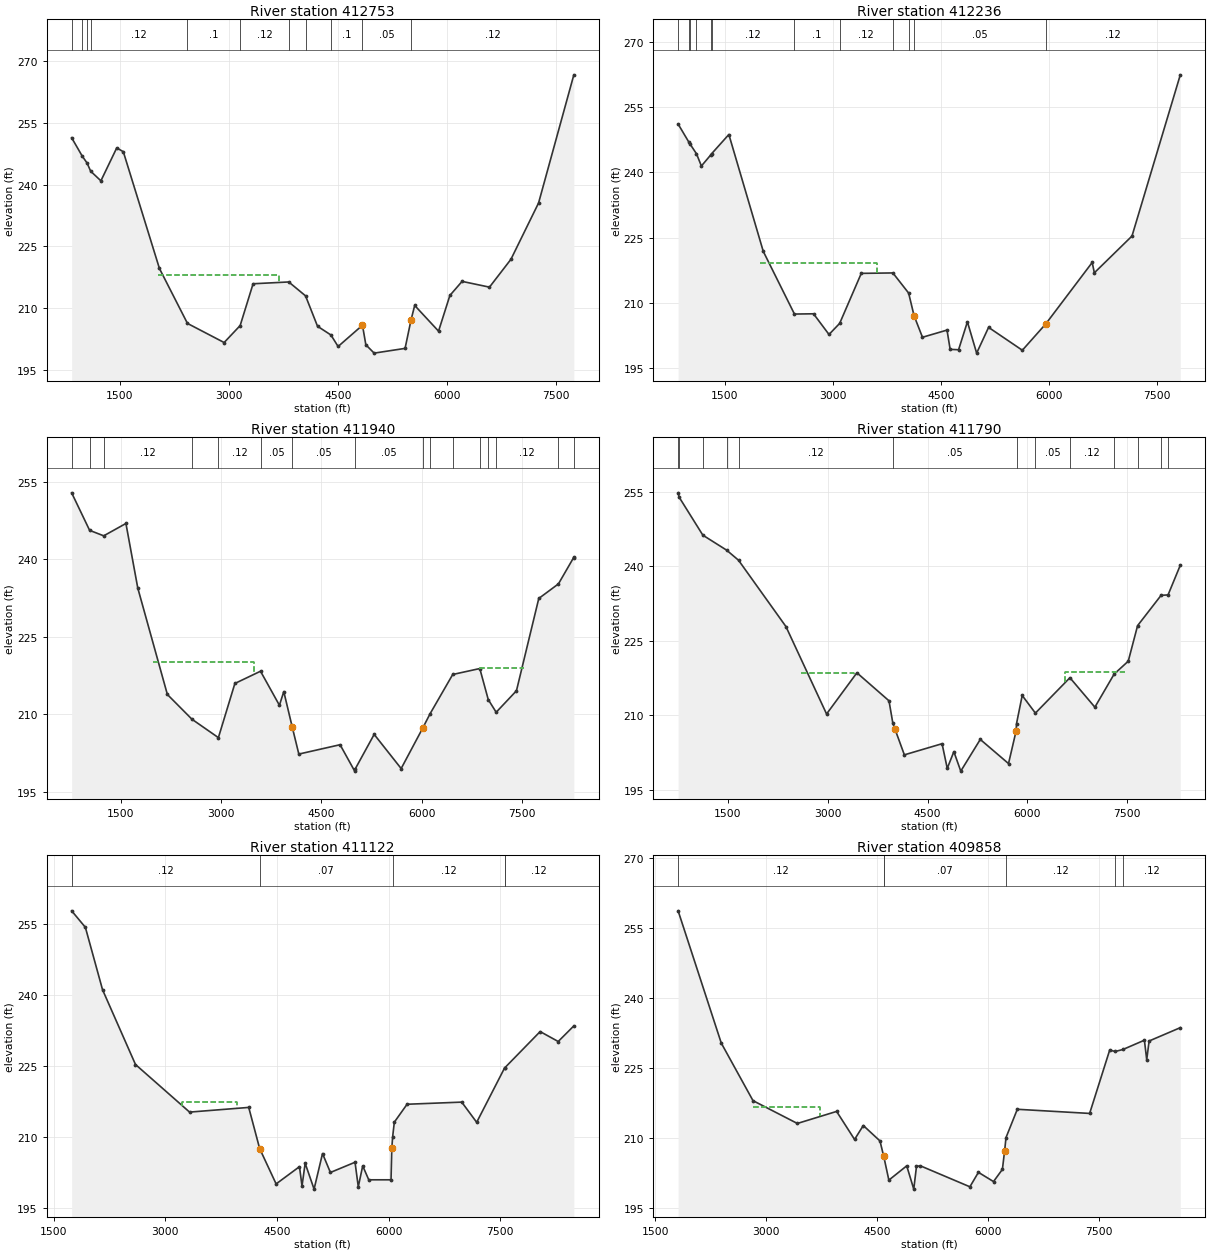
Type RM Length L Ch R = 1 ,412753  ,517,517,517
BEGIN DESCRIPTION:
WFSJ Main 410.0
END DESCRIPTION:
XS GIS Cut Line= 4
      3778236.68     10201841.31      3775370.68     10200737.23
      3774443.25     10200793.13      3771588.19     10200244.08
#Sta/Elev= 30
   838.2  251.36   984.2  246.89  1050.4  245.23    1100  243.24  1240.5  240.91
  1458.5   248.9  1548.9  247.97  2045.7  219.64  2431.2  206.31  2935.6  201.67
  3156.1  205.79  3333.9  215.93  3824.3  216.37  4055.4     213  4220.3  205.62
  4404.7   203.5  4503.4  200.71  4838.6  205.87  4884.9  201.13    4999   199.1
  5424.6  200.25    5506  207.11  5556.9  210.67    5885  204.43  6040.8  213.09
  6208.7  216.51  6585.5  215.11  6880.8  221.87  7260.8  235.53    7746  266.63
#Mann= 11 ,-1 , 0
   838.2     .05       0   984.2     .12       0  1050.4     .05       0
    1100     .12       0  2431.2      .1       0  3156.1     .12       0
  3824.3     .05       0  4055.4     .12       0  4404.7      .1       0
  4838.6     .05       0    5506     .12       0
#XS Ineff= 1 ,-1
    2025  3691.5  217.98
Permanent Ineff=
       F
Bank Sta=4838.6,5506
XS Rating Curve= 0 ,0
Exp/Cntr=0.3,0.1

Type RM Length L Ch R = 1 ,412236  ,296,296,296
BEGIN DESCRIPTION:
Mapping XS b5999d83
END DESCRIPTION:
XS GIS Cut Line= 4
      3778229.64     10201828.27      3775214.01     10200614.73
      3773917.14     10200052.23      3771604.63      10200156.4
#Sta/Elev= 30
   850.2  251.07   997.2  246.98  1015.8  246.49  1105.3  244.25  1173.8  241.44
  1306.8  244.04  1314.9  244.24  1555.4  248.67  2033.6  221.84  2466.8  207.45
  2732.1  207.51  2947.1  202.76  3095.4  205.31  3395.7  216.79  3834.8  216.89
  4053.7  212.27  4129.4  207.06    4246  202.12  4587.2  203.77  4630.8  199.34
    4748  199.26  4870.6  205.67    4999  198.48  5164.9  204.39  5633.9  199.14
  5959.8  205.19  6604.8  219.29  6634.9  216.92  7157.9  225.36  7829.3  262.37
#Mann= 12 ,-1 , 0
   850.2     .05       0   997.2     .12       0  1015.8     .05       0
  1105.3     .12       0  1306.8     .05       0  1314.9     .12       0
  2466.8      .1       0  3095.4     .12       0  3834.8     .05       0
  4053.7     .12       0  4129.4     .05       0  5959.8     .12       0
#XS Ineff= 1 ,-1
    1990  3616.1  219.06
Permanent Ineff=
       F
Bank Sta=4129.4,5959.8
XS Rating Curve= 0 ,0
Exp/Cntr=0.3,0.1

Type RM Length L Ch R = 1 ,411940  ,150,150,150
BEGIN DESCRIPTION:
WFSJ Main 409.0
END DESCRIPTION:
XS GIS Cut Line= 5
      3778241.77     10201809.17      3775005.68     10200453.27
      3774359.85     10199875.15      3773073.39     10198510.56
      3771891.99     10198089.01
#Sta/Elev= 30
   768.8  252.82  1037.4  245.56  1248.1   244.5  1579.9  246.89  1757.2  234.39
  2199.4   213.8  2566.9  209.01  2961.9  205.45  3208.2  215.93  3591.4   218.3
  3873.9  211.71  3939.1  214.36  4065.1  207.52    4164  202.27  4780.4  204.08
    4999  198.97    5010  199.47  5289.9  206.08  5693.3  199.47 6017.99  207.36
    6125  210.06  6463.8  217.67  6868.5  218.82    6995  212.81  7113.4  210.36
  7416.4  214.52    7750  232.38  8043.8   235.2  8272.9  240.33    8274  240.26
#Mann= 16 ,-1 , 0
   768.8     .05       0  1037.4     .12       0  1248.1     .12       0
  2566.9      .1       0  2961.9     .12       0  3591.4     .05       0
  4065.1     .05       0    5010     .05       0 6017.99      .1       0
    6125     .12       0  6463.8     .12       0  6868.5     .12       0
    6995     .05       0  7113.4     .12       0  8043.8     .12       0
  8272.9     .05       0
#XS Ineff= 2 ,-1
    1985  3496.9  220.05  6867.8    7530  218.85
Permanent Ineff=
       F       F
Bank Sta=4065.1,6017.99
XS Rating Curve= 0 ,0
Exp/Cntr=0.3,0.1

Type RM Length L Ch R = 1 ,411790  ,668,668,668
BEGIN DESCRIPTION:
Mapping XS c1504bff
END DESCRIPTION:
XS GIS Cut Line= 6
      3778255.72     10201781.43      3777177.55     10201010.56
      3775047.35     10200297.02      3773870.26     10199234.52
      3773255.68     10198448.06      3771937.97     10198010.56
#Sta/Elev= 30
   752.5  254.74   767.1  253.88  1124.3  246.23  1481.4  243.22  1659.9   241.2
  2372.3  227.87  2982.9   210.3  3438.5  218.58  3920.6  212.95  3978.9  208.42
  4011.7  207.22  4151.5  202.09    4718  204.33  4795.8  199.37  4895.2  202.73
    4999  198.82    5292  205.19  5716.4  200.34    5830  206.87  5836.8  208.38
    5922  214.02  6120.1  210.48  6638.6  217.59  7013.7  211.67  7302.7  218.31
  7515.2  220.91  7655.4  228.05  8008.2  234.14  8113.3  234.23  8297.2   240.2
#Mann= 13 ,-1 , 0
   752.5     .05       0   767.1     .12       0  1124.3     .12       0
  1481.4     .12       0  1659.9     .12       0  3978.9     .05       0
  5836.8      .1       0  6120.1     .05       0  6638.6     .12       0
  7302.7     .05       0  7655.4     .05       0  8008.2     .12       0
  8113.3     .05       0
#XS Ineff= 2 ,-1
    2600  3393.5  218.58  6570.5    7470  218.68
Permanent Ineff=
       F       F
Bank Sta=4011.7,5830
XS Rating Curve= 0 ,0
Exp/Cntr=0.3,0.1

Type RM Length L Ch R = 1 ,411122  ,1264,1264,1264
BEGIN DESCRIPTION:
WFSJ Main 408.0
END DESCRIPTION:
XS GIS Cut Line= 4
       3778035.2     10200776.19      3775201.86     10199595.63
      3774772.93     10199158.93      3772083.76     10197678.94
#Sta/Elev= 30
    1740  257.85  1924.5  254.36  2155.3  241.17  2598.3  225.37  3325.3  215.31
  4120.5   216.3 4267.64  207.59  4488.8  200.13  4802.9  203.78  4836.7  199.69
  4879.2  204.49    4999  199.03  5112.5  206.55  5218.6  202.55  5549.6  204.71
  5593.2  199.53  5652.8  203.94  5734.2     201  6033.5     201 6043.94  207.67
  6055.3   210.1    6078  213.19  6249.2  216.97  6984.2  217.42    7185  213.15
  7559.5  224.62  7559.6  224.62  8038.2  232.33    8281  230.23  8491.1  233.53
#Mann= 5 ,-1 , 0
    1740     .12       0 4267.64     .07       0  6055.3     .12       0
  7559.5     .05       0  7559.6     .12       0
#XS Ineff= 2 ,-1
    3230    3958  217.48  6984.2    7360  217.42
Permanent Ineff=
       F       F
Bank Sta=4267.64,6043.94
XS Rating Curve= 0 ,0
Exp/Cntr=0.3,0.1

Type RM Length L Ch R = 1 ,409858  ,920,920,920
BEGIN DESCRIPTION:
WFSJ Main 407.0
END DESCRIPTION:
XS GIS Cut Line= 3
      3778229.63     10200394.24      3776326.86     10199005.36
      3772194.92      10197387.3
#Sta/Elev= 30
  1811.3  258.66  2395.4  230.29  2824.2  217.96  3424.3  213.07  3955.3  215.65
  4198.2  209.64  4316.3  212.63  4541.9  209.32  4591.1  206.11  4595.6  205.82
    4662  200.92  4903.6  203.98    4999  198.99  5035.9  203.88  5089.6  203.98
  5758.2  199.49  5873.5  202.59  6077.6  200.61  6197.8  203.22  6227.9  207.18
  6246.7  210.04  6399.8  216.11  7378.1  215.22  7649.5  228.81  7724.1   228.5
  7828.5  228.93  8118.8  230.92  8150.3  226.73  8182.5  230.75  8604.5  233.61
#Mann= 6 ,-1 , 0
  1811.3     .12       0  4591.1      .1       0  4595.6     .07       0
  6246.7     .12       0  7724.1     .05       0  7828.5     .12       0
#XS Ineff= 1 ,-1
    2830  3732.5  216.57
Permanent Ineff=
       F
Bank Sta=4591.1,6227.9
XS Rating Curve= 0 ,0
Exp/Cntr=0.3,0.1

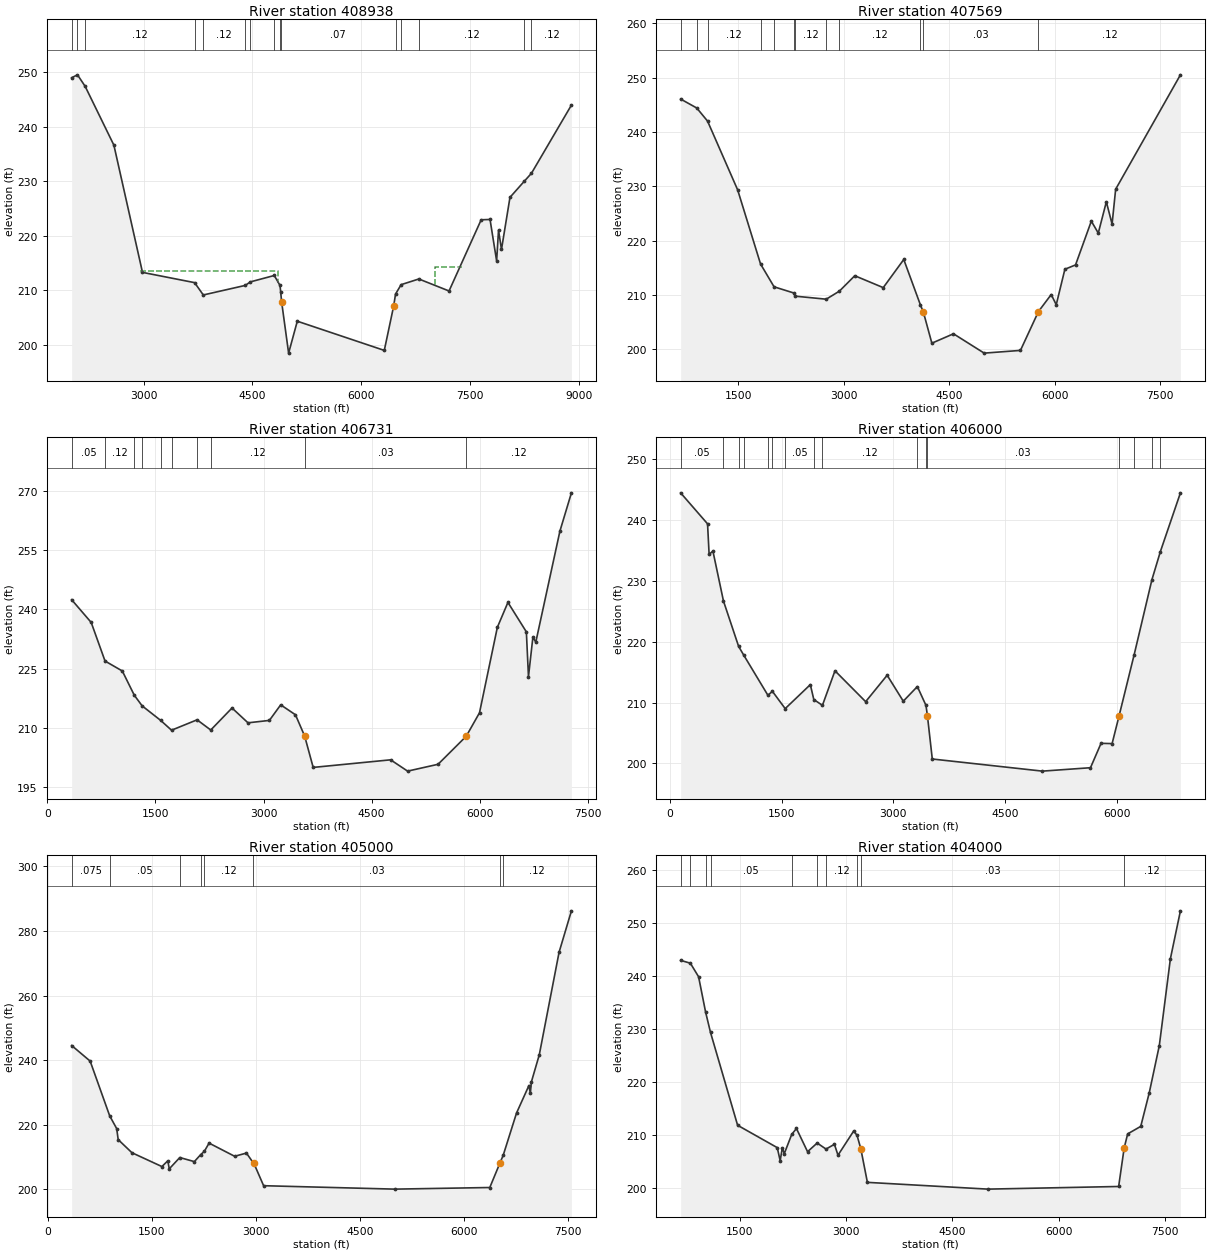
Type RM Length L Ch R = 1 ,408938  ,1369,1369,1369
BEGIN DESCRIPTION:
WFSJ Main 406.0
END DESCRIPTION:
XS GIS Cut Line= 4
      3778764.35      10199012.3      3777479.64     10198442.86
      3775424.08      10197762.3      3772209.12     10196935.99
#Sta/Elev= 30
  2007.9  248.97  2088.3   249.5  2194.4  247.38  2590.1  236.61  2984.4  213.29
  3702.8  211.41  3822.7  209.15  4400.8   210.9  4472.1  211.55  4801.3  212.72
  4880.1   210.9  4889.8   209.7  4901.9  207.95    4999  198.49  5118.6  204.34
    6318  198.99    6447   207.1 6473.11  209.32  6550.2  211.04  6794.3  212.08
  7210.7  209.88  7653.6  222.93  7775.9  222.99  7866.7   215.4  7892.9  221.03
  7933.6  217.49  8050.7  227.04  8245.8  229.96  8346.7  231.45  8897.9  243.95
#Mann= 15 ,-1 , 0
  2007.9     .12       0  2088.3     .05       0  2194.4     .12       0
  3702.8      .1       0  3822.7     .12       0  4400.8      .1       0
  4472.1     .12       0  4801.3     .05       0  4880.1      .1       0
  4889.8     .07       0 6473.11     .12       0  6550.2     .05       0
  6794.3     .12       0  8245.8     .05       0  8346.7     .12       0
#XS Ineff= 2 ,-1
  7020.1    7390  214.23    2950  4858.2  213.61
Permanent Ineff=
       F       F
Bank Sta=4901.9,6447
XS Rating Curve= 0 ,0
Exp/Cntr=0.3,0.1

Type RM Length L Ch R = 1 ,407569  ,838,838,838
BEGIN DESCRIPTION:
WFSJ Main 405.0
END DESCRIPTION:
XS GIS Cut Line= 4
      3778840.72     10198915.04      3777806.03     10197581.74
       3775083.8     10196727.58      3772563.01     10196248.42
#Sta/Elev= 30
   682.9  246.06     912  244.41  1065.4     242  1493.3  229.34    1819  215.69
  2011.1  211.49  2292.7  210.35  2309.3  209.77  2752.9  209.21  2939.9  210.69
  3158.9  213.53  3563.7  211.34  3855.5  216.52  4092.8  208.14  4135.6  206.78
    4255  201.11  4562.5  202.84    4999  199.28  5514.7  199.78  5770.8  206.94
  5952.4  210.07  6023.7  208.19  6146.5  214.72  6298.1  215.52  6522.5  223.58
  6621.6  221.38  6736.2  227.14  6817.7  223.04  6868.6  229.46  7789.6  250.52
#Mann= 12 ,-1 , 0
   682.9     .12       0     912     .05       0  1065.4     .12       0
    1819     .05       0  2011.1     .12       0  2292.7     .05       0
  2309.3     .12       0  2752.9     .05       0  2939.9     .12       0
  4092.8      .1       0  4135.6     .03       0  5770.8     .12       0
#XS Ineff= 1 ,-1
    1700  3855.5  216.52
Permanent Ineff=
       F
Bank Sta=4135.6,5770.8
XS Rating Curve= 0 ,0
Exp/Cntr=0.3,0.1

Type RM Length L Ch R = 1 ,406731  ,731,731,731
BEGIN DESCRIPTION:
WFSJ Main 404.0
END DESCRIPTION:
XS GIS Cut Line= 4
      3779215.74     10198109.52      3775410.19     10196144.24
      3773743.53     10195533.13      3772882.62     10195366.51
#Sta/Elev= 30
   337.1  242.44   608.3  236.69   800.3  226.93  1040.1  224.41  1206.3  218.28
  1315.2  215.59  1573.1   211.9    1723  209.43  2077.7  212.06  2267.2  209.48
  2562.5  215.05  2784.1   211.3  3080.9  211.91    3238  215.85    3443  213.33
  3570.3  207.95  3688.6  200.02  4763.3  201.94    4999  199.08  5421.5  200.81
 5812.81  207.91  5996.6  213.84  6244.2  235.45    6391  241.76  6646.8  234.31
  6676.1  222.99  6737.2  232.92    6778  231.73  7112.8  259.82  7272.2  269.48
#Mann= 10 ,-1 , 0
   337.1     .05       0   800.3     .12       0  1206.3     .05       0
  1315.2     .12       0  1573.1     .05       0    1723     .12       0
  2077.7     .05       0  2267.2     .12       0  3570.3     .03       0
 5812.81     .12       0
#XS Ineff= 1 ,-1
    1210    3238  215.85
Permanent Ineff=
       F
Bank Sta=3570.3,5812.81
XS Rating Curve= 0 ,0
Exp/Cntr=0.3,0.1

Type RM Length L Ch R = 1 ,406000  ,1000,1000,1000
BEGIN DESCRIPTION:
WFSJ Main 403.0
END DESCRIPTION:
XS GIS Cut Line= 3
      3779264.34     10198005.34      3775228.79     10195310.34
      3773952.32     10193971.12
#Sta/Elev= 30
   147.3  244.41     508  239.33     529  234.33   580.1  234.85   721.5  226.66
   924.9  219.21   993.3  217.78  1317.6  211.19  1377.7  211.84  1549.3     209
  1886.6  212.94  1933.1  210.49  2048.8  209.54    2217  215.21  2628.5  210.14
  2916.9  214.48  3133.1  210.22  3321.8  212.62  3437.5  209.53  3457.5  207.76
  3522.1  200.73    4999  198.74  5643.9   199.3  5785.4   203.3  5933.9  203.26
  6025.7  207.73  6230.2  217.88    6468  230.17  6581.3  234.78  6850.1  244.42
#Mann= 16 ,-1 , 0
   147.3     .05       0   721.5     .12       0   924.9     .05       0
   993.3     .12       0  1317.6     .05       0  1377.7     .12       0
  1549.3     .05       0  1933.1     .05       0  2048.8     .12       0
  3321.8     .05       0  3437.5     .05       0  3457.5     .03       0
  6025.7     .12       0  6230.2     .05       0    6468     .05       0
  6581.3     .12       0
#XS Ineff= 2 ,-1
    1030    2217  215.21    2218  2916.9  214.48
Permanent Ineff=
       F       F
Bank Sta=3457.5,6025.7
XS Rating Curve= 0 ,0
Exp/Cntr=0.3,0.1

Type RM Length L Ch R = 1 ,405000  ,1000,1000,1000
BEGIN DESCRIPTION:
WFSJ Main 402.0
END DESCRIPTION:
XS GIS Cut Line= 3
       3779352.9     10197772.71      3775924.02     10194627.07
      3773917.86     10193061.07
#Sta/Elev= 30
   346.8  244.54   613.2  239.71   894.4  222.77   995.5   218.8  1017.1   215.4
    1215  211.34  1646.6  207.06  1731.7  208.84  1752.7  206.35  1904.3  209.85
    2114  208.59  2205.1  210.75  2257.5  211.76  2326.1  214.32  2694.2  210.24
  2864.2  211.23    2963   208.2  2970.4   208.1  3111.6  201.13    4999  200.07
  6369.2  200.57 6513.49  208.06  6562.4  210.55  6754.5  223.64  6932.7  232.14
  6953.5  229.73  6967.9  233.24  7081.9  241.65  7367.4  273.44    7545  286.24
#Mann= 8 ,-1 , 0
   346.8    .075       0   894.4     .05       0  1904.3     .12       0
  2205.1     .05       0  2257.5     .12       0    2963     .03       0
 6513.49      .1       0  6562.4     .12       0
#XS Ineff= 1 ,-1
    1000  2326.1  214.32
Permanent Ineff=
       F
Bank Sta=2970.4,6513.49
XS Rating Curve= 0 ,0
Exp/Cntr=0.3,0.1

Type RM Length L Ch R = 1 ,404000  ,987,987,987
BEGIN DESCRIPTION:
WFSJ Main 401.0
END DESCRIPTION:
XS GIS Cut Line= 3
      3779422.34     10197651.18      3776822.92       10194189.
      3774817.87     10192361.09
#Sta/Elev= 30
   670.6     243   807.4  242.46   923.3   239.9  1022.2  233.21  1091.3  229.36
  1473.2   211.8  2031.5  207.57  2073.2  205.09  2102.3   207.5  2131.5  206.45
    2236  210.08  2302.3  211.19  2458.9   206.8  2594.4  208.44    2719   207.3
  2837.6   208.2  2887.6  206.14  3109.2  210.72  3156.5  209.88  3209.2  207.36
  3302.1     201    4999  199.72  6842.7  200.22  6920.4   207.5  6969.7  210.17
  7154.1  211.59  7274.4  217.97  7415.6  226.87  7571.7   243.3  7713.2  252.37
#Mann= 10 ,-1 , 0
   670.6    .075       0   807.4     .05       0  1022.2    .075       0
  1091.3     .05       0    2236     .12       0  2594.4     .05       0
    2719     .12       0  3156.5     .05       0  3209.2     .03       0
  6920.4     .12       0
#XS Ineff= 1 ,-1
    1500  3109.2  210.72
Permanent Ineff=
       F
Bank Sta=3209.2,6920.4
XS Rating Curve= 0 ,0
Exp/Cntr=0.3,0.1

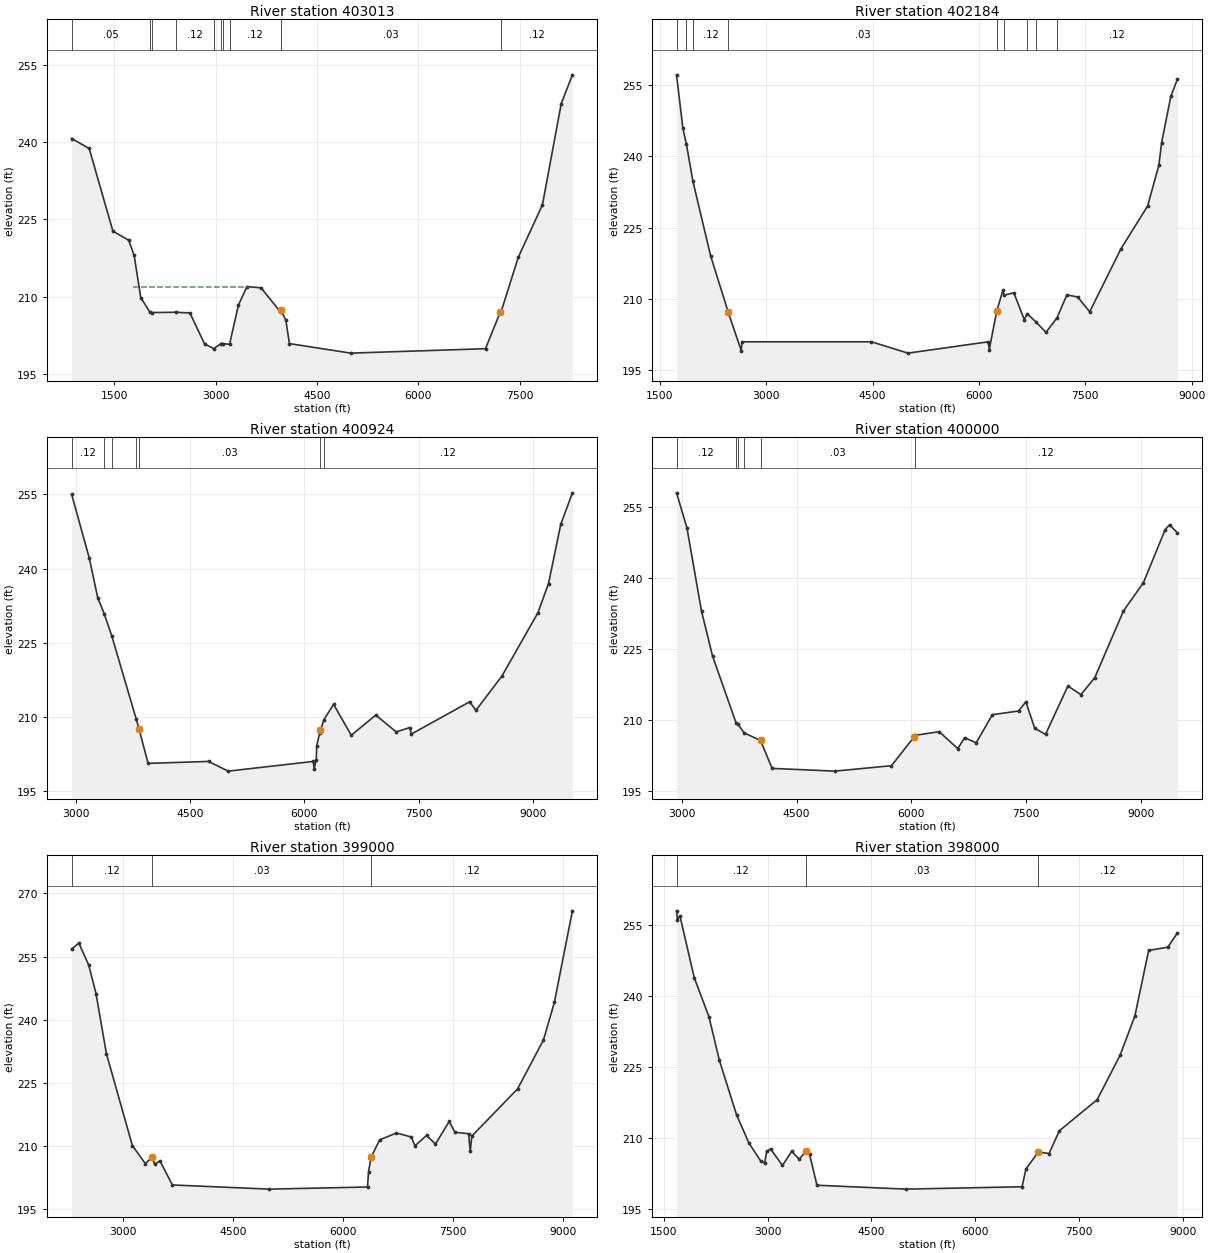
Type RM Length L Ch R = 1 ,403013  ,829,829,829
BEGIN DESCRIPTION:
WFSJ Main 400.0
END DESCRIPTION:
XS GIS Cut Line= 4
      3779491.78     10197581.72      3778380.68     10194526.19
      3777100.23     10193229.04      3775073.41     10192060.92
#Sta/Elev= 30
   867.1   240.7  1127.9  238.76  1479.1   222.7  1713.1  220.94  1793.5  217.98
  1891.4   209.8  2021.6  207.07  2061.2  206.89  2410.4  206.95  2618.9  206.81
  2836.3  200.78  2973.6  199.89  3079.6  200.88  3106.3  200.87  3205.7  200.73
  3336.4  208.33  3463.5  211.94  3672.4  211.69  3962.3  206.96  3967.6  207.31
  4038.7   205.4  4091.9  200.86    4999  199.01  6994.1  199.87  7213.9  207.04
  7223.9  206.99  7478.9  217.62  7836.7  227.81  8114.7  247.46  8280.4  253.07
#Mann= 10 ,-1 , 0
   867.1     .05       0  2021.6     .12       0  2061.2     .05       0
  2410.4     .12       0  2973.6     .05       0  3079.6     .12       0
  3106.3     .05       0  3205.7     .12       0  3962.3     .03       0
  7223.9     .12       0
#XS Ineff= 1 ,-1
    1770  3538.6  211.91
Permanent Ineff=
       F
Bank Sta=3967.6,7213.9
XS Rating Curve= 0 ,0
Exp/Cntr=0.3,0.1

Type RM Length L Ch R = 1 ,402184  ,1260,1260,1260
BEGIN DESCRIPTION:
WFSJ Main 399.0
END DESCRIPTION:
XS GIS Cut Line= 4
      3781696.65      10193718.9      3778962.28     10193970.63
      3777616.79     10192937.65       3775203.6     10191913.34
#Sta/Elev= 30
  1733.9   257.1  1823.1  245.89  1873.9  242.47    1965  234.73  2214.7  219.06
  2463.7  207.19  2646.5  199.12  2656.6     201  4483.6     201    4999  198.62
  6130.1     201  6144.6  199.37    6251  207.51  6338.5  211.88  6352.7  210.79
  6491.4   211.3  6638.8  205.66  6679.3  206.91  6802.4  205.18  6944.4  202.98
  7099.6  206.03  7239.6  210.87  7391.7  210.41  7561.1  207.31  8001.4  220.53
    8378  229.54  8536.3  238.06  8575.8  242.86  8706.2  252.63  8797.7  256.14
#Mann= 9 ,-1 , 0
  1733.9     .12       0  1873.9     .05       0    1965     .12       0
  2463.7     .03       0    6251     .05       0  6352.7     .12       0
  6679.3     .05       0  6802.4      .1       0  7099.6     .12       0
#XS Ineff= 1 ,-1
  6338.5    7800   211.8
Permanent Ineff=
       F
Bank Sta=2463.7,6251
XS Rating Curve= 0 ,0
Exp/Cntr=0.3,0.1

Type RM Length L Ch R = 1 ,400924  ,924,924,924
BEGIN DESCRIPTION:
WFSJ Main 398.0
END DESCRIPTION:
XS GIS Cut Line= 3
      3781609.84     10193258.83      3779821.65     10193102.58
      3775205.15     10191835.64
#Sta/Elev= 30
  2939.7  255.06  3172.6  242.12    3283  234.14  3369.1  230.85  3467.9  226.39
  3787.2  209.68  3825.1   207.6  3945.5  200.61  4739.3     201    4999  199.04
  6116.1     201  6128.2  199.54  6155.7  201.33  6160.9  204.07  6200.8  206.83
  6211.1  207.26  6255.5  209.42  6383.2  212.55  6615.8  206.29    6937  210.38
  7206.6  206.97  7382.9  207.84  7406.6  206.55    8171  213.06    8254  211.34
  8596.2  218.29  9067.4  231.04    9208  236.97  9368.9  248.96  9521.9  255.33
#Mann= 7 ,-1 , 0
  2939.7     .12       0  3369.1     .05       0  3467.9     .12       0
  3787.2     .05       0  3825.1     .03       0  6200.8     .05       0
  6255.5     .12       0
#XS Ineff= 1 ,-1
  6383.2    8400  212.55
Permanent Ineff=
       F
Bank Sta=3825.1,6211.1
XS Rating Curve= 0 ,0
Exp/Cntr=0.3,0.1

Type RM Length L Ch R = 1 ,400000  ,1000,1000,1000
BEGIN DESCRIPTION:
WFSJ Main 397.0
END DESCRIPTION:
XS GIS Cut Line= 3
      3781517.89     10192961.09       3779633.7     10192110.71
      3775186.19      10191618.2
#Sta/Elev= 30
  2932.8  258.08  3068.3  250.69  3258.8  233.05    3403  223.54    3710  209.39
  3730.1  209.16  3816.5  207.26    4030  205.66  4181.4  199.75    4999  199.17
  5740.3  200.32  6032.1  206.34  6044.4  206.74  6364.1  207.52  6605.6  203.94
  6696.2  206.23  6847.1  205.17  7058.4  211.12  7399.9   211.9  7495.6  213.84
  7611.7  208.24  7752.6  206.96  8044.9  217.18  8215.4  215.37  8396.5  218.98
  8770.5  233.08  9030.3  239.03  9314.7  250.26  9372.4  251.32  9474.7  249.62
#Mann= 6 ,-1 , 0
  2932.8     .12       0    3710     .05       0  3730.1     .12       0
  3816.5     .05       0    4030     .03       0  6044.4     .12       0
#XS Ineff= 1 ,-1
  7495.6    8000  213.84
Permanent Ineff=
       F
Bank Sta=4030,6032.1
XS Rating Curve= 0 ,0
Exp/Cntr=0.3,0.1

Type RM Length L Ch R = 1 ,399000  ,1000,1000,1000
BEGIN DESCRIPTION:
WFSJ Main 396.0
END DESCRIPTION:
XS GIS Cut Line= 3
      3781617.86     10193011.08       3779707.2     10191113.42
      3776358.12     10188710.22
#Sta/Elev= 30
  2307.1   256.8  2406.1  258.19  2540.5  252.98  2639.5  246.21  2780.9  231.95
  3134.4  210.08  3311.2   205.8  3403.1  207.35  3438.5  205.63  3509.2  206.46
  3678.9  200.73    4999  199.74    6334  200.24  6348.7  203.91 6381.28  207.26
  6499.8  211.46  6728.2  213.08  6929.6  212.13  6979.9  210.04  7137.1  212.49
  7258.7  210.46  7445.3  215.81  7522.7  213.26  7709.4  212.91  7731.6  208.75
  7753.5  212.35  8376.1  223.56  8728.6   235.2  8877.2  244.16  9122.1  265.87
#Mann= 3 , 0 , 0
  2307.1     .12       0  3403.1     .03       0 6381.28     .12       0
#XS Ineff= 1 ,-1
  7445.3    8030  215.81
Permanent Ineff=
       F
Bank Sta=3403.1,6381.28
XS Rating Curve= 0 ,0
Exp/Cntr=0.3,0.1

Type RM Length L Ch R = 1 ,398000  ,1155,1155,1155
BEGIN DESCRIPTION:
WFSJ Main 395.0
END DESCRIPTION:
XS GIS Cut Line= 3
      3782061.23     10192816.12      3780005.71     10190215.34
      3777043.85     10187651.17
#Sta/Elev= 30
    1685  257.88  1698.2  256.03  1733.4  256.84  1940.2  243.83  2153.4  235.55
  2303.2  226.42  2552.5   214.9  2730.5  208.98    2902  205.17  2958.1   204.8
  2986.9  207.25    3043  207.76  3214.5  204.26  3349.2  207.26  3456.6  205.56
    3556  207.36  3605.6  206.64  3713.1   200.1    4999  199.28  6674.9  199.78
  6730.9  203.51  6908.6   207.1  7064.3  206.78  7213.4  211.57  7759.6  218.12
  8092.2  227.52  8304.7   235.8  8503.2  249.54    8780  250.23  8917.6  253.21
#Mann= 3 , 0 , 0
    1685     .12       0    3556     .03       0  6908.6     .12       0
Bank Sta=3556,6908.6
XS Rating Curve= 0 ,0
Exp/Cntr=0.3,0.1

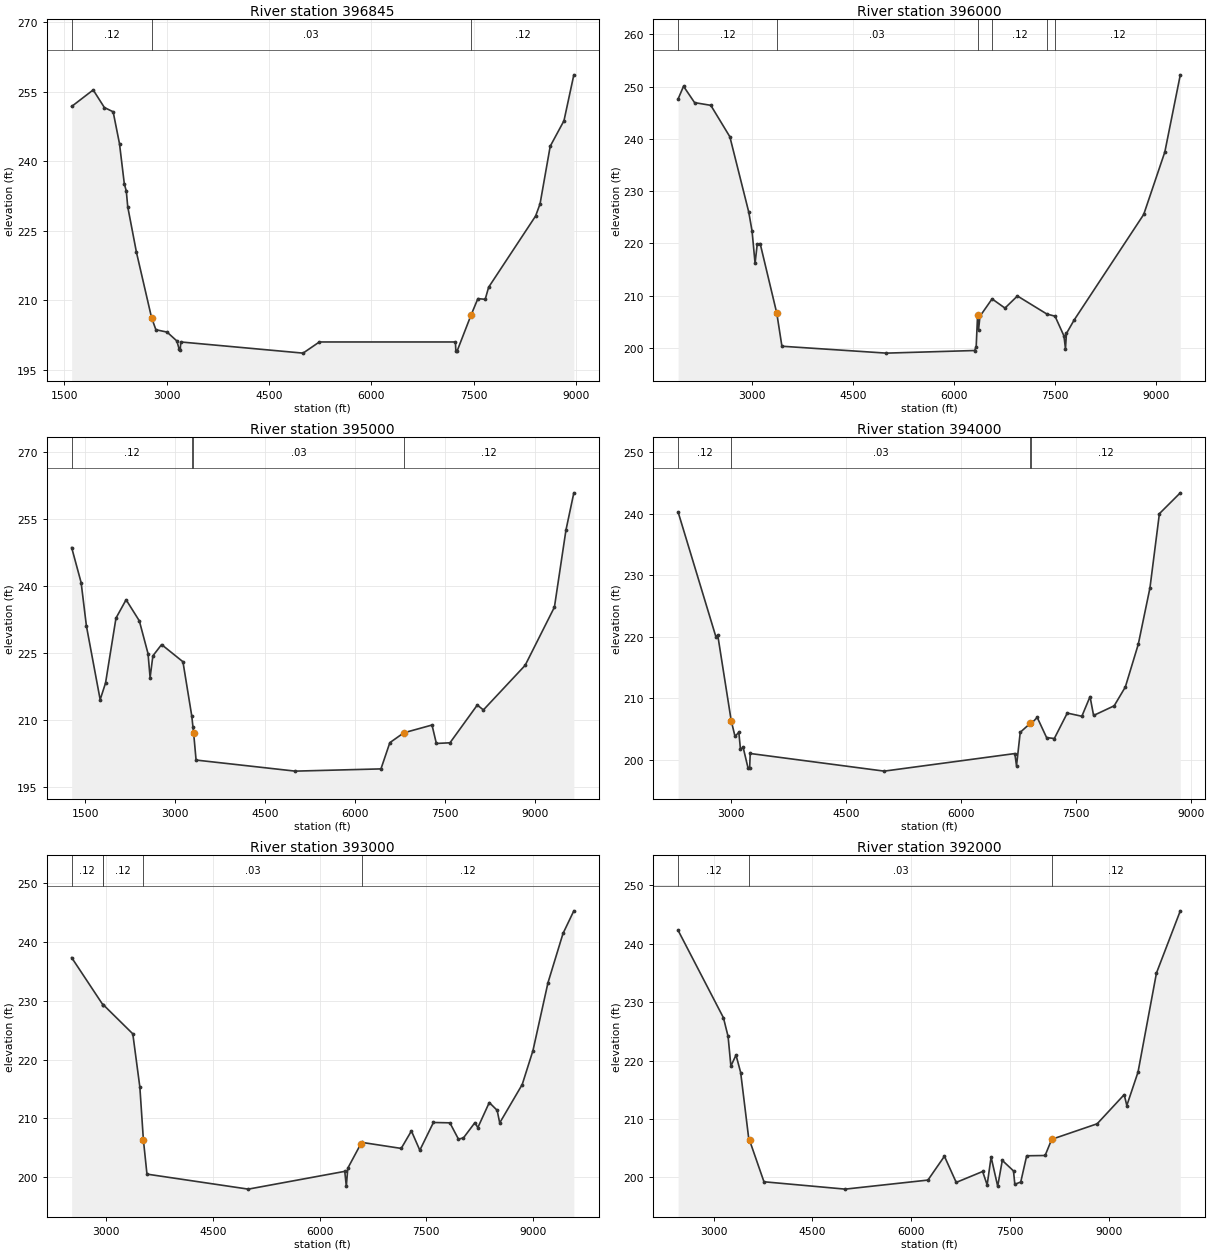
Type RM Length L Ch R = 1 ,396845  ,845,845,845
BEGIN DESCRIPTION:
WFSJ Main 394.0
END DESCRIPTION:
XS GIS Cut Line= 3
      3783024.75     10192347.34      3780802.55     10189474.11
      3777764.37     10187312.66
#Sta/Elev= 30
    1607  251.85  1922.7  255.42  2086.6  251.62  2215.2   250.7  2308.4   243.8
  2379.1  235.13    2408  233.59  2428.9  230.21  2557.4  220.32    2778  206.27
  2841.8  203.64  3005.7  203.13  3148.8  201.22  3184.1  199.39  3198.6  199.36
  3206.7     201    4999  198.59  5237.8     201    7232     201  7238.2  199.09
  7259.1  199.12  7460.7  206.79  7561.6  210.36  7668.6  210.21    7719  212.82
  8407.6   228.2  8472.7  230.82  8621.6  243.26  8823.3  248.77  8967.9  258.68
#Mann= 3 , 0 , 0
    1607     .12       0    2778     .03       0  7460.7     .12       0
Bank Sta=2778,7460.7
XS Rating Curve= 0 ,0
Exp/Cntr=0.3,0.1

Type RM Length L Ch R = 1 ,396000  ,1000,1000,1000
BEGIN DESCRIPTION:
WFSJ Main 393.0
END DESCRIPTION:
XS GIS Cut Line= 3
      3783250.48     10192277.94      3781786.23      10189552.7
      3778328.62     10186887.32
#Sta/Elev= 30
  1906.3  247.65  1986.8  250.08  2150.8  246.95  2391.9  246.43  2674.7  240.42
  2955.3  226.01  3004.8  222.35  3049.3   216.2  3081.1  219.82  3124.9  219.97
 3372.09  206.63    3448  200.32    4999     199  6311.1   199.5  6333.8  200.24
  6354.6  206.27  6369.1  203.48  6389.9  206.06  6569.8  209.38  6761.4  207.62
  6946.2  209.94    7384  206.48    7505  206.07  7637.4  202.29    7660  199.85
  7674.5  202.77  7788.4  205.33  8822.3  225.55  9135.8   237.5  9365.7  252.27
#Mann= 6 ,-1 , 0
  1906.3     .12       0 3372.09     .03       0  6354.6     .05       0
  6569.8     .12       0    7384     .05       0    7505     .12       0
Bank Sta=3372.09,6354.6
XS Rating Curve= 0 ,0
Exp/Cntr=0.3,0.1

Type RM Length L Ch R = 1 ,395000  ,1000,1000,1000
BEGIN DESCRIPTION:
WFSJ Main 392.0
END DESCRIPTION:
XS GIS Cut Line= 3
       3784040.4     10192295.28      3782529.65     10188890.83
      3778517.86     10186561.08
#Sta/Elev= 30
  1275.4  248.62  1433.2  240.77    1521  231.07  1750.4  214.53  1839.9  218.27
  2013.7  232.81  2182.1  236.92  2402.4   232.2  2547.5  224.85  2581.9  219.46
  2628.2  224.35  2773.3  226.88  3128.9  223.03  3276.3  210.85  3294.7  208.51
 3307.19  207.03  3347.7     201    4999  198.52  6426.8  199.02  6574.8   204.9
  6806.7   207.1    7277  208.85  7349.6  204.72  7576.6  204.87  8031.1  213.33
    8133  212.23  8828.4  222.23  9315.9  235.27    9508  252.54  9639.2  260.88
#Mann= 4 ,-1 , 0
  1275.4     .12       0  3276.3      .1       0  3294.7     .03       0
  6806.7     .12       0
Bank Sta=3307.19,6806.7
XS Rating Curve= 0 ,0
Exp/Cntr=0.3,0.1

Type RM Length L Ch R = 1 ,394000  ,1000,1000,1000
BEGIN DESCRIPTION:
WFSJ Main 391.0
END DESCRIPTION:
XS GIS Cut Line= 3
      3785167.88      10190161.1      3783286.97     10188238.71
      3779978.84     10186245.51
#Sta/Elev= 30
  2310.5   240.3  2805.5  219.91  2826.8  220.32  3003.6  206.31    3053  203.78
  3102.6  204.46  3123.7  201.71  3159.1  201.99  3222.7  198.63    3244   198.7
    3251     201    4999  198.13  6703.5  200.99  6725.3  198.99  6773.9  204.45
  6905.9  205.92    6911  205.77  6995.2  206.88  7117.6  203.59  7218.6  203.44
  7387.5  207.58  7577.8  207.06  7684.6  210.26  7730.9  207.19  7999.4  208.76
  8144.8  211.82  8313.7  218.77  8466.4  227.97  8589.4  240.04  8862.2  243.43
#Mann= 4 ,-1 , 0
  2310.5     .12       0  3003.6     .03       0  6905.9     .05       0
    6911     .12       0
Bank Sta=3003.6,6905.9
XS Rating Curve= 0 ,0
Exp/Cntr=0.3,0.1

Type RM Length L Ch R = 1 ,393000  ,1000,1000,1000
BEGIN DESCRIPTION:
WFSJ Main 390.0
END DESCRIPTION:
XS GIS Cut Line= 4
      3785667.83     10189511.04      3784067.76     10187613.91
      3782712.28     10186383.83      3779986.61     10186097.37
#Sta/Elev= 30
  2518.2  237.34  2958.4  229.29  2960.2  229.35    3377  224.38  3475.9  215.34
  3525.5  206.39  3575.9  200.53    4999  197.98    6354     201  6375.6  198.48
  6396.5  201.54  6580.3  205.69    6602  205.91  7146.6   204.9  7289.8  207.87
    7408  204.59  7599.1  209.31  7830.3  209.25    7951  206.47  8021.4   206.7
  8182.2  209.29  8222.5  208.43  8383.4   212.7    8494  211.38  8530.1  209.24
  8845.9  215.76  8996.7  221.52  9207.9  233.07    9419  241.44  9571.1  245.29
#Mann= 5 ,-1 , 0
  2518.2     .12       0  2958.4     .05       0  2960.2     .12       0
  3525.5     .03       0    6602     .12       0
Bank Sta=3525.5,6580.3
XS Rating Curve= 0 ,0
Exp/Cntr=0.3,0.1

Type RM Length L Ch R = 1 ,392000  ,942,942,942
BEGIN DESCRIPTION:
WFSJ Main 389.0
END DESCRIPTION:
XS GIS Cut Line= 4
      3786670.58     10188901.16      3784885.32     10187098.32
       3783059.5     10186097.37        3780056.     10186053.97
#Sta/Elev= 30
  2462.8  242.29  3150.7  227.33  3221.4  224.12  3263.9  219.05  3341.6  220.94
  3412.3  217.95  3539.6  206.19  3546.6  206.37  3765.9  199.24    4999  197.98
    6255  199.53  6505.3  203.61  6684.4  199.13  7085.5     201  7153.8   198.7
  7213.9  203.47  7313.9  198.48  7383.9   202.9  7553.9   201.1  7573.9  198.81
  7663.9   199.2  7753.9  203.69  8033.9  203.74  8133.9  206.51    8824  209.17
  9234.1  214.16  9274.1   212.3  9444.1  218.02  9724.1  234.99   10086  245.64
#Mann= 3 ,-1 , 0
  2462.8     .12       0  3539.6     .03       0  8133.9     .12       0
Bank Sta=3546.6,8133.9
XS Rating Curve= 0 ,0
Exp/Cntr=0.3,0.1

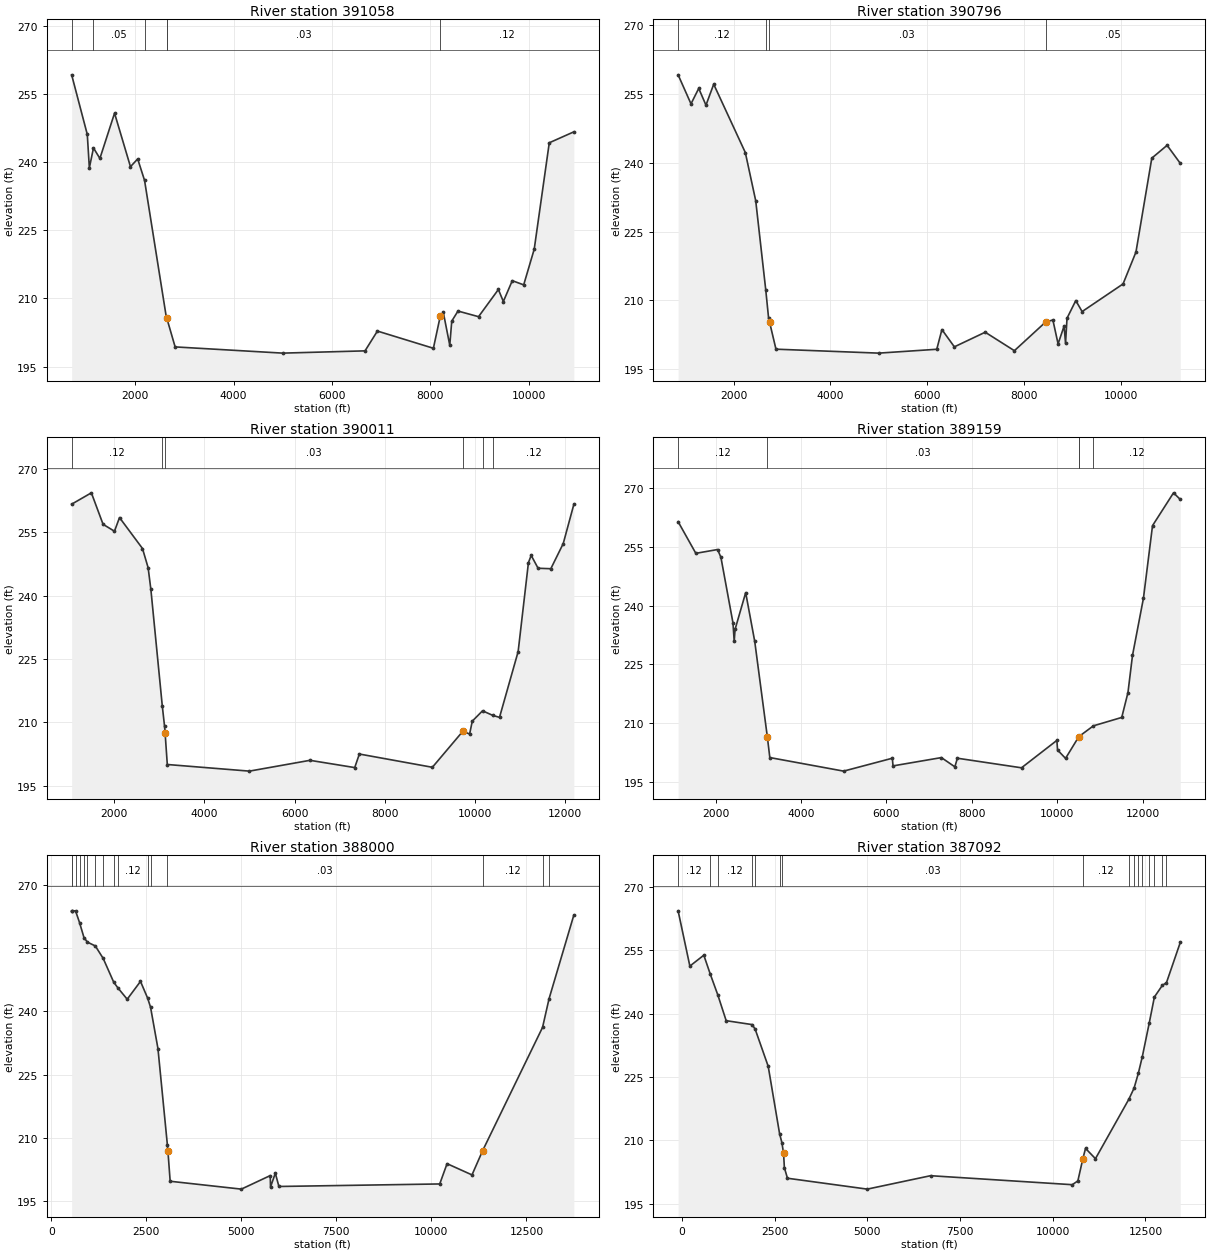
Type RM Length L Ch R = 1 ,391058  ,262,262,262
BEGIN DESCRIPTION:
WFSJ Main 388.0
END DESCRIPTION:
XS GIS Cut Line= 5
      3789439.74     10188241.47      3787755.68     10187833.48
      3784413.67     10185741.47      3783111.58      10185593.9
      3779917.13     10186010.56
#Sta/Elev= 30
   708.4  259.27  1026.4  246.13  1068.2  238.77  1152.1  243.16  1282.4  240.85
  1580.3  250.82  1903.9  239.03  2050.5  240.74  2190.4  236.01  2637.8  205.53
  2638.4  205.49  2644.3  205.59  2811.7  199.33    4999  197.96  6671.6  198.46
  6923.2  202.82  8061.2  199.03  8202.4  206.17  8262.9  206.93    8394  199.69
  8434.3  205.01    8561  207.23  8978.9  205.99  9382.3  211.98  9483.1  209.33
  9664.7  213.92  9896.6     213 10110.7  220.86 10416.6   244.3 10915.9  246.71
#Mann= 6 ,-1 , 0
   708.4     .12       0  1152.1     .05       0  2190.4     .12       0
  2637.8      .1       0  2638.4     .03       0  8202.4     .12       0
Bank Sta=2644.3,8202.4
XS Rating Curve= 0 ,0
Exp/Cntr=0.3,0.1

Type RM Length L Ch R = 1 ,390796  ,785,785,785
BEGIN DESCRIPTION:
WFSJ Main 387.0
END DESCRIPTION:
XS GIS Cut Line= 5
      3789517.82     10188015.77      3787868.53     10187573.06
       3784421.4     10185473.31      3783137.62     10185333.48
      3779812.97     10185750.15
#Sta/Elev= 30
   850.1  259.17  1116.5  252.84  1276.5  256.21  1426.1  252.55  1586.1  257.12
  2240.1  242.22  2454.9  231.72  2662.7  212.25  2720.8  206.16  2742.1  205.21
  2873.8  199.34    4999  198.48  6199.3  199.32  6305.9  203.61  6563.1  199.85
  7201.2  203.04  7804.7  199.01  8449.6  205.25  8600.8  205.71  8708.5  200.49
  8832.6  204.38  8862.8  200.63    8893  206.09  9074.4  209.94  9205.5  207.54
   10052  213.57 10318.9  220.52 10646.6     241 10963.1   243.8 11236.1  239.86
#Mann= 4 ,-1 , 0
   850.1     .12       0  2662.7     .05       0  2720.8     .03       0
  8449.6     .05       0
Bank Sta=2742.1,8449.6
XS Rating Curve= 0 ,0
Exp/Cntr=0.3,0.1

Type RM Length L Ch R = 1 ,390011  ,852,852,852
BEGIN DESCRIPTION:
WFSJ Main 386.0
END DESCRIPTION:
XS GIS Cut Line= 4
      3789848.75     10187629.25      3787233.72     10186262.06
      3783197.26     10184015.97       3779921.6     10182627.61
#Sta/Elev= 30
  1060.4  261.68  1497.4  264.37  1756.7  256.91  2009.3  255.27  2120.7  258.51
  2629.9  251.18  2755.2  246.62  2815.8  241.49  3068.5  213.92  3119.2  209.05
  3131.9  207.38  3179.8  200.01    4999  198.44  6341.1     201  7332.8  199.28
  7435.8  202.49  9053.5  199.35  9726.8  207.86    9879  207.24  9937.9  210.28
 10165.1  212.73 10396.9  211.62 10541.5  211.18 10954.2  226.76 11182.3  247.84
 11243.1  249.55   11396   246.5 11678.1  246.39 11953.4  252.35 12188.3  261.63
#Mann= 6 ,-1 , 0
  1060.4     .12       0  3068.5     .05       0  3119.2     .03       0
  9726.8     .12       0 10165.1     .05       0 10396.9     .12       0
Bank Sta=3131.9,9726.8
XS Rating Curve= 0 ,0
Exp/Cntr=0.3,0.1

Type RM Length L Ch R = 1 ,389159  ,1159,1159,1159
BEGIN DESCRIPTION:
Mapping XS 06ff7629
END DESCRIPTION:
XS GIS Cut Line= 4
       3790098.3     10187477.34      3788807.07     10186251.21
      3782947.69     10182876.64      3779855.25     10181986.89
#Sta/Elev= 30
  1123.4  261.48  1538.3  253.39  2047.9  254.36  2125.6  252.37  2408.3  235.59
  2436.6  230.92    2458  233.98  2705.6  243.34  2917.4  230.88  3212.3  206.51
  3270.8  201.17    4999   197.7  6140.2     201    6156  199.04  7288.3  201.16
  7604.3   198.8  7663.2     201  9164.7  198.55  9993.3  205.56 10008.9   203.1
 10196.2  200.96 10507.2  206.52 10848.3  209.28 11512.4  211.43 11657.6  217.77
 11763.8  227.27 12020.5  241.92   12233  260.47 12724.8  268.86 12883.6  267.16
#Mann= 5 ,-1 , 0
  1123.4     .12       0  3212.3     .03       0 10507.2     .12       0
 10507.2      .1       0 10848.3     .12       0
Bank Sta=3212.3,10507.2
XS Rating Curve= 0 ,0
Exp/Cntr=0.3,0.1

Type RM Length L Ch R = 1 ,388000  ,908,908,908
BEGIN DESCRIPTION:
WFSJ Main 385.0
END DESCRIPTION:
XS GIS Cut Line= 4
      3790391.28     10187292.91      3789447.26      10185372.3
      3787460.63     10184162.85      3779714.15     10180098.85
#Sta/Elev= 30
   534.1  263.89   534.2  263.89   635.9  263.92   741.8  261.12   859.1  257.54
   949.4  256.48  1156.9  255.57  1364.5   252.6  1640.4  246.97    1752  245.59
  1995.8  242.91  2345.5  247.15  2533.3  243.17  2609.9  241.02  2804.8  231.19
  3053.9   208.2  3068.2  206.73  3126.3  199.65    4999  197.78  5759.7     201
  5766.7  198.28  5893.4  201.58  5987.2  198.41 10219.2  199.01   10412  203.83
   11068  201.16   11350  206.96 12924.6  236.22 13095.1  243.01 13747.8  262.91
#Mann= 16 ,-1 , 0
   534.1     .05       0   534.2     .12       0   635.9     .05       0
   741.8     .12       0   859.1     .05       0   949.4     .12       0
  1156.9     .12       0  1364.5     .12       0  1640.4     .05       0
    1752     .12       0  2533.3     .05       0  2609.9     .12       0
  3053.9     .03       0   11350     .12       0 12924.6      .1       0
 13095.1     .12       0
Bank Sta=3068.2,11350
XS Rating Curve= 0 ,0
Exp/Cntr=0.3,0.1

Type RM Length L Ch R = 1 ,387092  ,1092,1092,1092
BEGIN DESCRIPTION:
WFSJ Main 384.0
END DESCRIPTION:
XS GIS Cut Line= 5
      3790530.15     10187153.98      3789579.64     10185318.05
      3788798.39     10183820.65      3784879.12      10182036.8
      3779983.48     10179575.96
#Sta/Elev= 30
  -101.6  264.34   215.1  251.25   591.4  253.83   768.6  249.27   968.5  244.43
  1194.3  238.32  1896.8  237.39  1977.6  236.27  2327.7  227.51    2634  211.58
  2697.5  209.39  2741.7  206.93  2763.8   203.5  2846.5     201    4999  198.42
  6705.8   201.6   10527  199.47 10677.7  200.37 10811.6  205.58 10884.2  208.07
 11152.1  205.63 12053.9  219.73 12193.4  222.34 12307.9  225.84 12416.3  229.82
 12600.8  237.69 12741.4  243.93 12958.1  246.71 13066.5  247.31 13440.2  256.87
#Mann= 16 ,-1 , 0
  -101.6     .12       0   768.6     .05       0   968.5     .12       0
  1896.8     .05       0  1977.6     .12       0    2634     .05       0
  2697.5     .03       0 10811.6     .12       0 12053.9      .1       0
 12193.4     .12       0 12307.9     .05       0 12416.3     .12       0
 12600.8     .05       0 12741.4     .12       0 12958.1     .05       0
 13066.5     .12       0
Bank Sta=2741.7,10811.6
XS Rating Curve= 0 ,0
Exp/Cntr=0.3,0.1