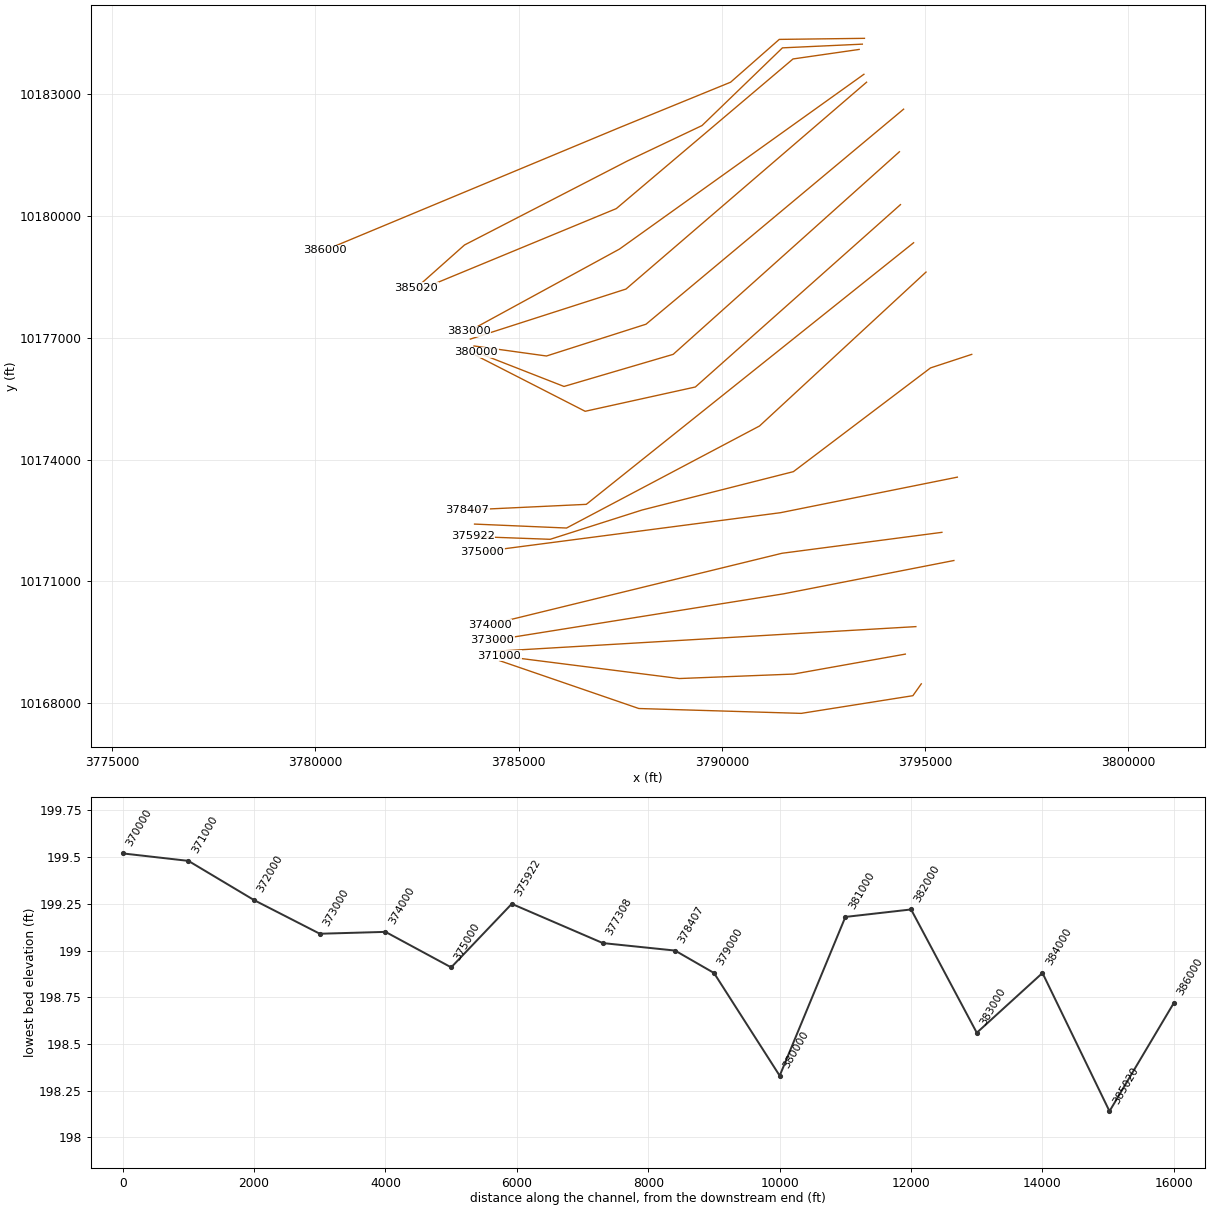
HEC-RAS study WFSJ Main.prj: WFSJ Main Base Level Engineering

--- WFSJ Main.g02 (geometry) --- (continued)

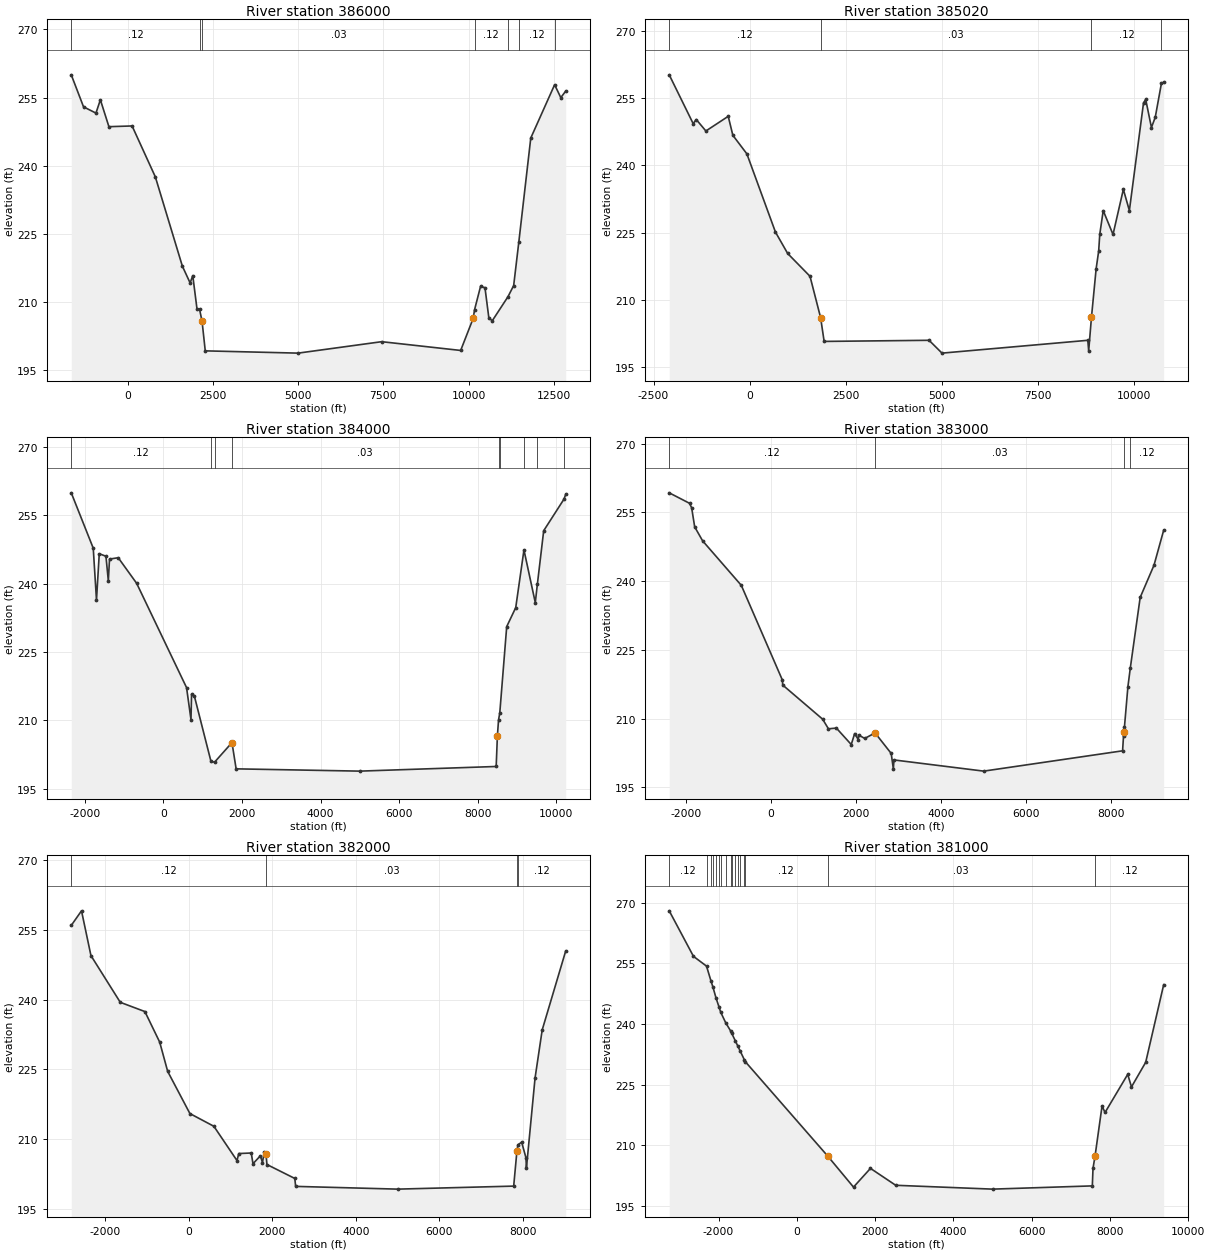
Type RM Length L Ch R = 1 ,386000  ,980,980,980
BEGIN DESCRIPTION:
WFSJ Main 383.0
END DESCRIPTION:
XS GIS Cut Line= 5
      3793511.93     10184380.55      3791415.58     10184354.51
      3790217.66     10183299.82      3787476.45     10182178.92
      3780231.72     10179159.63
#Sta/Elev= 30
 -1654.1  260.01 -1294.3  252.96    -930  251.58    -800  254.51  -549.9  248.59
   130.1  248.75   812.1  237.53  1605.2  217.86    1832  214.18  1909.8  215.79
    2035  208.37  2107.9   208.4  2182.3  205.74  2275.9  199.22    4999  198.72
  7451.6  201.24  9767.6  199.31 10133.8  206.36   10176  208.31 10350.3   213.4
 10480.3  213.13 10595.2  206.41   10696  205.87 11154.8  211.14 11322.1   213.6
 11472.7  223.16 11823.7  246.09   12523  257.83 12704.3  254.99 12848.7  256.43
#Mann= 7 ,-1 , 0
 -1654.1     .12       0  2107.9     .05       0  2182.3     .03       0
   10176     .12       0 11154.8      .1       0 11472.7     .12       0
   12523     .05       0
#XS Ineff= 1 ,-1
 10350.3   11350   213.4
Permanent Ineff=
       F
Bank Sta=2182.3,10133.8
XS Rating Curve= 0 ,0
Exp/Cntr=0.3,0.1

Type RM Length L Ch R = 1 ,385020  ,1020,1020,1020
BEGIN DESCRIPTION:
WFSJ Main 382.0
END DESCRIPTION:
XS GIS Cut Line= 6
      3793459.89     10184237.32       3791493.7     10184146.18
      3789514.53     10182232.11       3787678.6     10181359.72
      3783668.18      10179289.4      3782484.07     10178235.42
#Sta/Elev= 30
 -2091.4  260.18 -1468.7   249.3 -1388.6  250.22 -1138.3  247.66  -557.7  250.93
  -437.6   246.7     -73  242.56   669.6  225.13   987.8  220.35  1567.9  215.27
  1843.7  206.05  1935.5  200.75  4662.9     201    4999  198.14  8789.6     201
  8811.8  198.64  8883.9   206.1  9005.6  216.93    9072  220.92  9099.8  224.61
  9189.7  229.91  9444.3  224.59  9713.2  234.65  9869.5  229.92 10237.5  253.93
 10294.3  254.69 10443.1  248.43 10542.1  250.71 10702.4  258.26 10761.4  258.54
#Mann= 4 ,-1 , 0
 -2091.4     .12       0  1843.7     .03       0  8883.9     .12       0
 10702.4     .05       0
Bank Sta=1843.7,8883.9
XS Rating Curve= 0 ,0
Exp/Cntr=0.3,0.1

Type RM Length L Ch R = 1 ,384000  ,1000,1000,1000
BEGIN DESCRIPTION:
WFSJ Main 381.0
END DESCRIPTION:
XS GIS Cut Line= 4
      3793381.75     10184107.12      3791754.12     10183872.74
      3787404.28     10180185.92      3782562.11     10178182.92
#Sta/Elev= 30
 -2346.5  259.95 -1786.9   247.8 -1704.4  236.41 -1633.9  246.59 -1463.6  246.03
   -1403  240.65 -1372.7  245.41 -1150.9  245.71  -681.8  240.09   588.1  217.21
   701.2  210.19   715.5  215.72   786.9  215.36  1209.2  201.04  1300.7  200.84
  1744.4  205.14  1850.2  199.38    4999  198.88  8469.9   199.9  8501.1  206.66
  8530.4  210.14  8561.6  211.65  8737.9  230.59  8967.7  234.76    9177  247.41
  9465.5  235.86  9518.5   239.9  9679.5  251.64 10194.7  258.55 10240.1  259.61
#Mann= 9 ,-1 , 0
 -2346.5     .12       0  1209.2      .1       0  1300.7     .05       0
  1744.4     .03       0  8530.4      .1       0  8561.6     .12       0
    9177      .1       0  9518.5     .12       0 10194.7     .05       0
Bank Sta=1744.4,8501.1
XS Rating Curve= 0 ,0
Exp/Cntr=0.3,0.1

Type RM Length L Ch R = 1 ,383000  ,1000,1000,1000
BEGIN DESCRIPTION:
WFSJ Main 380.0
END DESCRIPTION:
XS GIS Cut Line= 3
       3793498.9     10183495.13      3787483.01      10179189.2
      3783767.85     10177161.07
#Sta/Elev= 30
 -2398.1  259.25   -1921  256.97 -1870.6  255.99 -1799.4  251.83 -1612.7  248.78
  -702.3  239.07   264.5   218.4   271.8  217.33  1210.4  209.89  1346.8  207.79
  1533.5  207.95  1883.7  204.36  1963.5  206.75  2049.5  205.42  2055.6  206.44
  2200.6  205.69  2443.8  206.89  2823.4  202.42  2873.8  199.06  2888.5     201
    4999  198.56  8266.1  202.99  8287.9  206.19  8304.1     207  8309.9  208.18
  8391.4  216.99  8446.2  220.95  8679.9  236.44  9004.8  243.46  9232.7   251.1
#Mann= 4 ,-1 , 0
 -2398.1     .12       0  2443.8     .03       0  8309.9     .05       0
  8446.2     .12       0
Bank Sta=2443.8,8304.1
XS Rating Curve= 0 ,0
Exp/Cntr=0.3,0.1

Type RM Length L Ch R = 1 ,382000  ,1000,1000,1000
BEGIN DESCRIPTION:
WFSJ Main 379.0
END DESCRIPTION:
XS GIS Cut Line= 3
      3793564.04     10183299.85      3787642.98     10178204.39
      3783812.15     10176971.94
#Sta/Elev= 30
 -2811.7     256 -2566.6  259.14 -2340.6   249.5 -1638.4  239.44 -1049.2  237.45
  -694.8  230.87  -503.8  224.57    28.3  215.49   602.2  212.75  1155.2  205.37
    1198  206.88  1496.4     207  1538.1  204.69  1715.9   206.4  1765.3  204.94
    1808  207.24  1850.8  206.78  1871.7  204.52  2538.8  201.52  2559.6  199.81
    4999  199.22  7778.7  199.87 7855.38  207.35  7879.7  208.75  7969.4  209.33
  8072.8  205.96  8083.3  203.72  8290.2  223.14  8461.5  233.51  9024.2  250.51
#Mann= 4 ,-1 , 0
 -2811.7     .12       0  1850.8     .03       0 7855.38     .05       0
  7879.7     .12       0
Bank Sta=1850.8,7855.38
XS Rating Curve= 0 ,0
Exp/Cntr=0.3,0.1

Type RM Length L Ch R = 1 ,381000  ,1000,1000,1000
BEGIN DESCRIPTION:
WFSJ Main 378.0
END DESCRIPTION:
XS GIS Cut Line= 4
      3794475.51     10182635.79      3788136.25     10177338.51
      3785686.41     10176555.03      3783902.75      10176802.4
#Sta/Elev= 30
 -3261.2  267.99 -2641.5  256.73 -2308.3  254.32 -2192.7   250.6 -2147.6  249.25
   -2068  246.53   -1987  244.15 -1943.4  242.87 -1818.8  240.33 -1694.1  238.32
 -1665.7  237.74 -1569.5  235.79   -1505  234.48 -1444.9  233.26 -1344.4  231.22
 -1320.3  230.73  783.44  207.41  1447.4  199.68  1880.8  204.31  2526.3  200.13
    4999  199.18  7549.6  199.98    7567  204.32 7619.97  207.41  7797.9  219.73
  7874.7  218.13  8453.6  227.56  8549.9  224.45  8913.3  230.54  9372.8  249.73
#Mann= 17 ,-1 , 0
 -3261.2     .12       0 -2308.3     .12       0 -2192.7     .05       0
 -2147.6     .12       0   -2068     .05       0   -1987     .12       0
 -1943.4     .05       0 -1818.8     .05       0 -1694.1     .12       0
 -1665.7     .05       0 -1569.5     .12       0   -1505     .05       0
 -1444.9     .12       0 -1344.4     .05       0 -1320.3     .12       0
  783.44     .03       0 7619.97     .12       0
Bank Sta=783.44,7619.97
XS Rating Curve= 0 ,0
Exp/Cntr=0.3,0.1

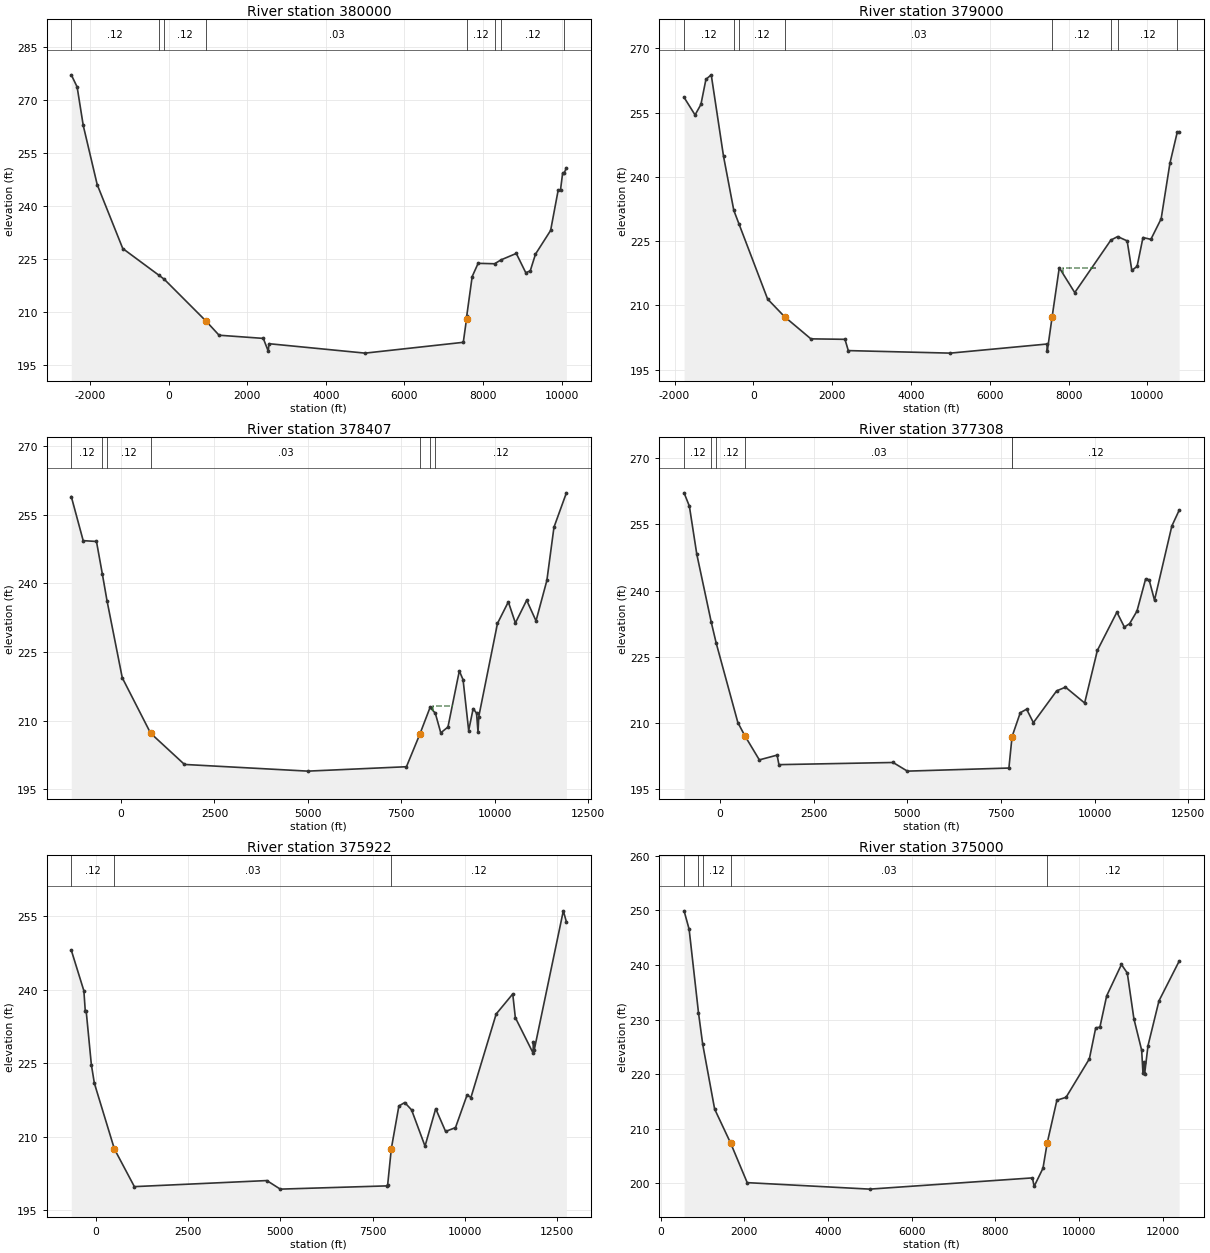
Type RM Length L Ch R = 1 ,380000  ,1000,1000,1000
BEGIN DESCRIPTION:
WFSJ Main 377.0
END DESCRIPTION:
XS GIS Cut Line= 4
      3794372.39     10181586.26      3788804.67     10176595.82
      3786117.21     10175805.03      3783955.79     10176651.37
#Sta/Elev= 30
 -2476.9  277.11 -2328.3  273.67 -2172.8  262.77 -1818.4  246.06 -1167.3  227.94
  -244.2  220.35  -112.3  219.25  954.55  207.37  1283.3   203.4  2409.1   202.5
    2537  198.83  2551.2     201    4999  198.33  7498.4  201.39  7580.9  207.98
  7586.1  208.84  7724.7  220.01  7875.9  223.75  8294.8  223.63  8461.1  224.74
  8847.1  226.55  9088.7  221.09  9202.6  221.62  9335.6  226.35  9720.9  233.06
  9913.5  244.49  9973.2  244.62 10027.4  249.33 10060.9  249.21 10122.6  250.78
#Mann= 8 ,-1 , 0
 -2476.9     .12       0  -244.2     .05       0  -112.3     .12       0
  954.55     .03       0  7586.1     .12       0  8294.8     .05       0
  8461.1     .12       0 10060.9     .05       0
Bank Sta=954.55,7580.9
XS Rating Curve= 0 ,0
Exp/Cntr=0.3,0.1

Type RM Length L Ch R = 1 ,379000  ,593,593,593
BEGIN DESCRIPTION:
WFSJ Main 376.0
END DESCRIPTION:
XS GIS Cut Line= 4
      3794398.43     10180284.17      3789350.27     10175791.52
      3786638.05     10175193.05      3783942.75     10176573.25
#Sta/Elev= 30
 -1757.8  258.54 -1478.7  254.44 -1329.9   256.9 -1202.8  262.75 -1068.2   263.8
  -756.3  244.79  -495.5  232.18  -367.7   229.1   362.5  211.49  793.08  207.37
  1460.4  202.21    2325   202.1  2409.4  199.47    4999  198.88    7450     201
  7460.2  199.43  7583.1  207.42  7762.9   218.8  8155.6     213  9072.9  225.25
  9244.6  226.07  9485.4  225.06  9604.2  218.17  9737.5  219.12  9887.3  225.85
 10087.1  225.42   10348  230.21   10570  243.13 10756.9  250.43 10805.6  250.51
#Mann= 8 ,-1 , 0
 -1757.8     .12       0  -495.5     .05       0  -367.7     .12       0
  793.08     .03       0  7583.1     .12       0  9072.9     .05       0
  9244.6     .12       0 10756.9     .05       0
#XS Ineff= 1 ,-1
  7850.3    8700  218.82
Permanent Ineff=
       F
Bank Sta=793.08,7583.1
XS Rating Curve= 0 ,0
Exp/Cntr=0.3,0.1

Type RM Length L Ch R = 1 ,378407  ,1099,1099,1099
BEGIN DESCRIPTION:
WFSJ Main 375.0
END DESCRIPTION:
XS GIS Cut Line= 3
      3794721.42     10179344.99      3786665.82     10172900.52
       3783735.3     10172761.63
#Sta/Elev= 30
 -1330.8  258.94 -1012.4  249.32  -657.1  249.14  -498.4  241.98  -375.7  236.24
    32.9  219.39  792.05  207.28  1697.7  200.46    4999     199  7638.2  199.96
  8001.6  207.17  8270.1   212.9  8410.2  211.66    8557  207.36  8749.1  208.63
  9053.4  220.87  9153.6  218.96  9303.7  207.86  9423.9  212.65    9514  211.65
    9554  207.51    9574  210.92 10074.6  231.25 10364.9  235.95   10554  231.34
 10855.5  236.31 11105.7  231.81 11396.1  240.62 11586.3  252.25 11919.2  259.76
#Mann= 7 ,-1 , 0
 -1330.8     .12       0  -498.4     .05       0  -375.7     .12       0
  792.05     .03       0  8001.6     .12       0  8270.1     .05       0
  8410.2     .12       0
#XS Ineff= 2 ,-1
  9053.4    9865  220.87  8356.9    8875  213.12
Permanent Ineff=
       F       F
Bank Sta=792.05,8001.6
XS Rating Curve= 0 ,0
Exp/Cntr=0.3,0.1

Type RM Length L Ch R = 1 ,377308  ,1386,1386,1386
BEGIN DESCRIPTION:
WFSJ Main 374.0
END DESCRIPTION:
XS GIS Cut Line= 4
      3795026.95     10178622.75      3790929.71     10174831.07
      3786179.71     10172317.18       3783915.8     10172414.41
#Sta/Elev= 30
  -964.5  262.15  -822.4  259.12  -624.5  248.22  -236.8  232.76  -106.9  228.09
   472.6  210.04   656.3   207.1  1045.8  201.59  1519.8  202.67  1569.2  200.51
    4618     201    4999  199.04  7710.8  199.74    7795  206.87  8014.3  212.28
    8184  213.09  8364.6  210.03  8985.7  217.24  9222.1  218.08  9733.2  214.49
 10074.1  226.43 10594.6  235.09 10794.8  231.71 10934.9  232.49 11130.9  235.33
 11362.5  242.63 11455.4  242.43 11599.2   237.8 12062.5  254.63 12258.2  258.21
#Mann= 6 ,-1 , 0
  -964.5     .12       0  -236.8    .075       0  -106.9     .12       0
   656.3     .03       0    7795     .05       0    7795     .12       0
Bank Sta=656.3,7795
XS Rating Curve= 0 ,0
Exp/Cntr=0.3,0.1

Type RM Length L Ch R = 1 ,375922  ,922,922,922
BEGIN DESCRIPTION:
WFSJ Main 373.0
END DESCRIPTION:
XS GIS Cut Line= 6
      3796151.92     10176594.95      3795138.05     10176261.63
      3791763.05     10173706.07      3788040.82     10172761.63
      3785776.93      10172039.4      3783874.11     10172108.85
#Sta/Elev= 30
  -665.9  248.08  -324.8  239.78  -286.6  235.58  -261.6  235.57  -122.3   224.7
   -40.6  220.89     502  207.46  1043.8  199.76  4634.7     201    4999  199.25
  7879.6  199.91  7910.5  200.17  8009.1  207.52  8213.9  216.24  8372.6  216.95
  8557.9  215.45  8922.5  208.04  9212.3  215.69  9480.4  211.04  9748.4  211.82
   10063   218.5   10167  217.97 10851.2  235.04 11300.6  239.14 11370.6  234.31
   11851  227.08 11861.3  229.38   11881  227.63 12671.5  256.13 12755.3  253.87
#Mann= 3 , 0 , 0
  -665.9     .12       0     502     .03       0  8009.1     .12       0
#XS Ineff= 1 ,-1
  8372.6   10020  216.95
Permanent Ineff=
       F
Bank Sta=502,8009.1
XS Rating Curve= 0 ,0
Exp/Cntr=0.3,0.1

Type RM Length L Ch R = 1 ,375000  ,1000,1000,1000
BEGIN DESCRIPTION:
WFSJ Main 372.0
END DESCRIPTION:
XS GIS Cut Line= 3
       3795797.8     10173570.66      3791444.05     10172694.65
      3784108.65     10171735.83
#Sta/Elev= 30
     559  249.94     680  246.57     904  231.25  1003.9  225.51  1290.1  213.59
 1673.74  207.33  2068.6   200.1    4999  198.91    8889  200.97  8929.3  199.41
  9141.1  202.74    9242  207.37  9473.9  215.21  9693.1  215.75 10250.5   222.8
 10401.8  228.47 10502.6  228.62   10664  234.35   11017   240.1 11157.3  238.53
 11315.1  230.15   11501  224.37 11531.3  220.28 11546.8  222.04 11551.9  220.28
 11561.5  222.24 11571.6  220.04 11652.3  225.21 11914.5  233.43 12397.8  240.72
#Mann= 5 ,-1 , 0
     559     .12       0     904     .05       0  1003.9     .12       0
 1673.74     .03       0    9242     .12       0
Bank Sta=1673.74,9242
XS Rating Curve= 0 ,0
Exp/Cntr=0.3,0.1

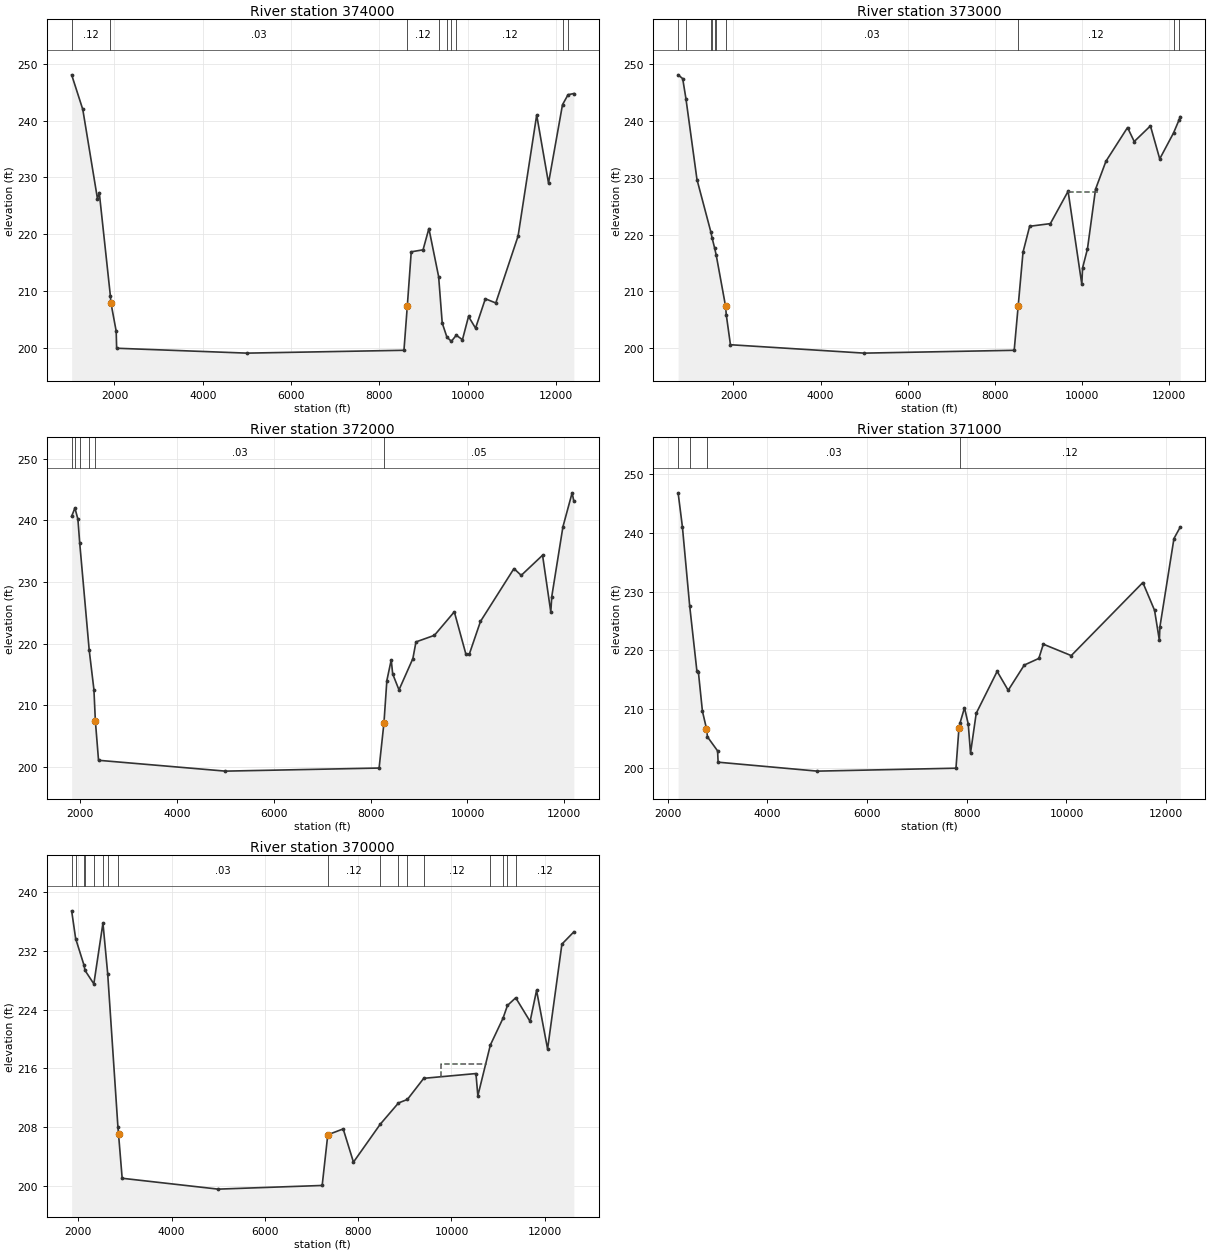
Type RM Length L Ch R = 1 ,374000  ,1000,1000,1000
BEGIN DESCRIPTION:
WFSJ Main 371.0
END DESCRIPTION:
XS GIS Cut Line= 3
       3795417.9     10172211.08      3791482.34     10171695.39
      3784290.99     10169937.44
#Sta/Elev= 30
  1030.8  248.05    1283  241.96  1615.8  226.23  1656.1  227.33  1908.3  209.13
  1919.7  207.96  2039.4  202.96  2049.5  199.96    4999   199.1  8556.2   199.6
 8632.61  207.45  8720.9  216.92  8988.6  217.27  9120.7  221.02  9341.4  212.55
  9422.5   204.4  9529.4   201.9  9630.1  201.18  9740.7  202.25  9880.6  201.46
   10018  205.55 10177.2  203.49 10398.9  208.66 10635.3  207.92 11140.1  219.68
 11561.8  240.98 11829.8  229.01 12146.4   242.8 12272.1  244.55 12403.1  244.76
#Mann= 9 ,-1 , 0
  1030.8     .12       0  1908.3     .03       0 8632.61     .12       0
  9341.4     .05       0  9529.4      .1       0  9630.1     .05       0
  9740.7     .12       0 12146.4     .05       0 12272.1     .12       0
#XS Ineff= 1 ,-1
  9120.7   11300  221.02
Permanent Ineff=
       F
Bank Sta=1919.7,8632.61
XS Rating Curve= 0 ,0
Exp/Cntr=0.3,0.1

Type RM Length L Ch R = 1 ,373000  ,1000,1000,1000
BEGIN DESCRIPTION:
WFSJ Main 370.0
END DESCRIPTION:
XS GIS Cut Line= 3
      3795712.75     10171516.84      3791520.63     10170696.12
      3784351.33     10169548.32
#Sta/Elev= 30
   728.3  248.15   833.3  247.48   907.4  243.97  1161.3  229.69  1478.4   220.5
  1506.3  219.47  1567.3   217.6  1603.9  216.34  1818.7  207.33  1833.8  205.87
    1930  200.57    4999  199.09  8446.1  199.59  8537.3  207.38  8648.7  216.89
  8800.7  221.45  9276.6  221.92    9684  227.63  9999.1   211.2 10015.9   214.1
 10128.2  217.45 10314.2  227.99 10552.6  232.91 11048.8  238.86 11202.6  236.39
 11574.7  239.15 11788.1  233.33 12106.2  237.92 12229.6  240.16 12260.6  240.78
#Mann= 10 ,-1 , 0
   728.3     .05       0   907.4     .12       0  1478.4     .05       0
  1506.3     .12       0  1567.3     .05       0  1603.9     .12       0
  1833.8     .03       0  8537.3     .12       0 12106.2     .05       0
 12229.6     .12       0
#XS Ineff= 1 ,-1
  9678.9   10400  227.56
Permanent Ineff=
       F
Bank Sta=1818.7,8537.3
XS Rating Curve= 0 ,0
Exp/Cntr=0.3,0.1

Type RM Length L Ch R = 1 ,372000  ,1000,1000,1000
BEGIN DESCRIPTION:
WFSJ Main 369.0
END DESCRIPTION:
XS GIS Cut Line= 3
      3794776.94     10169888.36      3791606.71     10169703.71
      3784422.85     10169280.73
#Sta/Elev= 30
  1824.4  240.66  1891.5  242.02  1953.7  240.19  1990.2  236.39  2187.4  218.89
  2284.3  212.52  2314.3  207.41  2379.6  201.03    4999  199.27  8174.3  199.77
  8274.5   207.1  8334.6  213.99  8424.8  217.34  8454.8  215.06  8585.1  212.47
  8871.7  217.55  8935.7  220.26  9316.3  221.33  9727.8  225.15  9967.4  218.26
 10037.6  218.28   10268  223.59 10959.2  232.17 11109.4  231.07 11550.2  234.34
 11720.5  225.11 11740.5  227.63 11970.9  238.96 12161.2  244.48 12196.3  243.12
#Mann= 6 ,-1 , 0
  1824.4     .12       0  1891.5     .05       0  1990.2     .12       0
  2187.4     .05       0  2314.3     .03       0  8274.5     .05       0
#XS Ineff= 1 ,-1
  8424.8    8905  217.34
Permanent Ineff=
       F
Bank Sta=2314.3,8274.5
XS Rating Curve= 0 ,0
Exp/Cntr=0.3,0.1

Type RM Length L Ch R = 1 ,371000  ,1000,1000,1000
BEGIN DESCRIPTION:
WFSJ Main 368.0
END DESCRIPTION:
XS GIS Cut Line= 4
      3794517.84     10169211.07       3791768.3     10168719.71
      3788954.49     10168609.37      3784521.42     10169171.17
#Sta/Elev= 30
  2206.9  246.79  2292.7  241.03  2438.6  227.61  2582.8  216.56  2613.2  216.37
  2694.8  209.66  2775.8  206.72  2796.1   205.3  2999.2  202.92  3009.4     201
    4999  199.48  7782.6  199.98  7842.8  206.81    7863  207.63  7953.8  210.25
  8028.8  207.49  8074.7  202.54    8189  209.31  8608.9  216.44  8830.7  213.22
  9153.2  217.51  9445.5  218.64  9535.4  221.06   10096  219.12 11532.6  231.54
 11767.8  226.82 11864.7  221.71 11874.8  223.98 12157.1  239.02 12284.5  240.99
#Mann= 4 ,-1 , 0
  2206.9     .12       0  2438.6     .05       0  2796.1     .03       0
    7863     .12       0
#XS Ineff= 1 ,-1
  8608.9    9220  216.44
Permanent Ineff=
       F
Bank Sta=2775.8,7842.8
XS Rating Curve= 0 ,0
Exp/Cntr=0.3,0.1

Type RM Length L Ch R = 1 ,370000  ,1000,1000,1000
BEGIN DESCRIPTION:
WFSJ Main 367.0
END DESCRIPTION:
XS GIS Cut Line= 5
      3794910.61     10168478.64      3794704.02     10168186.97
      3791955.86     10167751.28      3787959.23       10167871.
      3784532.51      10169049.7
#Sta/Elev= 30
  1860.1  237.47    1946  233.68  2125.1  230.05  2145.9  229.35  2335.6  227.51
  2530.8   235.8  2632.3  228.91  2851.5  208.01  2864.3  207.07  2942.6     201
    4999  199.52    7229  200.02  7349.1  206.93  7679.2  207.73  7899.3   203.2
  8472.1  208.36  8864.1  211.27  9055.4  211.75  9405.6  214.63 10524.2  215.28
   10565  212.25 10833.1  219.17 11104.9  222.83 11199.9  224.57 11376.8  225.61
 11684.7  222.39 11823.4  226.62 12059.5  218.63 12366.6  232.93 12622.2   234.6
#Mann= 17 ,-1 , 0
  1860.1     .12       0    1946     .05       0  2125.1     .12       0
  2145.9     .05       0  2335.6     .12       0  2530.8     .05       0
  2632.3     .12       0  2851.5     .03       0  7349.1     .12       0
  8472.1     .05       0  8864.1     .12       0  9055.4     .05       0
  9405.6     .12       0 10833.1     .05       0 11104.9     .12       0
 11199.9     .05       0 11376.8     .12       0
#XS Ineff= 1 ,-1
  9779.9   10770  216.63
Permanent Ineff=
       F
Bank Sta=2864.3,7349.1
XS Rating Curve= 0 ,0
Exp/Cntr=0.3,0.1