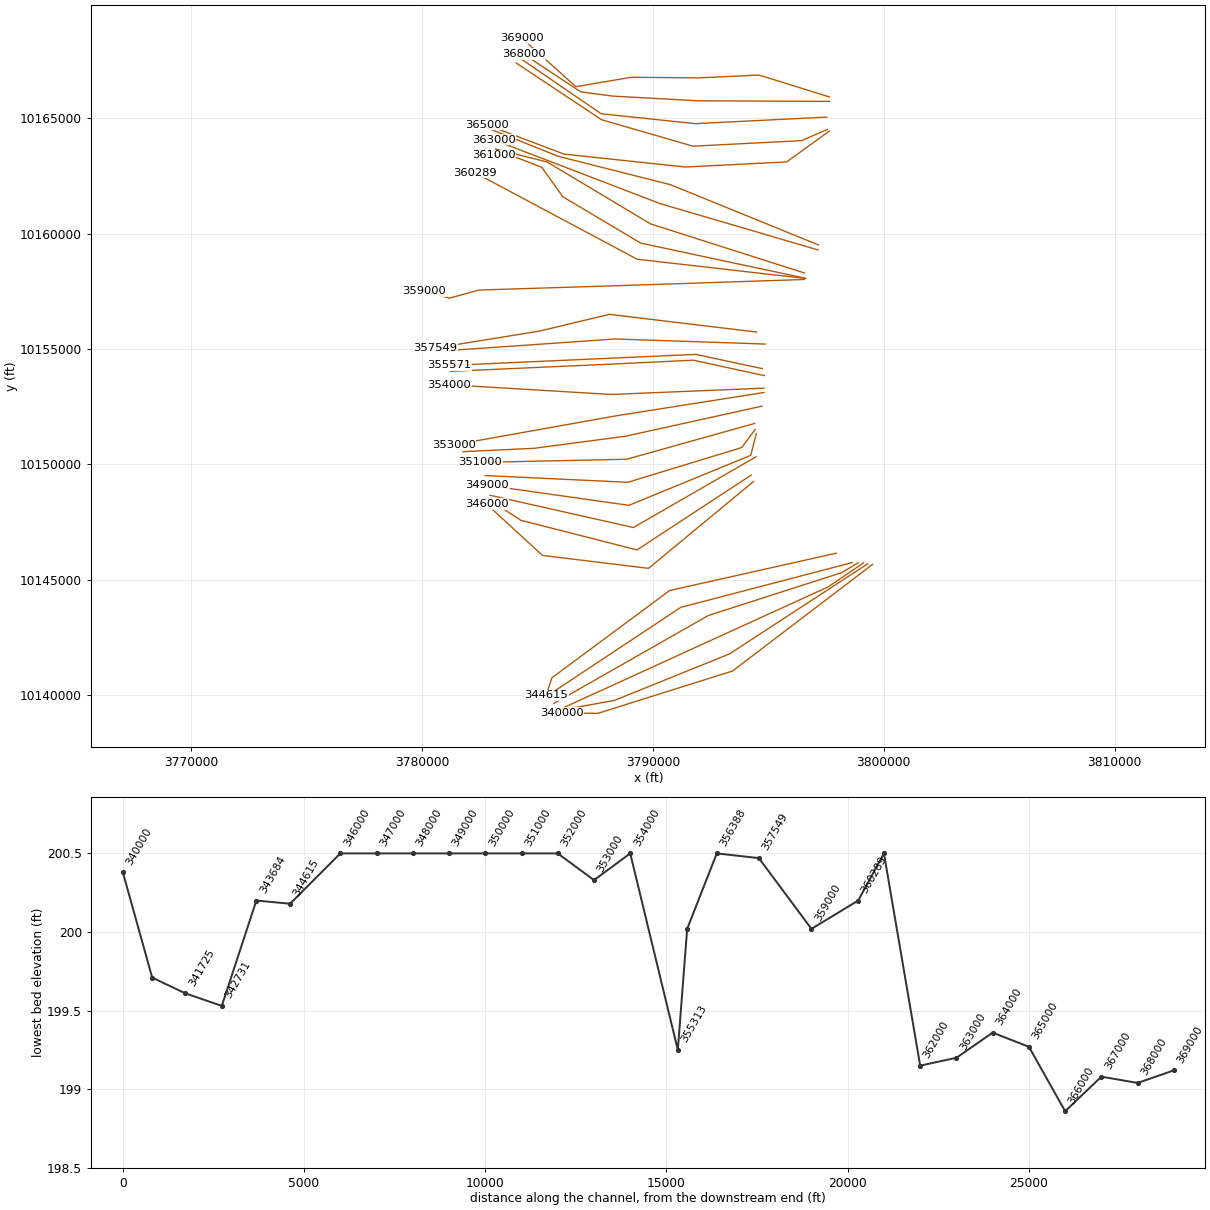
HEC-RAS study WFSJ Main.prj: WFSJ Main Base Level Engineering

--- WFSJ Main.g02 (geometry) --- (continued)

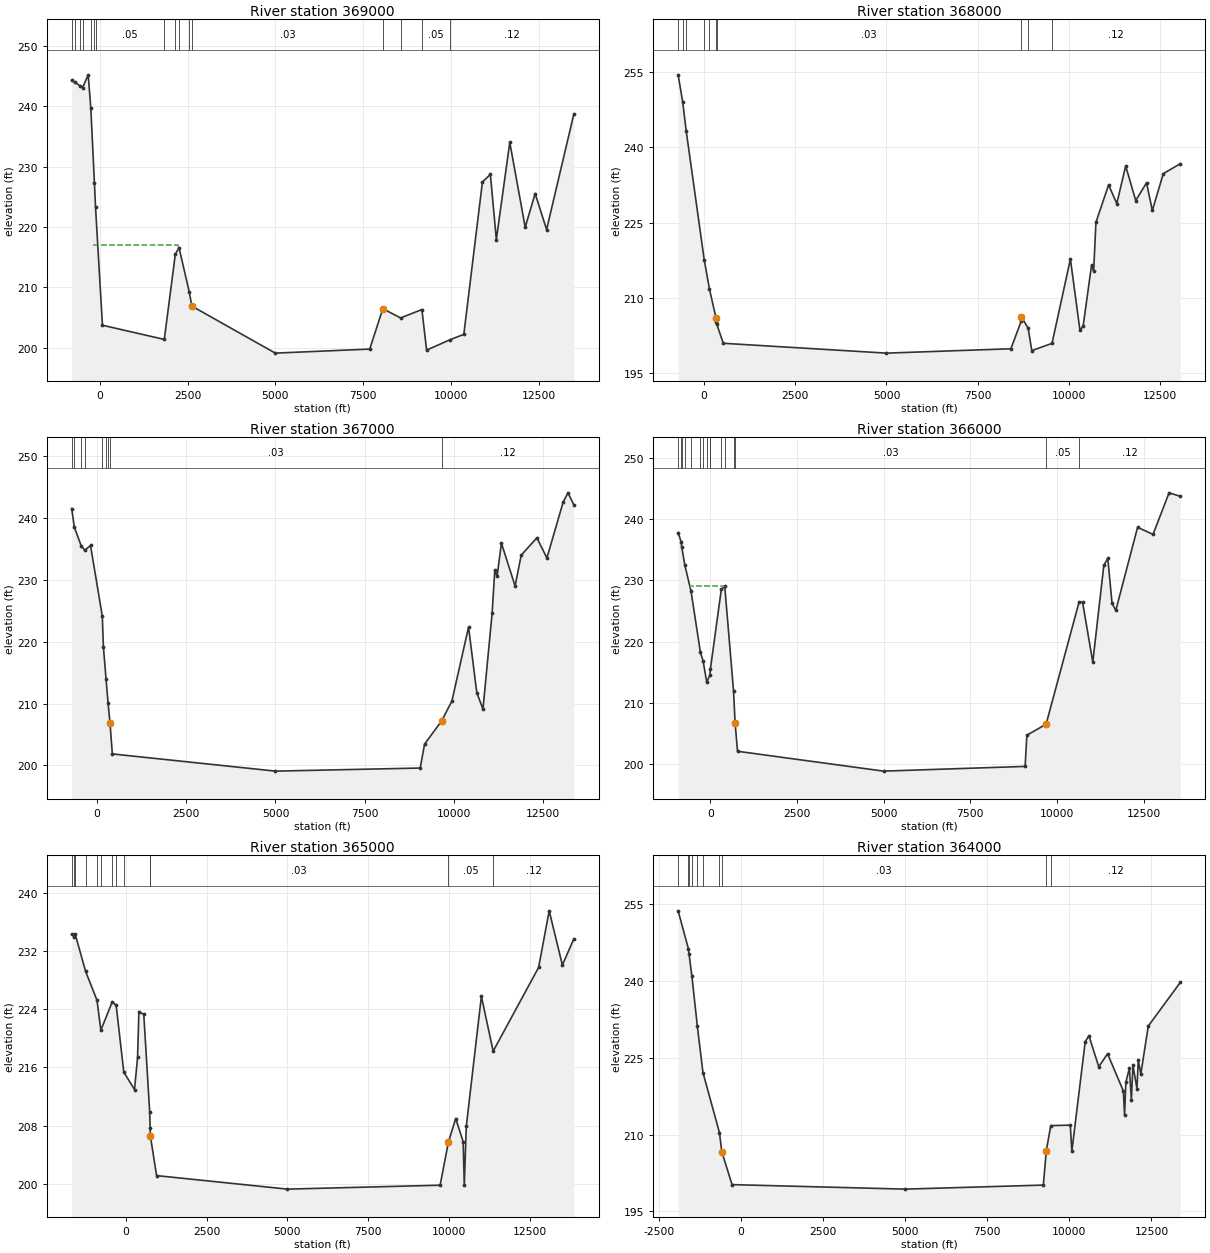
Type RM Length L Ch R = 1 ,369000  ,1000,1000,1000
BEGIN DESCRIPTION:
WFSJ Main 366.0
END DESCRIPTION:
XS GIS Cut Line= 6
      3797644.95     10165926.57       3794606.8     10166874.47
      3791994.16     10166752.01      3789065.13     10166777.25
      3786664.18     10166369.61      3784337.95     10168466.26
#Sta/Elev= 30
  -798.1  244.32  -706.8  243.98  -552.1  243.39  -483.6  243.13  -327.1  245.23
  -253.6  239.79    -149  227.23    -119  223.37    78.8  203.74    1839  201.39
  2152.9   215.5  2257.5  216.61    2549  209.25  2623.7  206.91    4999  199.12
  7686.4  199.79  8059.5  206.49  8563.7  204.95  9171.2  206.34  9305.5  199.62
  9976.6  201.35 10364.4  202.23 10894.1  227.47 11120.5  228.74 11290.2  217.94
 11672.8  234.04 12111.5  219.98 12394.8  225.55 12720.6  219.59 13496.1  238.73
#Mann= 16 ,-1 , 0
  -798.1     .05       0  -706.8     .12       0  -552.1     .05       0
  -483.6     .12       0  -253.6     .05       0    -149     .12       0
    -119     .05       0    1839     .12       0  2152.9     .05       0
  2257.5     .12       0    2549     .05       0  2623.7     .03       0
  8059.5     .12       0  8563.7      .1       0  9171.2     .05       0
  9976.6     .12       0
#XS Ineff= 1 ,-1
    -180  2221.5     217
Permanent Ineff=
       F
Bank Sta=2623.7,8059.5
XS Rating Curve= 0 ,0
Exp/Cntr=0.3,0.1

Type RM Length L Ch R = 1 ,368000  ,1000,1000,1000
BEGIN DESCRIPTION:
WFSJ Main 365.0
END DESCRIPTION:
XS GIS Cut Line= 5
      3797657.14     10165732.11       3791944.3     10165758.39
      3788250.89     10165963.02      3786877.63     10166145.31
       3784398.5     10167785.91
#Sta/Elev= 30
  -712.9  254.44  -589.3  249.13  -490.6  243.24     2.9  217.62   146.7  211.79
   326.4  206.01   339.5  205.22   346.4  204.81   526.4     201    4999  199.04
  8411.7  199.91  8692.1  205.36  8698.1  206.25  8885.2  204.02  8984.6  199.54
  9539.6  200.98 10043.8  217.77 10304.6  203.63 10391.9  204.37 10623.6  216.56
 10680.7  215.36 10743.9  225.07 11091.4  232.54 11315.6   228.8 11559.3   236.3
 11834.9  229.42   12131  232.94 12290.5  227.44 12591.3  234.77 13057.2  236.75
#Mann= 10 ,-1 , 0
  -712.9     .12       0  -589.3     .05       0  -490.6     .12       0
     2.9     .05       0   146.7     .12       0   339.5     .05       0
   346.4     .03       0  8692.1      .1       0  8885.2     .05       0
  9539.6     .12       0
#XS Ineff= 1 ,-1
 10043.8   10830  217.77
Permanent Ineff=
       F
Bank Sta=326.4,8698.1
XS Rating Curve= 0 ,0
Exp/Cntr=0.3,0.1

Type RM Length L Ch R = 1 ,367000  ,1000,1000,1000
BEGIN DESCRIPTION:
WFSJ Main 364.0
END DESCRIPTION:
XS GIS Cut Line= 4
       3797535.6     10165051.56      3791836.71     10164766.93
      3787761.12     10165196.46      3784252.75     10167603.56
#Sta/Elev= 30
    -706  241.52  -631.4  238.54  -434.2  235.41  -335.6   234.8  -177.6  235.55
   152.2  224.11   182.9  219.17   256.2  214.02   312.8  210.13  366.95  206.91
   433.2  201.86    4999  199.08  9051.2  199.58  9174.9  203.45  9649.7  207.18
  9938.9   210.4 10405.6  222.37 10635.8  211.77   10809   209.1 11066.8  224.71
 11139.5  231.53 11203.6  230.55 11326.1  235.92 11708.5  228.99 11879.3  233.98
 12318.2  236.79 12599.1  233.52 13053.2  242.55 13189.1  244.06 13352.9  242.11
#Mann= 9 ,-1 , 0
    -706     .05       0  -631.4     .12       0  -434.2     .05       0
  -335.6     .12       0   152.2    .075       0   256.2     .12       0
   312.8     .05       0  366.95     .03       0  9649.7     .12       0
#XS Ineff= 1 ,-1
 10405.6   11070  222.37
Permanent Ineff=
       F
Bank Sta=366.95,9649.7
XS Rating Curve= 0 ,0
Exp/Cntr=0.3,0.1

Type RM Length L Ch R = 1 ,366000  ,1000,1000,1000
BEGIN DESCRIPTION:
WFSJ Main 363.0
END DESCRIPTION:
XS GIS Cut Line= 5
      3797559.91     10164516.83      3796441.87     10164030.72
      3791739.15     10163790.47      3787779.59     10164937.78
      3784083.37     10167396.46
#Sta/Elev= 30
    -928  237.78  -843.8   236.3  -825.2   235.5    -738  232.56  -554.9  228.18
  -284.5  218.23  -208.7  216.87  -102.9  213.39   -14.2  214.48       3  215.48
   318.5  228.51   417.1  229.02   672.3  211.86  715.88  206.73   785.8   202.1
    4999  198.86  9084.1  199.63    9134  204.72    9689  206.51 10639.9  226.42
 10742.1  226.41 11036.7  216.64 11355.3  232.44 11469.6  233.57 11592.8  226.21
   11701  225.09 12329.2  238.63 12775.7  237.48   13237  244.26 13561.7  243.69
#Mann= 16 ,-1 , 0
    -928     .05       0  -843.8     .12       0  -825.2     .05       0
    -738     .12       0  -554.9     .05       0  -284.5     .12       0
  -208.7     .05       0  -102.9     .12       0   -14.2     .05       0
       3     .12       0   318.5     .05       0   417.1     .12       0
   672.3     .05       0  715.88     .03       0    9689     .05       0
 10639.9     .12       0
#XS Ineff= 1 ,-1
    -575   386.3  229.11
Permanent Ineff=
       F
Bank Sta=715.88,9689
XS Rating Curve= 0 ,0
Exp/Cntr=0.3,0.1

Type RM Length L Ch R = 1 ,365000  ,1000,1000,1000
BEGIN DESCRIPTION:
WFSJ Main 362.0
END DESCRIPTION:
XS GIS Cut Line= 5
      3797644.97      10164443.9      3795797.77     10163107.11
      3791400.61     10162887.71      3786148.46     10163447.39
      3782794.27     10164723.44
#Sta/Elev= 30
 -1682.8  234.34 -1608.3  233.99 -1575.7  234.38 -1252.7  229.24  -897.1  225.23
  -778.5  221.12  -422.9  225.05  -304.4  224.55   -67.3  215.36   264.1  212.96
   358.5  217.38   400.2  223.68     551  223.29   734.7  209.86   747.5  207.71
   757.5  206.51   947.7  201.13    4999  199.27  9729.4  199.81  9986.1  205.74
 10212.1  208.98 10442.3   205.8 10477.8  199.81 10539.3  207.89 11007.1  225.78
 11371.7  218.24   12781  229.77 13107.1  237.54 13515.7  230.08 13870.6  233.69
#Mann= 13 ,-1 , 0
 -1682.8     .05       0 -1608.3     .12       0 -1575.7     .05       0
 -1252.7     .12       0  -897.1     .05       0  -778.5     .12       0
  -422.9     .05       0  -304.4     .12       0   -67.3     .05       0
   734.7    .075       0   747.5     .03       0  9986.1     .05       0
 11371.7     .12       0
#XS Ineff= 1 ,-1
    -315   400.2  223.68
Permanent Ineff=
       F
Bank Sta=757.5,9986.1
XS Rating Curve= 0 ,0
Exp/Cntr=0.3,0.1

Type RM Length L Ch R = 1 ,364000  ,1000,1000,1000
BEGIN DESCRIPTION:
WFSJ Main 361.0
END DESCRIPTION:
XS GIS Cut Line= 4
      3797167.87     10159511.07       3790767.3     10162120.38
      3785905.41     10163350.17      3782782.49     10164601.76
#Sta/Elev= 30
   -1912  253.65 -1600.2  246.28 -1580.2  245.28 -1491.9  240.87 -1325.9  231.11
 -1155.4   222.1  -653.8  210.39 -583.06  206.69  -270.5  200.24  4998.9  199.36
  9207.9  200.15  9300.3  206.89  9434.9  211.75 10029.7  211.84   10077  206.74
 10484.4  228.14 10597.5  229.27 10896.1  223.24 11165.2  225.77 11644.1  218.51
 11682.2  213.89 11722.2  220.22 11829.8  222.97   11889  216.78 11937.4  223.54
 12059.3  218.96 12098.9  224.54 12176.9   221.8   12404  231.17 13379.4  239.69
#Mann= 10 ,-1 , 0
   -1912     .12       0 -1600.2     .05       0 -1580.2     .12       0
 -1491.9     .05       0 -1325.9     .12       0 -1155.4     .05       0
  -653.8     .05       0 -583.06     .03       0  9300.3     .05       0
  9434.9     .12       0
Bank Sta=-583.06,9300.3
XS Rating Curve= 0 ,0
Exp/Cntr=0.3,0.1

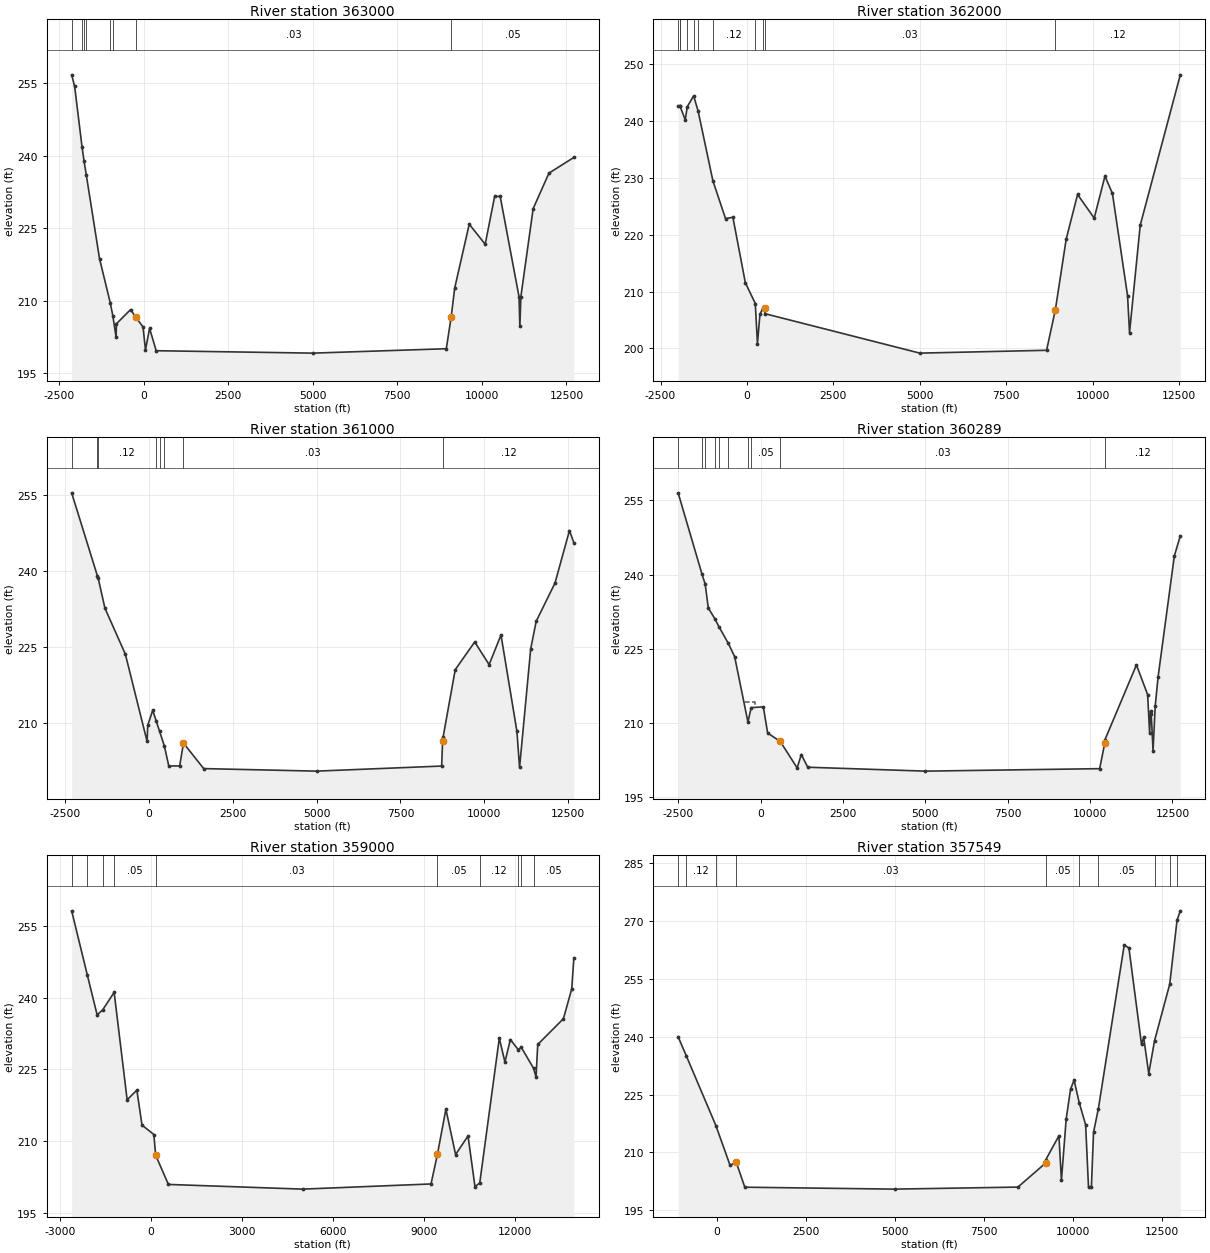
Type RM Length L Ch R = 1 ,363000  ,1000,1000,1000
BEGIN DESCRIPTION:
WFSJ Main 360.0
END DESCRIPTION:
XS GIS Cut Line= 3
      3797158.86     10159291.15      3790316.93     10161300.56
      3783110.24     10164067.19
#Sta/Elev= 30
 -2130.9  256.74 -2041.9  254.33   -1824  241.86 -1763.4  238.83 -1698.4  236.07
 -1306.5  218.72  -990.6  209.64  -913.5  206.94  -816.6  202.49  -806.2  205.27
  -389.3   208.2 -238.76  206.69   -19.5  204.59    52.5  199.85   173.5  204.33
   368.5   199.7  4998.9   199.2  8947.9  200.11  9092.6   206.7  9196.6  212.66
  9626.4  225.86 10098.3  221.71 10377.1  231.59 10541.1  231.61 11098.7  210.85
 11123.3  204.73 11153.3  210.88 11516.8  229.08   11983  236.41 12719.5  239.66
#Mann= 8 ,-1 , 0
 -2130.9     .05       0   -1824     .12       0 -1763.4     .05       0
 -1698.4     .12       0  -990.6     .05       0  -913.5     .05       0
 -238.76     .03       0  9092.6     .05       0
#XS Ineff= 1 ,-1
 10541.1   11825  231.61
Permanent Ineff=
       F
Bank Sta=-238.76,9092.6
XS Rating Curve= 0 ,0
Exp/Cntr=0.3,0.1

Type RM Length L Ch R = 1 ,362000  ,1000,1000,1000
BEGIN DESCRIPTION:
WFSJ Main 359.0
END DESCRIPTION:
XS GIS Cut Line= 4
       3796563.4     10158294.61       3789903.5      10160420.6
       3785419.3     10163107.11      3783183.29     10163666.12
#Sta/Elev= 30
   -1991  242.65 -1936.7  242.59 -1933.1   242.6 -1784.7  240.22 -1726.3  242.54
 -1541.8  244.45 -1412.1  241.76  -986.1  229.51  -620.5  222.85  -406.6  223.06
   -47.3  211.56     241  207.88   303.2  200.84   376.4  206.02   450.8  206.92
   515.7  207.13   523.6  206.09  4998.9  199.15  8664.9  199.65  8919.6  206.81
 8919.86206.8153  9232.7  219.24  9561.3  227.08 10042.5  222.92 10352.6  230.31
   10569  227.27 11006.8  209.26 11063.8  202.75 11372.7  221.66 12532.2  248.15
#Mann= 11 ,-1 , 0
   -1991     .12       0 -1936.7     .05       0 -1933.1     .12       0
 -1726.3     .05       0 -1541.8     .12       0 -1412.1     .05       0
  -986.1     .12       0     241      .1       0   450.8     .05       0
   523.6     .03       0  8919.6     .12       0
#XS Ineff= 1 ,-1
 10352.6   11930  230.31
Permanent Ineff=
       F
Bank Sta=515.7,8919.86
XS Rating Curve= 0 ,0
Exp/Cntr=0.3,0.1

Type RM Length L Ch R = 1 ,361000  ,711,711,711
BEGIN DESCRIPTION:
WFSJ Main 358.0
END DESCRIPTION:
XS GIS Cut Line= 6
       3796617.9     10158061.06      3789476.66     10159587.73
      3786106.54     10161594.89      3785188.39     10162876.21
      3784118.95      10163289.4      3783098.13     10163386.63
#Sta/Elev= 30
 -2302.6  255.42 -1532.7  238.98 -1514.6  238.66 -1310.6  232.66  -701.2  223.58
   -52.8  206.35     -34  209.52   114.5  212.51   215.1  210.47   316.9   208.4
   460.7  205.48   593.9  201.51   918.6  201.53  1031.1  206.03  1634.4     201
  4998.9   200.5  8729.2   201.5  8758.1  206.44    8772  207.17    9134  220.52
    9715  225.99 10144.9  221.52 10498.8  227.37 10973.3  208.36 11052.5  201.24
 11385.1  224.64 11548.8  230.08 12108.5  237.61 12540.5  247.98 12670.8  245.56
#Mann= 8 ,-1 , 0
 -2302.6     .12       0 -1532.7     .05       0 -1514.6     .12       0
   215.1     .05       0   316.9     .12       0   460.7     .05       0
  1031.1     .03       0    8772     .12       0
#XS Ineff= 1 ,-1
 10498.8   11630  227.37
Permanent Ineff=
       F
Bank Sta=1031.1,8758.1
XS Rating Curve= 0 ,0
Exp/Cntr=0.3,0.1

Type RM Length L Ch R = 1 ,360289  ,1289,1289,1289
BEGIN DESCRIPTION:
WFSJ Main 357.0
END DESCRIPTION:
XS GIS Cut Line= 3
      3796567.81     10158061.08      3789320.34      10158890.1
      3782308.15     10162633.17
#Sta/Elev= 30
 -2503.9  256.54 -1781.9  240.14 -1682.1  238.05   -1588  233.23 -1382.8  230.97
 -1265.7  229.45  -983.8  226.11    -788  223.38  -385.2  210.15  -285.4  213.06
    82.8  213.21   213.7  207.91   596.1  206.21  1109.5  200.85  1235.5  203.55
  1431.6  200.99  4998.9   200.2 10291.4   200.7 10448.3  205.93   10454  206.58
 11407.9   221.7 11747.8  215.69   11808  207.93 11835.6   212.4 11857.5  211.72
 11912.1  204.34 11977.9  213.39 12065.7  219.32 12559.3  243.78 12739.5  247.84
#Mann= 10 ,-1 , 0
 -2503.9     .12       0 -1781.9     .05       0 -1682.1     .12       0
 -1382.8     .05       0 -1265.7     .12       0  -983.8     .05       0
  -385.2     .12       0  -285.4     .05       0   596.1     .03       0
   10454     .12       0
#XS Ineff= 2 ,-1
 11407.9   12155   221.7    -515    -173  214.15
Permanent Ineff=
       F       F
Bank Sta=596.1,10448.3
XS Rating Curve= 0 ,0
Exp/Cntr=0.3,0.1

Type RM Length L Ch R = 1 ,359000  ,1451,1451,1451
BEGIN DESCRIPTION:
WFSJ Main 356.0
END DESCRIPTION:
XS GIS Cut Line= 5
      3796567.88     10158011.07      3788951.12     10157756.88
      3782466.17     10157553.29      3781190.13     10157200.86
       3780096.4     10157504.68
#Sta/Elev= 30
   -2621  258.12 -2106.4  244.78 -1780.5   236.4   -1595  237.46 -1218.9   241.1
    -790  218.67  -469.8  220.68  -299.7  213.39    90.5  211.42   150.6  207.11
   570.8     201  4998.8  200.02  9235.4   201.1  9445.5  207.25  9725.6  216.71
 10045.8  207.24   10456  211.12 10686.1  200.52 10843.1  201.33 11488.1  231.52
 11673.1  226.56   11854  231.23 12110.7  229.16   12212  229.63 12617.2  225.25
 12700.2  223.42   12756  230.22 13603.1   235.6 13877.9  241.84 13947.1  248.26
#Mann= 10 ,-1 , 0
   -2621     .12       0 -2106.4     .05       0   -1595     .12       0
 -1218.9     .05       0   150.6     .03       0  9445.5     .05       0
 10843.1     .12       0 12110.7     .05       0   12212     .12       0
 12617.2     .05       0
#XS Ineff= 1 ,-1
  9725.6   11300  216.71
Permanent Ineff=
       F
Bank Sta=150.6,9445.5
XS Rating Curve= 0 ,0
Exp/Cntr=0.3,0.1

Type RM Length L Ch R = 1 ,357549  ,1161,1161,1161
BEGIN DESCRIPTION:
WFSJ Main 355.0
END DESCRIPTION:
XS GIS Cut Line= 4
      3794497.82     10155731.25      3788118.95     10156499.91
      3785087.27     10155772.61      3780582.47     10155042.51
#Sta/Elev= 30
 -1082.2  239.97  -855.8  235.11   -20.9  216.94   376.2  206.66   550.4  207.43
   791.2  200.97  4998.8  200.47  8462.8     201 9240.45  207.23  9248.3  208.15
  9614.8   214.3  9684.8  202.71  9818.2  218.65  9941.5  226.41 10040.3  228.71
 10187.3  222.78 10364.5  217.18 10445.5     201 10526.5     201 10587.3  215.22
 10723.3  221.37 11448.4  263.72 11580.1  263.04 11934.4  237.99 11995.5   239.8
 12137.3  230.42 12300.5  238.95 12726.4  253.58 12932.8  270.21 13024.1  272.62
#Mann= 10 ,-1 , 0
 -1082.2     .05       0  -855.8     .12       0   -20.9     .05       0
   550.4     .03       0  9248.3     .05       0 10187.3    .075       0
 10723.3     .05       0 12300.5     .12       0 12726.4     .05       0
 12932.8     .12       0
#XS Ineff= 2 ,-1
  9614.8    9840   214.3 10040.3   10950  228.71
Permanent Ineff=
       F       F
Bank Sta=550.4,9240.45
XS Rating Curve= 0 ,0
Exp/Cntr=0.3,0.1

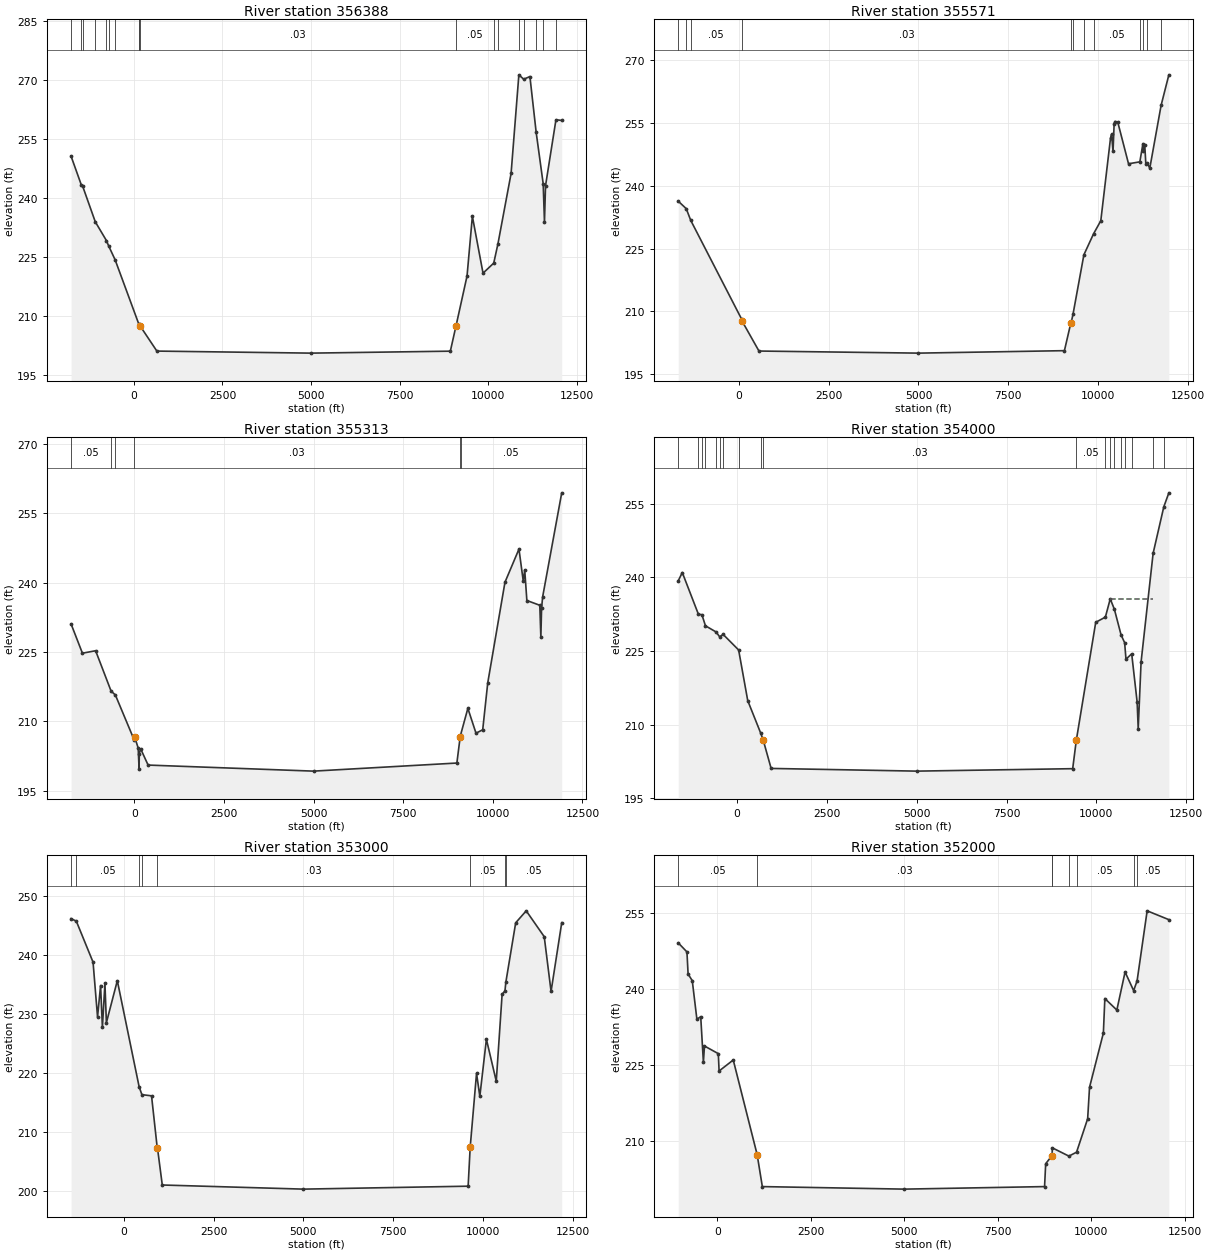
Type RM Length L Ch R = 1 ,356388  ,817,817,817
BEGIN DESCRIPTION:
WFSJ Main 354.0
END DESCRIPTION:
XS GIS Cut Line= 3
      3794867.88     10155211.07       3788378.5     10155431.77
      3781042.07     10154922.71
#Sta/Elev= 30
 -1772.8  250.66 -1485.6  243.39 -1443.2  242.95 -1090.1  233.96  -774.5  229.16
  -715.3  227.87  -529.7  224.27   142.4  207.81     149  207.61   168.4  207.52
   648.6  201.02  4998.8   200.5  8931.1     201  9081.4  207.06 9089.37  207.36
  9402.2  220.14  9552.6  235.35  9853.3  220.87 10155.6  223.43 10273.9  228.32
 10645.2  246.26 10864.8  271.39 11001.6  270.27 11176.5  270.95 11353.4  256.71
 11550.7  243.68 11587.4   233.9 11617.5  243.15 11911.6  259.95 12074.4  259.77
#Mann= 18 ,-1 , 0
 -1772.8     .05       0 -1485.6     .12       0 -1443.2     .05       0
 -1090.1     .12       0  -774.5     .05       0  -715.3     .12       0
  -529.7     .05       0   142.4     .12       0     149     .05       0
   168.4     .03       0  9081.4     .05       0 10155.6    .075       0
 10273.9     .05       0 10864.8    .075       0 11001.6     .05       0
 11353.4    .075       0 11550.7     .05       0 11911.6     .12       0
Bank Sta=168.4,9089.37
XS Rating Curve= 0 ,0
Exp/Cntr=0.3,0.1

Type RM Length L Ch R = 1 ,355571  ,258,258,258
BEGIN DESCRIPTION:
WFSJ Main 353.0
END DESCRIPTION:
XS GIS Cut Line= 3
      3794740.02     10154147.05       3791858.1     10154763.36
      3781177.93     10154284.19
#Sta/Elev= 30
 -1677.9  236.35 -1454.4  234.55 -1328.3  231.73    87.5   208.1   103.7  207.58
   566.9  200.52  4998.8  200.02  9057.3  200.61  9236.6  207.27  9241.6   207.2
    9295  209.26  9598.2  223.52  9867.8  228.55 10068.3  231.66 10338.6  251.41
 10368.6  252.31 10408.6  248.23 10438.7  254.78 10458.7  255.38 10538.8  255.27
 10839.1  245.28 11153.4  245.74 11239.5  250.09 11252.1  248.24 11289.5  249.83
 11319.5  245.33 11364.8  245.44 11429.6  244.19 11745.1  259.26 11960.1  266.54
#Mann= 12 ,-1 , 0
 -1677.9     .05       0 -1454.4     .12       0 -1328.3     .05       0
    87.5     .03       0  9241.6    .075       0    9295     .05       0
  9598.2    .075       0  9867.8     .05       0 11153.4     .12       0
 11252.1     .05       0 11364.8     .12       0 11745.1     .05       0
Bank Sta=103.7,9236.6
XS Rating Curve= 0 ,0
Exp/Cntr=0.3,0.1

Type RM Length L Ch R = 1 ,355313  ,1313,1313,1313
BEGIN DESCRIPTION:
WFSJ Main 352.0
END DESCRIPTION:
XS GIS Cut Line= 4
      3794826.82     10153843.23      3791753.93     10154511.63
      3788125.46     10154338.02      3781226.54     10154028.99
#Sta/Elev= 30
 -1761.9   231.1 -1445.7  224.77 -1077.3   225.3    -646  216.57  -526.6  215.73
    -2.7  206.01     7.5  206.74   109.8  204.24   134.4  199.75   140.5  203.04
   178.4  204.08   386.1  200.56  4998.8  199.25  8997.1     201  9087.1  206.53
  9102.2  207.12  9303.6  212.84  9530.4  207.46  9717.8   208.2  9857.9  218.34
 10338.4  240.12 10728.8   247.3 10848.9  240.34   10889  242.82   10949  236.17
 11309.4  235.14 11339.4  228.22 11359.4  234.48 11389.5  236.98 11921.3  259.47
#Mann= 6 ,-1 , 0
 -1761.9     .05       0    -646     .12       0  -526.6     .05       0
    -2.7     .03       0  9087.1    .075       0  9102.2     .05       0
Bank Sta=7.5,9087.1
XS Rating Curve= 0 ,0
Exp/Cntr=0.3,0.1

Type RM Length L Ch R = 1 ,354000  ,1000,1000,1000
BEGIN DESCRIPTION:
WFSJ Main 351.0
END DESCRIPTION:
XS GIS Cut Line= 3
      3794821.32      10153298.9      3788191.22     10153026.34
      3781186.72     10153446.65
#Sta/Elev= 30
 -1635.7  239.27 -1522.1  240.98 -1074.5  232.49  -975.9  232.37  -877.3  230.12
  -581.5  228.86  -482.9  227.88  -384.3  228.36    45.9  225.19   299.4  214.86
   658.1  208.28   729.8  206.83   949.9  201.05  4998.8   200.5  9341.2     201
  9441.3  206.76  9982.3  230.83 10250.6  231.89 10386.5  235.61 10502.2  233.46
 10687.6  228.26 10786.7  226.68 10823.8  223.31 10983.1  224.41 11134.4  214.58
 11164.4  209.16 11244.6  222.77 11579.4   244.9 11876.7  254.37 12017.1  257.22
#Mann= 19 ,-1 , 0
 -1635.7     .05       0 -1074.5     .12       0  -975.9     .05       0
  -877.3     .12       0  -581.5     .05       0  -482.9     .12       0
  -384.3     .05       0    45.9      .1       0   658.1    .075       0
   729.8     .03       0  9441.3     .05       0 10250.6    .075       0
 10386.5     .05       0 10502.2    .075       0 10687.6     .05       0
 10786.7    .075       0 10983.1     .05       0 11579.4    .075       0
 11876.7     .05       0
#XS Ineff= 1 ,-1
   10383   11575  235.66
Permanent Ineff=
       F
Bank Sta=729.8,9441.3
XS Rating Curve= 0 ,0
Exp/Cntr=0.3,0.1

Type RM Length L Ch R = 1 ,353000  ,1000,1000,1000
BEGIN DESCRIPTION:
WFSJ Main 350.0
END DESCRIPTION:
XS GIS Cut Line= 3
      3794817.83     10153111.07      3788435.78     10152104.73
      3781366.11     10150840.03
#Sta/Elev= 30
 -1460.9  246.22 -1315.3   245.8  -849.7  238.84  -724.8  229.53  -640.9  234.88
  -589.7   227.8  -519.4  235.23  -478.9  228.57  -175.2   235.7   430.9  217.71
   508.2  216.36   776.4  216.16   938.4  207.13  941.01207.3317    1075  201.03
  4998.8  200.33  9579.5  200.83 9636.36  207.42  9813.1  219.98  9904.6  216.07
 10087.4  225.76 10361.7  218.64 10524.3  233.39 10603.2  233.95 10627.4  235.41
 10901.8  245.52 11194.7  247.55 11695.5  243.16 11885.5  233.87 12181.9  245.54
#Mann= 8 ,-1 , 0
 -1460.9    .075       0 -1315.3     .05       0   430.9      .1       0
   508.2     .05       0   938.4     .03       0 9636.36     .05       0
 10603.2    .075       0 10627.4     .05       0
Bank Sta=941.01,9636.36
XS Rating Curve= 0 ,0
Exp/Cntr=0.3,0.1

Type RM Length L Ch R = 1 ,352000  ,1000,1000,1000
BEGIN DESCRIPTION:
WFSJ Main 349.0
END DESCRIPTION:
XS GIS Cut Line= 4
      3794726.28     10152517.97      3788817.29     10151215.67
      3784869.74     10150692.29      3781777.66     10150544.55
#Sta/Elev= 30
 -1050.8  249.06  -816.9  247.27  -786.2  242.91  -674.5   241.6  -550.7  233.99
  -448.3   234.5  -376.6  225.52    -348  228.72    22.2  227.21    43.3  223.79
   422.1  225.96 1061.36  207.31  1200.4     201  4998.8   200.5    8752     201
  8782.2  205.51 8952.84  207.12  8959.9  208.64  9402.9  207.01  9607.8  207.78
    9905  214.38  9955.3  220.58 10325.5  231.27 10365.1  238.08 10685.9  235.81
 10906.2  243.31 11135.2  239.64 11227.9  241.56 11496.8  255.37 12077.7  253.63
#Mann= 8 ,-1 , 0
 -1050.8     .05       0 1061.36     .03       0 8952.84    .075       0
  8959.9     .05       0  9402.9    .075       0  9607.8     .05       0
 11135.2    .075       0 11227.9     .05       0
Bank Sta=1061.36,8952.84
XS Rating Curve= 0 ,0
Exp/Cntr=0.3,0.1

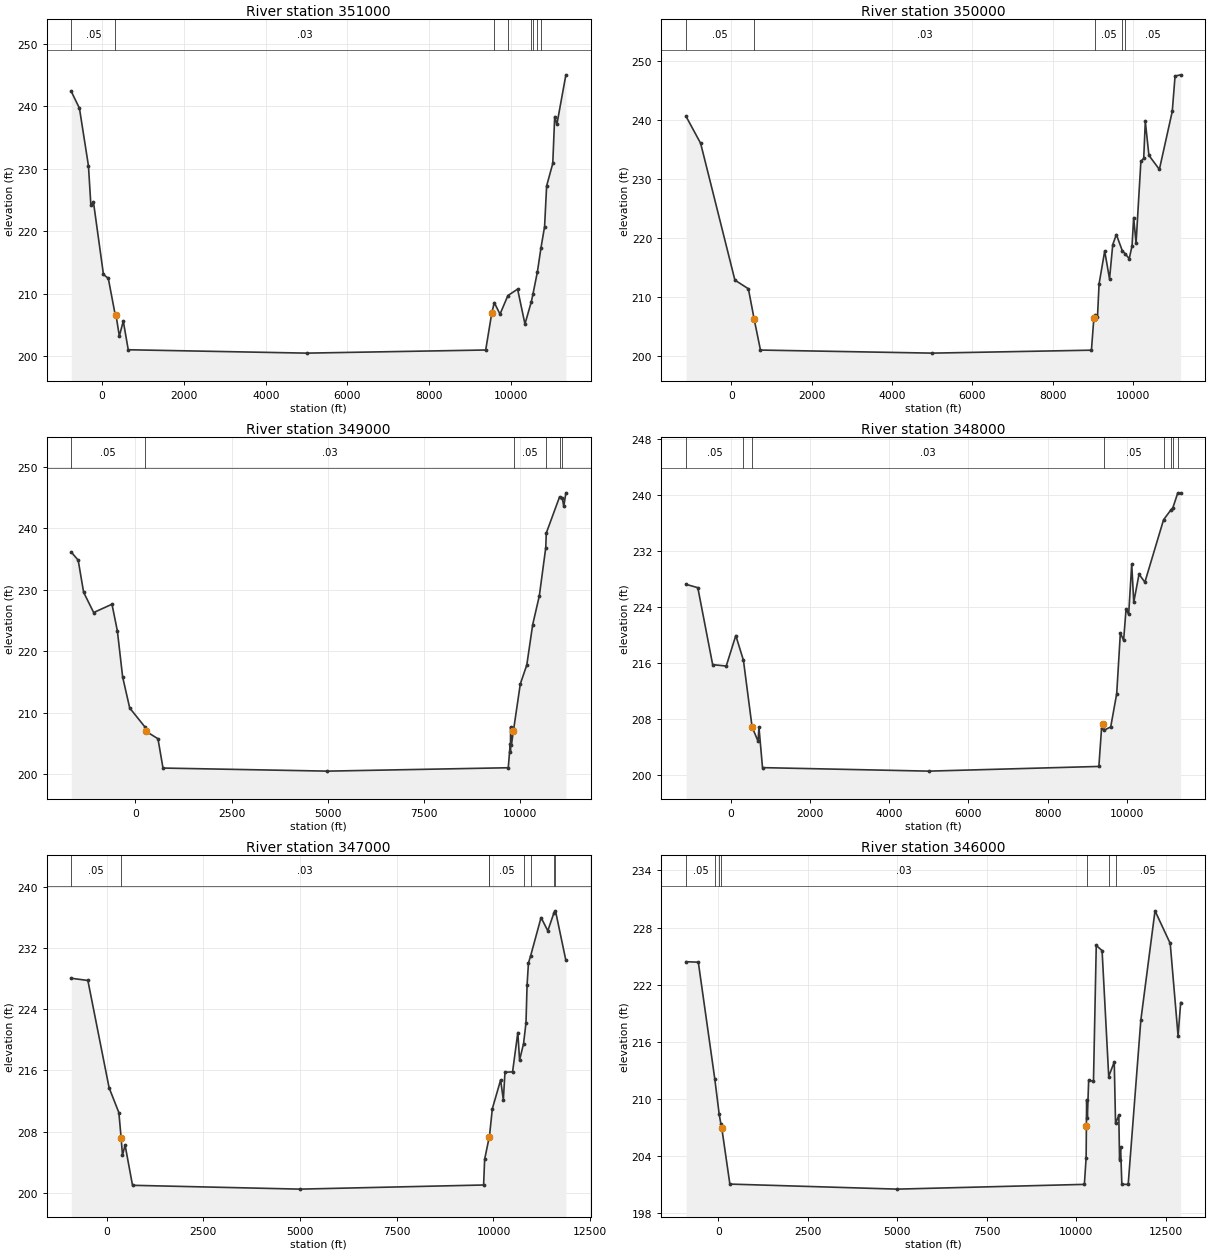
Type RM Length L Ch R = 1 ,351000  ,1000,1000,1000
BEGIN DESCRIPTION:
WFSJ Main 348.0
END DESCRIPTION:
XS GIS Cut Line= 3
      3794409.69      10151768.7      3788867.13     10150216.91
        3782527.     10150080.22
#Sta/Elev= 30
  -755.7   242.4  -555.9  239.71  -335.6   230.5  -276.1  224.18  -213.8  224.72
    31.6  213.09   149.7  212.48   325.3  206.42   336.6  206.67   419.7  203.23
   516.7  205.62   637.7  201.04  4998.8   200.5  9380.3     201  9530.3  206.97
  9590.3  208.59  9730.4  206.74  9922.5  209.71 10160.5  210.75 10340.5  205.16
 10494.7  208.69 10535.3  209.92 10644.2   213.5 10733.3   217.4 10820.6  220.76
 10870.6  227.28 11020.7  230.87 11067.8  238.38 11120.7  237.11 11341.6  245.06
#Mann= 8 ,-1 , 0
  -755.7     .05       0   325.3     .03       0  9590.3     .05       0
  9922.5     .05       0 10494.7    .075       0 10535.3     .05       0
 10644.2    .075       0 10733.3     .05       0
Bank Sta=336.6,9530.3
XS Rating Curve= 0 ,0
Exp/Cntr=0.3,0.1

Type RM Length L Ch R = 1 ,350000  ,1000,1000,1000
BEGIN DESCRIPTION:
WFSJ Main 347.0
END DESCRIPTION:
XS GIS Cut Line= 4
      3794430.81     10151504.86      3793850.41     10150723.95
      3788916.97     10149218.15      3782737.97     10149510.35
#Sta/Elev= 30
 -1131.1  240.64  -768.5  236.08      85  212.88   420.9  211.41     566  206.22
   721.4  201.02  4998.8   200.5  8963.5     201  9023.6  206.43  9043.6  206.93
  9113.7   206.6  9153.8  212.24  9293.9  217.81    9414  213.08  9494.1   218.9
  9584.2  220.61  9731.3  217.87  9798.6  217.38  9904.6  216.51  9974.7  218.68
 10014.7  223.48 10074.8  219.15 10194.9  233.02   10265  233.51   10305  239.78
 10395.1  234.03 10655.4  231.65 10975.8  241.48 11045.9  247.48 11185.9  247.69
#Mann= 5 ,-1 , 0
 -1131.1     .05       0     566     .03       0  9043.6     .05       0
  9731.3    .075       0  9798.6     .05       0
Bank Sta=566,9023.6
XS Rating Curve= 0 ,0
Exp/Cntr=0.3,0.1

Type RM Length L Ch R = 1 ,349000  ,1000,1000,1000
BEGIN DESCRIPTION:
WFSJ Main 346.0
END DESCRIPTION:
XS GIS Cut Line= 4
      3794483.59     10151325.46      3794240.87     10150386.25
      3788966.81      10148219.4      3782822.63      10149088.2
#Sta/Elev= 30
 -1671.9  236.14 -1491.8  234.83 -1350.8  229.61   -1089  226.31  -612.1  227.66
  -471.5  223.31  -334.7  215.83  -150.7  210.78   252.8  207.63   270.6  206.99
   585.3  205.77   715.9     201  4998.8   200.5  9705.3  201.05  9755.8  204.95
  9761.2  203.64  9766.3  207.63  9786.1  204.68  9837.4  206.99  9846.7  207.36
 10018.4  214.68 10187.6  217.78 10341.6  224.36 10513.3  229.01 10680.6  236.84
 10695.1  239.25 11042.3  245.16 11110.9  244.93 11149.5  243.61 11205.3  245.79
#Mann= 6 ,-1 , 0
 -1671.9     .05       0   252.8     .03       0  9846.7     .05       0
 10680.6    .075       0 11042.3     .05       0 11110.9    .075       0
Bank Sta=270.6,9837.4
XS Rating Curve= 0 ,0
Exp/Cntr=0.3,0.1

Type RM Length L Ch R = 1 ,348000  ,1000,1000,1000
BEGIN DESCRIPTION:
WFSJ Main 345.0
END DESCRIPTION:
XS GIS Cut Line= 3
      3794473.02     10150322.92      3789157.79     10147256.97
      3782951.01     10148655.12
#Sta/Elev= 30
 -1136.1  227.18    -839   226.7  -464.1  215.71  -120.9  215.51   120.4  219.87
   313.5  216.33   532.3  206.81   683.5  204.76   705.4  206.79   795.5     201
  4998.8   200.5  9294.9  201.17    9363  206.63  9411.4  207.21  9417.9  206.32
  9594.6  206.82  9745.9  211.58  9838.2  220.24  9920.2  219.18  9981.7  223.63
 10047.7  222.88 10125.2  230.06 10176.5  224.62 10309.7  228.63 10457.5  227.49
 10929.5   236.4 11117.5  237.83 11162.6  238.08 11289.9  240.25 11362.3  240.17
#Mann= 8 ,-1 , 0
 -1136.1     .05       0   313.5    .075       0   532.3     .03       0
  9417.9     .05       0 10929.5    .075       0 11117.5     .05       0
 11162.6    .075       0 11289.9     .05       0
Bank Sta=532.3,9411.4
XS Rating Curve= 0 ,0
Exp/Cntr=0.3,0.1

Type RM Length L Ch R = 1 ,347000  ,1000,1000,1000
BEGIN DESCRIPTION:
WFSJ Main 344.0
END DESCRIPTION:
XS GIS Cut Line= 5
        3794262.     10149531.47      3793955.94     10149330.95
      3789315.35     10146285.43      3784289.32     10147568.58
      3782875.68      10148486.4
#Sta/Elev= 30
  -916.6  228.05  -487.2  227.76    61.3  213.75   314.5  210.49   371.7  207.23
   407.9  204.92   474.3  206.27   667.1     201  4998.8   200.5    9745  201.04
  9771.8  204.39  9889.2  207.27  9896.5  207.41  9970.9  211.01 10185.4  214.76
 10255.3  212.16 10297.5  215.77 10493.9  215.82 10630.1  220.96 10675.2  217.35
 10778.1  219.51 10841.3  222.25 10868.6  227.12 10904.6  230.04 10958.7  230.94
 11230.8  235.98 11405.1  234.25 11565.5  236.62 11603.6  236.86 11872.7  230.38
#Mann= 8 ,-1 , 0
  -916.6     .05       0   371.7     .03       0  9889.2    .075       0
  9896.5     .05       0 10778.1    .075       0 10958.7     .05       0
 11565.5    .075       0 11603.6     .05       0
Bank Sta=371.7,9889.2
XS Rating Curve= 0 ,0
Exp/Cntr=0.3,0.1

Type RM Length L Ch R = 1 ,346000  ,1385,1385,1385
BEGIN DESCRIPTION:
WFSJ Main 343.0
END DESCRIPTION:
XS GIS Cut Line= 4
       3794360.6     10149251.13      3789813.75     10145486.77
        3785220.     10146048.04      3782798.16     10148274.57
#Sta/Elev= 30
  -902.9  224.41  -560.5  224.36  -101.9  212.13    22.3  208.38    72.6   207.3
    93.4  206.97     321  201.03  4998.8   200.5 10226.3     201 10275.6  203.79
   10283 207.128 10289.8  209.91 10310.7     208 10346.5  211.95 10480.9  211.83
 10558.6  226.12 10721.4  225.58 10906.9  212.34 11061.1  213.87 11097.7   207.4
 11188.7  208.27 11209.7   203.6   11238  204.91 11273.8     201 11450.7     201
 11804.2  218.26 12200.4  229.76 12625.2  226.33 12844.7  216.61 12917.7  220.12
#Mann= 7 ,-1 , 0
  -902.9     .05       0  -101.9    .075       0    22.3     .05       0
    72.6     .03       0 10310.7     .05       0 10906.9    .075       0
 11097.7     .05       0
#XS Ineff= 1 ,-1
 10721.4   12160  225.58
Permanent Ineff=
       F
Bank Sta=93.4,10283
XS Rating Curve= 0 ,0
Exp/Cntr=0.3,0.1

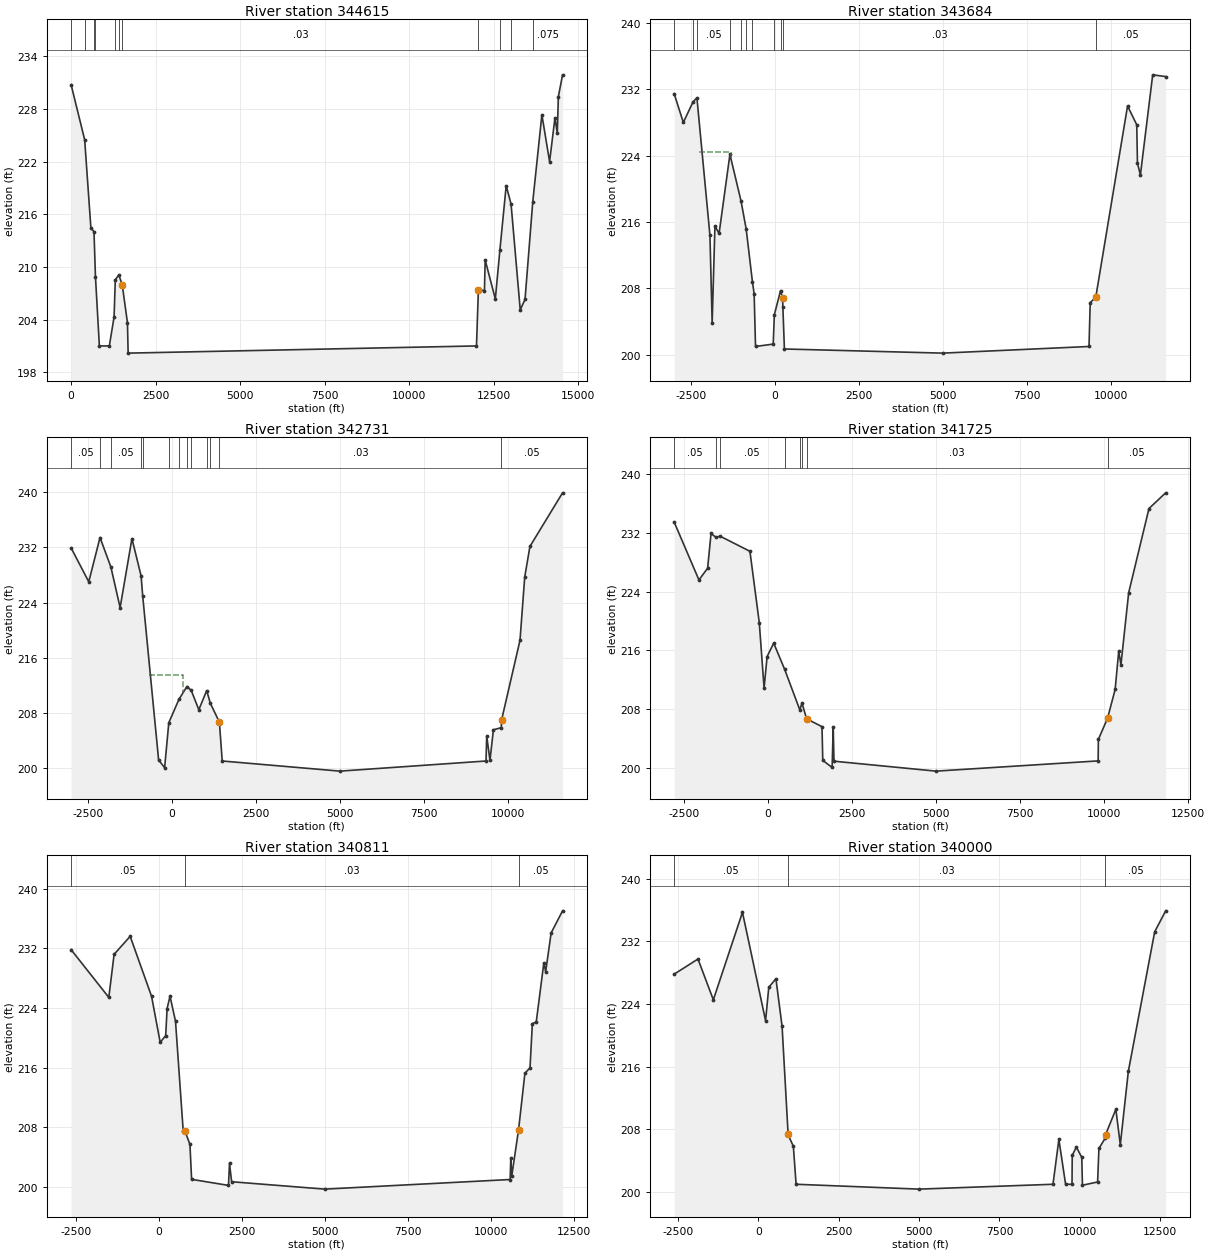
Type RM Length L Ch R = 1 ,344615  ,931,931,931
BEGIN DESCRIPTION:
WFSJ Main 341.0
END DESCRIPTION:
XS GIS Cut Line= 4
      3797943.17     10146144.12      3790727.81      10144524.6
      3785629.03     10140741.25      3785382.48     10139991.81
#Sta/Elev= 30
       0  230.75     401  224.48   584.6  214.45   676.4  214.01   719.7   208.9
   835.6     201  1130.2     201  1270.4   204.3    1307  208.53  1410.6  209.09
    1512  207.95  1665.8  203.65  1686.3  200.18   11987     201 12043.3  207.38
 12222.8  207.31 12243.7  210.79 12544.1  206.35 12679.7  211.94 12865.4  219.25
 13009.4  217.16 13280.7  205.11 13422.5   206.3   13652  217.45 13920.8  227.33
 14148.6  221.99 14307.6  226.99 14376.4  225.23 14408.2  229.39 14532.4  231.88
#Mann= 11 ,-1 , 0
       0     .05       0     401     .07       0   676.4    .075       0
   719.7     .05       0    1307    .075       0  1410.6     .05       0
    1512     .03       0 12043.3     .05       0 12679.7    .075       0
 13009.4     .05       0   13652    .075       0
#XS Ineff= 2 ,-1
 12865.4   13750  219.25 12243.7   12710  210.79
Permanent Ineff=
       F       F
Bank Sta=1512,12043.3
XS Rating Curve= 0 ,0
Exp/Cntr=0.3,0.1

Type RM Length L Ch R = 1 ,343684  ,953,953,953
BEGIN DESCRIPTION:
WFSJ Main 341.0
END DESCRIPTION:
XS GIS Cut Line= 3
      3798631.51     10145735.55      3791209.59     10143795.43
      3785401.78     10139942.02
#Sta/Elev= 30
 -2999.6  231.45 -2728.6     228 -2437.1  230.49 -2323.3  230.97 -1935.2  214.39
 -1869.2  203.82 -1786.5   215.5 -1662.5  214.63 -1339.8  224.15 -1006.9  218.49
  -855.1  215.14  -668.3  208.76  -618.5  207.34  -577.2     201   -50.1  201.29
   -16.4  204.83   167.9  207.73     229  206.85   237.4  205.76     283   200.7
  4998.7   200.2  9357.7     201  9393.8  206.29  9559.2  206.93 10506.2  229.99
 10780.2  227.72 10801.2  223.11 10888.5  221.67 11255.4  233.74 11641.6  233.53
#Mann= 11 ,-1 , 0
 -2999.6     .05       0 -2437.1    .075       0 -2323.3     .05       0
 -1339.8    .075       0 -1006.9     .05       0  -855.1    .075       0
  -668.3     .05       0   -16.4    .075       0   167.9     .05       0
   237.4     .03       0  9559.2     .05       0
#XS Ineff= 1 ,-1
   -2250   -1311  224.38
Permanent Ineff=
       F
Bank Sta=229,9559.2
XS Rating Curve= 0 ,0
Exp/Cntr=0.3,0.1

Type RM Length L Ch R = 1 ,342731  ,1006,1006,1006
BEGIN DESCRIPTION:
WFSJ Main 340.0
END DESCRIPTION:
XS GIS Cut Line= 4
      3798904.89     10145735.53      3798189.34     10145304.01
       3792407.5     10143443.87       3785714.8     10139628.77
#Sta/Elev= 30
   -2993  231.92 -2468.2  227.01 -2133.6  233.43 -1809.6  229.14 -1536.1  223.26
 -1184.4  233.28  -912.2  227.86  -864.4  224.95    -391  201.15  -212.5  200.03
   -88.4  206.55   212.9  209.94   450.9  211.81   578.5  211.25   804.2  208.44
  1038.2  211.22  1149.1  209.35  1415.8  206.64  1499.8     201  4998.7  199.53
  9343.4     201    9365  204.62  9461.5   201.1  9563.8  205.53  9797.8  205.84
  9805.8  206.93 10354.7  218.53 10494.4  227.69 10649.6  232.14   11620  239.92
#Mann= 13 ,-1 , 0
   -2993     .05       0 -2133.6    .075       0 -1809.6     .05       0
  -912.2    .075       0  -864.4     .05       0   -88.4    .075       0
   212.9     .05       0   450.9    .075       0   578.5     .05       0
  1038.2    .075       0  1149.1     .05       0  1415.8     .03       0
  9797.8     .05       0
#XS Ineff= 1 ,-1
    -665   333.8  213.44
Permanent Ineff=
       F
Bank Sta=1415.8,9805.8
XS Rating Curve= 0 ,0
Exp/Cntr=0.3,0.1

Type RM Length L Ch R = 1 ,341725  ,914,914,914
BEGIN DESCRIPTION:
WFSJ Main 339.0
END DESCRIPTION:
XS GIS Cut Line= 4
      3799126.24     10145722.51      3797589.73     10144680.98
      3792772.09     10142480.33      3785988.21     10139381.36
#Sta/Elev= 30
 -2783.4  233.42 -2048.4  225.57 -1790.2  227.16 -1688.4  231.88 -1538.1  231.34
 -1421.8  231.52  -532.5  229.46  -254.5  219.77  -111.5  210.87   -21.5  215.17
   174.3  216.99     498  213.45   949.6  207.94  1015.1  208.85 1153.24  206.71
  1610.4  205.65  1633.4  201.07  1911.3  200.11  1943.8  205.59  1966.3  200.96
  4998.7  199.61  9820.1     201    9827  203.9210099.77  206.79 10325.6   210.7
 10431.7   215.9 10497.8  214.06 10728.1  223.84 11331.2  235.27 11827.5   237.4
#Mann= 8 ,-1 , 0
 -2783.4     .05       0 -1538.1    .075       0 -1421.8     .05       0
     498    .075       0   949.6     .05       0  1015.1     .05       0
 1153.24     .03       010099.77     .05       0
#XS Ineff= 1 ,-1
    -350   174.3  216.99
Permanent Ineff=
       F
Bank Sta=1153.24,10099.77
XS Rating Curve= 0 ,0
Exp/Cntr=0.3,0.1

Type RM Length L Ch R = 1 ,340811  ,811,811,811
BEGIN DESCRIPTION:
WFSJ Main 338.0
END DESCRIPTION:
XS GIS Cut Line= 4
      3799308.55     10145683.46      3793312.71     10141773.37
      3788331.98     10139758.97      3786092.65     10139355.37
#Sta/Elev= 30
 -2641.9  231.82 -1506.3  225.42 -1346.3   231.2  -862.2  233.61  -217.7  225.56
    41.8  219.39   207.7   220.3   249.9  223.93   337.5  225.58   503.4  222.22
   735.8  207.46   785.3  207.52     938  205.71   988.2  201.02  2099.6  200.21
  2129.9  203.17    2194   200.7  4998.7  199.71 10585.5     201 10604.4  203.86
   10634   201.510838.82  207.67 11029.4  215.24 11183.5  215.98   11254   221.9
 11371.3  222.12 11600.9  230.07 11654.5  228.85 11820.4  234.07 12164.3  237.03
#Mann= 3 , 0 , 0
 -2641.9     .05       0   785.3     .03       010838.82     .05       0
Bank Sta=785.3,10838.82
XS Rating Curve= 0 ,0
Exp/Cntr=0.3,0.1

Type RM Length L Ch R = 1 ,340000  ,1000,1000,1000
BEGIN DESCRIPTION:
WFSJ Main 337.0
END DESCRIPTION:
XS GIS Cut Line= 4
      3799516.91     10145657.43      3793455.17     10141036.14
      3787615.84     10139199.08      3786066.35     10139225.12
#Sta/Elev= 30
 -2622.4  227.82 -1882.9  229.75 -1404.9  224.54  -498.6  235.71   220.7  221.88
   320.5  226.14   542.8  227.23   734.1  221.17   921.1  207.47   927.4  207.26
  1085.3  205.85  1170.6     201  4998.7  200.38  9164.9     201  9347.7  206.72
  9557.4     201  9756.6     201  9763.6  204.68  9892.8  205.75 10060.3  204.43
 10081.5  200.88 10553.3  201.29 10594.2  205.57 10793.7  206.91   10799  207.31
 11121.5  210.57 11259.5  206.05 11509.5  215.41 12329.6  233.22 12671.2   235.9
#Mann= 3 ,-1 , 0
 -2622.4     .05       0   927.4     .03       0 10793.7     .05       0
Bank Sta=921.1,10799
XS Rating Curve= 0 ,0
Exp/Cntr=0.3,0.1