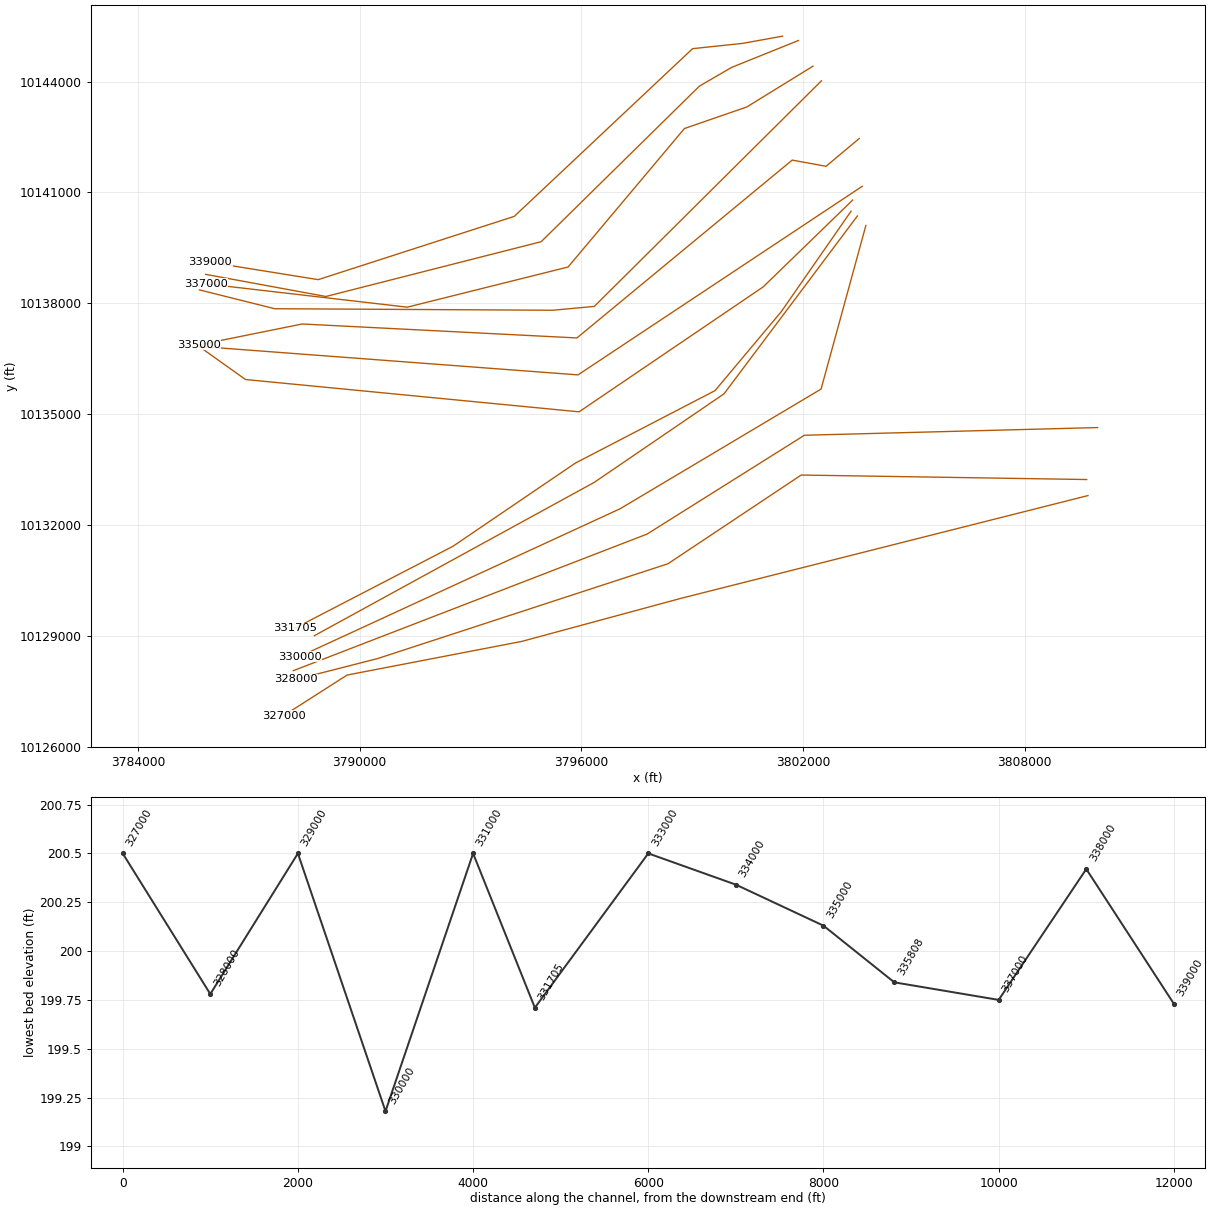
HEC-RAS study WFSJ Main.prj: WFSJ Main Base Level Engineering

--- WFSJ Main.g02 (geometry) --- (continued)

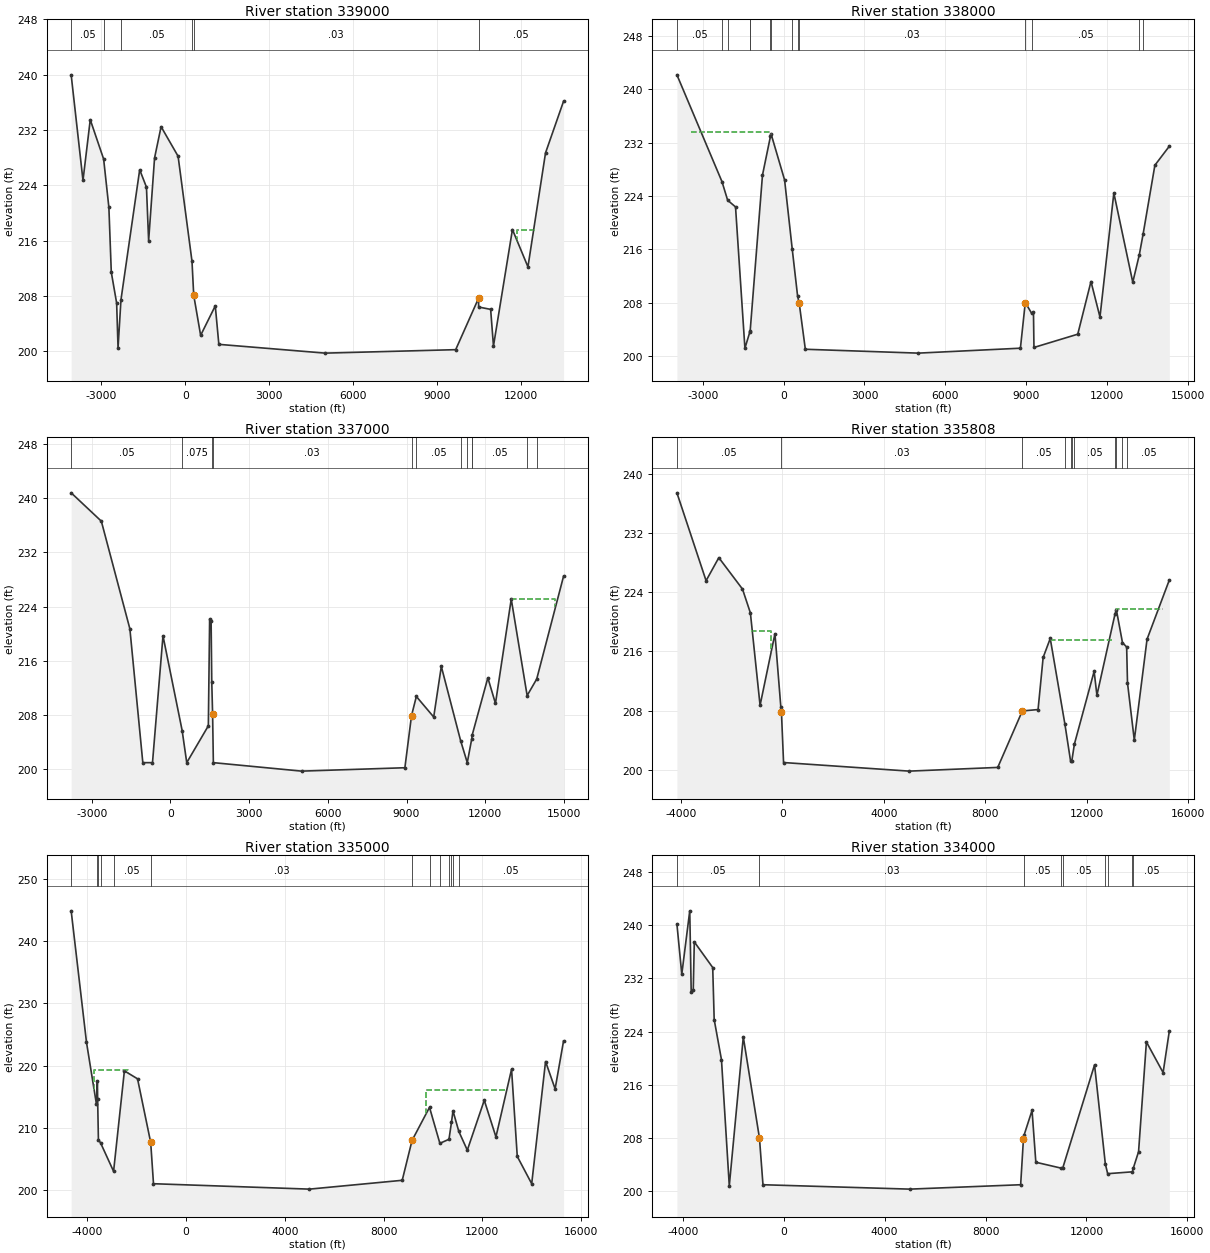
Type RM Length L Ch R = 1 ,339000  ,1000,1000,1000
BEGIN DESCRIPTION:
WFSJ Main 336.0
END DESCRIPTION:
XS GIS Cut Line= 6
      3801443.97     10145227.72      3800363.23     10145032.41
      3799009.06     10144889.18      3794183.58     10140350.99
      3788878.86     10138639.18      3785962.56     10139107.87
#Sta/Elev= 30
 -4084.2  239.99 -3661.3  224.71 -3401.2   233.5 -2922.5   227.8 -2734.9   220.8
 -2648.7  211.43 -2457.6  206.98 -2407.4  200.48 -2302.3  207.46 -1633.1  226.26
 -1391.1  223.74 -1313.4  215.99   -1101  227.97  -867.6  232.49  -259.4  228.21
   237.8  213.01   299.3  208.11   546.9   202.3  1070.5  206.57    1198     201
  4998.7  199.73  9669.3  200.23 10486.2  207.66 10491.4   206.4 10919.5  206.06
 11020.7  200.76 11699.3  217.61 12253.7  212.21 12882.8   228.7 13527.8  236.17
#Mann= 6 ,-1 , 0
 -4084.2     .05       0 -2922.5     .12       0 -2302.3     .05       0
   237.8    .075       0   299.3     .03       0 10491.4     .05       0
#XS Ineff= 2 ,-1
   -3900  -867.6  232.49 11877.3   12570  217.57
Permanent Ineff=
       F       F
Bank Sta=299.3,10486.2
XS Rating Curve= 0 ,0
Exp/Cntr=0.3,0.1

Type RM Length L Ch R = 1 ,338000  ,1000,1000,1000
BEGIN DESCRIPTION:
WFSJ Main 335.0
END DESCRIPTION:
XS GIS Cut Line= 6
      3801873.67     10145110.54      3800063.75     10144381.37
      3799191.36     10143873.56      3794911.98     10139665.84
      3789087.19     10138183.45      3785832.39     10138782.34
#Sta/Elev= 30
 -3962.2  242.16   -2288  226.13 -2078.5  223.35 -1785.9  222.35 -1437.1  201.15
 -1249.7  203.66 -1241.5  203.77  -785.2  227.12  -488.3  232.95    -468  233.32
    35.2   226.4   317.6  216.09   518.3  208.99  579.98  207.87   805.9     201
  4998.7  200.42  8791.2  201.16  8972.2  208.01  9208.5  206.39  9276.2  206.58
  9294.3  201.27 10920.4  203.26 11411.6  211.16 11745.1  205.83 12260.4  224.43
 12963.1  211.05 13204.3  215.14 13349.9  218.34 13784.2   228.6 14319.9  231.45
#Mann= 14 ,-1 , 0
 -3962.2     .05       0   -2288    .075       0 -2078.5     .05       0
 -1249.7    .075       0 -1241.5     .05       0  -488.3    .075       0
    -468     .05       0   317.6    .075       0   518.3     .05       0
  579.98     .03       0  8972.2     .12       0  9208.5     .05       0
 13204.3    .075       0 13349.9     .05       0
#XS Ineff= 2 ,-1
   -3433  -452.7   233.6 12260.4   13850  224.43
Permanent Ineff=
       F       F
Bank Sta=579.98,8972.2
XS Rating Curve= 0 ,0
Exp/Cntr=0.3,0.1

Type RM Length L Ch R = 1 ,337000  ,1192,1192,1192
BEGIN DESCRIPTION:
WFSJ Main 334.0
END DESCRIPTION:
XS GIS Cut Line= 6
      3802266.87     10144415.22      3800475.21     10143311.06
      3798787.71     10142727.72      3795640.38     10138980.69
      3791287.71     10137894.39      3785832.03     10138526.69
#Sta/Elev= 30
 -3783.5  240.79 -2633.5  236.61 -1545.4  220.74 -1051.8     201    -683     201
  -283.1   219.7   447.3  205.74   622.6     201    1446  206.43  1495.4  222.18
  1551.8  221.84  1576.2  212.93  1608.6  208.15  1637.2     201  4998.7  199.75
  8938.5  200.25 9191.18  207.93  9375.4  210.76 10037.1  207.73 10327.2  215.19
 11061.8  204.26   11317     201 11486.5   204.5 11509.6  205.15 12100.9  213.51
 12391.5  209.73 12993.3  225.12   13599  210.89 13963.8  213.33 14987.5  228.49
#Mann= 12 ,-1 , 0
 -3783.5     .05       0   447.3    .075       0  1576.2      .1       0
  1608.6     .03       0 9191.18     .12       0  9375.4     .05       0
 11061.8    .075       0   11317     .05       0 11486.5    .075       0
 11509.6     .05       0   13599    .075       0 13963.8     .05       0
#XS Ineff= 3 ,-1
   -2000  1495.4  222.18 10327.2   12890  215.19 12993.3   14680  225.12
Permanent Ineff=
       F       F       F
Bank Sta=1608.6,9191.18
XS Rating Curve= 0 ,0
Exp/Cntr=0.3,0.1

Type RM Length L Ch R = 1 ,335808  ,808,808,808
BEGIN DESCRIPTION:
WFSJ Main 333.0
END DESCRIPTION:
XS GIS Cut Line= 5
      3802496.03     10144019.37      3796350.21     10137915.22
      3795225.21     10137811.06      3787703.26     10137852.35
      3785666.02     10138361.66
#Sta/Elev= 30
   -4159   237.4 -3008.9  225.54 -2506.9  228.65 -1573.5  224.41 -1262.3   221.2
  -880.5  208.72  -293.6  218.38   -60.2  208.43  -37.94  207.81    45.8     201
  4998.7  199.84  8490.3  200.34  9459.5  207.96 10080.3  208.15 10280.3  215.18
 10560.3  217.74 11137.4   206.2 11361.5  201.21   11411  201.23 11512.8  203.49
 12290.4   213.3 12400.4  210.09 13113.9  221.04 13166.3  221.64 13407.6  217.19
 13572.8  216.59 13605.9  211.76 13874.1  204.02 14376.9  217.64 15254.9  225.63
#Mann= 11 ,-1 , 0
   -4159     .05       0   -60.2     .03       0  9459.5     .05       0
 11137.4    .075       0 11361.5     .05       0   11411    .075       0
 11512.8     .05       0 13113.9    .075       0 13166.3      .1       0
 13407.6    .075       0 13605.9     .05       0
#XS Ineff= 3 ,-1
   -1250  -449.2  218.75 10540.3   12990  217.57   13155   15020  221.67
Permanent Ineff=
       F       F       F
Bank Sta=-37.94,9459.5
XS Rating Curve= 0 ,0
Exp/Cntr=0.3,0.1

Type RM Length L Ch R = 1 ,335000  ,1000,1000,1000
BEGIN DESCRIPTION:
WFSJ Main 332.0
END DESCRIPTION:
XS GIS Cut Line= 6
       3803516.9     10142456.91      3802621.04     10141706.89
      3801704.38     10141873.56      3795879.05     10137061.46
      3788446.56      10137439.4      3785652.57      10136875.1
#Sta/Elev= 30
 -4655.9  244.91 -4034.6  223.75 -3629.9  213.76   -3593  217.56 -3583.2  214.58
 -3551.8  208.07   -3464  207.57 -2937.3  202.99 -2499.5  219.16 -1966.7  217.88
 -1433.8  207.64 -1320.5     201  4998.7  200.13    8756  201.55 9153.91  207.96
  9861.3  213.29 10281.5   207.5 10650.6  208.15 10752.3   210.9 10812.7  212.72
 11049.3  209.41 11393.2   206.4 12080.3  214.43   12553  208.53 13185.5  219.42
 13416.9  205.39 14001.7     201 14562.8  220.66 14950.4  216.26 15292.5  223.98
#Mann= 13 ,-1 , 0
 -4655.9     .05       0   -3593      .1       0 -3583.2     .05       0
   -3464      .1       0 -2937.3     .05       0 -1433.8     .03       0
 9153.91     .05       0  9861.3    .075       0 10281.5     .05       0
 10650.6    .075       0 10752.3     .05       0 10812.7    .075       0
 11049.3     .05       0
#XS Ineff= 3 ,-1
   -3725 -2371.8  219.26  9727.3   13000  216.02 13185.5   14565  219.42
Permanent Ineff=
       F       F       F
Bank Sta=-1433.8,9153.91
XS Rating Curve= 0 ,0
Exp/Cntr=0.3,0.1

Type RM Length L Ch R = 1 ,334000  ,1000,1000,1000
BEGIN DESCRIPTION:
WFSJ Main 331.0
END DESCRIPTION:
XS GIS Cut Line= 3
       3803600.2     10141165.22      3795908.29     10136061.89
      3785652.59     10136833.73
#Sta/Elev= 30
 -4230.9  240.18 -4037.8  232.63   -3722  242.16   -3664  229.94 -3583.7  230.19
 -3541.6  237.49   -2812  233.64 -2753.6  225.82 -2464.9  219.79 -2155.1  200.84
 -1599.9   223.2 -959.61  208.02  -819.9     201  4998.7  200.34  9392.8     201
  9503.1  207.88  9533.2  208.51  9844.1  212.17  9994.5  204.38 10991.6   203.5
 11055.1  203.44 12321.1  219.01 12749.2  204.13 12841.4  202.66 13819.7  202.94
   13860  203.52   14066  205.96 14376.9  222.46 15038.7  217.85 15284.7  224.09
#Mann= 9 ,-1 , 0
 -4230.9     .05       0 -959.61     .03       0  9533.2     .05       0
 10991.6     .12       0 11055.1     .05       0 12749.2    .075       0
 12841.4     .05       0 13819.7    .075       0   13860     .05       0
#XS Ineff= 3 ,-1
   -2800 -1599.9   223.2 12321.1   14418  219.01  9844.1   12040  212.17
Permanent Ineff=
       F       F       F
Bank Sta=-959.61,9503.1
XS Rating Curve= 0 ,0
Exp/Cntr=0.3,0.1

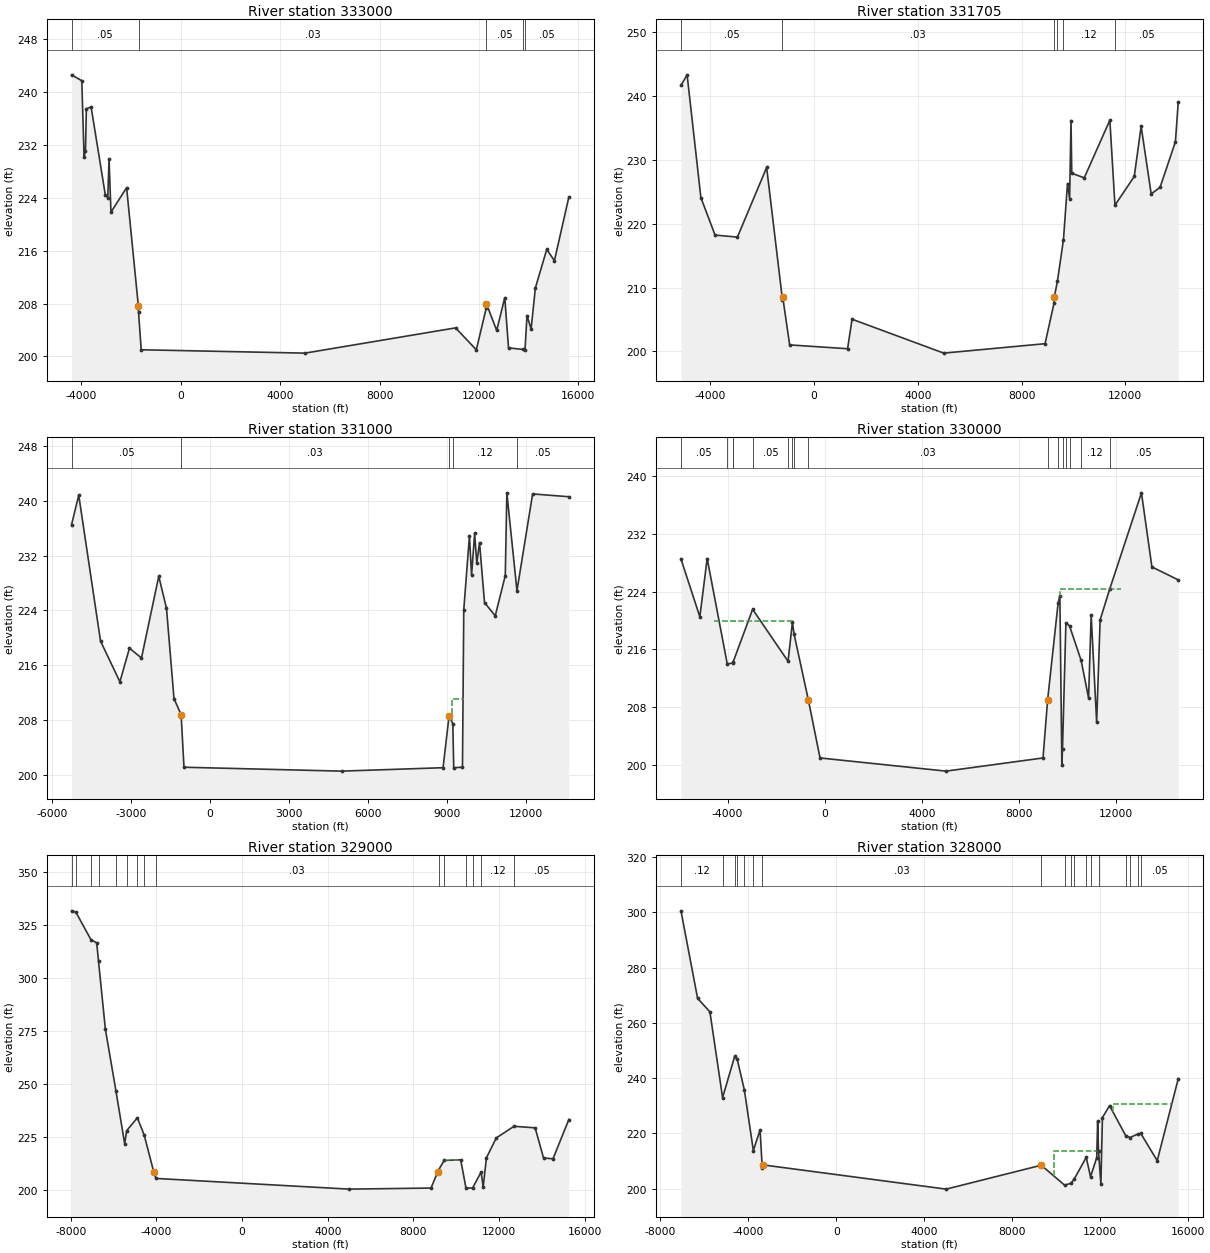
Type RM Length L Ch R = 1 ,333000  ,1295,1295,1295
BEGIN DESCRIPTION:
WFSJ Main 330.0
END DESCRIPTION:
XS GIS Cut Line= 5
      3803340.31      10140792.2      3800919.74     10138443.25
      3795937.53     10135062.32      3786911.93     10135936.74
      3785652.57     10136833.55
#Sta/Elev= 30
   -4394   242.6 -3981.3  241.71 -3889.3  230.16 -3832.9   231.1 -3797.4  237.46
 -3606.5  237.75 -3033.7  224.41 -2934.7  224.03 -2885.3  229.85 -2807.3  221.82
 -2177.9  225.53 -1704.1  207.58 -1697.1  206.67 -1590.9  201.01  4998.7   200.5
 11058.3  204.32 11891.8     201 12293.3  207.34 12298.4  207.98 12711.7  203.93
 13037.1  208.89 13187.8   201.3 13772.4  201.05 13851.8  201.02 13931.3  206.18
 14096.2  204.14 14268.4  210.36 14725.7  216.19 15034.3  214.48 15613.9  224.09
#Mann= 5 ,-1 , 0
   -4394     .05       0 -1697.1     .03       0 12293.3     .05       0
 13772.4    .075       0 13851.8     .05       0
Bank Sta=-1704.1,12298.4
XS Rating Curve= 0 ,0
Exp/Cntr=0.3,0.1

Type RM Length L Ch R = 1 ,331705  ,705,705,705
BEGIN DESCRIPTION:
WFSJ Main 329.0
END DESCRIPTION:
XS GIS Cut Line= 6
      3803297.34     10140491.42      3801406.72     10137770.07
      3799616.36     10135635.96      3795835.11     10133673.72
      3792526.51     10131425.02        3788245.     10129205.51
#Sta/Elev= 30
 -5137.8   241.7   -4901  243.36 -4370.2  224.11 -3822.3  218.22 -2960.2  217.91
 -1833.2  228.83 -1222.7  208.09 -1214.9  208.57  -945.6     201  1289.5   200.4
  1460.9  205.03  4998.7  199.71    8906  201.19  9254.3  207.58  9261.5  208.48
  9384.9  211.03  9615.6  217.48  9772.4  226.31  9853.4  223.96  9907.6  236.19
  9936.2  227.93 10417.4   227.2 11405.7  236.24 11602.6  222.91 12347.4  227.42
 12612.9  235.28   13000  224.68 13342.7  225.71 13934.6  232.86 14044.6  239.13
#Mann= 6 ,-1 , 0
 -5137.8     .05       0 -1222.7     .03       0  9254.3    .075       0
  9384.9     .05       0  9615.6     .12       0 11602.6     .05       0
Bank Sta=-1214.9,9261.5
XS Rating Curve= 0 ,0
Exp/Cntr=0.3,0.1

Type RM Length L Ch R = 1 ,331000  ,1000,1000,1000
BEGIN DESCRIPTION:
WFSJ Main 328.0
END DESCRIPTION:
XS GIS Cut Line= 4
       3803469.2      10140362.5      3799859.85     10135550.02
      3796351.86     10133155.52      3788775.41     10129005.27
#Sta/Elev= 30
 -5262.9  236.52   -4989  240.85 -4161.1  219.52 -3424.4  213.56 -3061.1  218.48
 -2603.6  217.04 -1947.3  228.99 -1653.6   224.3 -1368.2   211.1 -1097.3  208.76
    -989  201.07  4998.7   200.5  8858.5     201  9086.5  208.57  9229.4  207.43
  9264.6     201  9596.4  201.07  9645.7  224.09  9861.8  234.92  9941.7  229.12
 10059.1  235.25 10140.7  230.87   10244  233.91 10434.6  225.14 10842.3  223.21
 11223.4   229.1 11283.2  241.19 11667.6  226.87 12262.6  241.03 13638.7  240.62
#Mann= 5 ,-1 , 0
 -5262.9     .05       0 -1097.3     .03       0  9086.5     .05       0
  9229.4     .12       0 11667.6     .05       0
#XS Ineff= 2 ,-1
  9189.1    9670  211.09   -4620 -1947.3  228.99
Permanent Ineff=
       F       F
Bank Sta=-1097.3,9086.5
XS Rating Curve= 0 ,0
Exp/Cntr=0.3,0.1

Type RM Length L Ch R = 1 ,330000  ,1000,1000,1000
BEGIN DESCRIPTION:
WFSJ Main 327.0
END DESCRIPTION:
XS GIS Cut Line= 4
      3803698.38     10140104.66      3802486.15     10135678.49
      3797050.42     10132440.96      3788371.13     10128439.71
#Sta/Elev= 30
   -5916   228.5 -5138.9  220.51 -4837.1  228.56 -4010.5     214 -3789.9  214.11
 -3775.9   214.2 -2965.8  221.54 -1507.6  214.36 -1326.2  219.77 -1262.4  218.16
  -672.5  209.03  -191.3     201  4998.7  199.18    8989     201  9179.8  209.06
  9610.6  222.41  9682.7  223.43  9765.1  200.09  9791.3  202.25  9931.5  219.67
 10082.9  219.23 10557.4  214.49   10865  209.28 10971.1  220.75 11197.4  205.92
 11340.6  220.08 11729.9  224.29   13042  237.64 13471.7   227.4 14557.2  225.61
#Mann= 16 ,-1 , 0
   -5916     .05       0 -4010.5     .12       0 -3789.9     .05       0
 -3775.9     .12       0 -2965.8     .05       0 -1507.6    .075       0
 -1326.2    .075       0 -1262.4     .05       0  -672.5     .03       0
  9179.8     .05       0  9610.6     .12       0  9791.3     .05       0
  9931.5    .075       0 10082.9     .05       0 10557.4     .12       0
 11729.9     .05       0
#XS Ineff= 2 ,-1
   -4540 -1326.8  219.92  9667.8   12218   224.3
Permanent Ineff=
       F       F
Bank Sta=-672.5,9179.8
XS Rating Curve= 0 ,0
Exp/Cntr=0.3,0.1

Type RM Length L Ch R = 1 ,329000  ,1000,1000,1000
BEGIN DESCRIPTION:
WFSJ Main 326.0
END DESCRIPTION:
XS GIS Cut Line= 4
      3809968.75     10134636.82      3802034.76     10134428.49
      3797777.11     10131753.99      3788206.68     10128059.15
#Sta/Elev= 30
 -7964.7  331.84 -7761.8   331.2 -7055.5  318.19 -6790.8  316.75 -6705.2  308.14
 -6383.3  275.89 -5888.9  246.77 -5482.9  221.89 -5390.3  228.08 -4890.3  234.17
 -4569.6  225.96 -4126.9  208.68 -4024.7  205.55  4998.7   200.5  8823.3  201.01
 9131.88   208.5  9179.3  209.62  9440.5  214.07 10208.8  214.32 10456.6     201
 10761.9     201 11164.9  208.57 11259.3  201.51 11411.4  215.28 11870.3  224.66
 12700.5  230.15   13686  229.43 14078.7  215.19 14520.6  214.82 15258.9  233.34
#Mann= 15 ,-1 , 0
 -7964.7     .12       0 -7761.8     .05       0 -7055.5      .1       0
 -6705.2     .12       0 -5888.9     .05       0 -5390.3    .075       0
 -4890.3     .05       0 -4569.6     .05       0 -4024.7     .03       0
  9179.3    .075       0  9440.5     .05       0 10456.6     .12       0
 10761.9     .05       0 11164.9     .12       0 12700.5     .05       0
#XS Ineff= 2 ,-1
  9479.9 10208.7  214.16 10208.8   11450  214.32
Permanent Ineff=
       F       F
Bank Sta=-4126.9,9131.88
XS Rating Curve= 0 ,0
Exp/Cntr=0.3,0.1

Type RM Length L Ch R = 1 ,328000  ,1000,1000,1000
BEGIN DESCRIPTION:
WFSJ Main 325.0
END DESCRIPTION:
XS GIS Cut Line= 5
      3809673.61     10133230.58      3801947.95      10133352.1
      3798343.15      10130951.7      3790489.62     10128386.83
      3788272.33     10127820.57
#Sta/Elev= 30
 -7057.5  300.57 -6301.6  268.88 -5741.6  263.98 -5165.2  232.92 -4615.3  247.89
 -4497.4  246.73 -4175.1  235.67 -3767.3  213.76 -3461.3  221.23 -3361.3  207.33
 -3341.3  208.57  4998.7  199.78 9321.72  208.44 10383.8  201.21 10675.6  201.92
 10813.5  203.33 11366.5  211.29 11561.5  204.28 11842.5  211.16 11885.5  224.38
 11924.1  213.72 12032.8  201.59 12102.9  225.71   12427  230.01 13157.6   219.2
 13357.6  218.47 13724.7  219.78 13845.2  219.95 14594.1  210.09 15550.2  239.79
#Mann= 18 ,-1 , 0
 -7057.5     .12       0 -5165.2     .05       0 -4615.3     .12       0
 -4497.4     .05       0 -4175.1     .12       0 -3767.3     .05       0
 -3361.3     .03       0 9321.72     .05       0 10383.8     .12       0
 10675.6     .12       0 10813.5     .05       0 11366.5     .12       0
 11561.5     .05       0 11924.1     .12       0 13157.6     .05       0
 13357.6     .05       0 13724.7    .075       0 13845.2     .05       0
#XS Ineff= 3 ,-1
  9913.6   11881  213.57 11885.5   12372  224.38 12586.4   15300  230.51
Permanent Ineff=
       F       F       F
Bank Sta=-3341.3,9321.72
XS Rating Curve= 0 ,0
Exp/Cntr=0.3,0.1

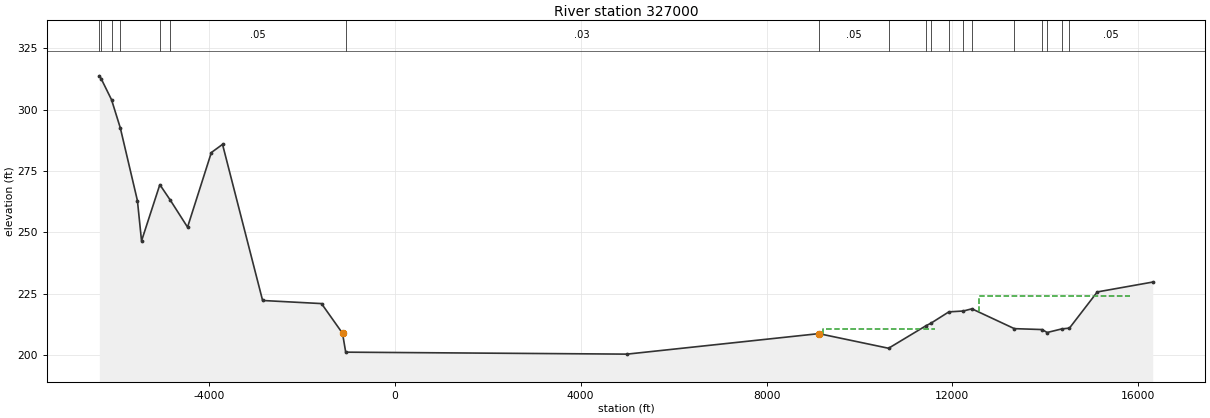
Type RM Length L Ch R = 1 ,327000  ,1000,1000,1000
BEGIN DESCRIPTION:
WFSJ Main 324.0
END DESCRIPTION:
XS GIS Cut Line= 5
       3809708.4     10132796.55        3798696.     10130016.04
      3794391.53     10128851.23      3789660.63     10127939.78
      3787946.26     10126843.88
#Sta/Elev= 30
   -6358  313.76 -6320.7  312.67 -6095.5  304.03 -5906.7  292.56 -5538.3  262.96
 -5449.8  246.58 -5056.1  269.47   -4830  263.14 -4459.7  252.17 -3947.6  282.54
 -3706.8  285.86 -2844.3  222.33 -1576.9  221.07-1124.79  208.99 -1056.1   201.3
  4998.7   200.5 9126.55  208.84 10626.4  202.89 11438.6  212.13 11538.4  213.08
 11924.1   217.7 12236.6  218.05   12420  218.94 13333.9  210.87 13932.3   210.5
 14039.3   209.3 14349.8  210.74 14519.6   211.1 15118.4  225.81 16311.9  229.83
#Mann= 19 ,-1 , 0
   -6358     .05       0 -6320.7     .12       0 -6095.5     .05       0
 -5906.7     .12       0 -5056.1     .05       0   -4830     .05       0
 -1056.1     .03       0 9126.55     .05       0 10626.4    .075       0
 11438.6    .075       0 11538.4     .05       0 11924.1     .12       0
 12236.6     .05       0   12420     .12       0 13333.9      .1       0
 13932.3    .075       0 14039.3     .05       0 14349.8    .075       0
 14519.6     .05       0
#XS Ineff= 2 ,-1
  9210.2   11625  210.85 12569.1   15820  224.04
Permanent Ineff=
       F       F
Bank Sta=-1124.79,9126.55
XS Rating Curve= 0 ,0
Exp/Cntr=0.3,0.1