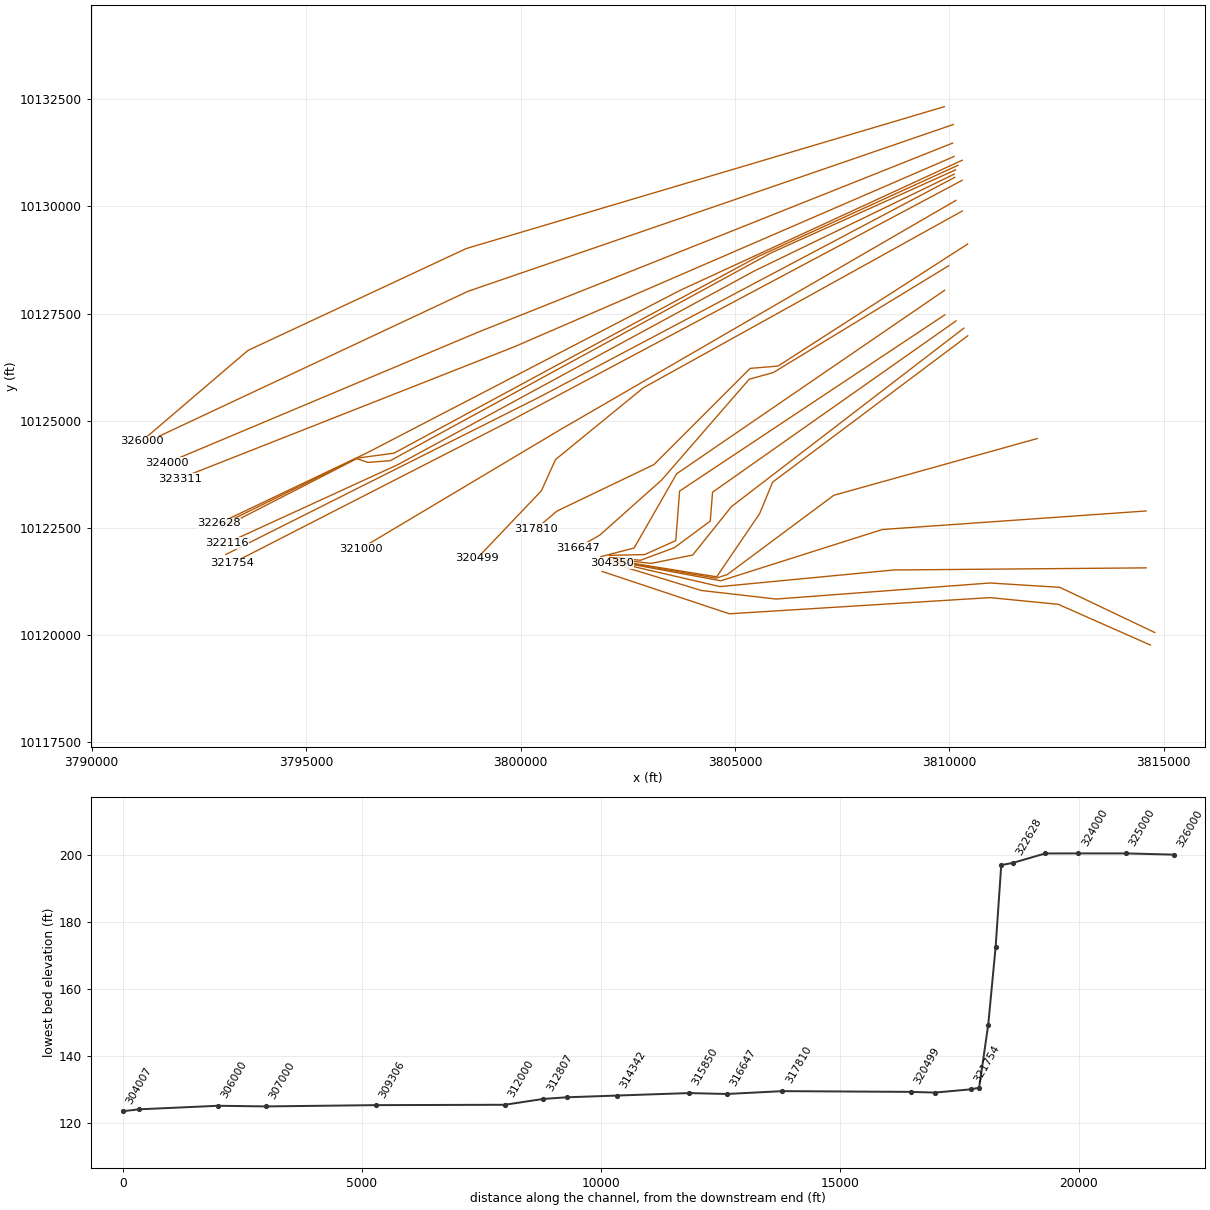
HEC-RAS study WFSJ Main.prj: WFSJ Main Base Level Engineering

--- WFSJ Main.g02 (geometry) --- (continued)

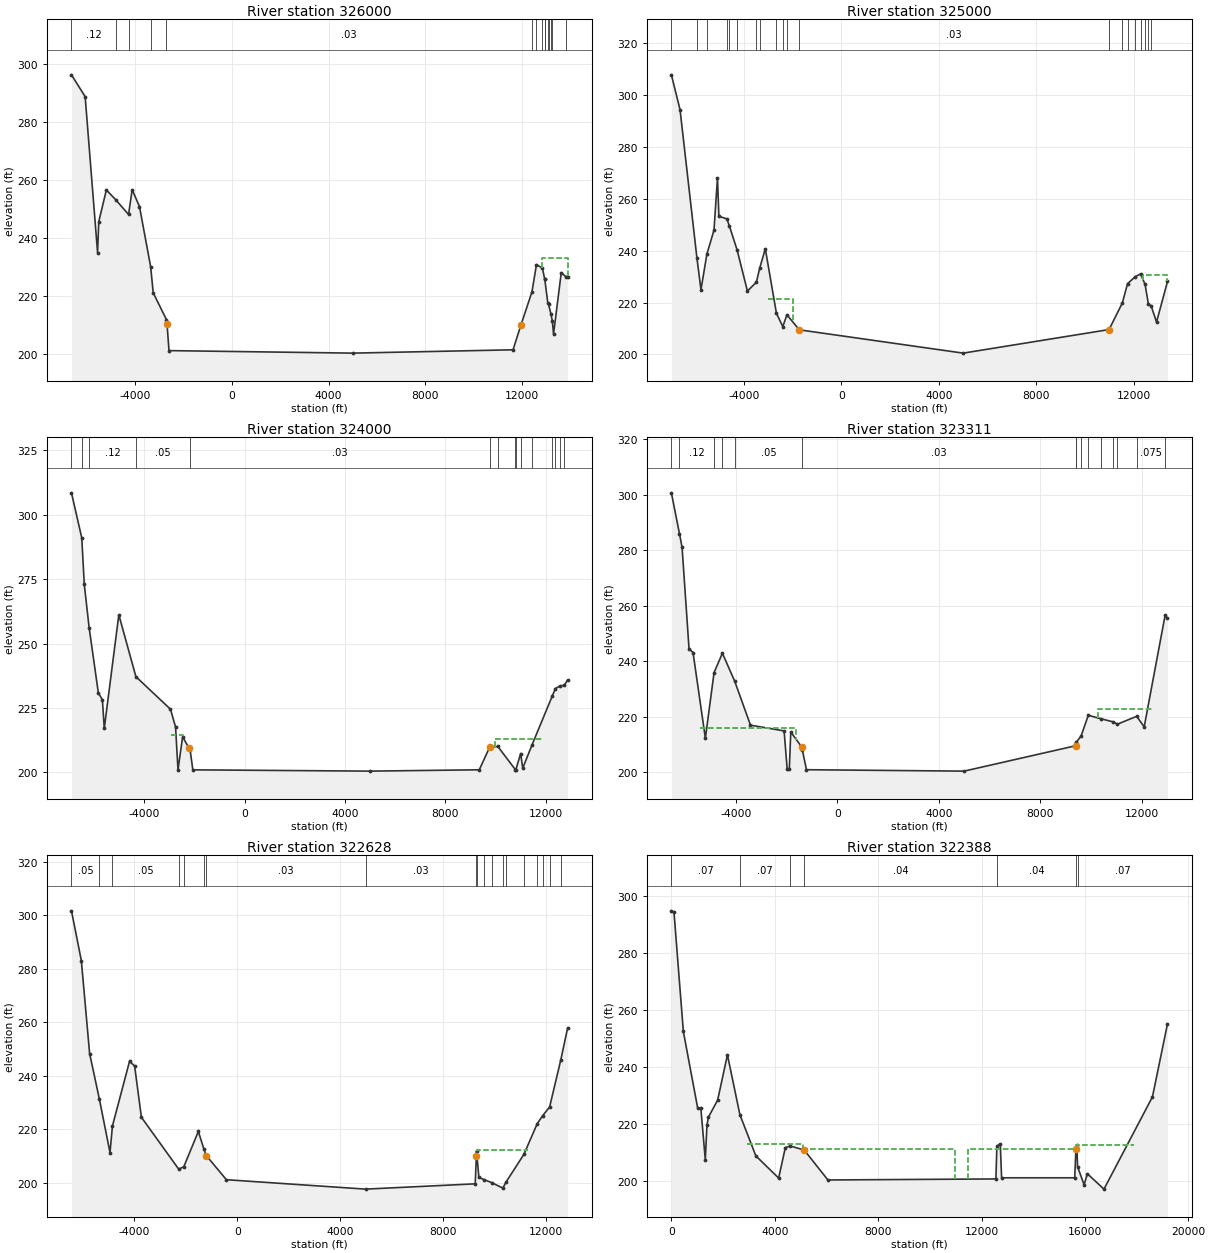
Type RM Length L Ch R = 1 ,326000  ,1000,1000,1000
BEGIN DESCRIPTION:
WFSJ Main 323.0
END DESCRIPTION:
XS GIS Cut Line= 4
      3809882.02     10132327.81      3798735.55     10129016.91
      3793642.83     10126637.69      3791168.91     10124521.84
#Sta/Elev= 30
 -6627.8  296.29 -6062.6  288.76   -5549  234.88   -5500  245.56 -5185.4  256.51
 -4804.3  253.17 -4268.4  248.04 -4119.8  256.61 -3817.3  250.78 -3355.7     230
 -3249.5  220.97 -2701.1  211.68-2677.47  210.07 -2596.8     201  4998.7  200.13
 11622.4  201.2811947.09  209.81 12402.9  221.26 12590.8  230.74 12836.7  229.49
 12929.3  225.73 12933.7  225.69 13059.4  217.43 13087.7  217.02 13185.1  213.79
   13246  211.27 13296.4  206.76 13614.8  227.93 13811.6  226.49 13876.4  226.59
#Mann= 15 ,-1 , 0
 -6627.8     .12       0 -4804.3     .05       0 -4268.4     .12       0
 -3355.7     .05       0 -2701.1     .03       0 12402.9     .05       0
 12590.8    .075       0 12836.7     .05       0 12929.3    .075       0
 12933.7     .05       0 13059.4    .075       0 13087.7     .05       0
 13185.1    .075       0   13246     .05       0 13811.6    .075       0
#XS Ineff= 1 ,-1
 12813.4 13876.4  233.15
Permanent Ineff=
       F
Bank Sta=-2677.47,11947.09
XS Rating Curve= 0 ,0
Exp/Cntr=0.3,0.1

Type RM Length L Ch R = 1 ,325000  ,1000,1000,1000
BEGIN DESCRIPTION:
WFSJ Main 322.0
END DESCRIPTION:
XS GIS Cut Line= 3
      3810090.27     10131911.12      3798773.83     10128017.64
      3791191.67     10124457.22
#Sta/Elev= 30
 -6967.5  307.87 -6612.3  294.43 -5921.4  237.33 -5753.7  224.95 -5512.1  238.68
   -5220  247.96 -5077.1   268.1   -5020   253.3 -4688.2  252.29 -4585.2  249.42
 -4276.2  240.43   -3849  224.45   -3481  227.87 -3349.2  233.17 -3115.5  240.75
 -2660.6  215.91 -2397.7  210.72 -2230.3   215.3-1722.17  209.49  4998.6   200.5
10981.02  209.59 11524.7  219.85 11738.9  227.32 12060.1  230.02 12274.3   231.1
   12458  226.98 12595.5  219.32 12702.6  218.82 12927.2  212.48 13376.5  228.15
#Mann= 20 ,-1 , 0
 -6967.5     .12       0 -5921.4     .05       0 -5512.1     .12       0
 -4688.2     .05       0 -4585.2     .12       0 -4276.2     .12       0
   -3481     .12       0 -3349.2     .05       0 -2660.6     .05       0
 -2397.7    .075       0 -2230.3     .05       0-1722.17     .03       0
10981.02     .05       0 11524.7     .05       0 11738.9      .1       0
 12060.1    .075       0 12274.3    .075       0   12458     .05       0
 12595.5    .075       0 12702.6     .05       0
#XS Ineff= 2 ,-1
   -2990 -1970.3  221.37   12386 13376.5  230.58
Permanent Ineff=
       F       F
Bank Sta=-1722.17,10981.02
XS Rating Curve= 0 ,0
Exp/Cntr=0.3,0.1

Type RM Length L Ch R = 1 ,324000  ,689,689,689
BEGIN DESCRIPTION:
WFSJ Main 321.0
END DESCRIPTION:
XS GIS Cut Line= 3
        3810073.     10131477.12      3799016.19     10127066.92
      3791754.81     10124011.82
#Sta/Elev= 30
 -6903.9  308.54 -6493.7  291.05   -6393  272.96 -6200.1  256.24 -5832.5  230.86
   -5671  228.22 -5595.7  217.09 -5015.7  261.19 -4334.9  237.17 -2956.4  224.53
 -2753.4  217.62 -2656.5     201 -2471.3  213.84 -2231.4  209.65   -2172  208.63
 -2064.3     201  4998.6   200.5  9357.1  201.02 9771.11   209.8 10095.8  210.08
 10796.3  201.08 10814.6  201.05   11007  207.34 11088.8  201.64 11464.1  210.78
 12271.2  229.75 12394.3  232.56 12587.2  233.61 12740.8  233.77 12877.9  235.86
#Mann= 15 ,-1 , 0
 -6903.9     .12       0 -6493.7     .05       0 -6200.1     .12       0
 -4334.9     .05       0   -2172     .03       0 9771.11     .05       0
 10095.8     .05       0 10796.3    .075       0 10814.6      .1       0
   11007    .075       0 11464.1     .05       0 12271.2      .1       0
 12394.3     .05       0 12587.2    .075       0 12740.8     .05       0
#XS Ineff= 2 ,-1
  9988.8   11845  213.16   -2950 -2441.2  214.45
Permanent Ineff=
       F       F
Bank Sta=-2231.4,9771.11
XS Rating Curve= 0 ,0
Exp/Cntr=0.3,0.1

Type RM Length L Ch R = 1 ,323311  ,683,683,683
BEGIN DESCRIPTION:
WFSJ Main 320.0
END DESCRIPTION:
XS GIS Cut Line= 3
      3810107.64     10131164.59      3799847.26     10126720.16
      3792052.47     10123647.38
#Sta/Elev= 30
 -6543.1  300.74 -6223.9  286.01 -6121.4  281.11 -5846.9  244.55 -5689.6  243.22
 -5202.9  212.35 -4859.6     236 -4531.4  242.96 -4045.6  232.86 -3424.1  217.05
 -2098.1  214.98 -1977.1  201.18 -1893.9  201.11 -1835.5  214.58 -1391.7  209.03
 -1377.7  208.02 -1216.5     201  4998.6  200.49  9394.2  209.63  9399.7  210.52
  9415.3  210.82  9610.8  213.15  9894.8   220.6 10410.5  219.31 10862.8  218.27
 11044.1   217.4 11803.5  220.24 12098.3  216.43 12924.7   256.7 13017.1  255.49
#Mann= 15 ,-1 , 0
 -6543.1     .05       0 -6223.9     .12       0 -4859.6     .05       0
 -4531.4     .12       0 -4045.6     .05       0 -1377.7     .03       0
  9399.7     .05       0  9415.3    .075       0  9610.8     .05       0
  9894.8    .075       0 10410.5      .1       0 10862.8    .075       0
 11044.1     .05       0 11803.5    .075       0 12924.7     .05       0
#XS Ineff= 2 ,-1
   -5400 -1613.9  216.08 10295.6   12450  222.91
Permanent Ineff=
       F       F
Bank Sta=-1391.7,9394.2
XS Rating Curve= 0 ,0
Exp/Cntr=0.3,0.1

Type RM Length L Ch R = 1 ,322628  ,240,240,240
BEGIN DESCRIPTION:
Mapping XS ff1f583c
END DESCRIPTION:
XS GIS Cut Line= 4
      3810298.63     10131077.79      3803718.79      10128039.6
      3796401.08     10124237.52      3792967.89     10122601.22
#Sta/Elev= 30
 -6449.1  301.72 -6065.8  283.13 -5743.3  248.37 -5362.9  231.28 -4950.3  211.34
 -4855.7  221.27 -4190.3  245.46 -3992.7  243.68 -3729.4  224.54 -2276.9  205.12
   -2079  206.05 -1513.7  219.22   -1303 212.761 -1206.6  210.22  -423.3  201.18
    4990  197.66  9255.3  199.64  9300.7  210.15  9306.3  211.96  9397.1  202.08
  9601.8  201.21  9899.4  200.07 10329.2  198.05 10460.6   200.4 11149.8  210.68
 11665.9  222.11 11880.6  225.14 12149.3  228.38 12583.8  245.98   12848  257.86
#Mann= 19 ,-1 , 0
 -6449.1     .05       0 -5362.9     .05       0 -4855.7     .05       0
 -2276.9     .12       0   -2079     .05       0   -1303     .03       0
 -1206.6     .03       0    4990     .03       0  9300.7     .05       0
  9306.3     .05       0  9601.8    .075       0  9899.4     .05       0
 10329.2    .075       0 10460.6     .05       0 11149.8     .05       0
 11665.9    .075       0 11880.6     .05       0 12149.3     .05       0
 12583.8     .12       0
#XS Ineff= 2 ,-1
   -5770 -1513.7  219.22  9336.4   11325  212.45
Permanent Ineff=
       F       T
Bank Sta=-1206.6,9300.7
XS Rating Curve= 0 ,0
Exp/Cntr=0.5,0.3

Type RM Length L Ch R = 1 ,322388  ,118,118,118
XS GIS Cut Line= 5
      3810201.02     10130959.54      3805526.54     10128824.12
      3797049.97     10124240.79      3796178.45      10124122.3
      3793002.66     10122557.19
#Sta/Elev= 30
       0  294.82   100.8  294.36   462.7  252.45  1019.8  225.39  1140.4  225.38
  1312.6  207.34  1376.2  219.43  1433.2  222.32  1789.6  228.27  2169.1   244.2
  2651.6  223.15  3268.7  208.69  4150.7   200.9  4409.5  211.63    4599  212.17
  5139.1  210.75  6056.5  200.23 12556.1  200.59 12594.2  212.05 12725.4  212.93
 12777.1  200.99 15605.2  200.99 15652.8  211.13 15687.6  212.47 15715.7  204.91
 15968.3  198.54 16097.5   202.4 16737.5  197.01 18612.8  229.42 19195.4  255.09
#Mann= 7 ,-1 , 0
       0     .07       0  2651.6     .07       0    4599     .07       0
  5139.1     .04       0 12594.2     .04       0 15652.8     .05       0
 15715.7     .07       0
#XS Ineff= 5 ,-1
 15670.8   17900  212.39     545  2169.1   244.2    2920  5087.3  213.02
    5088   10975     211   11465   15670     211
Permanent Ineff=
       T       F       F       T       T
Bank Sta=5139.1,15652.8
XS Rating Curve= 0 ,0
Exp/Cntr=0.5,0.3

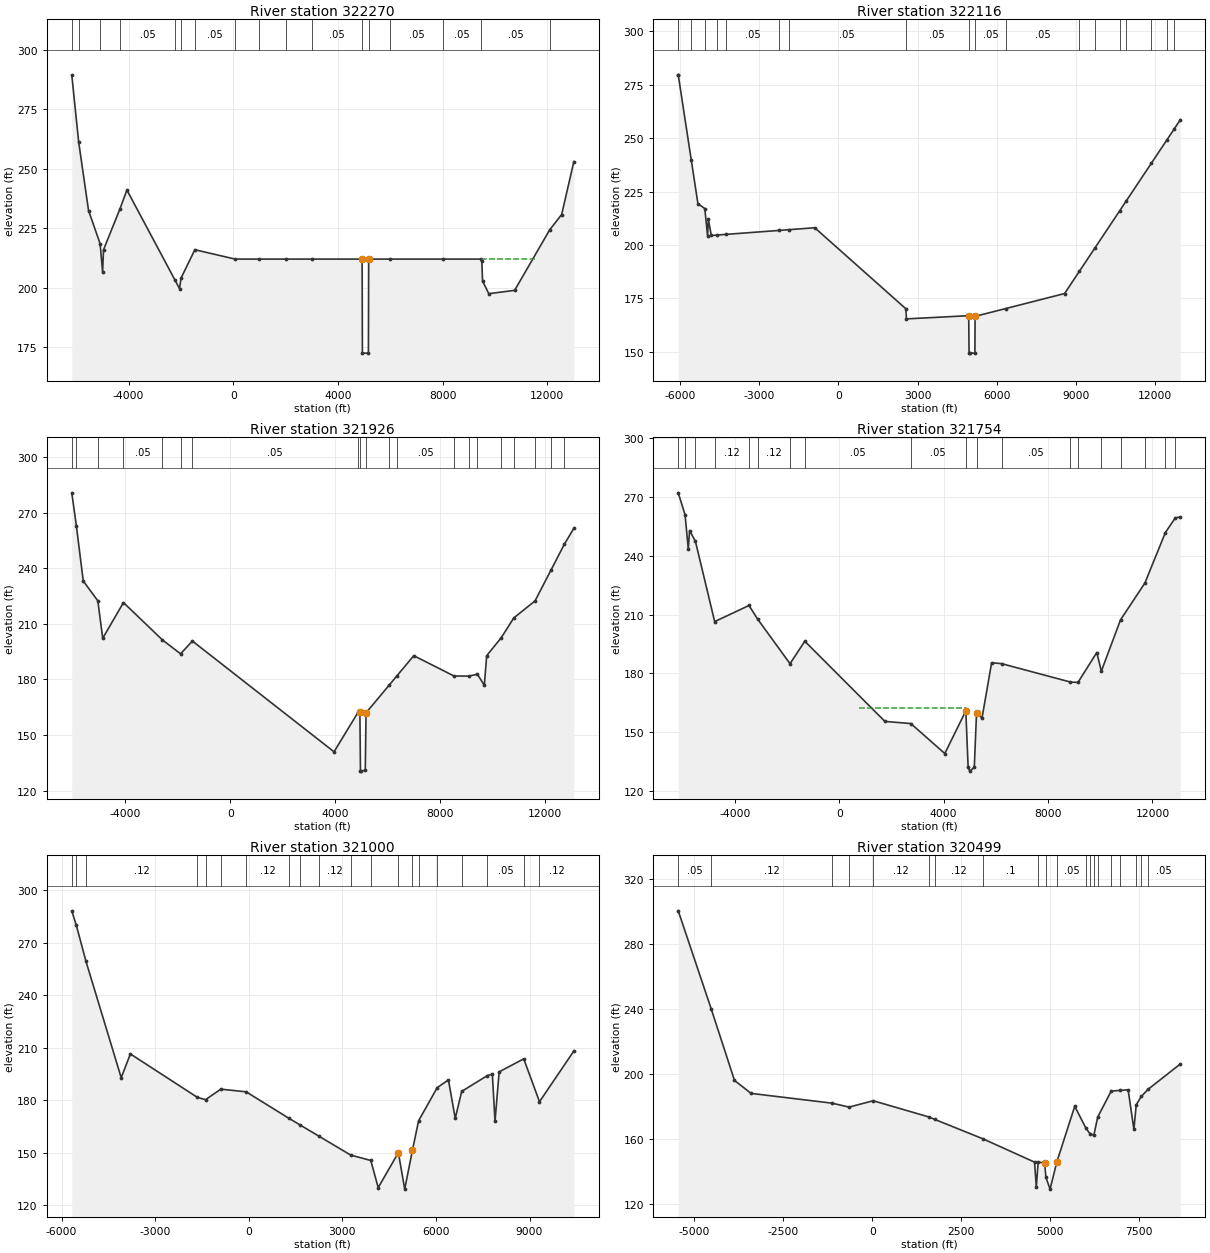
Type RM Length L Ch R = 1 ,322270  ,154,154,154
BEGIN DESCRIPTION:
Mapping XS 5c372406. Elevations of dam from TWDB website. Invert modeled as if gates are open. Gates are 30' tall with top elevation when closed of 202.5. SJRA normal pool elevation of lake is 201.0'
END DESCRIPTION:
XS GIS Cut Line= 6
      3810142.43     10130852.12       3805854.2     10128920.68
      3796960.97     10124063.91      3796440.14     10124024.85
      3796179.72     10124111.65      3793024.37      10122488.4
#Sta/Elev= 30
 -6169.8   289.4 -5904.7  261.06 -5528.7  232.41 -5086.3  218.44 -4991.5  206.58
 -4957.4  215.88 -4334.8  232.92 -4062.7     241 -2227.2  203.21   -2052   199.6
 -1994.3  204.02 -1466.7  215.94      70     212    1000     212    2000     212
    3000     212    4925     212    4935   172.5    5165   172.5    5175     212
    6000     212    8000     212    9465     212  9498.3  211.07  9526.1   202.8
  9764.4  197.47 10751.1  198.87 12091.4  224.28 12549.6  230.73 13014.6  252.96
#Mann= 17 ,-1 , 0
 -6169.8     .12       0 -5904.7     .05       0 -5086.3     .05       0
 -4334.8     .05       0 -2227.2     .12       0 -1994.3     .06       0
 -1466.7     .05       0      70     .05       0    1000     .05       0
    2000     .05       0    3000     .05       0    4925     .03       0
    5175     .05       0    6000     .05       0    8000     .05       0
    9465     .05       0 12091.4     .05       0
#XS Ineff= 3 ,-1
   -5735 -4062.7     241 -3080.1 -1466.7  215.94  9470.1   11540   212.1
Permanent Ineff=
       F       F       T
Bank Sta=4925,5175
XS Rating Curve= 0 ,0
Exp/Cntr=0.8,0.6

Type RM Length L Ch R = 1 ,322116  ,190,190,190
BEGIN DESCRIPTION:
Mapping XS dd0cefc1
END DESCRIPTION:
XS GIS Cut Line= 5
        3810112.     10130752.63      3805454.61     10128494.54
      3800059.93     10125561.67      3797138.64     10123971.97
      3793151.51     10122142.13
#Sta/Elev= 30
 -6069.4  279.62 -6066.2  279.36 -5576.9  239.84 -5323.3  219.36 -5062.6  217.04
 -4956.6  204.22 -4928.4  212.04 -4815.6  204.44 -4598.2  204.64 -4276.5  204.94
   -2245  206.81 -1881.2  207.15  -895.2  208.06  2557.6  170.15  2579.4  165.41
  4940.4  166.91  4953.3  149.68    4990  149.39  5175.1  149.39    5181   166.6
  6348.9  170.27  8572.7  177.27  9129.8   187.6  9723.9  198.61 10655.5  215.88
 10898.2  220.38 11857.6  238.16 12455.9  249.25 12723.1   254.2 12959.7  258.59
#Mann= 19 ,-1 , 0
 -6069.4     .12       0 -6066.2     .05       0 -5576.9     .12       0
 -5062.6     .05       0 -4598.2     .12       0 -4276.5     .05       0
   -2245     .12       0 -1881.2     .05       0  2557.6     .05       0
  4940.4     .03       0    5181     .05       0  6348.9     .05       0
  9129.8    .075       0  9723.9      .1       0 10655.5     .05       0
 10898.2     .12       0 11857.6    .075       0 12455.9     .05       0
 12723.1     .12       0
Bank Sta=4940.4,5181
XS Rating Curve= 0 ,0
Exp/Cntr=0.5,0.3

Type RM Length L Ch R = 1 ,321926  ,172,172,172
BEGIN DESCRIPTION:
WFSJ Main 319.0
END DESCRIPTION:
XS GIS Cut Line= 3
      3810125.05      10130678.5      3800489.62     10125574.33
      3793128.52     10121876.41
#Sta/Elev= 30
 -6043.3  280.69   -5869  263.04 -5605.1  233.13 -5050.5  222.46 -4863.5  202.22
 -4072.7  221.49 -2590.1  201.38 -1894.8  193.84 -1444.4  200.74  3955.6  140.99
  4860.6  162.03  4940.5  162.43  4962.9  130.86    4990  130.56  5147.1  131.08
  5175.9     162  6067.3  177.11    6352  181.94  6994.8  192.84  8530.4  181.87
  9091.6  181.83  9420.6  182.81  9685.5  176.89  9774.8  192.82 10335.3  202.63
 10809.5  213.22 11617.8  222.38 12232.2  239.16 12736.7  252.96 13098.3  261.56
#Mann= 20 ,-1 , 0
 -6043.3     .05       0   -5869     .12       0 -5050.5     .12       0
 -4072.7     .05       0 -2590.1     .12       0 -1894.8     .05       0
 -1444.4     .05       0  4860.6     .05       0  4940.5     .04       0
  5175.9     .05       0  6067.3    .075       0    6352     .05       0
  8530.4      .1       0  9091.6    .075       0  9420.6     .12       0
 10335.3     .05       0 10809.5     .12       0 11617.8     .05       0
 12232.2     .05       0 12736.7     .12       0
#XS Ineff= 1 ,-1
    1540  4860.6  162.03
Permanent Ineff=
       F
Bank Sta=4940.5,5175.9
XS Rating Curve= 0 ,0
Exp/Cntr=0.3,0.1

Type RM Length L Ch R = 1 ,321754  ,754,754,754
BEGIN DESCRIPTION:
Mapping XS 333a849d
END DESCRIPTION:
XS GIS Cut Line= 3
      3810298.64     10130609.04      3799708.37     10124966.69
       3793273.9     10121668.07
#Sta/Elev= 30
 -6164.8  272.22 -5902.9  261.01   -5780  243.55 -5730.4  252.96 -5506.5  247.45
 -4769.1  206.45 -3454.3  214.68 -3128.3   207.8 -1882.7  184.95 -1317.6  196.41
  1751.7  155.46  2743.2  154.37  4044.6  139.07  4849.6  160.85  4938.7  132.17
  4998.6  130.07  5174.7  132.02 5260.27159.7544  5470.8  157.18  5838.6  185.44
  6218.9  184.97  8851.7  175.59  9145.5  175.36  9866.7  190.66 10040.8  181.12
 10776.1  207.37 11707.8  226.11   12492  251.89 12872.5  259.41 13065.5  259.89
#Mann= 19 ,-1 , 0
 -6164.8     .05       0 -5902.9     .12       0 -5506.5     .05       0
 -4769.1     .12       0 -3454.3     .05       0 -3128.3     .12       0
 -1882.7     .05       0 -1317.6     .05       0  2743.2     .05       0
  4849.6     .04       0 5260.27     .05       0  6218.9     .05       0
  8851.7    .075       0  9145.5      .1       0 10040.8     .05       0
 10776.1     .12       0 11707.8     .05       0   12492     .05       0
 12872.5     .05       0
#XS Ineff= 1 ,-1
     750  4840.2  162.32
Permanent Ineff=
       F
Bank Sta=4849.6,5260.27
XS Rating Curve= 0 ,0
Exp/Cntr=0.3,0.1

Type RM Length L Ch R = 1 ,321000  ,501,501,501
BEGIN DESCRIPTION:
WFSJ Main 318.0
END DESCRIPTION:
XS GIS Cut Line= 3
      3810153.55     10130141.31      3800921.61     10124785.93
      3796267.48     10122008.46
#Sta/Elev= 30
 -5672.8  288.23 -5525.7  279.89 -5216.8  259.31 -4088.1   192.8 -3794.1   206.4
 -1645.8  181.56 -1385.3  180.25  -894.5  186.27   -83.4  184.73  1277.9   169.7
  1640.8  165.84  2249.2  159.38  3264.3   148.6  3912.4  145.47  4148.9  129.94
  4795.5  149.97  4998.6   129.1  5248.3   151.5  5443.7  168.18  6041.2  187.15
  6400.4  191.53  6618.3  169.54  6825.1  184.98  7645.2  193.99  7807.4  194.91
    7893  167.83  8025.4  196.15  8814.2   203.6  9318.9  179.08 10419.9  208.09
#Mann= 20 ,-1 , 0
 -5672.8     .12       0 -5525.7     .05       0 -5216.8     .12       0
 -1645.8     .05       0 -1385.3     .12       0  -894.5     .05       0
   -83.4     .12       0  1277.9      .1       0  1640.8     .12       0
  2249.2     .12       0  3264.3      .1       0  3912.4     .05       0
  4795.5     .04       0  5248.3     .05       0  5443.7     .12       0
  6041.2     .12       0  6825.1    .075       0  7645.2     .05       0
  8814.2      .1       0  9318.9     .12       0
Bank Sta=4795.5,5248.3
XS Rating Curve= 0 ,0
Exp/Cntr=0.3,0.1

Type RM Length L Ch R = 1 ,320499  ,2689,2689,2689
BEGIN DESCRIPTION:
WFSJ Main 317.0
END DESCRIPTION:
XS GIS Cut Line= 5
      3810299.44     10129891.35      3802864.71     10125767.15
       3800816.1      10124091.8      3800486.24     10123362.63
      3798993.18     10121791.45
#Sta/Elev= 30
 -5455.6  300.25 -4524.9  239.78   -3874   196.1 -3408.2  188.11 -1133.9  182.12
  -652.8   179.7    25.8  183.59    1591  173.64  1751.9  172.17  3108.3  160.24
  4562.4  145.89  4611.9  130.34  4663.3  145.95  4846.7  145.32  4881.8  136.53
  4998.6  129.31 5191.66146.2109  5692.8   180.2  6009.4  166.64  6119.3  163.44
  6229.1   162.4  6338.9   173.6  6717.7  189.53  6972.5  189.96  7193.4  190.33
    7356  165.97  7421.4  181.12  7562.2  186.21  7754.6  190.62  8660.6  206.17
#Mann= 20 ,-1 , 0
 -5455.6     .05       0 -4524.9     .12       0 -1133.9     .12       0
  -652.8     .05       0    25.8     .12       0    1591      .1       0
  1751.9     .12       0  3108.3      .1       0  4663.3     .05       0
  4881.8     .03       0 5191.66     .05       0  6009.4      .1       0
  6119.3     .05       0  6229.1      .1       0  6338.9     .12       0
  6717.7     .05       0  6972.5     .12       0  7421.4     .05       0
  7562.2    .075       0  7754.6     .05       0
Bank Sta=4846.7,5191.66
XS Rating Curve= 0 ,0
Exp/Cntr=0.3,0.1

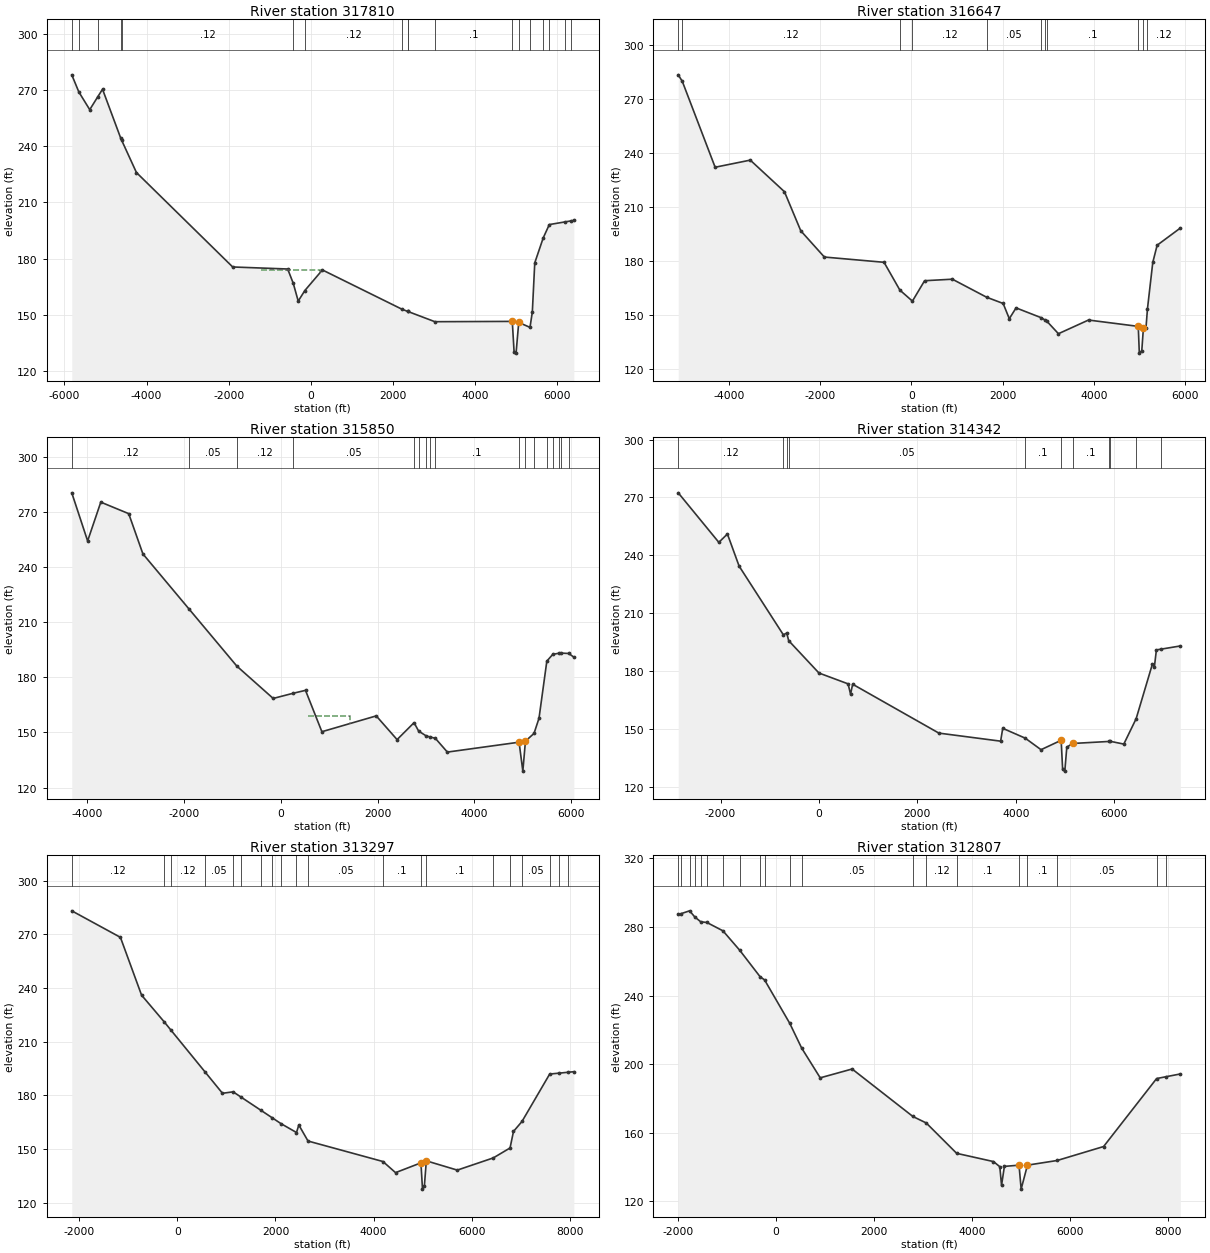
Type RM Length L Ch R = 1 ,317810  ,1163,1163,1163
BEGIN DESCRIPTION:
WFSJ Main 316.0
END DESCRIPTION:
XS GIS Cut Line= 6
      3810424.42     10129120.51      3806003.35     10126273.14
      3805354.25       10126219.       3803111.9     10123974.66
        3800849.     10122888.43      3800364.71     10122477.22
#Sta/Elev= 30
 -5822.3  278.03   -5650  268.88 -5384.8  259.44 -5187.2  266.39 -5073.2  270.33
 -4626.9  244.06 -4608.1  243.16 -4247.3  225.89   -1903   175.5  -563.6  174.42
  -426.8  166.71  -307.3   157.3  -145.2  162.94   281.7  173.92  2219.4  152.96
  2363.4  151.76  2363.9  151.76  3021.2   146.3  4906.4  146.46  4950.8  130.04
  4998.6  129.53  5063.4  145.91  5337.7  143.27  5394.5  151.41  5453.9   177.7
  5660.1  191.03  5808.2  198.13  6201.5  199.59    6334  200.08  6405.7  200.35
#Mann= 18 ,-1 , 0
 -5822.3     .12       0   -5650     .05       0 -5187.2     .12       0
 -4626.9     .05       0 -4608.1     .12       0  -426.8      .1       0
  -145.2     .12       0  2219.4     .05       0  2363.4     .12       0
  2363.9     .05       0  3021.2      .1       0  4906.4     .07       0
  5063.4      .1       0  5337.7     .12       0  5660.1     .05       0
  5808.2     .12       0  6201.5     .05       0    6334     .12       0
#XS Ineff= 1 ,-1
   -1220   225.1  173.94
Permanent Ineff=
       F
Bank Sta=4906.4,5063.4
XS Rating Curve= 0 ,0
Exp/Cntr=0.3,0.1

Type RM Length L Ch R = 1 ,316647  ,797,797,797
BEGIN DESCRIPTION:
WFSJ Main 315.0
END DESCRIPTION:
XS GIS Cut Line= 6
      3809985.57     10128616.13      3805892.24     10126120.78
      3805331.63     10125966.12      3803292.89     10123616.15
      3801847.58     10122327.09      3801338.29     10122035.29
#Sta/Elev= 30
 -5113.4   283.5 -5023.9  279.85 -4304.3  232.09 -3533.5  236.05 -2784.1  218.48
   -2426  196.74 -1908.9  182.13  -599.9  179.21  -252.8  163.74    22.3  157.61
   289.6  168.96   898.3  169.81  1651.3  159.76    2012  156.31  2147.2  147.83
  2295.4  153.85  2851.2  148.34    2940  146.92  2970.5  146.43  3224.6  139.48
    3884  147.09    4975  143.56  4998.6  128.68  5052.8  130.08  5087.9  142.57
  5144.7  142.76  5177.5  153.42  5293.6  179.12  5389.1   188.7  5897.5  198.25
#Mann= 11 ,-1 , 0
 -5113.4     .05       0 -5023.9     .12       0  -252.8      .1       0
    22.3     .12       0  1651.3     .05       0  2851.2      .1       0
    2940     .05       0  2970.5      .1       0    4975     .07       0
  5087.9      .1       0  5177.5     .12       0
#XS Ineff= 1 ,-1
    -480   289.6  168.96
Permanent Ineff=
       F
Bank Sta=4975,5087.9
XS Rating Curve= 0 ,0
Exp/Cntr=0.3,0.1

Type RM Length L Ch R = 1 ,315850  ,1508,1508,1508
BEGIN DESCRIPTION:
WFSJ Main 314.0
END DESCRIPTION:
XS GIS Cut Line= 4
      3809890.15     10128043.26      3803640.11     10123759.38
      3802647.69     10122025.83      3801875.14     10121826.18
#Sta/Elev= 30
 -4320.2  280.36 -3992.6  254.18 -3720.5  275.29 -3143.8  269.03 -2850.5  247.12
 -1890.4  216.92  -908.7  186.05  -159.1   168.5   255.2  171.32   508.7   172.9
   847.2  150.39  1970.2     159  2400.6   146.1  2751.2  155.31  2846.1  150.74
  3002.9  148.09    3074   147.6    3191   146.8  3439.5  139.31  4921.1  144.69
  4998.6  128.95  5052.6  145.26  5229.9  149.48  5332.7  157.71  5494.5   188.8
  5617.7  192.49  5745.9  193.09  5787.7  193.17  5947.7  192.95  6052.5  190.96
#Mann= 17 ,-1 , 0
 -4320.2     .12       0 -1890.4     .05       0  -908.7     .12       0
   255.2     .05       0  2751.2      .1       0  2846.1     .05       0
  3002.9      .1       0    3074     .05       0    3191      .1       0
  4921.1     .07       0  5052.6      .1       0  5229.9     .12       0
  5494.5     .05       0  5617.7      .1       0  5745.9     .05       0
  5787.7      .1       0  5947.7     .05       0
#XS Ineff= 2 ,-1
     570  1423.2  158.95    2000  2751.2  155.31
Permanent Ineff=
       F       F
Bank Sta=4921.1,5052.6
XS Rating Curve= 0 ,0
Exp/Cntr=0.3,0.1

Type RM Length L Ch R = 1 ,314342  ,1045,1045,1045
BEGIN DESCRIPTION:
WFSJ Main 313.0
END DESCRIPTION:
XS GIS Cut Line= 5
      3809894.47     10127470.33      3803709.56     10123355.73
      3803618.93     10122199.01      3802892.49     10121873.05
      3802071.19     10121855.72
#Sta/Elev= 30
   -2860  272.38 -2034.6  246.72 -1860.2  251.06 -1622.8  234.43  -723.9  198.86
  -654.4  199.72    -615  195.81      .4  179.04   592.5  173.42   643.1  168.09
   685.7  173.23  2438.1  147.91  3693.8  143.73  3736.6  150.39  4194.5  145.28
  4515.1  139.31  4924.3  144.19  4954.4  129.06  4998.6  128.21    5039  140.61
    5155  142.53  5893.8  143.58  5927.3  143.63  6197.9  142.22  6448.8  155.38
  6779.7  183.71  6819.7  182.27  6860.3     191  6948.1  191.37  7346.5  193.05
#Mann= 11 ,-1 , 0
   -2860     .12       0  -723.9     .05       0  -654.4     .12       0
    -615     .05       0  4194.5      .1       0  4924.3     .07       0
    5155      .1       0  5893.8     .05       0  5927.3      .1       0
  6448.8     .05       0  6948.1      .1       0
Bank Sta=4924.3,5155
XS Rating Curve= 0 ,0
Exp/Cntr=0.3,0.1

Type RM Length L Ch R = 1 ,313297  ,490,490,490
BEGIN DESCRIPTION:
WFSJ Main 312.0
END DESCRIPTION:
XS GIS Cut Line= 6
       3810154.9     10127327.11      3804477.79     10123329.69
      3804423.74      10122654.3      3803583.46     10122032.77
      3802798.74     10121741.11      3802081.45     10121806.94
#Sta/Elev= 30
 -2155.7  283.15 -1163.2  268.34    -732  236.05  -274.4  221.27  -141.6  216.81
   566.2  193.05   918.5  181.23  1135.7  182.04    1303     179  1699.3  171.79
  1925.5  167.67  2110.7   164.3  2428.3  159.32    2476   163.5  2663.3  154.56
  4192.1  143.11  4448.8   136.9  4966.8  142.37  4998.6  127.69    5037  129.44
  5077.1  143.49  5708.5  138.31  6443.2  145.13  6784.7  150.68  6854.9  159.93
  7028.3  165.49  7593.3  191.97  7792.2   192.5  7972.2  192.98    8086  193.29
#Mann= 20 ,-1 , 0
 -2155.7     .12       0  -274.4     .05       0  -141.6     .12       0
   566.2     .05       0  1135.7     .12       0    1303     .05       0
  1699.3     .12       0  1925.5     .05       0  2110.7     .12       0
  2428.3     .05       0  2663.3     .05       0  4192.1      .1       0
  4966.8     .07       0  5077.1      .1       0  6443.2     .05       0
  6784.7      .1       0  7028.3     .05       0  7593.3      .1       0
  7792.2    .075       0  7972.2      .1       0
Bank Sta=4966.8,5077.1
XS Rating Curve= 0 ,0
Exp/Cntr=0.3,0.1

Type RM Length L Ch R = 1 ,312807  ,807,807,807
BEGIN DESCRIPTION:
WFSJ Main 311.0
END DESCRIPTION:
XS GIS Cut Line= 5
      3810337.13      10127157.8      3804916.79     10122991.11
      3804014.01     10121862.63      3803046.65     10121667.49
      3802093.86     10121775.83
#Sta/Elev= 30
 -1986.9  287.33 -1925.8  287.82   -1756  289.44 -1649.5  285.86 -1528.6  283.05
 -1402.9  282.64 -1075.8  277.78  -733.7  266.43  -319.6  251.03  -228.1  249.17
   283.9   223.9   526.7  209.47   905.3  192.08  1555.1  197.23  2793.3  169.55
  3065.5  165.76  3685.2  148.06  4435.1  143.26  4563.8  140.27  4599.1  129.39
  4657.1  140.45  4949.1  141.16  4955.5  141.13  4998.6   127.2  5126.8  141.18
    5732  143.89  6677.9  152.03  7757.9  191.66  7957.4  192.77  8240.8  194.34
#Mann= 20 ,-1 , 0
 -1986.9     .12       0 -1925.8     .05       0   -1756     .12       0
 -1649.5     .05       0 -1528.6     .05       0 -1402.9     .05       0
 -1075.8     .12       0  -733.7     .05       0  -319.6     .12       0
  -228.1     .05       0   283.9     .05       0   526.7     .05       0
  2793.3    .075       0  3065.5     .12       0  3685.2      .1       0
  4949.1     .07       0  5126.8      .1       0    5732     .05       0
  7757.9      .1       0  7957.4    .075       0
Bank Sta=4955.5,5126.8
XS Rating Curve= 0 ,0
Exp/Cntr=0.3,0.1

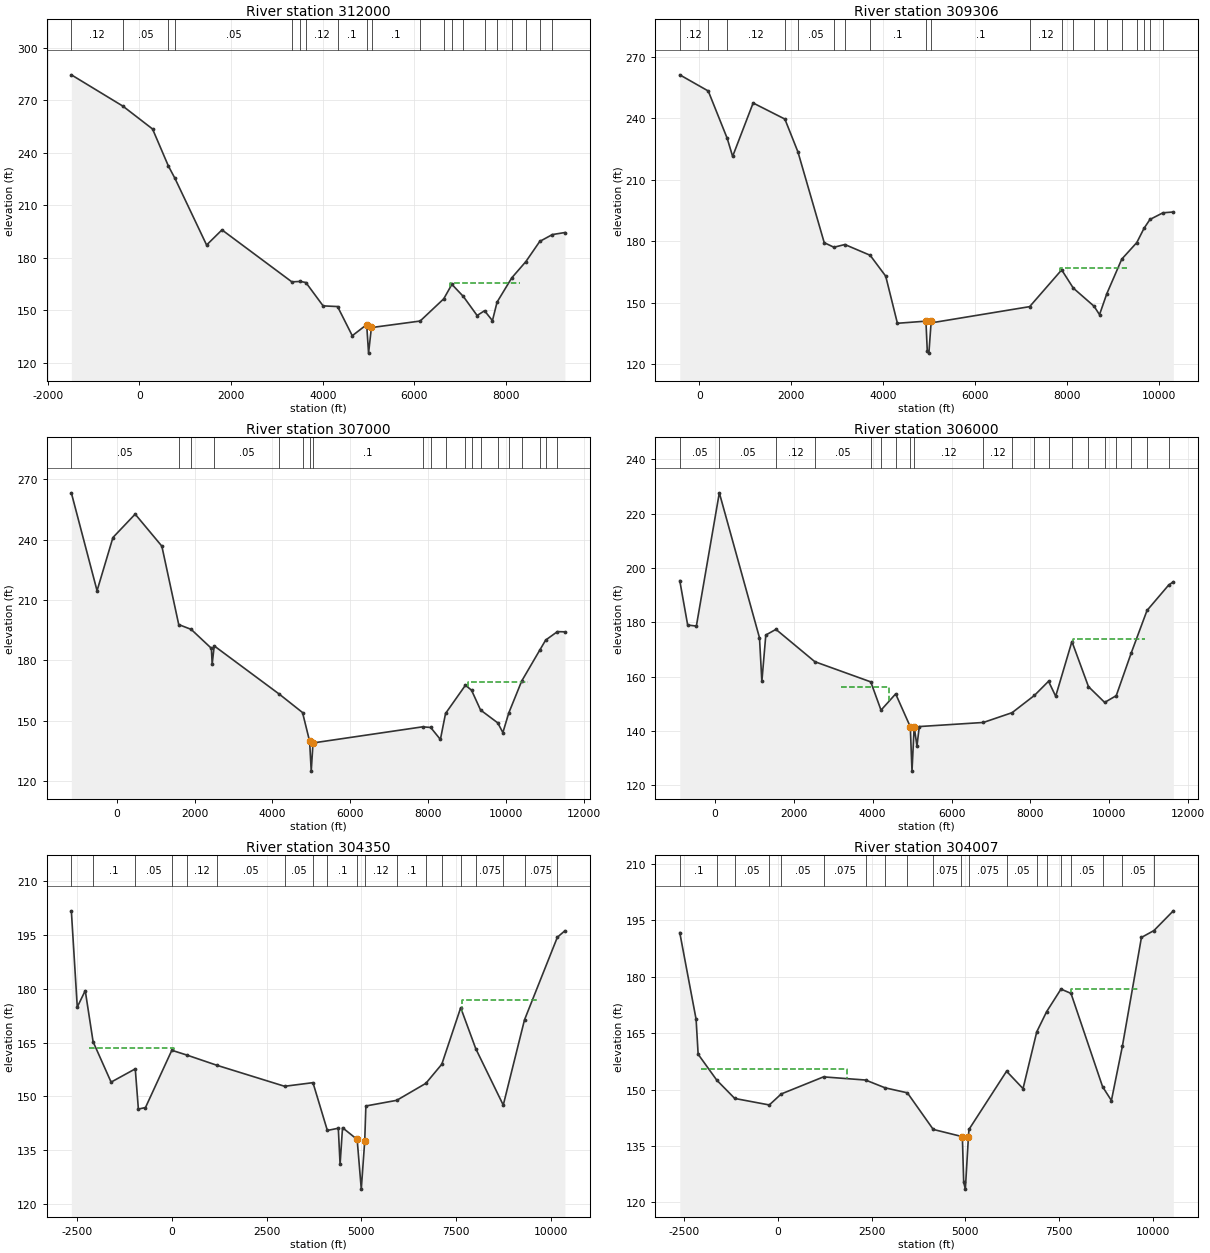
Type RM Length L Ch R = 1 ,312000  ,2694,2694,2694
BEGIN DESCRIPTION:
WFSJ Main 310.0
END DESCRIPTION:
XS GIS Cut Line= 5
      3810428.56     10126979.97       3805878.6     10123564.02
      3805575.43     10122829.57      3804574.43     10121354.99
      3802107.74     10121751.53
#Sta/Elev= 30
 -1484.1  284.44  -359.9  266.56     287   253.5   632.6  232.35     777  225.22
    1466  187.22  1801.4  195.86  3325.6  166.17  3511.1  166.42    3631   165.8
  4007.3  152.45  4322.3  152.07  4643.3   135.4  4957.4  141.75  4998.6  125.46
  5061.3  140.27  5070.2  140.09  6123.6  143.79  6638.6  156.49  6815.7  164.75
  7066.5  157.81  7366.2  146.95  7528.1  149.68  7700.5  144.01  7801.5  154.61
  8122.2  168.48  8429.9  177.76  8732.8  189.29  9008.1  193.19  9280.6  194.35
#Mann= 20 ,-1 , 0
 -1484.1     .12       0  -359.9     .05       0   632.6     .12       0
     777     .05       0  3325.6    .075       0  3511.1     .05       0
    3631     .12       0  4322.3      .1       0  4957.4     .07       0
  5070.2      .1       0  6123.6     .12       0  6638.6     .05       0
  6815.7    .075       0  7066.5     .05       0  7528.1      .1       0
  7801.5     .05       0  8122.2    .075       0  8429.9     .05       0
  8732.8      .1       0  9008.1    .075       0
#XS Ineff= 1 ,-1
  6781.6    8305  165.63
Permanent Ineff=
       F
Bank Sta=4957.4,5061.3
XS Rating Curve= 0 ,0
Exp/Cntr=0.3,0.1

Type RM Length L Ch R = 1 ,309306  ,2306,2306,2306
BEGIN DESCRIPTION:
WFSJ Main 307.0
END DESCRIPTION:
XS GIS Cut Line= 5
      3812046.89     10124581.13      3807305.16     10123257.35
      3804821.62     10121407.48      3804561.76     10121322.58
      3802141.32       10121739.
#Sta/Elev= 30
  -427.2  261.29   193.2  253.39   605.6  230.28   724.2  221.44  1170.7  247.53
  1862.1  239.68  2146.8  223.62  2719.2   179.3  2929.9  177.07  3168.5   178.4
    3719  173.15  4058.3  162.94    4313  139.93  4934.2  140.97  4963.4  126.49
  4998.6  125.35  5048.9  140.96  5055.1  140.15  7193.3  148.06  7890.4  166.02
  8143.6  157.12  8596.8  148.24  8714.8  144.14  8873.3  154.36  9199.7  171.28
  9526.9  179.36  9684.2  186.32  9812.9  190.64 10096.8   193.9   10322  194.29
#Mann= 20 ,-1 , 0
  -427.2     .12       0   193.2     .12       0   605.6     .12       0
  1862.1     .05       0  2146.8     .05       0  2929.9     .12       0
  3168.5     .05       0    3719      .1       0  4934.2     .07       0
  5055.1      .1       0  7193.3     .12       0  7890.4    .075       0
  8143.6     .05       0  8596.8      .1       0  8873.3     .05       0
  9199.7    .075       0  9526.9     .05       0  9684.2    .075       0
  9812.9      .1       0 10096.8    .075       0
#XS Ineff= 1 ,-1
  7859.8    9315  167.13
Permanent Ineff=
       F
Bank Sta=4934.2,5048.9
XS Rating Curve= 0 ,0
Exp/Cntr=0.3,0.1

Type RM Length L Ch R = 1 ,307000  ,1000,1000,1000
BEGIN DESCRIPTION:
WFSJ Main 305.0
END DESCRIPTION:
XS GIS Cut Line= 4
      3814586.82     10122891.16       3808438.1     10122458.86
      3804669.28     10121261.93      3802151.31     10121728.22
#Sta/Elev= 30
 -1163.9  263.31  -503.3  214.65   -95.3   241.1   475.6  252.72  1160.8  236.82
  1594.8  197.82  1914.6  195.43  2433.9  186.01    2454  178.14  2506.5  187.22
  4183.5  163.16  4775.4  154.09  4957.2  139.82  4998.6  124.97  5044.9  138.98
  7862.5     147  8067.2  146.67    8317  140.71  8449.2  153.63  8960.5  167.68
  9116.6  165.21  9348.7  155.35  9791.9  148.94  9921.9  144.12 10072.2  153.81
 10405.4  169.75 10875.2  185.31 11021.7  190.12 11323.3  194.32 11515.1  194.21
#Mann= 20 ,-1 , 0
 -1163.9     .05       0  1594.8     .05       0  1914.6     .12       0
  2506.5     .05       0  4183.5      .1       0  4775.4      .1       0
  4957.2     .07       0  5044.9      .1       0  7862.5     .12       0
  8067.2      .1       0  8449.2     .12       0  8960.5     .05       0
  9116.6    .075       0  9348.7     .05       0  9791.9      .1       0
 10072.2     .05       0 10405.4    .075       0 10875.2    .075       0
 11021.7      .1       0 11323.3    .075       0
#XS Ineff= 1 ,-1
  9026.9   10570  169.34
Permanent Ineff=
       F
Bank Sta=4957.2,5044.9
XS Rating Curve= 0 ,0
Exp/Cntr=0.3,0.1

Type RM Length L Ch R = 1 ,306000  ,1650,1650,1650
BEGIN DESCRIPTION:
WFSJ Main 304.0
END DESCRIPTION:
XS GIS Cut Line= 4
      3814588.34     10121563.33      3808701.34     10121513.82
      3804650.82     10121125.83      3802164.73     10121702.21
#Sta/Elev= 30
  -887.2  195.31  -686.7  178.95  -466.7  178.57   115.4  227.63  1133.4  174.25
  1193.4  158.17  1293.4  175.27  1550.1  177.36  2536.4  165.45  3953.7  158.02
  4213.3  147.61  4584.7   153.6 4955.59  141.48  4998.6  125.16  5053.7  141.59
  5124.1  134.37  5182.7  141.57  6806.9  143.08  7536.3  146.69  8102.4  153.05
  8458.9  158.25  8640.1  152.73  9051.4  172.88  9470.5  156.28  9881.4  150.46
 10174.9  152.94 10554.5  168.67 10954.6  184.31 11500.1  193.62 11621.1  194.88
#Mann= 20 ,-1 , 0
  -887.2     .05       0   115.4     .05       0  1550.1     .12       0
  2536.4     .05       0  3953.7     .12       0  4213.3     .05       0
  4584.7     .12       0 4955.59     .07       0  5053.7     .12       0
  6806.9     .12       0  7536.3      .1       0  8102.4     .05       0
  8458.9     .12       0  9051.4     .05       0  9470.5     .05       0
  9881.4      .1       0 10174.9     .05       0 10554.5    .075       0
 10954.6    .075       0 11500.1    .075       0
#XS Ineff= 2 ,-1
  9069.1   10895  173.67    3200  4423.5  156.12
Permanent Ineff=
       F       F
Bank Sta=4955.59,5053.7
XS Rating Curve= 0 ,0
Exp/Cntr=0.3,0.1

Type RM Length L Ch R = 1 ,304350  ,343,343,343
BEGIN DESCRIPTION:
WFSJ Main 303.0
END DESCRIPTION:
XS GIS Cut Line= 6
       3814789.1     10120054.11      3812575.56      10121108.8
      3810947.59     10121209.99      3805960.97     10120835.36
      3804213.32     10121035.55      3802123.02     10121674.44
#Sta/Elev= 30
   -2656  201.79 -2499.5  174.92 -2289.1  179.52 -2081.7  165.25 -1606.5  153.97
  -968.5  157.67  -886.2  146.45    -699  146.87    -3.3  162.86   389.7  161.54
  1196.5  158.64  2974.3  152.81  3722.8  153.82  4102.8  140.48  4391.9   141.1
  4438.8  131.02  4503.2  141.25  4889.4  137.97  4998.6   124.1  5089.6   137.6
  5119.6  147.31  5934.3  148.89  6703.2  153.63  7124.4  158.97    7623  174.75
  8020.5  163.32  8746.8  147.56  9307.6  171.36 10175.3  194.42 10373.8  196.22
#Mann= 19 ,-1 , 0
   -2656     .05       0 -2081.7      .1       0  -968.5     .05       0
    -3.3     .05       0   389.7     .12       0  1196.5     .05       0
  2974.3     .05       0  3722.8     .05       0  4102.8      .1       0
  4889.4     .07       0  5089.6     .12       0  5934.3      .1       0
  6703.2     .05       0  7124.4     .12       0    7623     .05       0
  8020.5    .075       0  8746.8     .05       0  9307.6    .075       0
 10175.3    .075       0
#XS Ineff= 2 ,-1
   -2200    44.2  163.47  7663.5    9640  176.95
Permanent Ineff=
       F       F
Bank Sta=4889.4,5089.6
XS Rating Curve= 0 ,0
Exp/Cntr=0.3,0.1

Type RM Length L Ch R = 1 ,304007  ,207,207,207
BEGIN DESCRIPTION:
WFSJ Main 302.0
END DESCRIPTION:
XS GIS Cut Line= 5
      3814686.14     10119761.97      3812537.68     10120712.51
      3810949.14     10120868.76      3804868.41     10120491.15
       3801901.3     10121480.19
#Sta/Elev= 30
 -2619.3  191.77 -2183.7  168.72 -2129.1  159.41 -1631.3  152.51 -1152.6  147.65
    -231  145.92    87.9  148.85  1215.1  153.39  2336.7  152.55  2860.4  150.47
  3452.2  149.15  4142.5  139.41  4894.4  137.55  4919.3  137.46  4954.5   125.4
  4998.6  123.53  5080.1  137.33  5094.8   139.4  6098.3  154.89  6537.6  150.27
    6904  165.38  7167.1  170.74  7549.8  176.74    7817   175.6  8659.8  150.77
    8895   147.1  9186.5  161.48  9696.1  190.48 10029.3  192.31 10546.3  197.56
#Mann= 20 ,-1 , 0
 -2619.3      .1       0 -1631.3    .075       0 -1152.6     .05       0
    -231      .1       0    87.9     .05       0  1215.1    .075       0
  2336.7     .05       0  2860.4      .1       0  3452.2     .05       0
  4142.5    .075       0  4894.4     .07       0  5094.8    .075       0
  6098.3     .05       0    6904    .075       0  7167.1    .075       0
  7549.8    .075       0    7817     .05       0  8659.8      .1       0
  9186.5     .05       0 10029.3     .05       0
#XS Ineff= 2 ,-1
   -2065  1853.6   155.5  7808.9    9610  176.86
Permanent Ineff=
       F       F
Bank Sta=4919.3,5080.1
XS Rating Curve= 0 ,0
Exp/Cntr=0.3,0.1