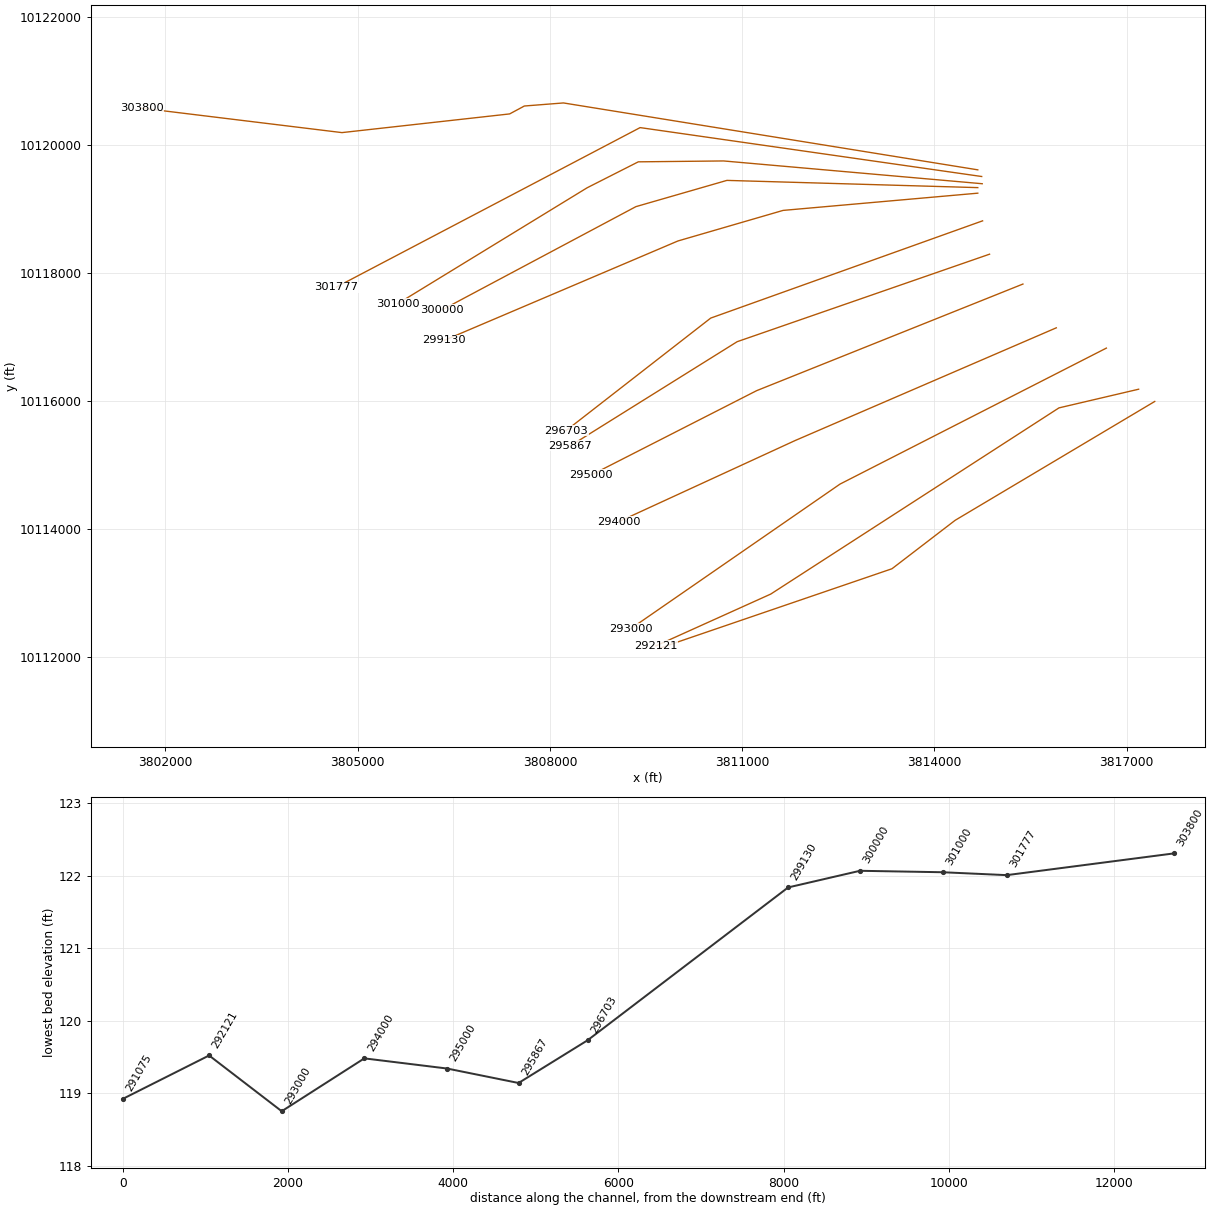
HEC-RAS study WFSJ Main.prj: WFSJ Main Base Level Engineering

--- WFSJ Main.g02 (geometry) --- (continued)

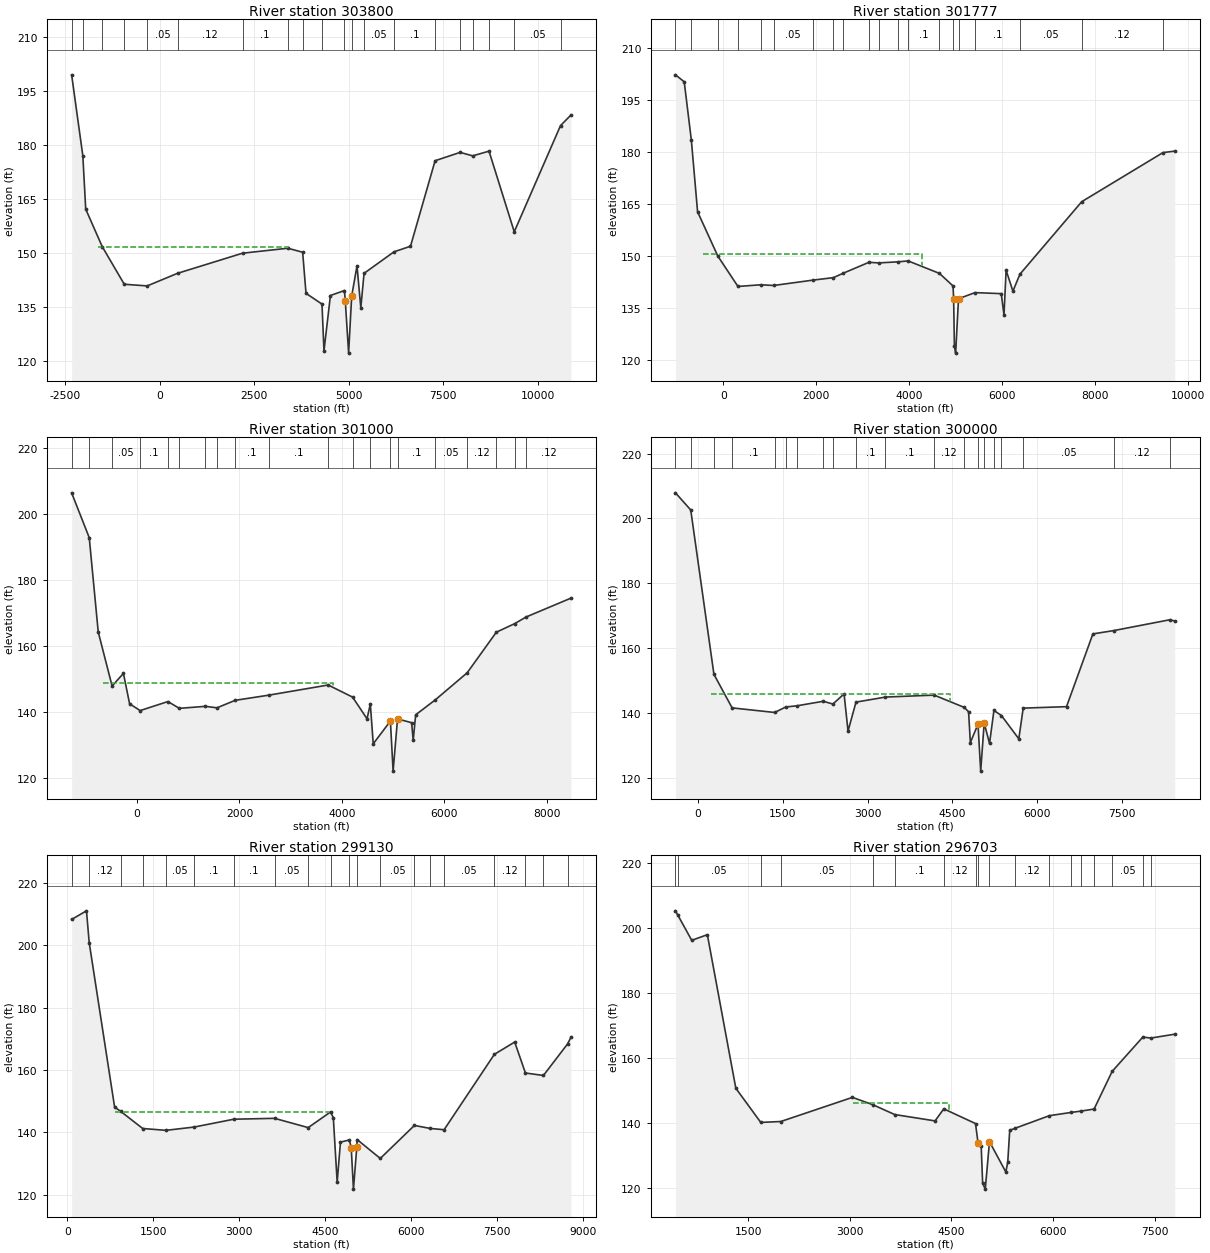
Type RM Length L Ch R = 1 ,303800  ,2023,2023,2023
BEGIN DESCRIPTION:
WFSJ Main 301.0
END DESCRIPTION:
XS GIS Cut Line= 6
      3814675.68     10119613.13      3808210.48     10120658.05
      3807600.68     10120610.31      3807370.64     10120486.61
      3804753.81     10120194.73      3801630.85     10120576.38
#Sta/Elev= 30
 -2325.1  199.49 -2028.9  177.04 -1952.5  162.24 -1516.9  151.86  -933.4  141.41
  -327.1  140.95   474.6  144.44  2192.9  150.02  3391.1   151.4  3783.4  150.29
  3872.1  138.89  4294.8  135.91    4347  122.91  4517.5  138.29  4888.4  139.67
  4910.3  136.87  4998.6  122.31  5079.9  138.14  5220.4  146.51    5321  134.88
  5407.2  144.44  6198.1   150.4  6634.7  151.95  7285.5  175.67  7946.5  177.98
  8279.6  177.02    8711  178.32  9378.2  155.96 10601.7  185.41 10876.1  188.33
#Mann= 20 ,-1 , 0
 -2325.1     .05       0 -2028.9      .1       0 -1516.9     .05       0
  -933.4      .1       0  -327.1     .05       0   474.6     .12       0
  2192.9      .1       0  3391.1     .05       0  3783.4      .1       0
  4294.8    .075       0  4888.4     .07       0  5079.9      .1       0
  5407.2     .05       0  6198.1      .1       0  7285.5     .12       0
  7946.5    .075       0  8279.6     .05       0    8711     .12       0
  9378.2     .05       0 10601.7     .12       0
#XS Ineff= 1 ,-1
   -1615  3393.9  151.73
Permanent Ineff=
       F
Bank Sta=4910.3,5079.9
XS Rating Curve= 0 ,0
Exp/Cntr=0.3,0.1

Type RM Length L Ch R = 1 ,301777  ,777,777,777
BEGIN DESCRIPTION:
WFSJ Main 300.0
END DESCRIPTION:
XS GIS Cut Line= 3
      3814736.46     10119508.96      3809406.59     10120272.85
      3804667.01     10117781.53
#Sta/Elev= 30
 -1027.7  202.16  -839.4  200.16  -685.5  183.29    -552  162.72  -116.2  149.95
   316.7  141.21   811.9   141.7  1082.7  141.49  1920.3  143.02  2368.7  143.75
  2580.5  145.02    3134  148.17  3343.8  147.99  3753.7   148.3  3977.5  148.56
  4650.7  144.97  4942.7  141.35  4955.6  137.53  4971.9  123.98  4998.6  122.01
  5060.1  137.68  5415.6  139.44  5979.8  139.14  6038.5  132.96  6083.7  145.89
  6230.6  139.86  6380.9  144.74  7710.2  165.62  9458.5  179.77  9711.1  180.18
#Mann= 20 ,-1 , 0
 -1027.7     .05       0  -685.5      .1       0  -116.2     .05       0
   316.7      .1       0   811.9      .1       0  1082.7     .05       0
  1920.3     .12       0  2368.7      .1       0  2580.5     .12       0
    3134     .12       0  3343.8     .05       0  3753.7    .075       0
  3977.5      .1       0  4650.7     .05       0  4942.7     .07       0
  5060.1      .1       0  5415.6      .1       0  6380.9     .05       0
  7710.2     .12       0  9458.5     .05       0
#XS Ineff= 1 ,-1
    -440  4264.4  150.49
Permanent Ineff=
       F
Bank Sta=4955.6,5060.1
XS Rating Curve= 0 ,0
Exp/Cntr=0.3,0.1

Type RM Length L Ch R = 1 ,301000  ,1000,1000,1000
BEGIN DESCRIPTION:
WFSJ Main 299.0
END DESCRIPTION:
XS GIS Cut Line= 5
       3814745.1     10119396.12      3810708.68     10119752.02
      3809378.19     10119738.13      3808580.87     10119333.42
      3805622.37     10117521.42
#Sta/Elev= 30
 -1276.8  206.36  -933.1  192.78  -757.5  164.21  -487.2  147.85  -265.6  151.64
  -145.2  142.45    60.7  140.39   602.6  143.13   825.6  141.07  1335.7  141.68
  1560.6  141.23  1916.4   143.5    2570  145.06  3730.7  148.14  4207.2  144.48
  4489.6  137.91    4554  142.37  4610.9  130.33  4945.8  137.22  4998.6  122.05
  5085.2  137.87  5359.9  136.72  5390.5  131.37  5439.3  139.11  5821.2  143.63
  6444.6  151.84    7014  164.14  7369.4  166.71  7595.5  168.75  8469.3  174.45
#Mann= 20 ,-1 , 0
 -1276.8     .05       0  -933.1      .1       0  -487.2     .05       0
    60.7      .1       0   602.6      .1       0   825.6     .12       0
  1335.7      .1       0  1560.6     .12       0  1916.4      .1       0
    2570      .1       0  3730.7     .05       0  4207.2     .05       0
    4554      .1       0  4945.8     .07       0  5085.2      .1       0
  5821.2     .05       0  6444.6     .12       0    7014     .05       0
  7369.4     .05       0  7595.5     .12       0
#XS Ineff= 1 ,-1
    -655  3816.2  148.62
Permanent Ineff=
       F
Bank Sta=4945.8,5085.2
XS Rating Curve= 0 ,0
Exp/Cntr=0.3,0.1

Type RM Length L Ch R = 1 ,300000  ,870,870,870
BEGIN DESCRIPTION:
WFSJ Main 298.0
END DESCRIPTION:
XS GIS Cut Line= 4
      3814675.67     10119335.35      3810760.76      10119448.2
      3809340.79     10119038.23      3806316.69     10117425.83
#Sta/Elev= 30
  -394.5  207.89  -124.6   202.6   285.1  151.92   606.4  141.57  1357.6  140.16
  1555.2  141.85  1752.9  142.22  2217.2  143.61  2386.2  142.76  2584.6  145.87
  2654.6  134.43  2795.4  143.35  3316.2  144.91  4176.9  145.51  4706.5  141.73
  4784.5  140.38  4815.7  130.88    4951  136.54  4998.6  122.07    5060  136.89
  5154.8  130.62  5232.4  140.78  5365.8   139.2    5672  132.03  5749.7   141.5
  6514.9  141.95  6981.1  164.39  7349.9  165.41  8347.2  168.77  8427.1  168.32
#Mann= 20 ,-1 , 0
  -394.5     .05       0  -124.6      .1       0   285.1     .05       0
   606.4      .1       0  1357.6     .05       0  1555.2      .1       0
  1752.9     .12       0  2217.2      .1       0  2386.2     .12       0
  2795.4      .1       0  3316.2      .1       0  4176.9     .12       0
  4706.5      .1       0    4951     .07       0    5060      .1       0
  5232.4     .05       0  5365.8      .1       0  5749.7     .05       0
  7349.9     .12       0  8347.2     .12       0
#XS Ineff= 1 ,-1
     235  4461.8  145.96
Permanent Ineff=
       F
Bank Sta=4951,5060
XS Rating Curve= 0 ,0
Exp/Cntr=0.3,0.1

Type RM Length L Ch R = 1 ,299130  ,2427,2427,2427
BEGIN DESCRIPTION:
WFSJ Main 297.0
END DESCRIPTION:
XS GIS Cut Line= 4
      3814675.64     10119248.54       3811637.5     10118979.45
      3809996.87     10118502.02      3806352.64     10116950.21
#Sta/Elev= 30
    76.7  208.32   335.9  211.08   383.9  200.83   827.4  148.14   935.3  146.75
  1318.4  141.28    1725  140.69  2218.6  141.75  2909.6  144.26  3620.4  144.54
  4208.3  141.57  4598.1  146.58  4647.1  144.75  4714.1   124.1  4771.9   136.9
    4927  137.62 4959.74  135.15  4998.6  121.84 5057.59  135.48  5062.6  137.73
  5467.2  131.68    6063  142.26  6338.8   141.3  6581.9  140.89  7459.6  165.06
  7814.6     169    8002  159.08  8316.2  158.28  8738.3  168.41  8796.3  170.49
#Mann= 20 ,-1 , 0
    76.7     .05       0   383.9     .12       0   935.3     .05       0
  1318.4      .1       0    1725     .05       0  2218.6      .1       0
  2909.6      .1       0  3620.4     .05       0  4208.3     .12       0
  4598.1      .1       0    4927     .07       0  5062.6      .1       0
  5467.2     .05       0    6063     .05       0  6338.8     .05       0
  6581.9     .05       0  7459.6     .12       0    8002     .12       0
  8316.2     .05       0  8738.3     .12       0
#XS Ineff= 1 ,-1
     830  4594.9  146.69
Permanent Ineff=
       F
Bank Sta=4959.74,5057.59
XS Rating Curve= 0 ,0
Exp/Cntr=0.3,0.1

Type RM Length L Ch R = 1 ,296703  ,836,836,836
BEGIN DESCRIPTION:
WFSJ Main 296.0
END DESCRIPTION:
XS GIS Cut Line= 3
      3814750.76      10118816.4      3810508.19     10117297.32
      3808252.07     10115540.15
#Sta/Elev= 30
   428.1  205.26   458.2  204.12   668.3  196.19   898.5  197.93  1318.6  150.73
  1686.5  140.23  1982.3  140.51  3039.2  147.93  3340.2  145.67  3663.1  142.65
  4258.1   140.7  4386.8   144.4 4854.69139.8827  4892.3  133.93  4938.8  132.84
  4960.2  121.51  4998.6  119.73    5061  134.32  5302.4  124.99  5330.6  128.09
  5359.5  137.81  5439.3  138.44  5944.1   142.3  6265.2   143.3    6414  143.72
  6604.2  144.34  6870.3   155.9  7323.2  166.46  7442.9  166.16  7794.1  167.35
#Mann= 18 ,-1 , 0
   428.1     .12       0   458.2     .05       0  1686.5      .1       0
  1982.3     .05       0  3340.2     .12       0  3663.1      .1       0
  4386.8     .12       0 4854.69      .1       0  4892.3     .07       0
    5061      .1       0  5439.3     .12       0  5944.1      .1       0
  6265.2     .12       0    6414      .1       0  6604.2     .12       0
  6870.3     .05       0  7323.2     .12       0  7442.9     .05       0
#XS Ineff= 2 ,-1
    1370  3039.2  147.93    3040  4462.8  146.17
Permanent Ineff=
       F       F
Bank Sta=4892.3,5061
XS Rating Curve= 0 ,0
Exp/Cntr=0.3,0.1

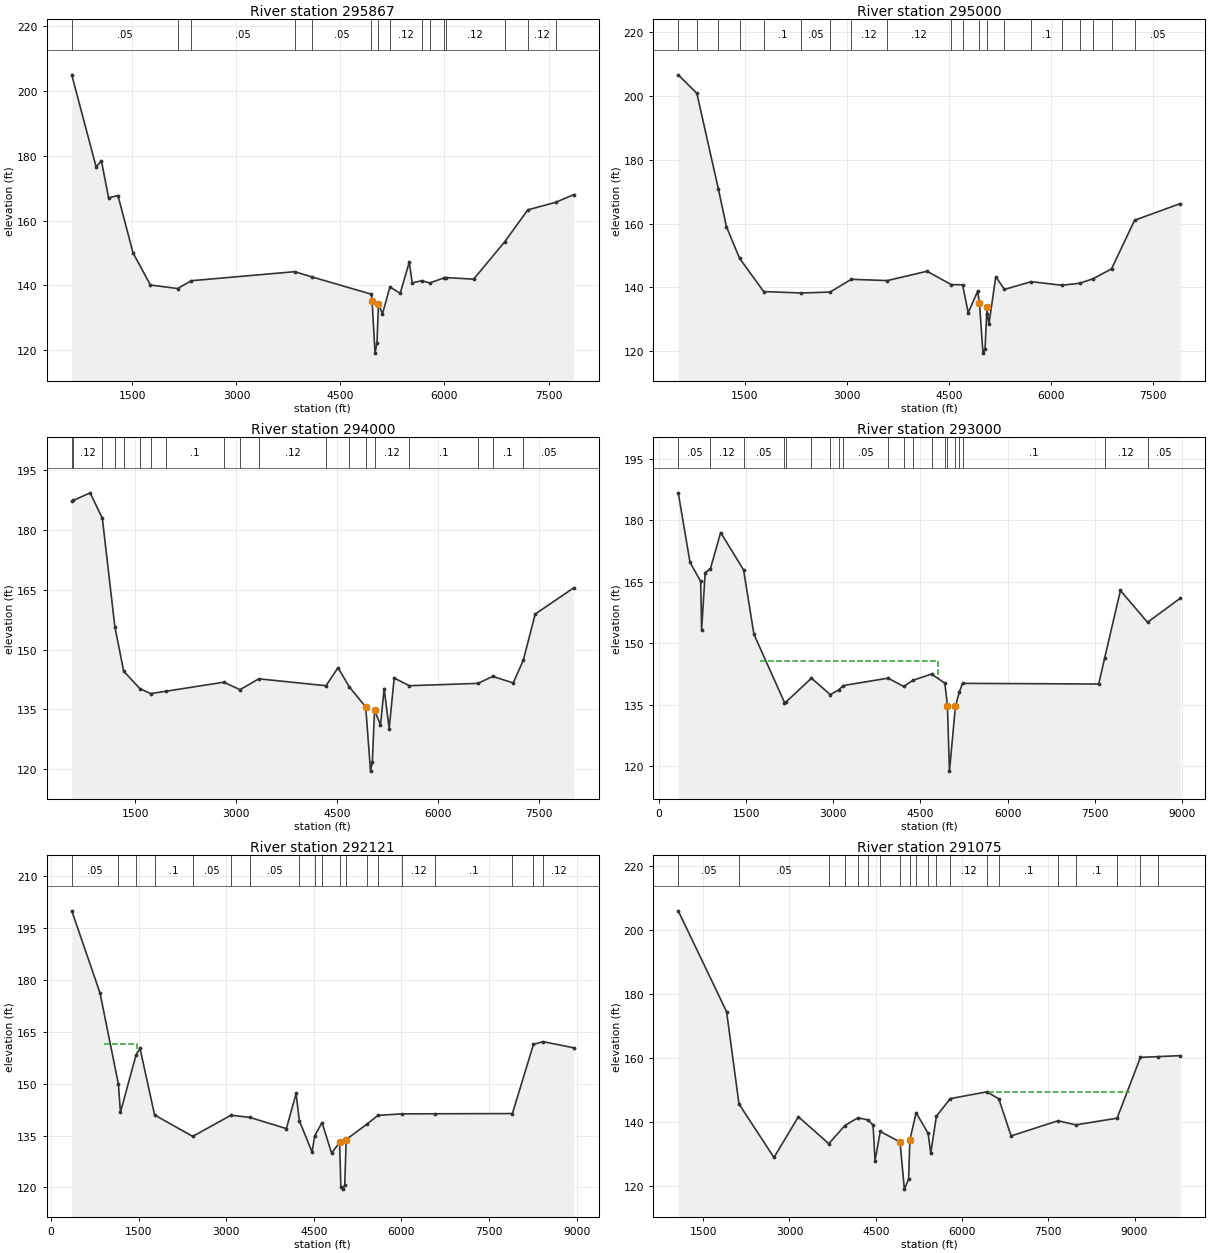
Type RM Length L Ch R = 1 ,295867  ,867,867,867
BEGIN DESCRIPTION:
WFSJ Main 295.0
END DESCRIPTION:
XS GIS Cut Line= 3
      3814859.31     10118295.58      3810920.51     10116928.39
      3808316.34     10115300.78
#Sta/Elev= 30
   625.2  204.88   976.1   176.5    1053  178.39    1156  166.99  1291.5  167.68
  1509.3     150  1759.4  140.12  2151.2  139.04  2349.8  141.45    3840  144.23
  4085.3  142.64  4947.5  137.29 4956.46  135.19  4998.6  119.14  5026.5  122.26
  5047.7  134.31  5105.5  131.21  5212.8  139.54  5361.4  137.57  5492.3  147.19
  5534.7  140.76  5673.9  141.47  5787.6  140.75  5997.4  142.37  6014.8  142.42
  6420.3  141.93  6867.1   153.4  7201.9  163.28  7605.7  165.62  7865.5  167.98
#Mann= 15 ,-1 , 0
   625.2     .05       0  2151.2      .1       0  2349.8     .05       0
    3840      .1       0  4085.3     .05       0  4947.5     .07       0
  5047.7     .05       0  5212.8     .12       0  5673.9      .1       0
  5787.6     .12       0  5997.4      .1       0  6014.8     .12       0
  6867.1     .05       0  7201.9     .12       0  7605.7     .05       0
#XS Ineff= 1 ,-1
  5492.3    6715  147.19
Permanent Ineff=
       F
Bank Sta=4956.46,5047.7
XS Rating Curve= 0 ,0
Exp/Cntr=0.3,0.1

Type RM Length L Ch R = 1 ,295000  ,1000,1000,1000
BEGIN DESCRIPTION:
WFSJ Main 294.0
END DESCRIPTION:
XS GIS Cut Line= 3
      3815380.13     10117828.99      3811223.65     10116163.09
      3808643.35     10114845.81
#Sta/Elev= 30
   522.1  206.65   795.6  200.85  1112.4  170.77  1229.5  159.05  1422.5   149.1
  1777.5  138.66    2332  138.21  2750.7  138.49  3064.8   142.5  3593.3   142.1
  4176.7  145.03  4530.4  140.85    4699  140.77  4781.2  132.04  4920.1  138.73
 4946.85  135.12  4998.6  119.34    5029  120.74  5058.2  133.88  5063.8  131.75
  5086.1  128.43    5186  143.32  5314.4  139.33  5707.9  141.76    6154  140.64
  6420.4  141.27  6617.5   142.7  6887.2  145.79  7225.6  161.03  7897.1  166.26
#Mann= 20 ,-1 , 0
   522.1     .05       0   795.6     .12       0  1112.4     .05       0
  1422.5     .12       0  1777.5      .1       0    2332     .05       0
  2750.7      .1       0  3064.8     .12       0  3593.3     .12       0
  4530.4     .05       0    4699      .1       0 4946.85     .07       0
  5063.8      .1       0  5314.4     .12       0  5707.9      .1       0
    6154      .1       0  6420.4     .05       0  6617.5      .1       0
  6887.2     .12       0  7225.6     .05       0
Bank Sta=4946.85,5058.2
XS Rating Curve= 0 ,0
Exp/Cntr=0.3,0.1

Type RM Length L Ch R = 1 ,294000  ,1000,1000,1000
BEGIN DESCRIPTION:
WFSJ Main 293.0
END DESCRIPTION:
XS GIS Cut Line= 3
      3815900.97      10117145.4      3811821.22     10115382.62
      3809075.86     10114118.05
#Sta/Elev= 30
   555.7  187.28   577.9  187.42   828.7  189.34  1010.5  182.95  1196.5  155.73
  1327.7  144.59  1568.2  140.19  1730.1  138.94  1962.1  139.55  2815.9   141.8
  3058.2  139.92  3336.7  142.65  4336.9  140.92  4515.6  145.46    4684  140.61
  4927.4  135.59  4998.6  119.48  5025.7  121.74  5058.4  134.77  5146.8  131.07
  5201.6  140.22    5276  130.12  5350.4  142.86    5575  140.92  6597.9  141.51
  6815.9  143.26  7121.1  141.62  7270.4   147.3  7447.9  158.91  8022.6  165.51
#Mann= 19 ,-1 , 0
   555.7      .1       0   577.9     .12       0  1010.5     .05       0
  1196.5    .075       0  1327.7      .1       0  1568.2     .05       0
  1730.1      .1       0  1962.1      .1       0  2815.9     .05       0
  3058.2      .1       0  3336.7     .12       0  4336.9     .05       0
    4684     .12       0  4927.4     .05       0  5058.4     .12       0
    5575      .1       0  6597.9     .12       0  6815.9      .1       0
  7270.4     .05       0
#XS Ineff= 1 ,-1
    1270  4515.6  145.46
Permanent Ineff=
       F
Bank Sta=4927.4,5058.4
XS Rating Curve= 0 ,0
Exp/Cntr=0.3,0.1

Type RM Length L Ch R = 1 ,293000  ,879,879,879
BEGIN DESCRIPTION:
WFSJ Main 292.0
END DESCRIPTION:
XS GIS Cut Line= 3
      3816682.26     10116828.58      3812525.91     10114704.16
      3809260.37     10112444.89
#Sta/Elev= 30
   332.2  186.64   534.6  169.71     719  165.01   734.5  153.27   795.6  167.16
   886.2  168.15  1062.2  176.96  1457.2   167.8  1634.2  152.16  2160.5  135.49
  2188.4  135.64    2625  141.44  2947.1  137.42  3094.6  138.57  3168.5  139.62
  3943.2  141.43  4212.6   139.4    4364  140.87  4690.1  142.43  4919.2  140.22
  4964.1  134.72  4998.6  118.75  5101.6  134.61  5167.1  137.99  5223.5  140.16
  7566.1     140  7670.1  146.39  7940.4  162.82  8406.9  155.06  8970.9  160.94
#Mann= 20 ,-1 , 0
   332.2     .05       0   886.2     .12       0  1457.2     .05       0
  2160.5      .1       0  2188.4     .05       0    2625      .1       0
  2947.1     .05       0  3094.6      .1       0  3168.5     .05       0
  3943.2     .12       0  4212.6     .05       0    4364     .12       0
  4690.1     .05       0  4919.2     .12       0  4964.1     .07       0
  5101.6     .12       0  5167.1      .1       0  5223.5      .1       0
  7670.1     .12       0  8406.9     .05       0
#XS Ineff= 1 ,-1
    1740  4799.7  145.55
Permanent Ineff=
       F
Bank Sta=4964.1,5101.6
XS Rating Curve= 0 ,0
Exp/Cntr=0.3,0.1

Type RM Length L Ch R = 1 ,292121  ,1046,1046,1046
BEGIN DESCRIPTION:
WFSJ Main 291.0
END DESCRIPTION:
XS GIS Cut Line= 4
      3817185.72     10116186.21      3815942.42     10115894.47
      3811444.61     10112986.02      3809652.22     10112176.34
#Sta/Elev= 30
   352.6  199.89   836.5  176.16  1151.3  149.85  1186.2  141.68  1452.6  158.22
  1521.4  160.17  1771.5  140.93    2424  134.75  3079.3  140.86  3400.8  140.24
  4028.7     137  4195.4  147.14  4250.3  139.29  4469.3  130.19  4511.9  134.86
  4639.4  138.74  4802.8  129.92  4940.7  133.02  4961.8  120.17  4998.6  119.52
  5028.4  120.75 5053.14  133.85  5405.1  138.24  5597.5  140.82  6015.2  141.26
  6582.2  141.28  7900.4  141.34  8260.4   161.3  8423.9  162.12  8952.7  160.32
#Mann= 19 ,-1 , 0
   352.6     .05       0  1151.3     .05       0  1452.6     .12       0
  1771.5      .1       0    2424     .05       0  3079.3      .1       0
  3400.8     .05       0  4250.3      .1       0  4511.9      .1       0
  4639.4     .12       0  4940.7     .07       0 5053.14      .1       0
  5405.1     .05       0  5597.5      .1       0  6015.2     .12       0
  6582.2      .1       0  7900.4     .12       0  8260.4     .05       0
  8423.9     .12       0
#XS Ineff= 2 ,-1
     905    1470  161.48    1615  4195.4  147.14
Permanent Ineff=
       F       F
Bank Sta=4940.7,5053.14
XS Rating Curve= 0 ,0
Exp/Cntr=0.3,0.1

Type RM Length L Ch R = 1 ,291075  ,2185,2185,2185
BEGIN DESCRIPTION:
WFSJ Main 290.0
END DESCRIPTION:
XS GIS Cut Line= 4
      3817437.47     10115995.25      3814322.86     10114138.75
      3813336.75     10113381.81      3809683.98     10112131.81
#Sta/Elev= 30
  1066.7  206.03  1907.6  174.45  2122.7   145.6    2731  128.82  3155.4  141.57
  3684.6  133.15  3964.1  138.82  4190.2  141.24  4366.8  140.59    4454  138.97
  4488.9  127.83  4579.7  136.98  4923.3  133.66  4998.6  118.92  5072.8  122.07
  5093.6  134.28  5202.9  142.82  5412.2  136.37  5457.1  130.14  5555.7  141.76
  5797.3  147.25  6435.4  149.38  6641.3  147.15  6854.3  135.57    7671  140.33
  7979.4  139.03  8696.8  141.12  9103.4  160.16  9415.2   160.4  9796.5   160.7
#Mann= 20 ,-1 , 0
  1066.7     .05       0  2122.7     .05       0  3684.6     .05       0
  3964.1      .1       0  4190.2     .05       0  4366.8      .1       0
  4579.7     .05       0  4923.3     .07       0  5093.6      .1       0
  5202.9     .12       0  5412.2      .1       0  5555.7     .05       0
  5797.3     .12       0  6435.4     .05       0  6641.3      .1       0
    7671     .12       0  7979.4      .1       0  8696.8     .12       0
  9103.4     .05       0  9415.2     .12       0
#XS Ineff= 1 ,-1
  6478.7    8915  149.39
Permanent Ineff=
       F
Bank Sta=4923.3,5093.6
XS Rating Curve= 0 ,0
Exp/Cntr=0.3,0.1