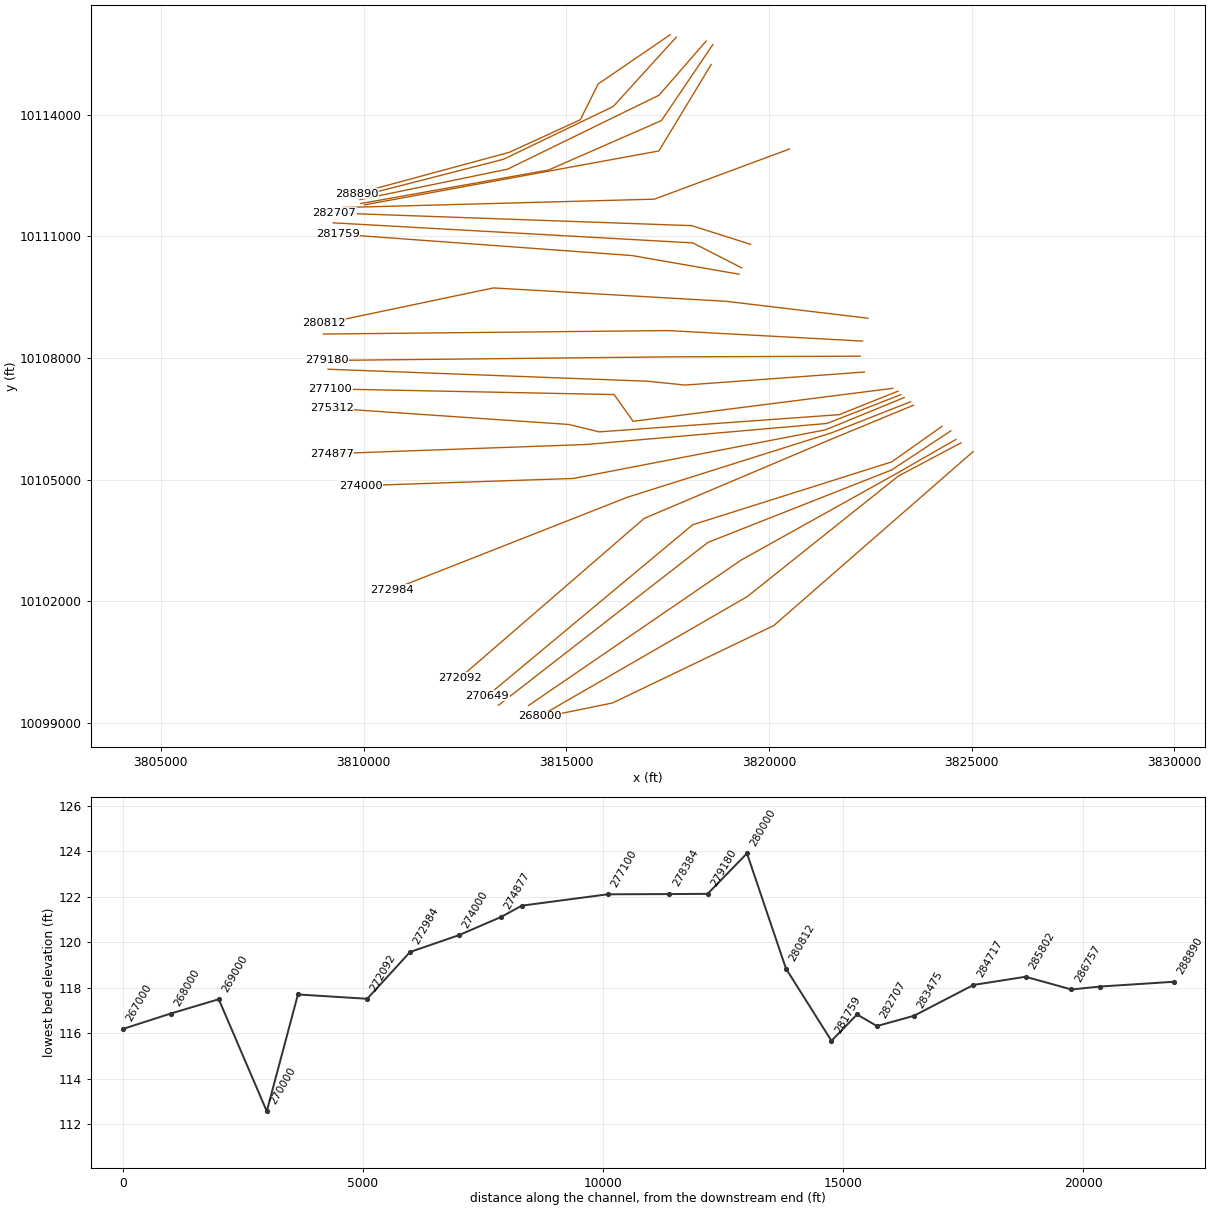
HEC-RAS study WFSJ Main.prj: WFSJ Main Base Level Engineering

--- WFSJ Main.g02 (geometry) --- (continued)

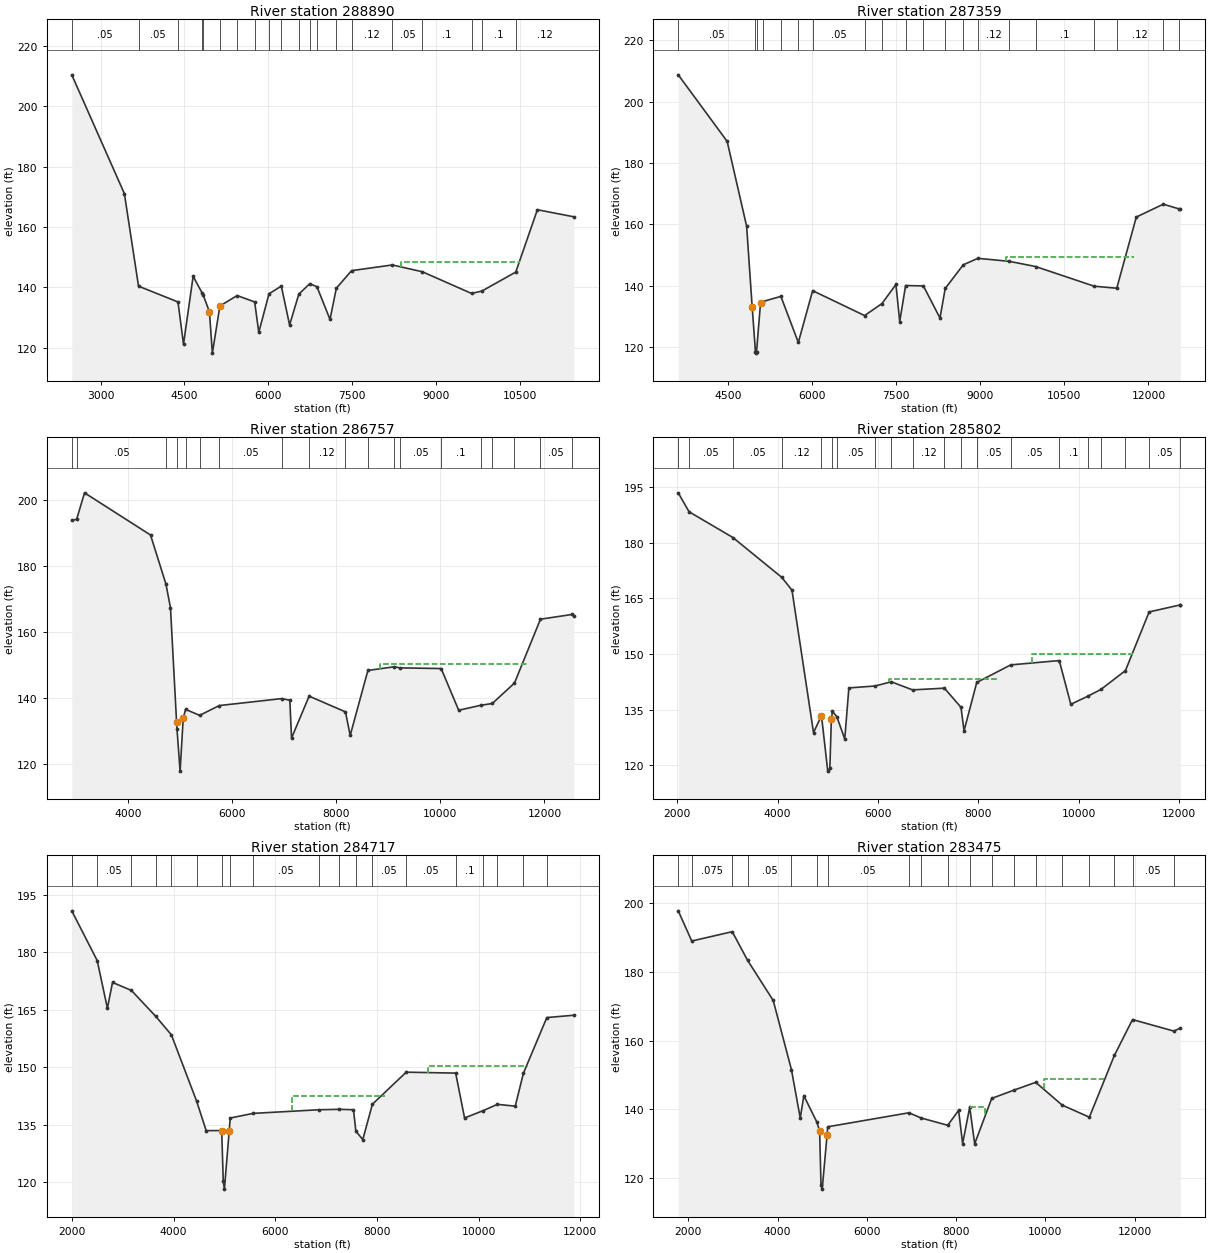
Type RM Length L Ch R = 1 ,288890  ,1531,1531,1531
BEGIN DESCRIPTION:
WFSJ Main 288.0
END DESCRIPTION:
XS GIS Cut Line= 5
      3817567.63     10115977.86      3815788.14     10114762.59
      3815348.96     10113879.71      3813600.17     10113077.26
      3809824.07     10112055.74
#Sta/Elev= 30
  2484.7  210.39  3425.3  171.06  3678.3  140.43  4383.8   135.2  4482.5  121.22
  4654.7   143.7    4820  138.01  4833.9  137.53  4945.9  131.95  4998.6  118.26
  5132.7  133.86  5441.7  137.32  5754.8  135.21  5828.3  125.14    6011   137.9
  6231.7  140.45  6379.1  127.58  6544.8  137.82  6739.6  141.23  6868.3  140.25
  7101.9  129.42  7214.8  139.72  7486.4  145.56  8216.3  147.45  8752.6   145.2
  9631.9  138.02  9816.4   138.8 10423.4   145.1 10809.8  165.73 11461.6  163.39
#Mann= 20 ,-1 , 0
  2484.7     .05       0  3678.3     .05       0  4383.8     .05       0
    4820      .1       0  4833.9     .07       0  5132.7      .1       0
  5441.7     .05       0  5754.8      .1       0    6011     .12       0
  6231.7     .12       0  6544.8     .12       0  6739.6     .05       0
  6868.3     .12       0  7214.8      .1       0  7486.4     .12       0
  8216.3     .05       0  8752.6      .1       0  9631.9     .05       0
  9816.4      .1       0 10423.4     .12       0
#XS Ineff= 1 ,-1
  8370.6   10500  148.59
Permanent Ineff=
       F
Bank Sta=4945.9,5132.7
XS Rating Curve= 0 ,0
Exp/Cntr=0.3,0.1

Type RM Length L Ch R = 1 ,287359  ,602,602,602
BEGIN DESCRIPTION:
WFSJ Main 287.0
END DESCRIPTION:
XS GIS Cut Line= 4
      3817715.23     10115917.12       3816161.4     10114207.04
      3813453.81      10112904.7      3809927.02     10111999.86
#Sta/Elev= 30
  3613.2  208.73  4486.1  187.04  4833.4  159.39    4932  133.11    4990  118.55
  4998.6  118.05    5010  118.55  5080.7  134.28  5118.5  134.84  5444.1  136.54
  5755.3  121.53  6011.1   138.4  6937.3  130.29    7247  134.19  7496.3  140.42
  7564.2  128.34    7669  140.07  7986.2  139.95  8282.5  129.48  8375.3  139.11
  8697.8  146.83  8957.8  148.94    9519  147.96  9986.7  146.27   11032  139.86
 11435.5  139.19 11784.4  162.39 12265.7  166.58   12545  165.05 12569.3  164.93
#Mann= 20 ,-1 , 0
  3613.2     .05       0    4990     .05       0    5010     .05       0
  5118.5      .1       0  5444.1     .12       0  5755.3      .1       0
  6011.1     .05       0  6937.3      .1       0    7247     .12       0
    7669     .12       0  7986.2     .12       0  8375.3      .1       0
  8697.8     .12       0  8957.8     .12       0    9519     .05       0
  9986.7      .1       0   11032      .1       0 11435.5     .12       0
 12265.7     .05       0   12545     .12       0
#XS Ineff= 1 ,-1
    9461   11750  149.23
Permanent Ineff=
       F
Bank Sta=4932,5080.7
XS Rating Curve= 0 ,0
Exp/Cntr=0.3,0.1

Type RM Length L Ch R = 1 ,286757  ,955,955,955
BEGIN DESCRIPTION:
WFSJ Main 286.0
END DESCRIPTION:
XS GIS Cut Line= 4
      3818453.07     10115821.62      3817289.87     10114484.82
      3813554.94     10112660.89      3809913.14     10111909.59
#Sta/Elev= 30
  2917.3  193.67  3011.7  194.06  3162.3  202.03  4430.8  189.28  4726.9  174.43
    4814  167.28 4930.76  132.85  4939.6  130.53  4998.6  117.92  5058.8  133.88
  5103.3   136.6  5373.6  134.77  5751.3  137.74  6951.3  139.84  7107.1  139.35
  7139.9  127.91  7477.9  140.58  8176.1  135.83  8266.9  128.71  8607.2  148.35
  9113.9  149.46  9224.3  149.13 10015.1  148.92 10351.7  136.32 10779.2  137.83
 10997.2  138.36 11423.2  144.53   11923  163.84 12527.3  165.26 12564.3  164.79
#Mann= 19 ,-1 , 0
  2917.3    .075       0  3011.7     .05       0  4726.9     .12       0
  4939.6     .07       0  5103.3      .1       0  5373.6     .05       0
  5751.3     .05       0  6951.3      .1       0  7477.9     .12       0
  8176.1      .1       0  8607.2     .05       0  9113.9     .12       0
  9224.3     .05       0 10015.1      .1       0 10779.2     .12       0
 10997.2      .1       0 11423.2     .12       0   11923     .05       0
 12527.3     .12       0
#XS Ineff= 1 ,-1
  8845.8   11690  150.26
Permanent Ineff=
       F
Bank Sta=4930.76,5058.8
XS Rating Curve= 0 ,0
Exp/Cntr=0.3,0.1

Type RM Length L Ch R = 1 ,285802  ,1085,1085,1085
BEGIN DESCRIPTION:
WFSJ Main 285.0
END DESCRIPTION:
XS GIS Cut Line= 4
      3818617.98     10115734.79      3817350.64     10113859.82
      3814562.83     10112638.85        3809934.     10111812.37
#Sta/Elev= 30
  2018.1  193.46  2233.8  188.36  3108.7  181.41  4083.3  170.67  4285.5  167.22
  4714.9  128.86  4873.8  133.44  4998.6  118.48  5040.7  119.25  5070.3  132.46
  5092.9   134.6    5180  133.13  5337.6  127.13  5419.6   140.9  5944.5  141.42
  6264.6  142.55  6688.3  140.37    7324  140.83  7654.3  135.68  7715.7  129.36
  7968.6  142.37  8645.5   147.1  9613.5  148.27  9843.8  136.49 10182.4  138.66
 10444.5  140.49 10933.1  145.57 11405.3  161.37 12016.8  163.24 12026.7  163.21
#Mann= 20 ,-1 , 0
  2018.1     .05       0  2233.8     .05       0  3108.7     .05       0
  4083.3     .12       0  4873.8     .07       0  5092.9      .1       0
    5180     .05       0  5944.5     .12       0  6264.6     .12       0
  6688.3     .12       0    7324      .1       0  7654.3      .1       0
  7968.6     .05       0  8645.5     .05       0  9613.5      .1       0
 10182.4     .12       0 10444.5      .1       0 10933.1     .12       0
 11405.3     .05       0 12016.8     .12       0
#XS Ineff= 2 ,-1
  6210.5    8400  143.18  9076.9   11080  150.02
Permanent Ineff=
       F       F
Bank Sta=4873.8,5070.3
XS Rating Curve= 0 ,0
Exp/Cntr=0.3,0.1

Type RM Length L Ch R = 1 ,284717  ,1242,1242,1242
BEGIN DESCRIPTION:
WFSJ Main 284.0
END DESCRIPTION:
XS GIS Cut Line= 3
      3818577.22     10115242.96      3817286.49     10113110.18
      3810024.66     10111779.37
#Sta/Elev= 30
  1996.6  190.84  2497.1  177.84  2697.3  165.39  2798.2  172.13  3169.1  170.05
  3649.4  163.25  3955.9  158.44  4450.4  141.18  4640.6  133.41  4945.6  133.42
  4976.1  120.34  4998.6  118.12 5093.46  133.31  5113.3   136.7  5563.5  137.91
  6858.4  138.86  7256.8  138.97  7538.1  138.87  7584.8  133.26  7721.1  131.07
  7909.7   140.3  8574.9  148.68  9547.8  148.44  9722.9  136.71 10094.1  138.66
 10367.9  140.27 10720.2   139.8 10879.9  148.39 11340.7  162.95 11872.3  163.56
#Mann= 19 ,-1 , 0
  1996.6     .05       0  2497.1     .05       0  3169.1     .12       0
  3649.4     .05       0  3955.9     .05       0  4450.4     .12       0
  4945.6     .07       0  5113.3     .05       0  5563.5     .05       0
  6858.4     .12       0  7256.8      .1       0  7584.8      .1       0
  7909.7     .05       0  8574.9     .05       0  9547.8      .1       0
 10094.1     .12       0 10367.9      .1       0 10879.9     .12       0
 11340.7     .05       0
#XS Ineff= 2 ,-1
  6338.2    8160  142.53  9012.3   10980  150.22
Permanent Ineff=
       F       F
Bank Sta=4945.6,5093.46
XS Rating Curve= 0 ,0
Exp/Cntr=0.3,0.1

Type RM Length L Ch R = 1 ,283475  ,768,768,768
BEGIN DESCRIPTION:
WFSJ Main 283.0
END DESCRIPTION:
XS GIS Cut Line= 3
      3820506.45     10113157.41      3817175.29     10111920.43
      3809482.47     10111714.28
#Sta/Elev= 30
  1773.4  197.76  2076.2  188.97  2983.5  191.69  3326.7  183.36  3901.5  171.67
  4309.2  151.57  4507.2  137.44  4587.6  143.96  4880.6  136.24  4941.3  133.68
  4972.1  117.86  4998.6  116.76  5107.5  132.39  5121.4   134.9    6942  138.98
  7219.3  137.45  7810.9  135.35  8055.2  139.66  8145.3  130.03  8303.8   140.6
  8415.4  129.96  8796.8  143.16  9289.8  145.55  9782.8  147.84 10374.4  141.22
 10984.8   137.7 11546.6  155.73 11951.9  166.11 12876.6  162.76 13022.4  163.63
#Mann= 19 ,-1 , 0
  1773.4     .12       0  2076.2    .075       0  2983.5    .075       0
  3326.7     .05       0  4309.2     .12       0  4880.6     .07       0
  5121.4     .05       0    6942     .12       0  7219.3     .05       0
  7810.9     .12       0  8303.8      .1       0  8796.8     .12       0
  9289.8     .05       0  9782.8     .12       0 10374.4      .1       0
 10984.8     .05       0 11546.6     .12       0 11951.9     .05       0
 12876.6    .075       0
#XS Ineff= 3 ,-1
  8303.8    8650   140.6  9965.1   11370  148.69    4400  4587.6  143.96
Permanent Ineff=
       F       F       F
Bank Sta=4941.3,5107.5
XS Rating Curve= 0 ,0
Exp/Cntr=0.3,0.1

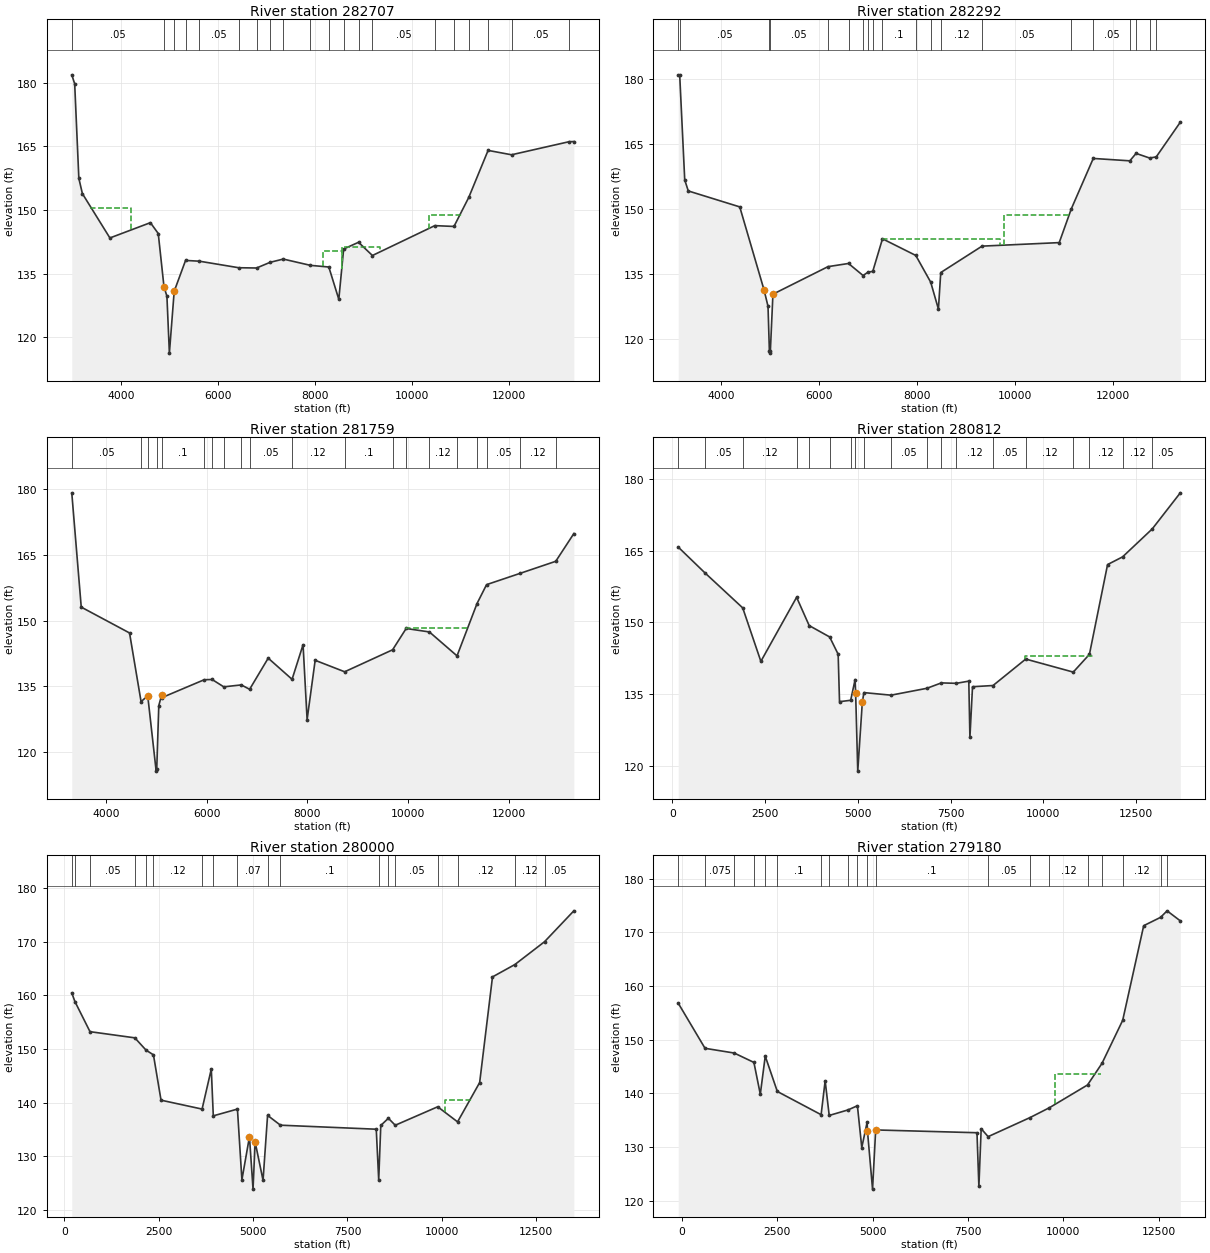
Type RM Length L Ch R = 1 ,282707  ,415,415,415
BEGIN DESCRIPTION:
WFSJ Main 282.0
END DESCRIPTION:
XS GIS Cut Line= 3
      3819546.82     10110806.86      3818097.16     10111266.93
      3809277.71     10111579.43
#Sta/Elev= 30
  2987.1  181.82  3047.2  179.72  3132.9  157.44  3206.3  153.85  3772.8  143.42
  4607.4  147.02  4769.3  144.46  4887.6   131.9  4947.6  129.72  4998.6  116.31
  5097.7  130.86  5331.9  138.13  5616.8  137.95  6428.4  136.41  6795.1  136.35
  7075.2  137.69  7345.4  138.45  7905.6  136.97  8283.9  136.58  8489.8  128.98
  8589.3  140.82    8896   142.4  9182.5  139.29 10467.6  146.32   10863  146.13
 11167.1  152.95 11565.9  164.03 12049.3     163 13235.6  166.08   13333  166.11
#Mann= 20 ,-1 , 0
  2987.1     .05       0  4887.6     .03       0  5097.7     .05       0
  5331.9     .12       0  5616.8     .05       0  6428.4      .1       0
  6795.1     .05       0  7075.2     .12       0  7345.4      .1       0
  7905.6     .12       0  8283.9      .1       0  8589.3     .05       0
    8896     .12       0  9182.5     .05       0 10467.6      .1       0
   10863    .075       0 11167.1     .05       0 11565.9     .12       0
 12049.3     .05       0 13235.6     .05       0
#XS Ineff= 4 ,-1
    3370  4213.5  150.42  8159.7  8549.8  140.26  8549.9    9338   141.4
   10341   11050  148.94
Permanent Ineff=
       F       F       F       F
Bank Sta=4887.6,5097.7
XS Rating Curve= 0 ,0
Exp/Cntr=0.3,0.1

Type RM Length L Ch R = 1 ,282292  ,533,533,533
BEGIN DESCRIPTION:
WFSJ Main 281.0
END DESCRIPTION:
XS GIS Cut Line= 3
      3819329.83     10110225.25      3818123.21     10110841.59
      3809252.22     10111336.35
#Sta/Elev= 30
  3131.1  180.81  3160.8  180.86  3263.6  156.67  3335.9  154.14  4385.7  150.47
    4882  131.33  4962.1  127.59    4990  117.32  4998.6  116.82    5010  117.32
  5062.3  130.38  6185.4  136.72  6603.6  137.45  6900.7  134.68  6999.7  135.44
  7098.7  135.64  7296.8  143.13  7975.6   139.3    8280  133.15  8437.5  126.95
  8485.1  135.36  9327.3  141.44 10901.3  142.25 11147.6  150.02 11595.5  161.62
 12341.7  161.07 12468.7  162.78 12743.2  161.72 12879.3  161.97 13370.8  169.96
#Mann= 20 ,-1 , 0
  3131.1      .1       0  3160.8     .05       0    4990     .05       0
    5010     .05       0  6185.4     .05       0  6603.6      .1       0
  6900.7     .05       0  6999.7      .1       0  7098.7     .05       0
  7296.8      .1       0  7975.6     .12       0    8280     .05       0
  8485.1     .12       0  9327.3     .05       0 11147.6     .12       0
 11595.5     .05       0 12341.7     .12       0 12468.7     .05       0
 12743.2     .12       0 12879.3     .05       0
#XS Ineff= 2 ,-1
  7295.7    9687  143.14  9779.6   11125  148.52
Permanent Ineff=
       F       F
Bank Sta=4882,5062.3
XS Rating Curve= 0 ,0
Exp/Cntr=0.3,0.1

Type RM Length L Ch R = 1 ,281759  ,947,947,947
BEGIN DESCRIPTION:
WFSJ Main 280.0
END DESCRIPTION:
XS GIS Cut Line= 3
        3819263.      10110069.3      3816624.07     10110529.38
      3809358.47     10111058.89
#Sta/Elev= 30
  3323.6  179.19  3511.5   153.1    4470   147.2  4698.8  131.52  4831.1  132.86
  4998.6  115.66    5010  116.16  5050.5   130.6  5104.9  132.95    5110  132.43
  5951.2  136.52  6108.3  136.58  6339.8   134.9  6687.9  135.34  6853.1  134.34
  7221.8  141.45  7695.5  136.62  7913.6  144.52  7993.8  127.42  8153.7  140.96
  8739.2  138.34  9690.7  143.36  9959.5  148.22 10420.9  147.43 10969.1  141.97
 11365.9  153.92 11555.3  158.23 12226.5  160.83 12928.2  163.56 13287.2  169.89
#Mann= 20 ,-1 , 0
  3323.6     .05       0  4698.8      .1       0  4831.1     .05       0
    5010     .05       0    5110      .1       0  5951.2      .1       0
  6108.3     .05       0  6339.8     .05       0  6687.9      .1       0
  6853.1     .05       0  7695.5     .12       0  8739.2      .1       0
  9690.7     .05       0  9959.5     .12       0 10420.9     .12       0
 10969.1     .05       0 11365.9     .12       0 11555.3     .05       0
 12226.5     .12       0 12928.2     .05       0
#XS Ineff= 3 ,-1
  7221.8  7913.5  141.45  7913.6    9885  144.52    9959   11196  148.23
Permanent Ineff=
       F       F       F
Bank Sta=4831.1,5104.9
XS Rating Curve= 0 ,0
Exp/Cntr=0.3,0.1

Type RM Length L Ch R = 1 ,280812  ,812,812,812
BEGIN DESCRIPTION:
Mapping XS e11f3f2d
END DESCRIPTION:
XS GIS Cut Line= 4
      3822440.03     10108984.24      3818941.78      10109400.9
      3813203.93     10109730.76      3809028.58     10108854.03
#Sta/Elev= 30
   158.5  165.74     871   160.4  1897.1  153.01  2386.3  141.82    3350  155.23
    3689  149.31  4240.5  146.93  4470.1  143.31  4506.8  133.38  4807.6  133.67
  4927.5  138.02 4941.43135.2123  4998.6  118.84 5121.68133.2735  5164.1  135.28
    5895  134.74    6863  136.18    7253  137.31  7655.3  137.22  7992.5  137.68
  8022.6  125.88  8092.7  136.51  8645.7  136.76  9527.7   142.3 10809.1  139.57
 11244.9  143.29 11733.9  162.08 12138.4  163.69   12938  169.54 13695.2   177.1
#Mann= 19 ,-1 , 0
   158.5     .12       0     871     .05       0  1897.1     .12       0
    3350    .075       0    3689     .12       0  4240.5     .05       0
  4807.6      .1       0  4927.5     .07       0  5164.1      .1       0
    5895     .05       0    6863     .05       0    7253      .1       0
  7655.3     .12       0  8645.7     .05       0  9527.7     .12       0
 10809.1     .12       0 11244.9     .12       0 12138.4     .12       0
   12938     .05       0
#XS Ineff= 1 ,-1
  9516.8   11345  143.03
Permanent Ineff=
       F
Bank Sta=4941.43,5121.68
XS Rating Curve= 0 ,0
Exp/Cntr=0.3,0.1

Type RM Length L Ch R = 1 ,280000  ,820,820,820
BEGIN DESCRIPTION:
WFSJ Main 279.0
END DESCRIPTION:
XS GIS Cut Line= 3
      3822309.81       10108420.      3817511.87     10108678.52
        3809012.     10108593.62
#Sta/Elev= 30
   195.1  160.46     279  158.84   678.3  153.24  1866.4  152.09  2163.4   149.8
  2359.6  148.92  2560.5  140.48  3648.5  138.82  3892.4  146.27  3945.6  137.56
  4585.6  138.82  4703.6  125.64  4903.9  133.67  4998.6  123.91    5054  132.71
    5264  125.55    5384  137.65  5724.9  135.82  8264.2  135.07  8329.1  125.63
  8384.2  135.77  8585.1  137.11  8767.3  135.81  9892.4  139.25   10419  136.44
 11004.3  143.76 11344.3  163.44 11938.5  165.75 12722.7  169.99 13500.3  175.75
#Mann= 18 ,-1 , 0
   195.1     .05       0     279     .12       0   678.3     .05       0
  1866.4      .1       0  2163.4    .075       0  2359.6     .12       0
  3648.5    .075       0  3945.6     .12       0  4585.6     .07       0
    5384     .12       0  5724.9      .1       0  8329.1     .05       0
  8585.1     .12       0  8767.3     .05       0  9892.4     .12       0
   10419     .12       0 11938.5     .12       0 12722.7     .05       0
#XS Ineff= 2 ,-1
    2365  3892.4  146.27 10074.3   10840  140.52
Permanent Ineff=
       F       F
Bank Sta=4903.9,5054
XS Rating Curve= 0 ,0
Exp/Cntr=0.3,0.1

Type RM Length L Ch R = 1 ,279180  ,796,796,796
BEGIN DESCRIPTION:
WFSJ Main 278.0
END DESCRIPTION:
XS GIS Cut Line= 3
      3822249.09     10108046.74      3817561.84     10108030.57
      3809087.99     10107941.63
#Sta/Elev= 30
     -95  156.78   607.5  148.37  1372.4  147.49  1888.9  145.74  2056.3  139.81
  2185.8  146.91  2502.3  140.33  3650.5     136  3756.3  142.31  3862.8  135.86
  4356.1  136.89  4601.9  137.67  4716.3  129.88  4856.3  134.59  4866.3  132.91
  4998.6  122.13 5080.74  133.16  7736.4  132.64  7786.4  122.63  7846.4  133.39
  8028.9  131.91  9125.7  135.46  9632.5  137.29 10634.3  141.54 11012.9  145.56
 11555.8  153.58 12106.7  171.22 12549.9  172.78 12719.8  173.99 13066.6  172.12
#Mann= 20 ,-1 , 0
     -95     .05       0   607.5    .075       0  1372.4    .075       0
  1888.9    .075       0  2185.8     .12       0  2502.3      .1       0
  3650.5     .05       0  3862.8     .12       0  4356.1     .05       0
  4601.9     .12       0  4856.3     .07       0 5080.74      .1       0
  8028.9     .05       0  9125.7      .1       0  9632.5     .12       0
 10634.3      .1       0 11012.9     .12       0 11555.8     .12       0
 12549.9     .05       0 12719.8     .12       0
#XS Ineff= 3 ,-1
    1485  2185.8  146.91    2186  3756.3  142.31  9783.2   10980  143.56
Permanent Ineff=
       F       F       F
Bank Sta=4866.3,5080.74
XS Rating Curve= 0 ,0
Exp/Cntr=0.3,0.1

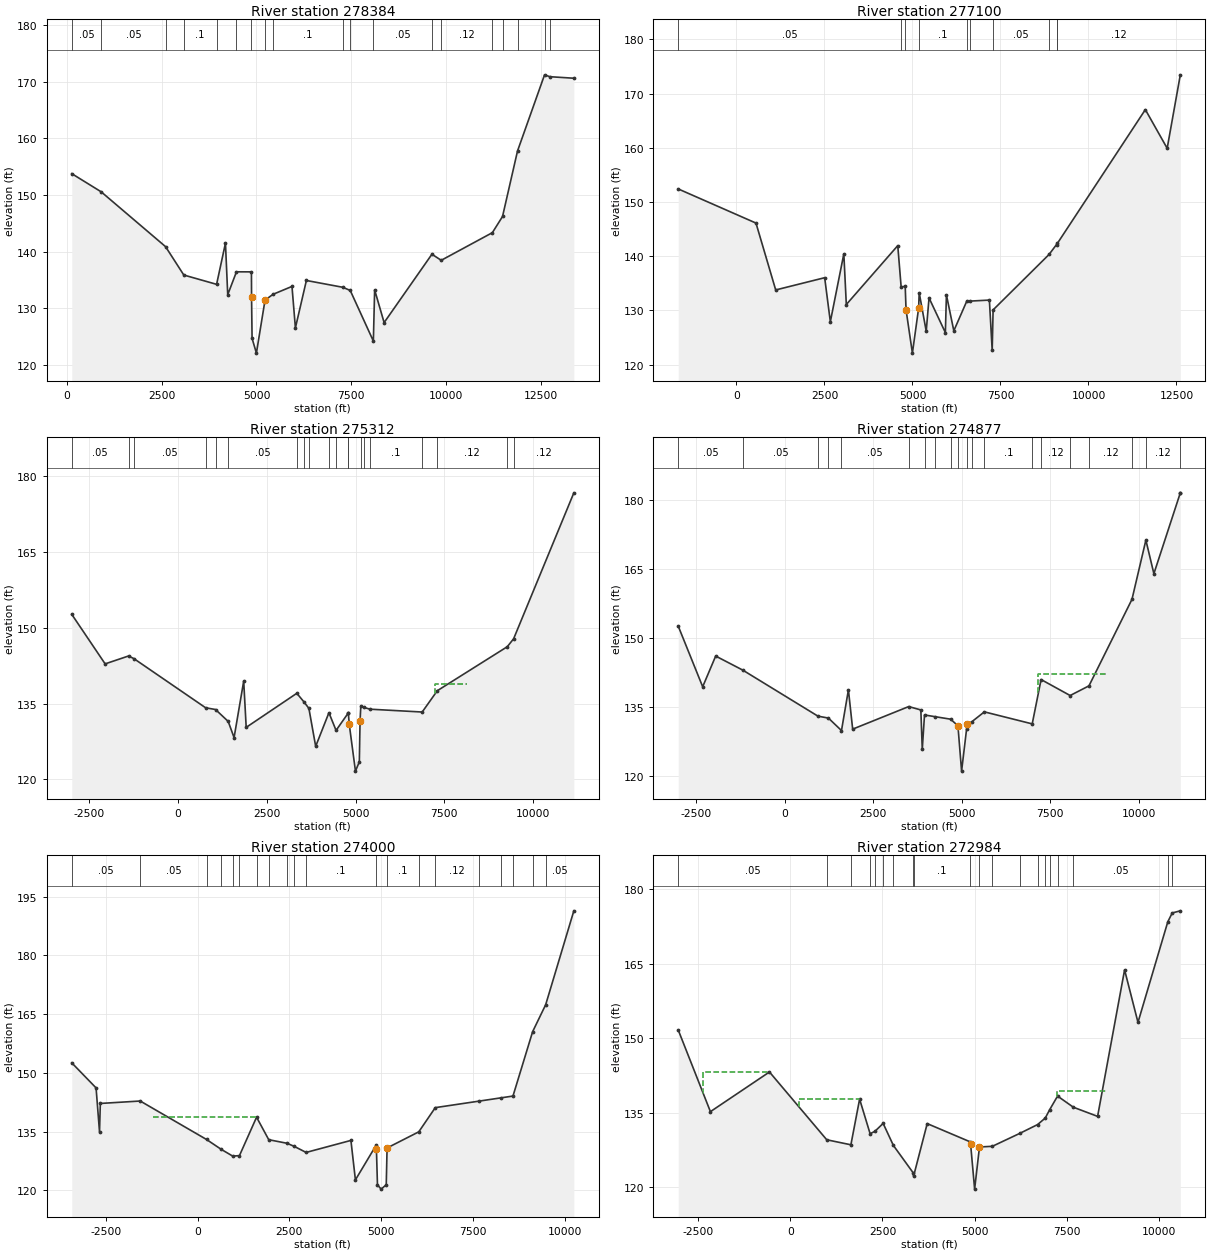
Type RM Length L Ch R = 1 ,278384  ,1284,1284,1284
BEGIN DESCRIPTION:
WFSJ Main 277.0
END DESCRIPTION:
XS GIS Cut Line= 4
      3822353.26     10107656.11      3817934.84     10107334.93
      3816988.66     10107430.42      3809124.06     10107725.56
#Sta/Elev= 30
   125.5  153.79   900.6  150.59  2600.7  140.91  3082.7   135.9    3948  134.26
  4181.6  141.53  4241.7  132.43  4472.1  136.47  4867.4  136.46 4870.68  132.01
  4884.2  124.73  4998.6  122.12    5226  131.47  5438.3   132.5  5937.7  133.89
  6027.7  126.57  6317.9  134.94  7277.4  133.74  7474.9  133.18  8085.3  124.25
  8119.2  133.28  8369.4  127.51  9630.9  139.57  9876.5   138.5 11226.5  143.38
 11494.5  146.23   11890  157.79 12603.6  171.23   12742   170.9 13376.7  170.63
#Mann= 19 ,-1 , 0
   125.5     .05       0   900.6     .05       0  2600.7     .12       0
  3082.7      .1       0    3948     .05       0  4472.1     .12       0
  4867.4     .07       0    5226     .12       0  5438.3      .1       0
  7277.4     .05       0  7474.9      .1       0  8085.3     .05       0
  9630.9     .12       0  9876.5     .12       0 11226.5      .1       0
 11494.5     .12       0   11890     .12       0 12603.6     .05       0
   12742     .12       0
#XS Ineff= 1 ,-1
 2387.99  4181.6  141.53
Permanent Ineff=
       F
Bank Sta=4870.68,5226
XS Rating Curve= 0 ,0
Exp/Cntr=0.3,0.1

Type RM Length L Ch R = 1 ,277100  ,1788,1788,1788
BEGIN DESCRIPTION:
WFSJ Main 276.0
END DESCRIPTION:
XS GIS Cut Line= 4
      3823054.64      10107254.2      3816650.11     10106440.83
      3816181.36     10107100.56      3809184.81     10107239.45
#Sta/Elev= 30
 -1653.7  152.41   554.8  146.11  1115.2  133.77  2506.2  136.03  2667.5   127.9
  3050.6  140.43  3121.1  131.08  4582.8  141.95  4678.4  134.35  4794.5  134.41
  4817.9  130.12  4998.6  122.11  5175.5  130.41  5191.8  133.25  5391.4  126.15
    5471   132.3  5935.1   125.9  5965.1  132.86  6175.2  126.23  6541.7  131.68
    6631  131.71  7185.4   131.9  7265.4  122.61  7291.4  130.09  8881.1  140.32
    9093  142.15  9117.1  142.36 11616.3  167.05 12236.4  159.91 12609.5  173.47
#Mann= 10 ,-1 , 0
 -1653.7     .05       0  4678.4      .1       0  4794.5     .07       0
  5191.8      .1       0  6541.7     .05       0    6631      .1       0
  7291.4     .05       0  8881.1     .12       0    9093      .1       0
  9117.1     .12       0
#XS Ineff= 1 ,-1
     680  4582.8  141.95
Permanent Ineff=
       F
Bank Sta=4817.9,5175.5
XS Rating Curve= 0 ,0
Exp/Cntr=0.3,0.1

Type RM Length L Ch R = 1 ,275312  ,435,435,435
BEGIN DESCRIPTION:
WFSJ Main 275.0
END DESCRIPTION:
XS GIS Cut Line= 5
      3823184.87     10107184.77      3821735.72     10106604.41
      3815816.78     10106180.42      3815061.57     10106362.71
      3809221.25      10106761.9
#Sta/Elev= 30
   -2983  152.67 -2044.4  142.86 -1386.5  144.42 -1234.5   143.9   783.6  134.16
  1061.1  133.82  1417.9  131.46  1583.6  128.25  1854.3  139.44  1924.5  130.28
  3348.3  137.03  3545.6  135.36  3688.5  134.04  3879.5  126.52    4252  133.18
  4453.2  129.68  4796.6  133.13  4799.1  133.09 4823.73   130.9  4998.6  121.61
  5107.7  123.46    5128   131.5  5148.9  134.48  5239.2  134.22  5411.4  133.88
  6876.3  133.32  7300.9  137.54  9269.9  146.26  9448.5  147.83   11143  176.75
#Mann= 20 ,-1 , 0
   -2983     .05       0 -1386.5    .075       0 -1234.5     .05       0
   783.6     .12       0  1061.1     .05       0  1417.9     .05       0
  3348.3      .1       0  3545.6     .05       0  3688.5      .1       0
    4252     .12       0  4453.2      .1       0  4796.6      .1       0
  4799.1     .07       0  5148.9      .1       0  5239.2     .05       0
  5411.4      .1       0  6876.3     .05       0  7300.9     .12       0
  9269.9      .1       0  9448.5     .12       0
#XS Ineff= 2 ,-1
    -455  1854.3  139.44  7237.3    8125  138.79
Permanent Ineff=
       F       F
Bank Sta=4823.73,5128
XS Rating Curve= 0 ,0
Exp/Cntr=0.3,0.1

Type RM Length L Ch R = 1 ,274877  ,877,877,877
BEGIN DESCRIPTION:
WFSJ Main 274.0
END DESCRIPTION:
XS GIS Cut Line= 4
      3823254.26     10107097.95      3821431.22     10106387.76
      3815478.24     10105867.92      3809221.23     10105642.28
#Sta/Elev= 30
 -3011.5   152.6 -2320.4  139.43 -1952.9   146.1 -1189.5  143.06   937.7  133.05
  1233.9  132.63  1603.6  129.92  1799.2  138.76  1919.6  130.23  3504.1  135.13
  3846.9   134.4  3887.1  125.82  3950.2  133.31  4236.5  132.95  4688.5  132.39
 4895.09  130.96  4998.6  121.11  5141.2  130.33  5151.2  131.24  5290.7  131.85
  5642.5  133.98  6995.1  131.37  7245.9     141  8067.2  137.53  8599.6  139.63
  9815.4  158.42 10208.3  171.28 10434.6  163.99 11176.4  181.42 11181.7  181.55
#Mann= 20 ,-1 , 0
 -3011.5     .05       0 -1189.5     .05       0   937.7     .05       0
  1233.9     .12       0  1603.6     .05       0  3504.1     .05       0
  3950.2     .05       0  4236.5     .12       0  4688.5     .12       0
 4895.09     .07       0  5141.2      .1       0  5290.7     .05       0
  5642.5      .1       0  6995.1     .05       0  7245.9     .12       0
  8067.2      .1       0  8599.6     .12       0  9815.4     .05       0
 10208.3     .12       0 11176.4     .05       0
#XS Ineff= 2 ,-1
    -405  1799.2  138.76  7172.5    9120  142.23
Permanent Ineff=
       F       F
Bank Sta=4895.09,5151.2
XS Rating Curve= 0 ,0
Exp/Cntr=0.3,0.1

Type RM Length L Ch R = 1 ,274000  ,1016,1016,1016
BEGIN DESCRIPTION:
WFSJ Main 273.0
END DESCRIPTION:
XS GIS Cut Line= 4
      3823337.62     10107026.41      3821394.94     10106230.04
      3815178.32     10105030.85      3809931.66     10104852.33
#Sta/Elev= 30
 -3430.8  152.56 -2768.6  146.16 -2674.5  134.92 -2652.9  142.19 -1565.3  142.81
   240.7  132.99   639.7  130.48   955.2  128.74  1138.4  128.87  1604.6  138.68
  1936.4  132.93  2435.1  132.02  2634.6  131.21  2954.8  129.68  4175.5  132.75
  4297.8  122.67  4864.9  131.56    4870  130.61  4898.6  121.41  4998.6  120.31
  5138.1  121.43  5160.6  130.82  6024.4  134.94    6474  141.12  7671.8  142.79
  8263.6  143.62  8591.2  144.08  9126.7  160.52  9482.4  167.41 10249.7  191.38
#Mann= 20 ,-1 , 0
 -3430.8     .05       0 -1565.3     .05       0   240.7     .12       0
   639.7     .12       0   955.2      .1       0  1138.4     .05       0
  1604.6    .075       0  1936.4     .05       0  2435.1     .12       0
  2634.6     .05       0  2954.8      .1       0  4864.9     .07       0
  5160.6      .1       0  6024.4     .05       0    6474     .12       0
  7671.8      .1       0  8263.6     .12       0  8591.2     .12       0
  9126.7     .12       0  9482.4     .05       0
#XS Ineff= 1 ,-1
   -1215  1598.9   138.8
Permanent Ineff=
       F
Bank Sta=4870,5160.6
XS Rating Curve= 0 ,0
Exp/Cntr=0.3,0.1

Type RM Length L Ch R = 1 ,272984  ,892,892,892
BEGIN DESCRIPTION:
WFSJ Main 272.0
END DESCRIPTION:
XS GIS Cut Line= 4
       3823497.3     10106924.33      3821553.33     10106159.05
      3816506.02     10104565.83       3810712.3      10102287.4
#Sta/Elev= 30
 -3034.4  151.65 -2162.3  135.19    -562  143.19   990.8  129.52    1645  128.51
  1881.4  137.71  2165.6  130.75  2294.1  131.21  2519.2  132.82  2797.3  128.37
  3337.6  122.81  3344.4  122.19  3713.4  132.78  4882.9  129.09  4889.6128.6489
  4998.6  119.57    5130  128.07  5477.7   128.2  6216.7  130.79    6704  132.58
  6912.9   133.9  7030.7  135.56  7246.5  138.33    7675  136.08  8331.5  134.24
  9062.9  163.77    9426  153.19 10234.2  173.47 10353.8  175.25 10573.2  175.68
#Mann= 20 ,-1 , 0
 -3034.4     .05       0   990.8      .1       0    1645     .05       0
  2165.6    .075       0  2294.1     .05       0  2519.2     .12       0
  2797.3      .1       0  3337.6     .05       0  3344.4      .1       0
  4882.9     .07       0    5130      .1       0  5477.7     .05       0
  6216.7      .1       0    6704     .05       0  6912.9     .12       0
  7030.7      .1       0  7246.5     .12       0    7675     .05       0
 10234.2      .1       0 10353.8     .12       0
#XS Ineff= 3 ,-1
   -2350    -562  143.19     230  1881.4  137.71  7225.4    8590  139.32
Permanent Ineff=
       F       F       F
Bank Sta=4889.6,5130
XS Rating Curve= 0 ,0
Exp/Cntr=0.3,0.1

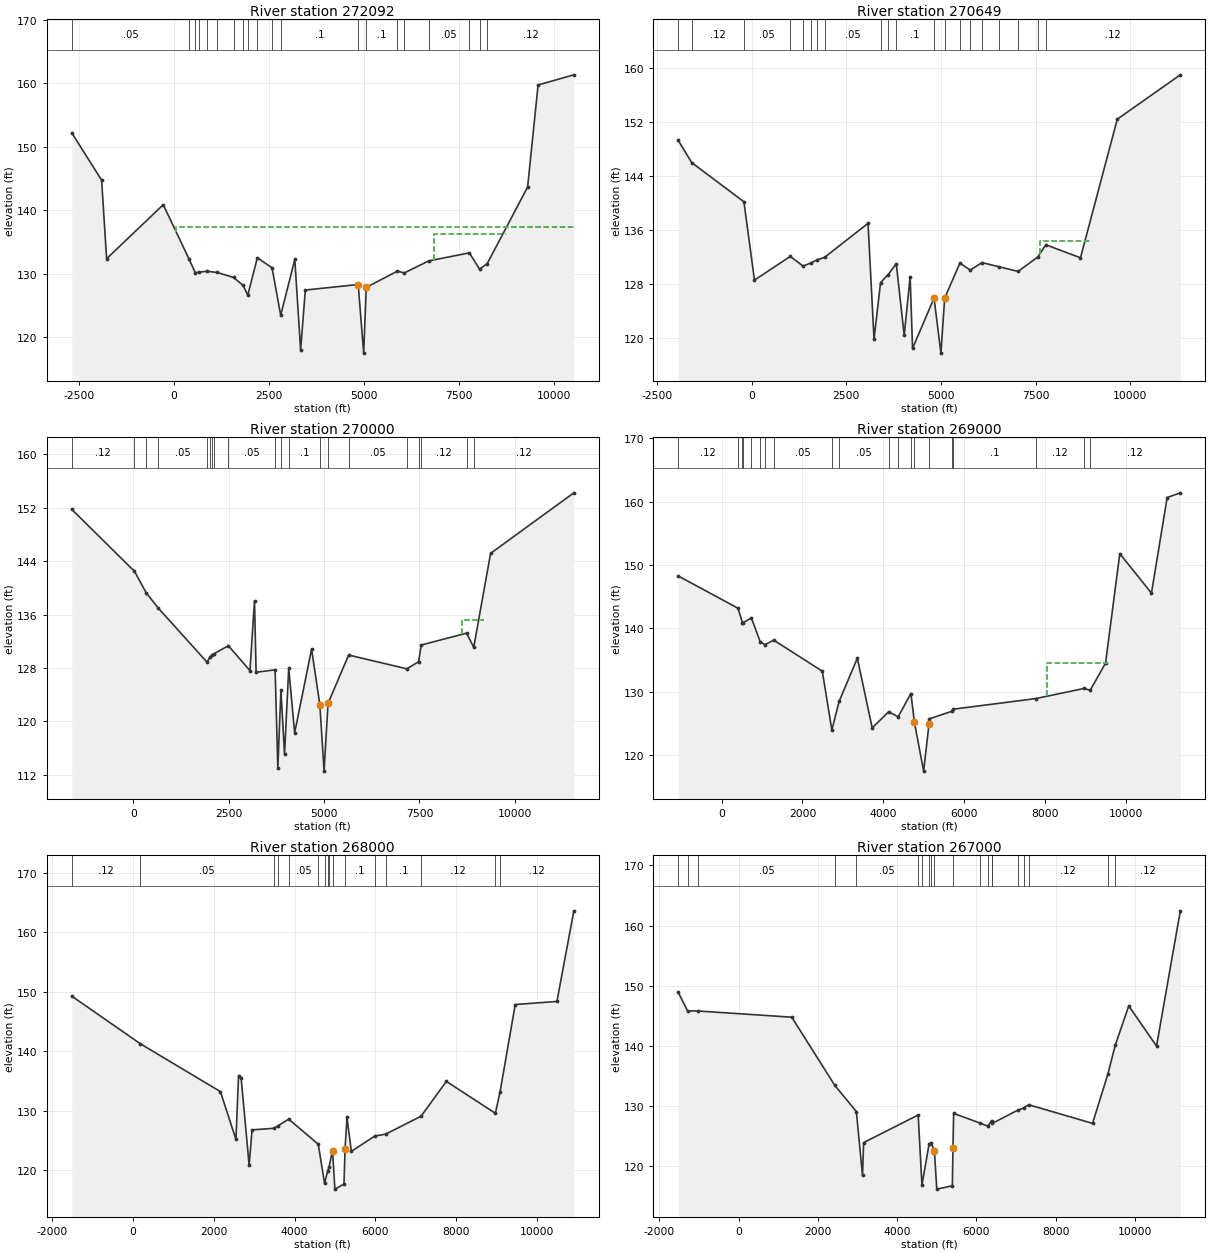
Type RM Length L Ch R = 1 ,272092  ,1443,1443,1443
BEGIN DESCRIPTION:
WFSJ Main 271.0
END DESCRIPTION:
XS GIS Cut Line= 4
      3823566.81     10106837.55      3821501.89     10105984.28
      3816922.68       10104045.      3812378.43     10100112.73
#Sta/Elev= 30
 -2685.6  152.18 -1899.2  144.72 -1768.8  132.37  -277.5  140.87   397.4  132.37
     564  130.18     663  130.25   870.7  130.39  1142.8  130.21  1572.1  129.42
  1825.7  128.16  1947.2  126.63  2199.5  132.52  2585.9  130.94  2814.3  123.46
  3185.5  132.27  3338.5  118.01  3462.3  127.44  4854.1  128.31  4998.6  117.51
  5066.8  127.86  5888.7  130.42  6067.8  130.13  6708.7  132.02  7779.3  133.29
  8050.8  130.71    8251  131.61  9313.6  143.64    9590  159.71   10531  161.31
#Mann= 20 ,-1 , 0
 -2685.6     .05       0   397.4     .12       0     564      .1       0
     663     .12       0   870.7      .1       0  1142.8      .1       0
  1572.1     .12       0  1825.7     .12       0  1947.2     .05       0
  2199.5      .1       0  2585.9     .05       0  2814.3      .1       0
  4854.1     .07       0  5066.8      .1       0  5888.7     .05       0
  6067.8      .1       0  6708.7     .05       0  7779.3     .12       0
  8050.8      .1       0    8251     .12       0
#XS Ineff= 3 ,-1
   -2050  -277.5  140.87      65 -2162.3  137.42  6845.8    8736  136.22
Permanent Ineff=
       F       F       F
Bank Sta=4854.1,5066.8
XS Rating Curve= 0 ,0
Exp/Cntr=0.3,0.1

Type RM Length L Ch R = 1 ,270649  ,649,649,649
BEGIN DESCRIPTION:
WFSJ Main 270.0
END DESCRIPTION:
XS GIS Cut Line= 4
      3824269.88     10106316.69      3823031.08     10105440.77
       3818120.6     10103888.75       3813055.5       10099670.
#Sta/Elev= 30
 -1938.7  149.24 -1584.4  145.95  -203.7  140.13    74.8  128.52  1020.8  132.04
  1357.6   130.6  1556.7  131.05  1729.4  131.53  1927.1   131.9  3073.6  136.94
  3231.6  119.79  3404.7  128.16    3605  129.34  3819.5  130.95  4028.6  120.34
  4185.9  129.03  4248.9   118.4 4816.98  125.86  4998.6   117.7  5097.4  125.85
  5499.3  131.04  5773.6  130.01  6082.7  131.12  6521.3  130.52  7035.4  129.81
  7555.6  131.94  7768.4  133.76  8683.8  131.83  9656.2  152.38 11320.3  158.95
#Mann= 20 ,-1 , 0
 -1938.7     .12       0 -1584.4     .12       0  -203.7     .05       0
  1020.8      .1       0  1357.6     .12       0  1556.7      .1       0
  1729.4     .12       0  1927.1     .05       0  3404.7     .12       0
    3605     .05       0  3819.5      .1       0 4816.98     .07       0
  5097.4      .1       0  5499.3      .1       0  5773.6     .05       0
  6082.7      .1       0  6521.3     .05       0  7035.4      .1       0
  7555.6     .05       0  7768.4     .12       0
#XS Ineff= 2 ,-1
    -135  3073.6  136.94  7604.6    8990  134.29
Permanent Ineff=
       F       F
Bank Sta=4816.98,5097.4
XS Rating Curve= 0 ,0
Exp/Cntr=0.3,0.1

Type RM Length L Ch R = 1 ,270000  ,1000,1000,1000
BEGIN DESCRIPTION:
WFSJ Main 269.0
END DESCRIPTION:
XS GIS Cut Line= 4
      3824486.94     10106203.87      3823031.33     10105242.03
      3818498.32     10103454.82      3813329.26     10099435.88
#Sta/Elev= 30
 -1617.3  151.75      27  142.48   332.6  139.28     646     137  1928.7  128.88
  2004.2  129.64  2062.8  129.91  2108.7  130.12  2487.9  131.34  3054.9  127.61
  3174.2  138.03  3216.1  127.36  3714.4  127.73  3785.8  113.06  3866.6  124.66
  3961.9  115.12  4071.5  128.01  4226.6  118.29    4671  130.84  4887.6   122.5
  4998.6  112.56    5102   122.7  5642.5  129.94  7168.6  127.88  7478.6  128.95
  7545.1  131.44  8733.2  133.22  8923.1  131.11  9364.3  145.16 11547.6  154.23
#Mann= 20 ,-1 , 0
 -1617.3     .12       0      27     .05       0   332.6     .12       0
     646     .05       0  1928.7      .1       0  2004.2     .12       0
  2062.8      .1       0  2108.7     .12       0  2487.9     .05       0
  3714.4     .12       0  3866.6     .05       0  4071.5      .1       0
  4887.6     .07       0    5102      .1       0  5642.5     .05       0
  7168.6      .1       0  7478.6     .05       0  7545.1     .12       0
  8733.2      .1       0  8923.1     .12       0
#XS Ineff= 2 ,-1
     265  3174.2  138.03  8623.3    9180  135.21
Permanent Ineff=
       F       F
Bank Sta=4887.6,5102
XS Rating Curve= 0 ,0
Exp/Cntr=0.3,0.1

Type RM Length L Ch R = 1 ,269000  ,1000,1000,1000
BEGIN DESCRIPTION:
WFSJ Main 268.0
END DESCRIPTION:
XS GIS Cut Line= 4
      3824612.78     10105992.62      3823125.22     10105139.66
      3819316.75     10103018.26      3814074.36     10099432.15
#Sta/Elev= 30
 -1074.2  148.29   404.2   143.2   515.5  140.91   522.5  140.89   737.4  141.66
   953.5  137.92  1069.2  137.45  1290.3  138.16  2491.8  133.26  2727.9  123.97
    2906  128.48  3358.3   135.3  3726.4  124.31  4129.6  126.84  4369.9  126.08
  4684.1  129.74 4771.22  125.19  4998.6  117.49  5132.9  124.98 5143.45125.7529
  5696.2  126.93  5724.5  127.26  7775.3  128.94  8963.2  130.53  9122.5  130.27
  9501.2  134.54    9854  151.81 10637.4  145.58 11026.1  160.67 11351.6  161.41
#Mann= 20 ,-1 , 0
 -1074.2     .12       0   404.2     .05       0   515.5     .12       0
   522.5     .05       0   737.4     .12       0   953.5     .05       0
  1069.2     .12       0  1290.3     .05       0  2727.9     .12       0
    2906     .05       0  4129.6    .075       0  4369.9     .12       0
  4684.1      .1       0 4771.22     .07       0 5143.45      .1       0
  5696.2     .05       0  5724.5      .1       0  7775.3     .12       0
  8963.2     .05       0  9122.5     .12       0
#XS Ineff= 2 ,-1
    1750  3358.3   135.3    8063    9550  134.48
Permanent Ineff=
       F       F
Bank Sta=4771.22,5132.9
XS Rating Curve= 0 ,0
Exp/Cntr=0.3,0.1

Type RM Length L Ch R = 1 ,268000  ,1000,1000,1000
BEGIN DESCRIPTION:
WFSJ Main 267.0
END DESCRIPTION:
XS GIS Cut Line= 4
      3824737.79      10105909.3      3823189.68     10105087.46
      3819467.24     10102116.85      3814345.18     10099161.31
#Sta/Elev= 30
 -1515.2   149.3   183.8  141.29  2164.5  133.25  2548.8  125.22  2612.8  135.88
  2676.9  135.58  2875.4   120.9  2947.5  126.82  3491.8  127.09  3586.3  127.49
  3854.6  128.62    4587  124.41  4742.1  117.83  4822.8  119.98  4854.7  120.63
 4939.82  123.35  4998.6  116.86    5223   117.7 5250.04  123.64  5297.7  128.91
  5405.4  123.21  5985.4  125.78    6255   126.1  7132.8  129.12  7757.8  134.97
  8970.7  129.61    9085  133.12  9462.5  147.89 10494.9  148.41 10913.6  163.64
#Mann= 16 ,-1 , 0
 -1515.2     .12       0   183.8     .05       0  3491.8      .1       0
  3586.3    .075       0  3854.6     .05       0    4587     .12       0
  4742.1      .1       0  4822.8     .12       0  4854.7      .1       0
 4939.82     .07       0 5250.04      .1       0  5985.4     .05       0
    6255      .1       0  7132.8     .12       0  8970.7     .05       0
    9085     .12       0
#XS Ineff= 2 ,-1
    1390  2612.8  135.88  7757.8    9230  134.97
Permanent Ineff=
       F       F
Bank Sta=4939.82,5250.04
XS Rating Curve= 0 ,0
Exp/Cntr=0.3,0.1

Type RM Length L Ch R = 1 ,267000  ,1000,1000,1000
BEGIN DESCRIPTION:
WFSJ Main 266.0
END DESCRIPTION:
XS GIS Cut Line= 4
      3825038.01     10105693.31      3820120.68     10101401.89
      3816145.51     10099493.62      3814445.08     10099145.87
#Sta/Elev= 30
 -1526.6  148.89 -1291.5  145.82 -1026.8  145.79  1338.7  144.76  2422.3  133.45
  2969.3  129.07  3124.3  118.45  3152.8  123.92    4529   128.5  4624.2  116.86
  4803.6  123.62  4853.5  123.91  4938.4  122.58  4998.6  116.18  5391.4  116.73
  5407.1  122.95  5424.2  128.78  6083.9  127.17  6286.9  126.65  6381.7  127.57
  6394.4  127.09  7036.3  129.29  7188.1  129.66  7318.1  130.21  8929.9  127.11
  9314.9  135.25  9503.7  140.12  9843.7  146.63 10545.2  139.96 11145.1  162.44
#Mann= 20 ,-1 , 0
 -1526.6     .12       0 -1291.5      .1       0 -1026.8     .05       0
  2422.3      .1       0  2969.3     .05       0    4529     .12       0
  4624.2      .1       0  4803.6     .12       0  4853.5      .1       0
  4938.4     .07       0  5407.1      .1       0  6083.9     .05       0
  6286.9     .12       0  6381.7     .05       0  6394.4      .1       0
  7036.3     .12       0  7188.1      .1       0  7318.1     .12       0
  9314.9     .05       0  9503.7     .12       0
Bank Sta=4938.4,5407.1
XS Rating Curve= 0 ,0
Exp/Cntr=0.3,0.1