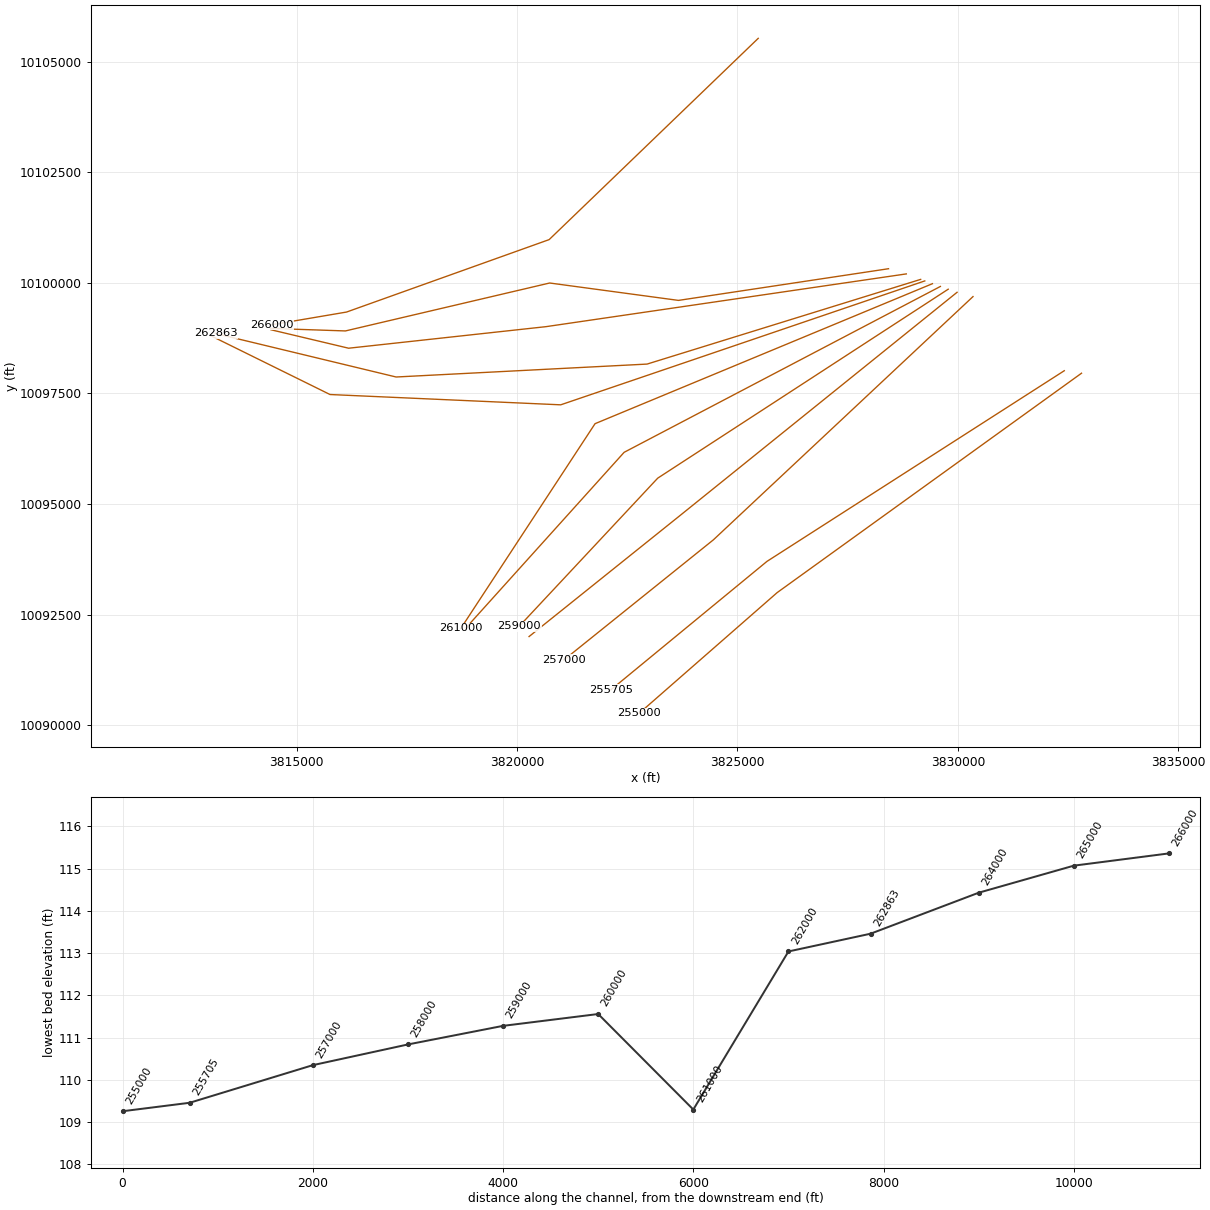
HEC-RAS study WFSJ Main.prj: WFSJ Main Base Level Engineering

--- WFSJ Main.g02 (geometry) --- (continued)

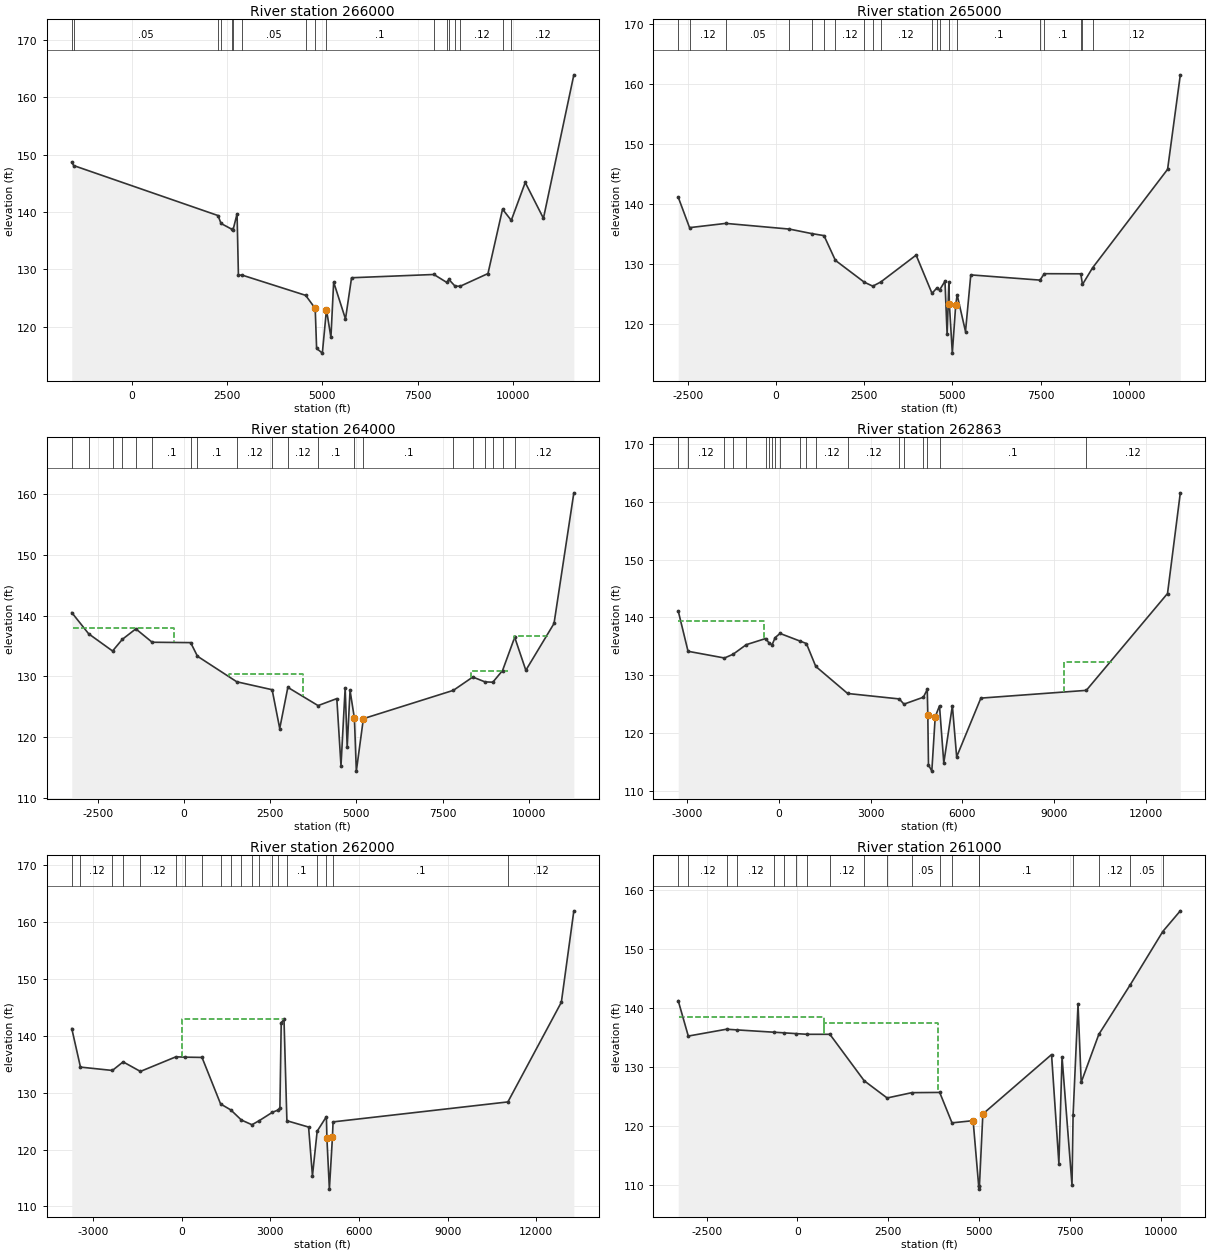
Type RM Length L Ch R = 1 ,266000  ,1000,1000,1000
BEGIN DESCRIPTION:
WFSJ Main 265.0
END DESCRIPTION:
XS GIS Cut Line= 4
      3825472.05     10105526.22      3820728.36     10100976.16
      3816131.62     10099338.38      3814440.85     10099052.25
#Sta/Elev= 30
 -1573.1  148.66 -1522.9  148.08  2262.4  139.36  2341.6  137.98  2622.3  136.98
  2656.9  136.86  2761.9  139.66  2797.5  128.96    2895  128.97  4560.8  125.44
 4808.65123.1817    4813  122.86  4848.3  116.18  4998.6  115.36  5106.7  122.95
  5223.5  118.11  5295.3  127.75  5605.6  121.32  5764.9  128.51  7924.8  129.08
  8257.6  127.71  8316.5  128.21    8480  127.04  8615.2  127.03  9342.4  129.24
  9724.4  140.47  9953.6  138.52 10319.7  145.13   10797  138.88 11594.6  163.91
#Mann= 17 ,-1 , 0
 -1573.1      .1       0 -1522.9     .05       0  2262.4     .12       0
  2341.6      .1       0  2622.3     .05       0  2656.9      .1       0
    2895     .05       0  4560.8      .1       0    4813     .07       0
  5106.7      .1       0  7924.8     .12       0  8257.6      .1       0
  8316.5     .12       0    8480      .1       0  8615.2     .12       0
  9724.4     .05       0  9953.6     .12       0
Bank Sta=4808.65,5106.7
XS Rating Curve= 0 ,0
Exp/Cntr=0.3,0.1

Type RM Length L Ch R = 1 ,265000  ,1000,1000,1000
BEGIN DESCRIPTION:
WFSJ Main 264.0
END DESCRIPTION:
XS GIS Cut Line= 5
      3828427.78     10100317.86      3823662.12     10099601.71
      3820740.02     10099994.91      3816105.58      10098911.3
      3814407.68     10098968.59
#Sta/Elev= 30
 -2767.6  141.08   -2447     136 -1421.3  136.71   382.6  135.76  1013.9  135.01
  1362.3  134.67  1685.7  130.54  2504.8   126.9  2744.8  126.24  2969.6  126.93
    3973  131.42  4423.2  125.04    4555   125.9  4636.2  125.59  4790.3  127.07
  4850.8  118.19  4901.3  126.94 4915.05  123.26  4998.6  115.07  5094.7  123.12
  5135.7  124.78  5371.9  118.67  5521.4  128.12  7481.2  127.25    7606  128.32
  8638.7   128.3  8686.2  126.52  8971.3  129.29 11097.9  145.73 11458.3  161.49
#Mann= 20 ,-1 , 0
 -2767.6     .05       0   -2447     .12       0 -1421.3     .05       0
   382.6      .1       0  1013.9     .12       0  1362.3      .1       0
  1685.7     .12       0  2504.8      .1       0  2744.8      .1       0
  2969.6     .12       0  4423.2      .1       0    4555     .05       0
  4636.2      .1       0  4901.3     .07       0  5135.7      .1       0
  7481.2     .12       0    7606      .1       0  8638.7     .12       0
  8686.2      .1       0  8971.3     .12       0
#XS Ineff= 1 ,-1
    1325    3973  131.42
Permanent Ineff=
       F
Bank Sta=4915.05,5094.7
XS Rating Curve= 0 ,0
Exp/Cntr=0.3,0.1

Type RM Length L Ch R = 1 ,264000  ,1137,1137,1137
BEGIN DESCRIPTION:
WFSJ Main 263.0
END DESCRIPTION:
XS GIS Cut Line= 4
      3828831.42     10100200.68      3820655.76     10099007.95
      3816178.49     10098520.67      3814418.04     10098937.35
#Sta/Elev= 30
 -3262.2  140.51 -2771.8  137.02 -2077.7  134.19 -1794.4  136.11 -1402.4  137.83
  -928.4  135.63   188.6  135.57   386.9  133.33  1526.9  129.13  2554.4  127.82
  2774.6  121.44  3010.3  128.21  3887.9  125.21    4432  126.36  4553.2  115.33
  4674.5  128.13    4733  118.37    4816  127.71    4943  123.11  4998.6  114.43
  5203.2  123.06  7815.5  127.72  8379.5  129.91  8734.1  129.11  8960.9  129.06
  9243.3  130.98  9595.8  136.45  9919.2  131.02 10737.5  138.72 11312.8  160.21
#Mann= 20 ,-1 , 0
 -3262.2     .05       0 -2771.8     .12       0 -2077.7      .1       0
 -1794.4     .12       0 -1402.4     .05       0  -928.4      .1       0
   188.6     .05       0   386.9      .1       0  1526.9     .12       0
  2554.4      .1       0  3010.3     .12       0  3887.9      .1       0
    4943     .07       0  5203.2      .1       0  7815.5     .12       0
  8379.5      .1       0  8734.1     .12       0  8960.9      .1       0
  9243.3     .12       0  9595.8     .12       0
#XS Ineff= 4 ,-1
    1315  3441.6  130.45   -3215  -307.7  137.91  8337.5    9390  130.96
  9570.9   10560  136.61
Permanent Ineff=
       F       F       F       F
Bank Sta=4943,5203.2
XS Rating Curve= 0 ,0
Exp/Cntr=0.3,0.1

Type RM Length L Ch R = 1 ,262863  ,863,863,863
BEGIN DESCRIPTION:
WFSJ Main 262.0
END DESCRIPTION:
XS GIS Cut Line= 4
      3829156.83     10100076.65      3822949.89     10098162.08
      3817255.87     10097869.94      3813157.69       10098854.
#Sta/Elev= 30
 -3290.1  141.12 -2969.4  134.16 -1778.7     133 -1496.6  133.65 -1067.2   135.3
  -432.7  136.36  -325.3  135.62  -223.3  135.27  -121.3  136.53    38.7  137.24
     682  135.94   899.2   135.5  1205.3  131.55  2247.5  126.87  3934.8  125.93
  4088.6  125.03    4724  126.23  4849.6  127.58 4867.98   123.1  4889.7  114.54
  4998.6  113.46    5110  122.85  5250.1  124.74  5390.3  114.87  5670.7  124.74
  5810.9  115.93  6601.9  126.07 10048.9  127.41 12703.5  144.14 13121.6  161.53
#Mann= 20 ,-1 , 0
 -3290.1     .05       0 -2969.4     .12       0 -1778.7     .05       0
 -1496.6     .12       0 -1067.2     .12       0  -432.7     .05       0
  -325.3    .075       0  -223.3     .05       0  -121.3    .075       0
    38.7     .05       0     682     .05       0   899.2    .075       0
  1205.3     .12       0  2247.5     .12       0  3934.8     .12       0
  4088.6      .1       0    4724     .12       0  4849.6     .07       0
  5250.1      .1       0 10048.9     .12       0
#XS Ineff= 2 ,-1
   -3300  -471.5   139.4  9314.9   10890  132.35
Permanent Ineff=
       F       F
Bank Sta=4867.98,5110
XS Rating Curve= 0 ,0
Exp/Cntr=0.3,0.1

Type RM Length L Ch R = 1 ,262000  ,1000,1000,1000
BEGIN DESCRIPTION:
WFSJ Main 261.0
END DESCRIPTION:
XS GIS Cut Line= 4
       3829250.6     10100041.93      3820990.47     10097240.99
      3815756.62      10097473.8      3813032.74      10098812.3
#Sta/Elev= 30
 -3722.1  141.27 -3427.8  134.49 -2347.2   133.9 -1983.8  135.41 -1398.9  133.73
    -196   136.3     100  136.24   686.7  136.19  1316.3  128.01    1662  126.96
    2021  125.18  2377.6  124.36  2631.3   125.1  3070.9  126.55  3270.3  126.96
  3323.8  127.34  3368.1  142.32  3462.4  142.86  3560.4  125.06  4294.6  123.95
  4425.5  115.38  4584.7  123.22  4897.2  125.78 4914.86  121.99  4998.5  113.04
 5103.11122.2745  5122.7  124.86 11041.7  128.37 12851.1  145.89   13274  161.96
#Mann= 20 ,-1 , 0
 -3722.1     .05       0 -3427.8     .12       0 -2347.2     .05       0
 -1983.8     .12       0 -1398.9     .12       0    -196     .05       0
     100    .075       0   686.7     .05       0  1316.3     .12       0
    1662      .1       0    2021     .12       0  2377.6      .1       0
  2631.3     .12       0  3070.9      .1       0  3270.3     .12       0
  3560.4      .1       0  4584.7     .12       0  4897.2     .07       0
  5122.7      .1       0 11041.7     .12       0
#XS Ineff= 2 , 0
       0  3462.4  142.86               0
Permanent Ineff=
       F       F
Bank Sta=4914.86,5103.11
XS Rating Curve= 0 ,0
Exp/Cntr=0.3,0.1

Type RM Length L Ch R = 1 ,261000  ,1000,1000,1000
BEGIN DESCRIPTION:
WFSJ Main 260.0
END DESCRIPTION:
XS GIS Cut Line= 3
      3829424.24     10099979.44       3821769.4     10096814.55
      3818723.41     10092185.28
#Sta/Elev= 30
 -3283.3  141.19 -3006.7  135.21 -1953.6  136.37 -1656.2  136.25  -642.1  135.86
  -377.1  135.76   -53.9  135.63   263.1  135.51   891.9  135.51  1837.8  127.64
  2468.4  124.73  3149.3  125.63  3916.1  125.67    4255  120.52  4836.5  120.89
    4990   109.8  4998.5   109.3    5010   109.8  5104.4  122.02  6996.1  132.08
  7197.9  113.63  7285.3  131.63  7559.4  109.96  7588.8  121.77  7725.1  140.62
  7812.4  127.38  8296.8  135.49  9167.2  143.93 10058.9  152.91 10541.5  156.41
#Mann= 20 ,-1 , 0
 -3283.3     .05       0 -3006.7     .12       0 -1953.6     .05       0
 -1656.2     .12       0  -642.1     .05       0  -377.1     .12       0
   -53.9      .1       0   263.1     .12       0   891.9     .12       0
  1837.8     .05       0  2468.4     .12       0  3149.3     .05       0
  3916.1     .05       0    4255      .1       0    4990     .07       0
    5010      .1       0  7588.8     .05       0  8296.8     .12       0
  9167.2     .05       0 10058.9     .12       0
#XS Ineff= 4 ,-1
     717  3876.3  137.34   -3265   716.6  138.49  6996.1    7694  132.08
  7725.1    9075  140.62
Permanent Ineff=
       F       F       F       F
Bank Sta=4836.5,5104.4
XS Rating Curve= 0 ,0
Exp/Cntr=0.3,0.1

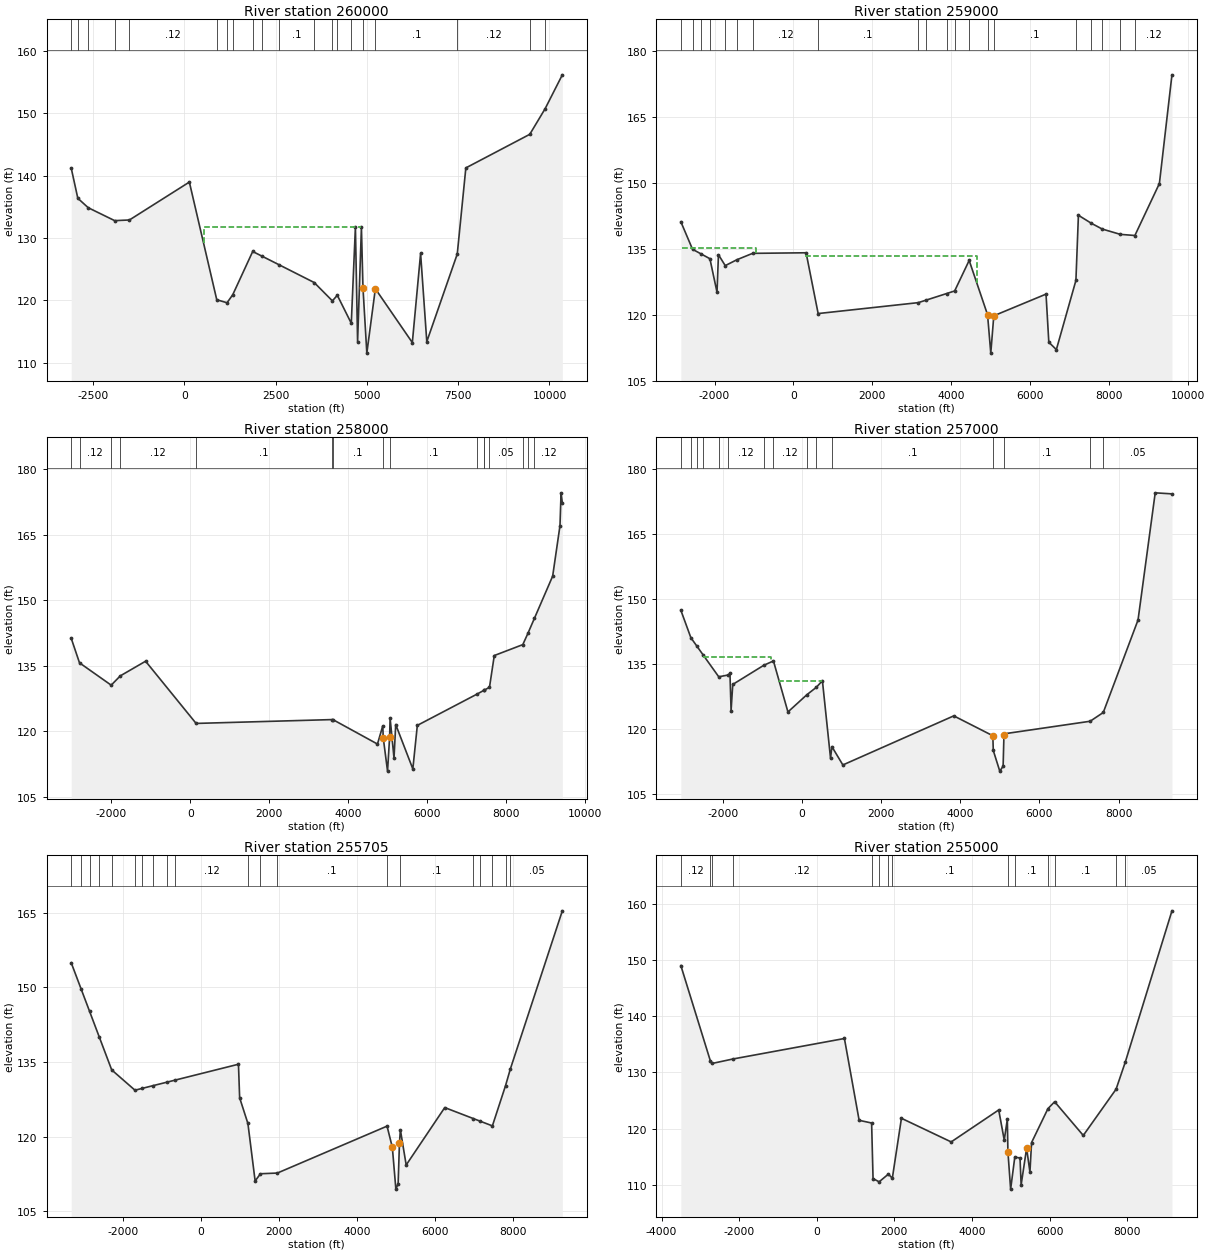
Type RM Length L Ch R = 1 ,260000  ,1000,1000,1000
BEGIN DESCRIPTION:
WFSJ Main 259.0
END DESCRIPTION:
XS GIS Cut Line= 3
      3829604.77     10099916.93      3822429.18     10096167.12
      3818839.96     10092197.33
#Sta/Elev= 30
 -3096.3   141.2 -2915.3  136.36 -2629.8  134.85 -1905.6  132.78   -1502  132.89
   138.5  138.96   889.1  120.11  1170.6  119.63  1327.4  120.92  1873.1  127.84
  2128.3  127.09  2586.4  125.74  3556.7  122.87  4055.8  119.93  4189.8  120.83
  4572.8  116.34  4685.6  131.75  4745.4  113.42  4850.2   131.7 4892.36  122.07
  4998.5  111.56  5231.8  121.87  6244.4  113.25  6470.8  127.52  6640.4   113.4
  7474.4  127.43  7709.7  141.23  9460.2  146.61  9880.2  150.71 10351.8  156.14
#Mann= 20 ,-1 , 0
 -3096.3     .05       0 -2915.3     .12       0 -2629.8     .12       0
 -1905.6     .05       0   -1502     .12       0   889.1     .12       0
  1170.6      .1       0  1327.4     .12       0  1873.1     .05       0
  2128.3     .05       0  2586.4      .1       0  3556.7     .05       0
  4055.8      .1       0  4189.8     .05       0  4572.8     .12       0
 4892.36     .07       0  5231.8      .1       0  7474.4     .12       0
  9460.2     .05       0  9880.2     .12       0
#XS Ineff= 3 ,-1
     530  4850.2   131.7   -3085   138.5  138.96 7709.78    9035  141.23
Permanent Ineff=
       F       F       F
Bank Sta=4892.36,5231.8
XS Rating Curve= 0 ,0
Exp/Cntr=0.3,0.1

Type RM Length L Ch R = 1 ,259000  ,1000,1000,1000
BEGIN DESCRIPTION:
WFSJ Main 258.0
END DESCRIPTION:
XS GIS Cut Line= 3
      3829781.84     10099854.42      3823191.56     10095583.11
      3820051.84     10092237.41
#Sta/Elev= 30
 -2853.4  141.16 -2557.6   134.9 -2334.1  133.81 -2117.1  132.75 -1937.1  125.12
 -1900.8  133.66 -1728.6  131.18 -1433.4  132.52 -1035.4  133.97   319.8   134.1
   624.9  120.28  3160.1  122.76  3352.7  123.31  3876.8  124.82  4083.1  125.42
  4450.9  132.36 4916.68  120.01  4998.5  111.28  5074.7  119.77  6397.9   124.7
  6468.7  113.76  6659.7  112.08  7155.1  127.81  7218.5  142.63  7549.5  140.79
  7821.2   139.5  8279.4  138.29  8649.1  138.03  9269.9  149.85  9588.2  174.57
#Mann= 20 ,-1 , 0
 -2853.4     .05       0 -2557.6     .12       0 -2334.1      .1       0
 -2117.1     .12       0 -1728.6     .05       0 -1433.4      .1       0
 -1035.4     .12       0   624.9      .1       0  3160.1     .12       0
  3352.7      .1       0  3876.8      .1       0  4083.1     .05       0
  4450.9      .1       0 4916.68     .07       0  5074.7      .1       0
  7155.1     .12       0  7549.5     .12       0  7821.2     .05       0
  8279.4     .05       0  8649.1     .12       0
#XS Ineff= 2 ,-1
   -2830  -953.9  135.15   292.5  4643.1  133.32
Permanent Ineff=
       F       F
Bank Sta=4916.68,5074.7
XS Rating Curve= 0 ,0
Exp/Cntr=0.3,0.1

Type RM Length L Ch R = 1 ,258000  ,1000,1000,1000
BEGIN DESCRIPTION:
WFSJ Main 257.0
END DESCRIPTION:
XS GIS Cut Line= 3
      3829983.28     10099785.01      3823731.89     10094765.81
      3820272.53     10092002.24
#Sta/Elev= 30
   -3017  141.25 -2807.2  135.63 -2004.3  130.52 -1772.8  132.65 -1132.6     136
   147.7  121.76  3599.2  122.64  3612.5  122.64  4743.2  117.04  4877.6  121.21
  4890.3  118.43  4998.5  110.84 5051.64  118.68  5063.2  122.99  5162.5  113.83
  5205.7  121.51  5639.6  111.34  5753.3  121.31  7267.8  128.48  7433.3   129.3
  7450.1  129.38  7581.9  130.04  7703.3   137.3  8426.1   139.8  8554.7  142.36
  8720.8  145.83  9182.7  155.48  9368.4  167.04  9395.6  174.55  9427.7  172.27
#Mann= 16 ,-1 , 0
   -3017     .05       0 -2807.2     .12       0 -2004.3     .05       0
 -1772.8     .12       0   147.7      .1       0  3599.2     .12       0
  3612.5      .1       0  4877.6     .07       0  5063.2      .1       0
  7267.8     .12       0  7433.3      .1       0  7450.1     .12       0
  7581.9     .05       0  8426.1     .12       0  8554.7     .05       0
  8720.8     .12       0
#XS Ineff= 1 ,-1
   -3000 -1132.6     136
Permanent Ineff=
       F
Bank Sta=4890.3,5051.64
XS Rating Curve= 0 ,0
Exp/Cntr=0.3,0.1

Type RM Length L Ch R = 1 ,257000  ,1295,1295,1295
BEGIN DESCRIPTION:
WFSJ Main 256.0
END DESCRIPTION:
XS GIS Cut Line= 3
      3830344.71     10099687.76      3824455.36      10094189.5
      3821061.88     10091472.44
#Sta/Elev= 30
   -3057  147.41 -2803.4  141.08 -2648.9   139.1 -2487.2  137.03 -2099.8  132.08
 -1858.6   132.5 -1816.4  132.84 -1788.2  124.31 -1745.7  130.32  -962.5  134.73
  -718.3  135.73    -352  123.98   128.7  127.97   361.6  129.63   518.6  131.18
   723.8  113.33   758.6  115.99    1035  111.77  3836.7  123.08 4823.13   118.5
  4834.2  115.11  4998.2  110.35  5082.8  111.48  5103.6   118.6  5111.6  118.95
  7281.1  121.84  7612.4  123.86  8490.5  145.17  8924.3  174.46  9347.2  174.22
#Mann= 15 ,-1 , 0
   -3057     .05       0 -2803.4     .12       0 -2648.9      .1       0
 -2487.2     .12       0 -2099.8     .05       0 -1858.6     .12       0
  -962.5     .05       0  -718.3     .12       0   128.7     .05       0
   361.6     .12       0   758.6      .1       0  4834.2     .07       0
  5111.6      .1       0  7281.1     .12       0  7612.4     .05       0
#XS Ineff= 2 ,-1
   -2490  -769.2  136.55    -570   518.6  131.18
Permanent Ineff=
       F       F
Bank Sta=4823.13,5103.6
XS Rating Curve= 0 ,0
Exp/Cntr=0.3,0.1

Type RM Length L Ch R = 1 ,255705  ,705,705,705
BEGIN DESCRIPTION:
WFSJ Main 255.0
END DESCRIPTION:
XS GIS Cut Line= 3
      3832416.05     10098012.06      3825671.29     10093702.18
      3822129.61     10090798.53
#Sta/Elev= 30
 -3320.4  154.95 -3067.6   149.7 -2848.6  145.16 -2601.2  140.02   -2283  133.42
 -1686.9  129.34 -1505.2   129.7 -1221.8  130.26  -854.3  130.98  -662.2  131.36
   964.8  134.56   995.3  127.81    1207  122.65    1392   111.1  1528.6  112.55
  1961.5  112.69  4772.3  122.12  4907.9  117.85  4998.2  109.46  5056.5  110.56
 5090.16118.7531  5113.9  121.38  5262.5  114.31  6250.7  125.85  6983.4  123.64
  7146.1  123.15  7471.5  122.17  7808.1  130.25  7931.8  133.61  9263.6  165.39
#Mann= 20 ,-1 , 0
 -3320.4     .05       0 -3067.6     .12       0 -2848.6     .05       0
 -2601.2      .1       0   -2283     .12       0 -1686.9      .1       0
 -1505.2     .12       0 -1221.8     .12       0  -854.3     .05       0
  -662.2     .12       0    1207      .1       0  1528.6     .05       0
  1961.5      .1       0  4772.3     .07       0  5113.9      .1       0
  6983.4     .12       0  7146.1      .1       0  7471.5     .05       0
  7808.1     .12       0  7931.8     .05       0
Bank Sta=4907.9,5090.16
XS Rating Curve= 0 ,0
Exp/Cntr=0.3,0.1

Type RM Length L Ch R = 1 ,255000  ,1000,1000,1000
BEGIN DESCRIPTION:
WFSJ Main 254.0
END DESCRIPTION:
XS GIS Cut Line= 3
       3832806.9      10097955.5       3825901.6     10092995.91
      3822768.46      10090265.4
#Sta/Elev= 30
 -3501.8  148.99 -2743.6  132.11 -2699.4  131.59 -2157.7  132.39     714  136.03
  1093.4  121.49  1415.1  121.01    1452  111.13  1609.3  110.56  1845.8  111.92
  1949.2  111.21  2183.7  121.85  3465.6  117.65  4690.9  123.33  4833.4  117.98
  4913.1  121.68  4927.9  115.92  4998.2  109.26  5105.4  114.95  5240.2  114.79
  5268.7     110  5410.1  116.53  5495.6  112.29  5537.3  117.53  5959.4  123.56
  6132.3  124.79  6870.3   118.8  7715.7  127.02  7953.3  131.84    9156  158.72
#Mann= 14 ,-1 , 0
 -3501.8     .12       0 -2743.6     .05       0 -2699.4      .1       0
 -2157.7     .12       0  1415.1     .05       0  1609.3      .1       0
  1845.8     .05       0  1949.2      .1       0  4927.9     .07       0
  5105.4      .1       0  5959.4     .05       0  6132.3      .1       0
  7715.7     .12       0  7953.3     .05       0
Bank Sta=4927.9,5410.1
XS Rating Curve= 0 ,0
Exp/Cntr=0.3,0.1