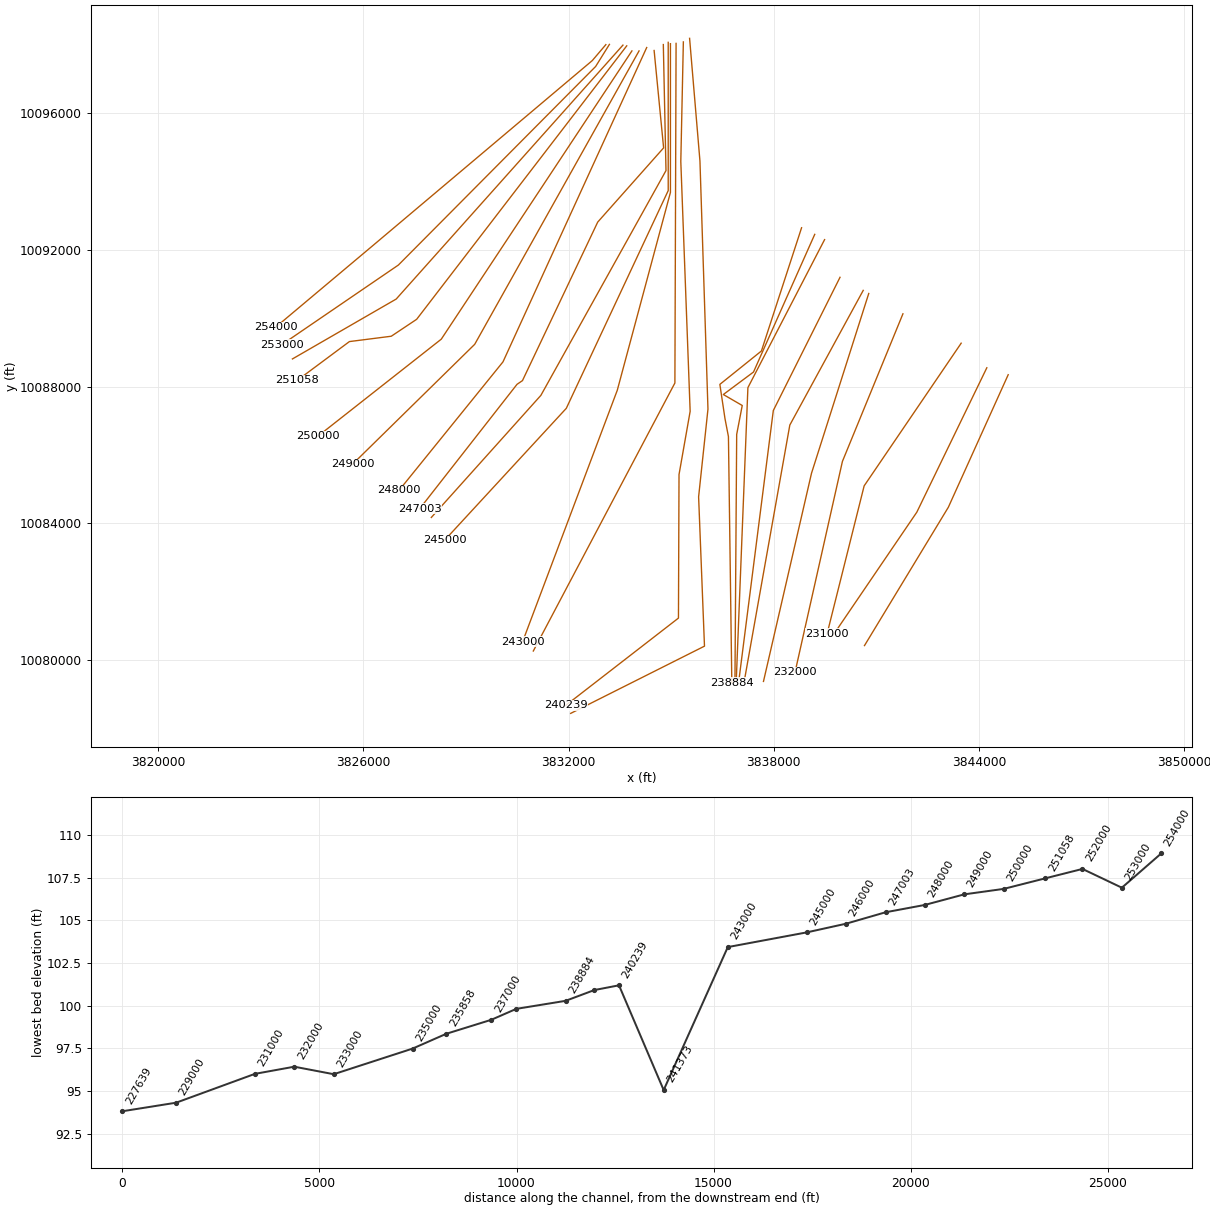
HEC-RAS study WFSJ Main.prj: WFSJ Main Base Level Engineering

--- WFSJ Main.g02 (geometry) --- (continued)

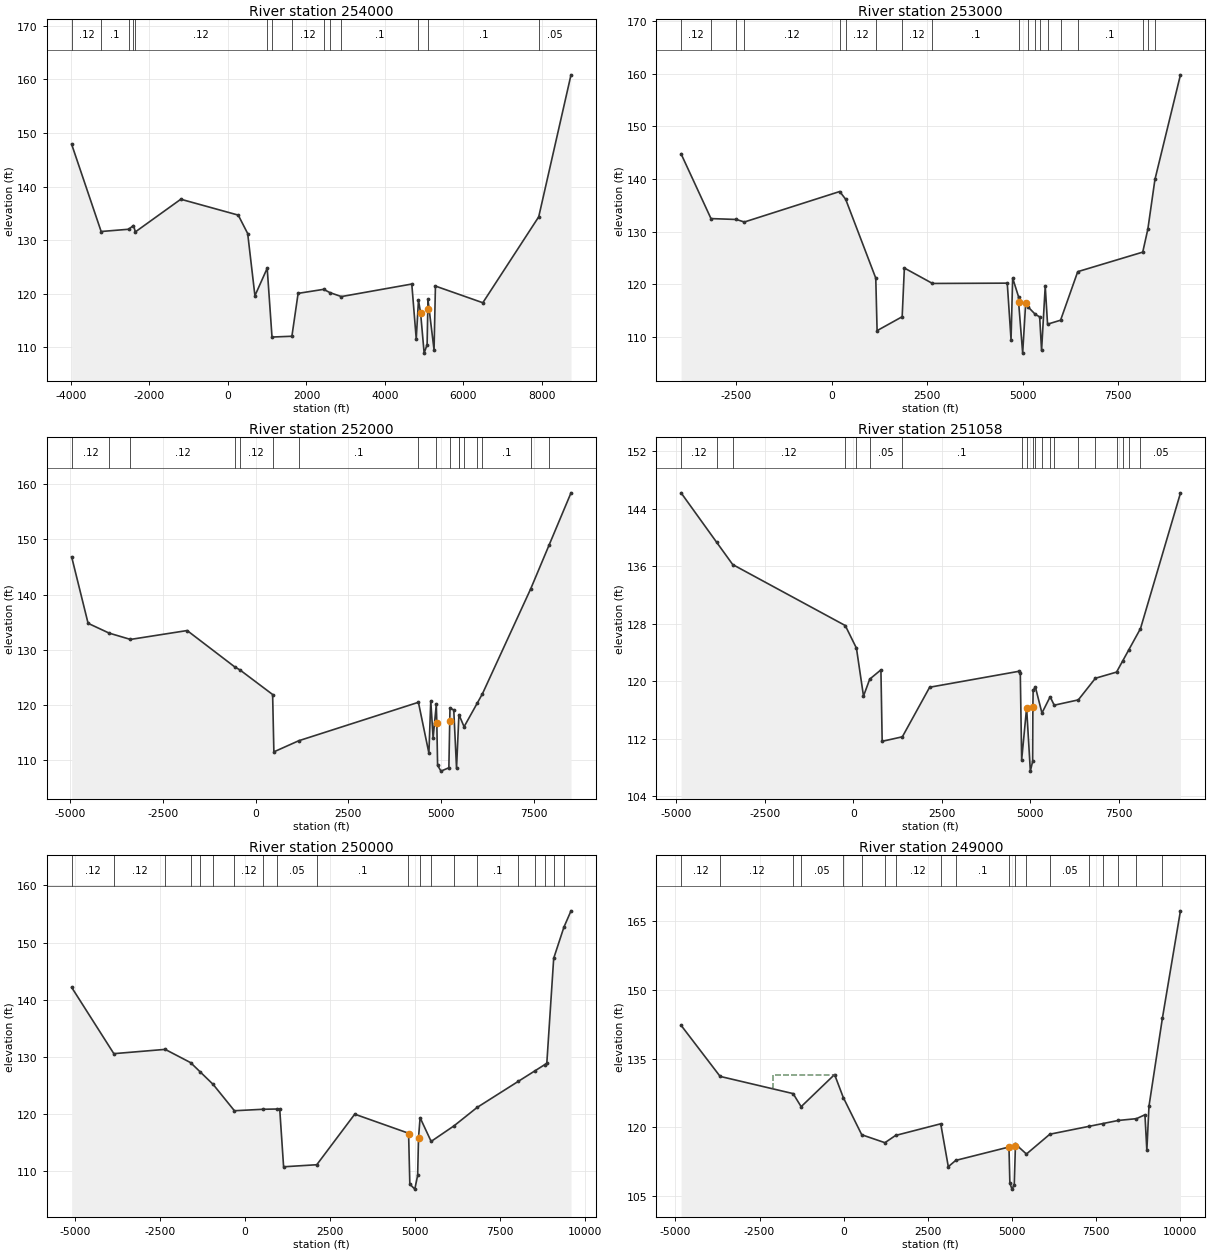
Type RM Length L Ch R = 1 ,254000  ,1000,1000,1000
BEGIN DESCRIPTION:
WFSJ Main 253.0
END DESCRIPTION:
XS GIS Cut Line= 4
      3833091.59     10097997.14      3832695.77     10097531.87
       3826296.2     10092136.21       3823432.3     10089731.33
#Sta/Elev= 30
 -3981.5   147.9 -3229.8  131.62 -2529.9  132.04 -2406.2  132.74 -2357.7  131.55
 -1200.4  137.64   262.4  134.68   503.1  131.24   687.7  119.64  1000.1  124.77
  1122.8  111.93  1629.6  112.08  1787.8  120.08  2438.2  120.83    2598  120.22
    2890  119.48  4683.7  121.82  4796.8  111.58    4854  118.82  4908.1  116.42
  4908.1  116.43  4998.2  108.93  5073.8  110.51 5091.32  117.19  5094.6  118.99
  5250.7  109.54  5285.9  121.44    6493  118.33    7917  134.36  8739.7  160.85
#Mann= 14 ,-1 , 0
 -3981.5     .12       0 -3229.8      .1       0 -2529.9     .12       0
 -2406.2      .1       0 -2357.7     .12       0  1000.1      .1       0
  1122.8     .05       0  1629.6     .12       0  2438.2      .1       0
    2598     .12       0    2890      .1       0    4854     .07       0
  5094.6      .1       0    7917     .05       0
Bank Sta=4908.1,5091.32
XS Rating Curve= 0 ,0
Exp/Cntr=0.3,0.1

Type RM Length L Ch R = 1 ,253000  ,1000,1000,1000
BEGIN DESCRIPTION:
WFSJ Main 252.0
END DESCRIPTION:
XS GIS Cut Line= 4
      3833195.77      10098004.1      3832792.99     10097358.26
      3827024.34      10091551.7      3823613.96     10089222.99
#Sta/Elev= 30
 -3946.1  144.77 -3162.6  132.47 -2497.3   132.3 -2289.1  131.82   208.1  137.61
   363.8  136.14    1152  121.16  1186.6  111.19  1843.2  113.83  1900.8  123.08
  2637.3  120.15  4594.9  120.21  4693.9  109.48  4736.3  121.18 4889.35  117.65
  4891.9  116.61  4998.2  106.92  5077.7   116.5  5148.5  115.63  5331.3  114.27
  5443.2  113.81  5493.5  107.42  5589.1  119.66  5649.8  112.42  5990.9  113.17
  6440.1  122.39  8142.1   126.1  8276.7  130.49  8461.8   139.9  9129.6  159.77
#Mann= 19 ,-1 , 0
 -3946.1     .12       0 -3162.6      .1       0 -2497.3     .12       0
 -2289.1     .12       0   208.1     .05       0   363.8     .12       0
    1152     .05       0  1843.2     .12       0  2637.3      .1       0
 4889.35     .05       0  5148.5      .1       0  5331.3      .1       0
  5443.2     .12       0  5649.8      .1       0  5990.9     .05       0
  6440.1      .1       0  8142.1     .05       0  8276.7     .12       0
  8461.8     .05       0
Bank Sta=4891.9,5077.7
XS Rating Curve= 0 ,0
Exp/Cntr=0.3,0.1

Type RM Length L Ch R = 1 ,252000  ,942,942,942
BEGIN DESCRIPTION:
WFSJ Main 251.0
END DESCRIPTION:
XS GIS Cut Line= 3
      3833591.57     10097983.23      3826960.74     10090557.33
      3823926.51     10088806.36
#Sta/Elev= 30
 -4955.5  146.85   -4512   134.8 -3943.2  133.02 -3370.3  131.88 -1842.3  133.49
  -558.8   126.9  -420.4  126.36   461.5   121.9   494.9  111.51  1163.6  113.52
  4390.6  120.49  4673.2  111.28  4723.4  120.73  4786.9  114.05  4872.2   120.1
  4886.4  116.81  4907.3  109.08  4998.2  108.02  5211.2  108.63 5234.87  117.04
  5241.3  119.45  5343.3   119.1  5417.9  108.52  5482.2  118.26  5621.5  116.06
  5980.5  120.39  6116.6  122.04  7418.3  141.07    7910  148.94  8503.2  158.44
#Mann= 17 ,-1 , 0
 -4955.5     .12       0 -3943.2      .1       0 -3370.3     .12       0
  -558.8     .05       0  -420.4     .12       0   461.5     .05       0
  1163.6      .1       0  4390.6     .05       0  4872.2     .03       0
  5241.3     .05       0  5482.2      .1       0  5482.2     .12       0
  5621.5      .1       0  5980.5     .05       0  6116.6      .1       0
  7418.3     .12       0    7910     .05       0
Bank Sta=4886.4,5234.87
XS Rating Curve= 0 ,0
Exp/Cntr=0.3,0.1

Type RM Length L Ch R = 1 ,251058  ,1058,1058,1058
BEGIN DESCRIPTION:
WFSJ Main 250.0
END DESCRIPTION:
XS GIS Cut Line= 5
      3833702.72     10097962.45      3827559.31     10089965.21
      3826817.12     10089470.41      3825593.16     10089314.16
       3824071.3     10088182.52
#Sta/Elev= 30
 -4868.9  146.22 -3864.7  139.34 -3409.7  136.23  -230.2  127.74    85.4  124.59
   284.6  117.92   460.6  120.28   776.8  121.57   812.1  111.62  1382.4  112.25
  2153.4  119.15  4684.7  121.38  4713.7  121.13  4752.6  109.04  4892.3  116.27
  4998.2  107.47  5062.6  108.82 5069.26  116.46  5077.1   118.7    5139   119.2
  5325.5  115.56  5556.7  117.82  5672.4  116.65  6352.8  117.39  6835.2   120.4
  7433.3  121.26  7611.6  122.86  7783.3   124.4  8109.4  127.32    9238  146.18
#Mann= 20 ,-1 , 0
 -4868.9     .12       0 -3864.7      .1       0 -3409.7     .12       0
  -230.2     .05       0    85.4     .12       0   460.6     .05       0
  1382.4      .1       0  4752.6      .1       0  4892.3     .07       0
  5077.1      .1       0    5139     .05       0  5325.5     .12       0
  5556.7      .1       0  5672.4      .1       0  6352.8     .05       0
  6835.2     .05       0  7433.3      .1       0  7611.6     .05       0
  7783.3     .12       0  8109.4     .05       0
Bank Sta=4892.3,5069.26
XS Rating Curve= 0 ,0
Exp/Cntr=0.3,0.1

Type RM Length L Ch R = 1 ,250000  ,1000,1000,1000
BEGIN DESCRIPTION:
WFSJ Main 249.0
END DESCRIPTION:
XS GIS Cut Line= 3
      3833853.76     10097813.48      3828279.41     10089384.85
      3824666.23     10086542.62
#Sta/Elev= 30
 -5105.2  142.17 -3862.3  130.56 -2351.5  131.31 -1602.4  128.99 -1330.9  127.43
  -940.7  125.19  -312.7  120.57   540.7  120.83   928.8  120.87  1020.9  120.88
  1135.3  110.76  2112.2  111.12  3229.7  119.97 4810.36116.6393  4815.6  116.52
  4851.7  107.72  4998.2  106.85  5081.8  109.26 5107.68115.8818    5154  119.35
    5479   115.2  6153.5  117.93  6830.9  121.14  8049.5  125.73  8536.9  127.56
    8818  128.62  8884.4  128.87  9087.2  147.25    9388   152.7  9597.1  155.56
#Mann= 20 ,-1 , 0
 -5105.2     .12       0 -3862.3     .12       0 -2351.5     .12       0
 -1602.4      .1       0 -1330.9     .05       0  -940.7     .12       0
  -312.7     .12       0   540.7     .12       0   928.8     .05       0
  2112.2      .1       0 4810.36     .07       0    5154      .1       0
    5479      .1       0  6153.5     .05       0  6830.9      .1       0
  8049.5     .12       0  8536.9      .1       0    8818     .05       0
  9087.2     .12       0    9388     .05       0
Bank Sta=4815.6,5107.68
XS Rating Curve= 0 ,0
Exp/Cntr=0.3,0.1

Type RM Length L Ch R = 1 ,249000  ,1000,1000,1000
BEGIN DESCRIPTION:
WFSJ Main 248.0
END DESCRIPTION:
XS GIS Cut Line= 3
      3834062.08     10097813.45       3829257.4     10089234.81
      3825687.08     10085730.13
#Sta/Elev= 30
 -4832.5  142.24 -3672.4   131.1 -1503.9  127.35 -1265.1   124.5  -272.2  131.51
   -13.3   126.5   535.2  118.38  1223.9  116.65  1540.1  118.23  2881.3  120.77
  3106.7  111.42  3327.1  112.79  4906.9  115.71 4908.69115.7532  4935.5  107.83
  4998.2  106.53    5066  107.51 5100.22 115.895  5101.3  116.35  5427.7  114.18
  6123.1   118.5  7289.8  120.22  7702.9  120.83  8157.2   121.5  8697.2  121.89
  8948.2  122.74  9004.8     115  9068.3  124.61  9467.4  143.82   10003  167.19
#Mann= 19 ,-1 , 0
 -4832.5     .12       0 -3672.4     .12       0 -1503.9      .1       0
 -1265.1     .05       0   -13.3     .05       0   535.2      .1       0
  1223.9     .05       0  1540.1     .12       0  2881.3     .05       0
  3327.1      .1       0  4906.9     .07       0  5101.3      .1       0
  5427.7     .05       0  6123.1     .05       0  7289.8      .1       0
  7702.9     .12       0  8157.2      .1       0  8697.2      .1       0
  9467.4     .05       0
#XS Ineff= 1 ,-1
   -2100  -272.2  131.51
Permanent Ineff=
       F
Bank Sta=4908.69,5100.22
XS Rating Curve= 0 ,0
Exp/Cntr=0.3,0.1

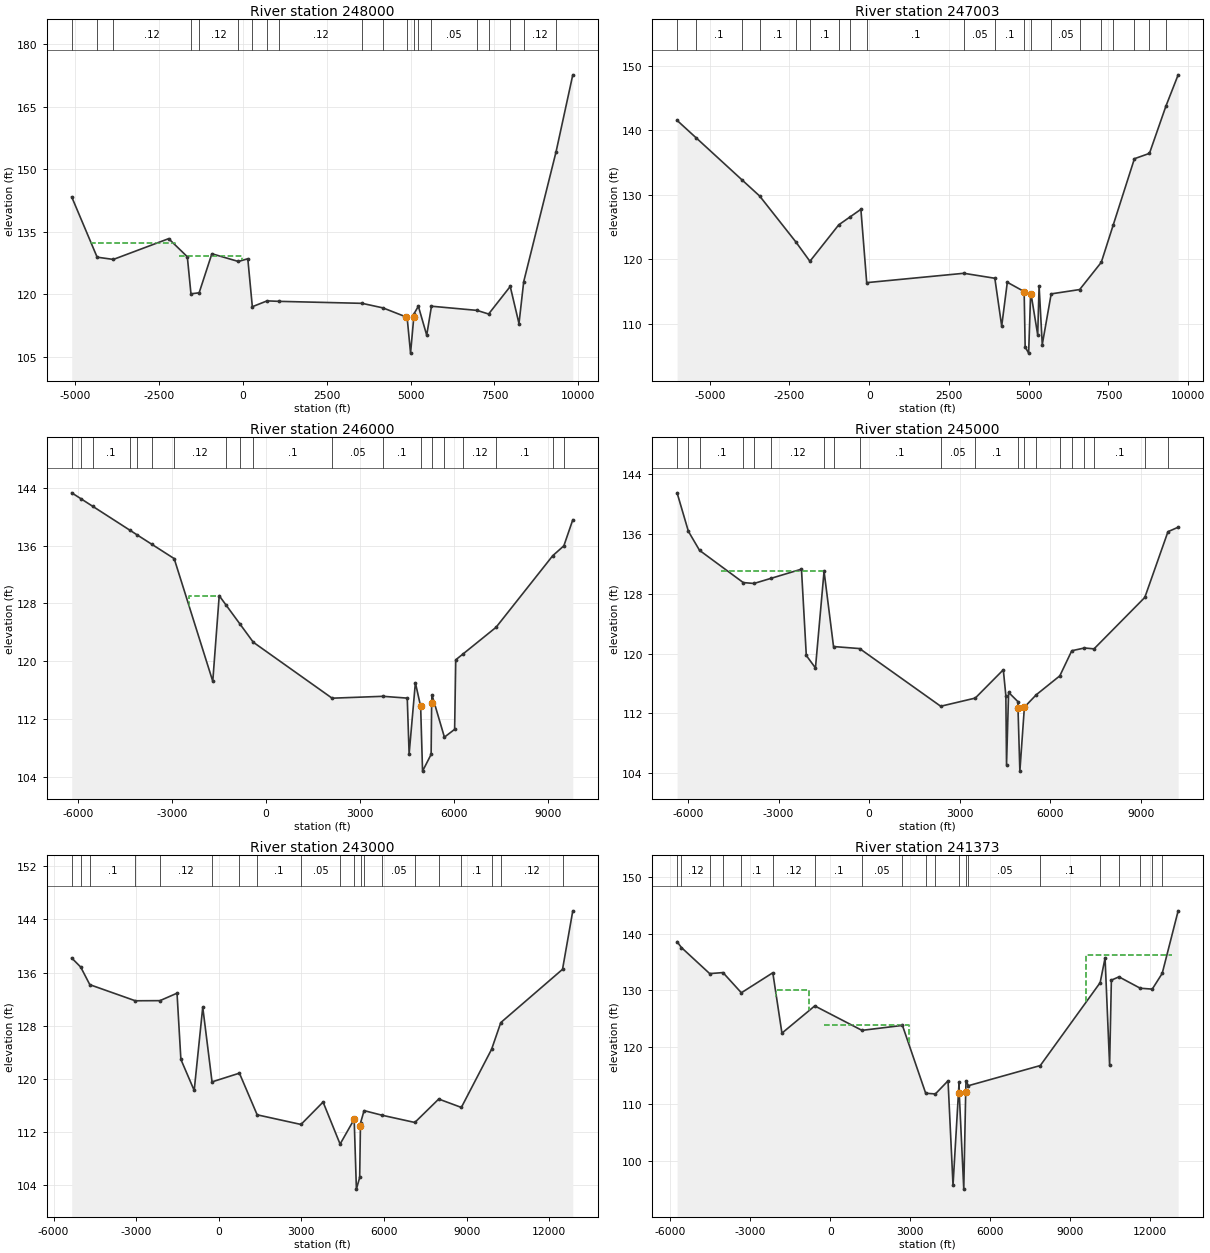
Type RM Length L Ch R = 1 ,248000  ,997,997,997
BEGIN DESCRIPTION:
WFSJ Main 247.0
END DESCRIPTION:
XS GIS Cut Line= 3
      3834286.04     10097912.41      3830083.59     10088720.52
      3827042.02     10084960.25
#Sta/Elev= 30
   -5107  143.37 -4348.9  128.92 -3865.5  128.38 -2216.2  133.36 -1659.3  129.02
 -1550.7  120.13   -1307  120.38  -927.2  129.74  -137.1  127.89   144.2  128.54
   279.4  117.04   718.9  118.44    1066  118.33  3554.7  117.85  4178.9  116.75
 4876.59  114.55 4897.81114.2915  4998.2  105.91 5094.29114.5215  5096.2  115.28
  5230.8  117.16  5479.9  110.21  5621.5  117.16  6979.4  116.16  7326.1  115.29
  7970.7   121.9  8231.6     113  8372.6  123.04  9336.5  154.16  9836.4  172.65
#Mann= 20 ,-1 , 0
   -5107     .12       0 -4348.9      .1       0 -3865.5     .12       0
 -1550.7      .1       0   -1307     .12       0  -137.1     .12       0
   279.4      .1       0   718.9     .12       0    1066     .12       0
  3554.7      .1       0  4178.9      .1       0 4897.81     .07       0
  5096.2      .1       0  5230.8     .12       0  5621.5     .05       0
  6979.4     .05       0  7326.1      .1       0  7970.7     .12       0
  8372.6     .12       0  9336.5     .05       0
#XS Ineff= 2 ,-1
   -1900   -22.4  129.16   -4550 -2037.8  132.37
Permanent Ineff=
       F       F
Bank Sta=4876.59,5094.29
XS Rating Curve= 0 ,0
Exp/Cntr=0.3,0.1

Type RM Length L Ch R = 1 ,247003  ,1003,1003,1003
BEGIN DESCRIPTION:
WFSJ Main 246.0
END DESCRIPTION:
XS GIS Cut Line= 6
      3834503.06     10097825.62      3834780.84      10094978.4
      3832853.75     10092808.26      3830653.48      10088172.6
      3830493.98     10088064.09      3827645.45     10084422.88
#Sta/Elev= 30
 -6023.7  141.54 -5424.3  138.83 -3992.1  132.34 -3434.7  129.82 -2295.3  122.68
 -1859.3  119.71  -954.5  125.36  -587.1  126.63  -260.7  127.76   -78.5   116.4
  2966.5  117.85  3938.7  117.08  4153.8  109.67  4329.9  116.46  4858.1  115.02
  4889.5  106.43  4998.2  105.48  5061.8  114.66  5069.6  114.78  5283.2   108.3
  5326.4  115.92  5425.8   106.8  5705.3  114.66  6598.6  115.33  7276.3  119.55
  7653.1  125.37    8315   135.6  8786.5  136.43  9301.3  143.73  9686.6   148.6
#Mann= 20 ,-1 , 0
 -6023.7     .12       0 -5424.3      .1       0 -3992.1     .12       0
 -3434.7      .1       0 -2295.3      .1       0 -1859.3      .1       0
  -954.5     .12       0  -587.1     .05       0   -78.5      .1       0
  2966.5     .05       0  3938.7      .1       0  4858.1     .07       0
  5069.6      .1       0  5705.3     .05       0  6598.6      .1       0
  7276.3     .12       0  7653.1      .1       0    8315     .05       0
  8786.5     .05       0  9301.3     .12       0
#XS Ineff= 1 ,-1
   -3290  -260.7  127.76
Permanent Ineff=
       F
Bank Sta=4858.1,5061.8
XS Rating Curve= 0 ,0
Exp/Cntr=0.3,0.1

Type RM Length L Ch R = 1 ,246000  ,1000,1000,1000
BEGIN DESCRIPTION:
WFSJ Main 245.0
END DESCRIPTION:
XS GIS Cut Line= 4
      3834772.15     10097999.26      3834850.28     10094314.34
      3831192.11     10087741.51       3827988.3     10084171.11
#Sta/Elev= 30
   -6208  143.31 -5919.6  142.51 -5538.9  141.45 -4357.9  138.16 -4114.6  137.48
 -3656.3  136.21 -2935.3  134.21 -1702.6  117.24 -1496.8  129.08 -1280.9   127.8
  -830.4  125.14    -408  122.64  2108.7   114.9  3731.2  115.16  4509.5  114.91
    4569  107.18  4769.1  117.04  4937.2  113.76  4998.2  104.81  5272.2  107.13
 5288.46  114.19 5298.26115.3689  5696.4  109.51  6022.7  110.59  6058.6  120.21
    6286     121  7346.9  124.71  9155.8  134.61  9511.9  135.98  9797.1  139.58
#Mann= 19 ,-1 , 0
   -6208     .12       0 -5919.6     .12       0 -5538.9      .1       0
 -4357.9      .1       0 -4114.6     .12       0 -3656.3      .1       0
 -2935.3     .12       0 -1280.9      .1       0  -830.4     .12       0
    -408      .1       0  2108.7     .05       0  3731.2      .1       0
  4937.2     .05       0 5298.26      .1       0  5696.4     .05       0
    6286     .12       0  7346.9      .1       0  9155.8     .12       0
  9511.9     .12       0
#XS Ineff= 1 ,-1
   -2450 -1496.8  129.08
Permanent Ineff=
       F
Bank Sta=4937.2,5288.46
XS Rating Curve= 0 ,0
Exp/Cntr=0.3,0.1

Type RM Length L Ch R = 1 ,245000  ,2000,2000,2000
BEGIN DESCRIPTION:
WFSJ Main 244.0
END DESCRIPTION:
XS GIS Cut Line= 4
      3834915.38     10098064.32      3834915.38      10093728.4
       3831935.4      10087362.6       3828378.9     10083507.02
#Sta/Elev= 30
 -6364.7  141.45   -5990  136.31 -5619.7  133.77 -4170.7  129.47 -3817.2  129.35
 -3238.3  130.05 -2241.4  131.26 -2081.4  119.74 -1777.8  118.07 -1492.7  130.99
 -1178.7  120.93  -313.6  120.66  2374.4  112.96  3519.4  114.05  4449.6  117.83
  4533.4  114.38  4556.2  105.16  4624.7  114.81  4932.6  113.58 4935.87  112.74
  4998.2   104.3  5148.1  112.84  5543.3   114.5  6322.6  117.02    6719  120.37
  7138.2  120.74  7456.2  120.62  9140.1  127.49  9907.1  136.26 10245.4  136.86
#Mann= 20 ,-1 , 0
 -6364.7     .12       0   -5990     .12       0 -5619.7      .1       0
 -4170.7     .12       0 -3817.2      .1       0 -3238.3     .12       0
 -1492.7     .12       0 -1178.7      .1       0  -313.6      .1       0
  2374.4     .05       0  3519.4      .1       0  4932.6     .07       0
  5148.1      .1       0  5543.3      .1       0  6322.6     .05       0
    6719     .12       0  7138.2     .12       0  7456.2      .1       0
  9140.1     .12       0  9907.1     .12       0
#XS Ineff= 1 ,-1
   -4900 -1490.7  131.03
Permanent Ineff=
       F
Bank Sta=4935.87,5148.1
XS Rating Curve= 0 ,0
Exp/Cntr=0.3,0.1

Type RM Length L Ch R = 1 ,243000  ,1627,1627,1627
BEGIN DESCRIPTION:
WFSJ Main 242.0
END DESCRIPTION:
XS GIS Cut Line= 4
      3834980.49      10098025.3      3834980.49     10093676.32
        3833426.     10087890.59      3830657.58     10080538.33
#Sta/Elev= 30
 -5339.9  138.18 -5014.2  136.82 -4682.8  134.17 -3030.5  131.75 -2134.5  131.77
 -1515.7  132.89 -1375.7  122.94  -892.3  118.27  -581.7  130.79  -244.2  119.56
   749.7  120.87  1394.5  114.61  2985.2  113.16    3788  116.53  4405.9  110.21
 4911.79113.8956  4916.7  114.03  4998.2  103.44    5117  105.19 5144.79112.9325
  5147.3  113.38  5277.5  115.24  5926.1  114.55  7119.4  113.46  7987.8  116.98
  8809.3  115.72  9906.8  124.45   10241  128.47 12483.5  136.48 12856.2  145.27
#Mann= 20 ,-1 , 0
 -5339.9     .12       0 -5014.2     .12       0 -4682.8      .1       0
 -3030.5      .1       0 -2134.5     .12       0  -244.2      .1       0
   749.7     .12       0  1394.5      .1       0  2985.2     .05       0
  4405.9      .1       0 4911.79     .07       0  5147.3     .12       0
  5277.5     .05       0  5926.1     .05       0  7119.4      .1       0
  7987.8      .1       0  8809.3      .1       0  9906.8    .075       0
   10241     .12       0 12483.5     .05       0
#XS Ineff= 1 ,-1
   -1700  -581.7  130.79
Permanent Ineff=
       F
Bank Sta=4916.7,5144.79
XS Rating Curve= 0 ,0
Exp/Cntr=0.3,0.1

Type RM Length L Ch R = 1 ,241373  ,1134,1134,1134
BEGIN DESCRIPTION:
WFSJ Main 240.0
END DESCRIPTION:
XS GIS Cut Line= 3
      3835145.42     10098033.98       3835110.7      10088103.4
       3830970.4     10080265.48
#Sta/Elev= 30
 -5751.5  138.57 -5589.6  137.55 -4528.6  132.96 -4029.5  133.14 -3341.1  129.59
 -2160.9  133.11 -1818.6  122.49  -587.4  127.28  1182.9  122.98  2701.5  123.85
  3573.5  111.92  3936.7   111.8  4411.8  114.11  4598.6   95.75  4826.4  113.88
 4832.48111.8833  5001.9   95.06  5074.3  112.06  5086.5   114.1  5176.1  113.25
    7872  116.79 10117.8  131.37 10301.8  135.71 10472.2  116.83 10538.3  131.81
 10823.1  132.39 11620.6  130.39 12071.7  130.23 12445.2     133 13043.4     144
#Mann= 20 ,-1 , 0
 -5751.5     .12       0 -5589.6     .12       0 -4528.6     .05       0
 -4029.5     .05       0 -3341.1      .1       0 -2160.9     .12       0
  -587.4      .1       0  1182.9     .05       0  2701.5     .05       0
  3573.5     .12       0  3936.7      .1       0  4826.4     .07       0
  5086.5      .1       0  5176.1     .05       0    7872      .1       0
 10117.8    .075       0 10823.1     .05       0 11620.6     .12       0
 12071.7     .12       0 12445.2     .05       0
#XS Ineff= 3 ,-1
    -227  2951.5  123.88   -2025  -818.6  130.07  9586.6   12805  136.19
Permanent Ineff=
       F       F       F
Bank Sta=4832.48,5074.3
XS Rating Curve= 0 ,0
Exp/Cntr=0.3,0.1

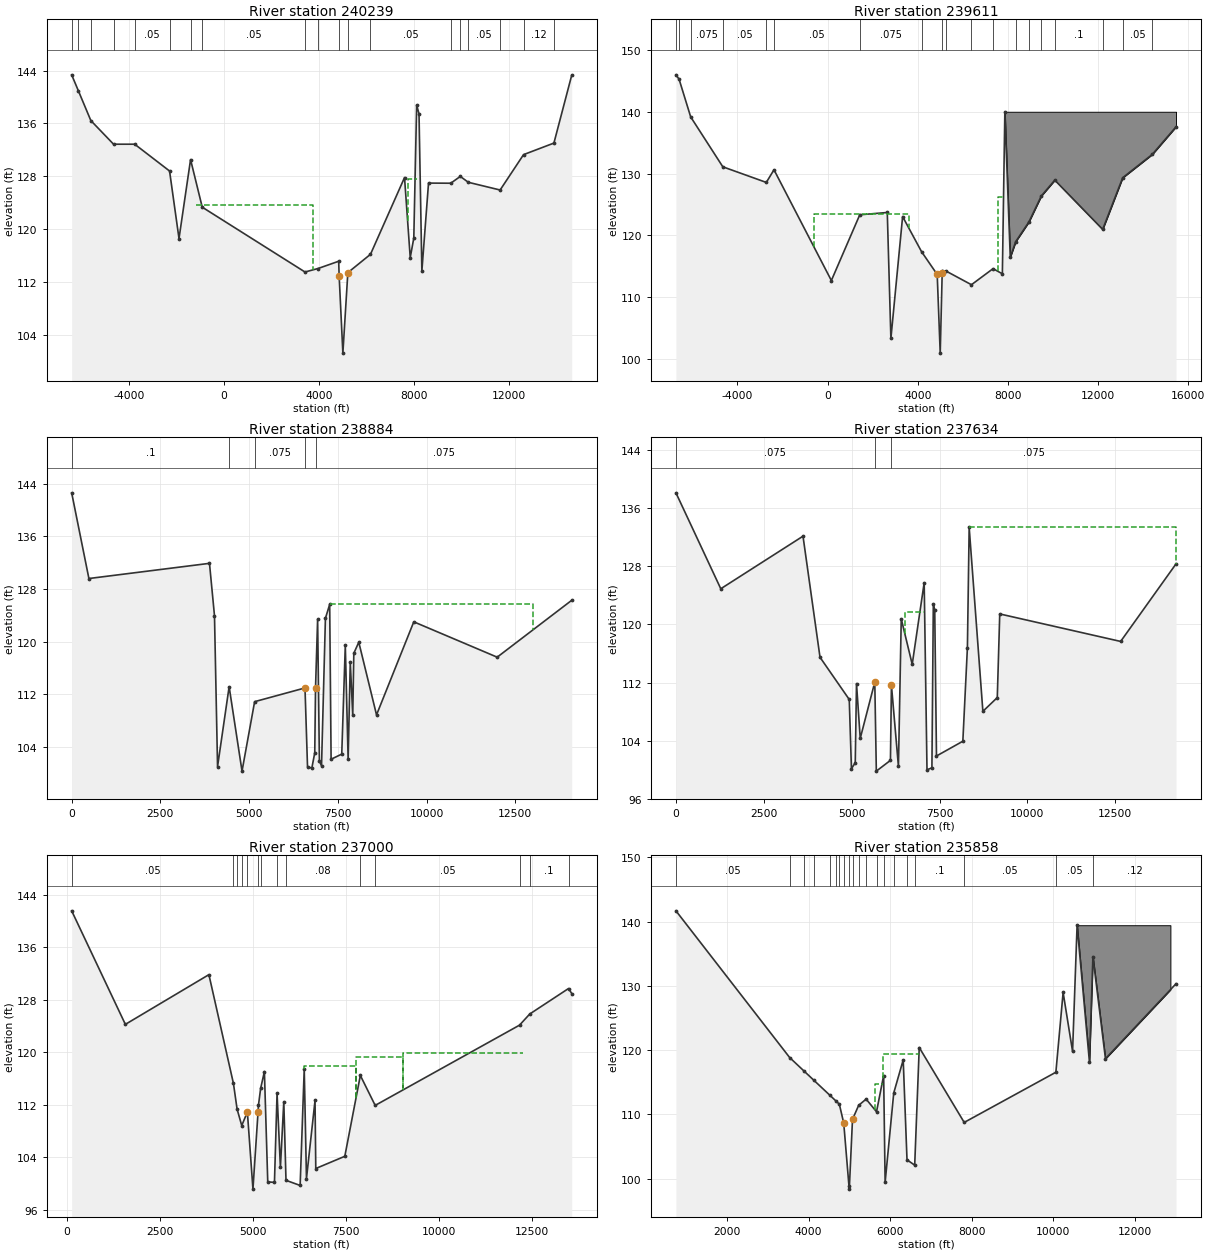
Type RM Length L Ch R = 1 ,240239  ,628,628,628
BEGIN DESCRIPTION:
WFSJ Main 239.0
END DESCRIPTION:
XS GIS Cut Line= 6
      3835358.09     10098077.31      3835283.44     10094579.09
      3835556.88     10087274.41      3835231.36     10085425.45
      3835214.86      10081228.4      3831921.76     10078677.22
#Sta/Elev= 30
 -6417.1  143.36 -6134.8  140.94 -5610.1  136.43 -4654.4  132.85 -3764.8  132.85
 -2296.9  128.79 -1899.3  118.56 -1412.6  130.52  -921.3  123.31    3403  113.49
  3954.2  114.02  4822.6  115.12 4840.72  112.94  4998.2   101.2  5207.4  113.39
  6160.5  116.17  7593.5   127.8  7833.5  115.67  7983.5  118.63  8103.5   138.8
  8203.5  137.43  8323.5  113.65  8603.5  126.96    9540  126.94  9940.8  127.97
 10278.3  127.08 11616.9  125.91 12603.2  131.27 13881.3  133.02 14631.9  143.32
#Mann= 19 ,-1 , 0
 -6417.1    .075       0 -6134.8    .075       0 -5610.1      .1       0
 -4654.4    .075       0 -3764.8     .05       0 -2296.9    .075       0
 -1412.6    .075       0  -921.3     .05       0    3403    .075       0
  3954.2     .07       0  4822.6     .06       0  5207.4     .07       0
  6160.5     .05       0    9540      .1       0  9940.8    .075       0
 10278.3     .05       0 11616.9      .1       0 12603.2     .12       0
 13881.3     .12       0
#XS Ineff= 4 ,-1
  8103.5   14505   138.8  7723.5    8103  127.53   -1175  3744.5  123.62
   -3100 -1412.6  130.52
Permanent Ineff=
       F       F       F       F
Bank Sta=4840.72,5207.4
XS Rating Curve= 0 ,0
Exp/Cntr=0.3,0.1

Type RM Length L Ch R = 1 ,239611  ,727,727,727
BEGIN DESCRIPTION:
WFSJ Main 238.0
END DESCRIPTION:
XS GIS Cut Line= 6
      3835540.39     10098181.51      3835843.34     10094592.12
      3836077.71     10087339.51      3835804.27     10084774.41
      3835975.84      10080407.8      3832063.86     10078441.96
#Sta/Elev= 30
 -6726.8     146 -6588.2   145.3 -6072.1  139.18 -4646.8   131.1 -2717.1  128.57
 -2377.2  130.62   168.8  112.68  1429.6  123.33  2649.7   123.7  2809.8  103.29
    3330  123.04  4170.8  117.35  4864.4  113.66  4998.2  100.92  5085.7  113.89
 5096.59114.2756    5263   114.2  6383.6     112  7341.7   114.6  7755.6  113.77
  7865.7  140.02  8105.9  116.46  8347.2  118.98  8933.2  122.17  9485.7  126.39
 10081.2  128.94 12205.4  120.96 13093.4  129.33 14406.7  133.11 15459.6  137.58
#Mann= 19 ,-1 , 0
 -6726.8    .075       0 -6588.2      .1       0 -6072.1    .075       0
 -4646.8     .05       0 -2717.1    .075       0 -2377.2     .05       0
  1429.6    .075       0  4170.8     .05       0 5096.59     .07       0
    5263     .05       0  6383.6     .05       0  7341.7      .1       0
  8347.2     .05       0  8933.2    .075       0  9485.7      .1       0
 10081.2      .1       0 12205.4     .05       0 13093.4     .05       0
 14406.7     .12       0
#XS Ineff= 2 ,-1
    -600  3600.9  123.47  7565.5    7877  126.26
Permanent Ineff=
       F       F
#Block Obstruct= 1 ,-1
  7865.7 15459.6  140.02
Bank Sta=4864.4,5085.7
XS Rating Curve= 0 ,0
Exp/Cntr=0.3,0.1

Type RM Length L Ch R = 1 ,238884  ,1250,1250,1250
XS GIS Cut Line= 6
      3838815.12     10092642.79      3837640.86     10089039.06
      3836425.58      10088062.5      3836574.72     10087064.54
       3836676.3     10086534.86      3836775.19     10079339.84
#Sta/Elev= 30
       0  142.64   485.6   129.6  3883.9  131.91    4025  123.93  4111.3  100.98
  4437.7  113.14  4800.9  100.29  5156.1  110.86  6575.6  112.95  6646.9  100.94
  6768.6  100.76  6850.6  103.07 6872.65  112.99  6931.4   123.4  6981.4  101.84
  7041.4  101.09  7151.4  123.55  7271.4  125.66  7311.4   102.1  7611.5  102.88
  7711.5  119.43  7791.5  102.07  7851.5   116.9  7921.5  108.78  7951.5  118.22
  8091.5  119.91  8591.6  108.85  9641.7  123.01 11991.9  117.63 14093.3  126.29
#Mann= 5 ,-1 , 0
       0      .1       0  4437.7    .075       0  5156.1    .075       0
  6575.6     .06       0 6872.65    .075       0
#XS Ineff= 2 ,-1
  6931.4  7271.3   123.4  7271.4   13005  125.66
Permanent Ineff=
       F       F
Bank Sta=6575.6,6872.65
XS Rating Curve= 0 ,0
Exp/Cntr=0.3,0.1

Type RM Length L Ch R = 1 ,237634  ,634,634,634
XS GIS Cut Line= 6
      3839199.79     10092449.24      3837409.43     10088423.63
      3836526.81     10087766.08      3837079.82     10087445.14
      3836917.49     10086599.22      3836866.89       10079385.
#Sta/Elev= 30
       0  138.08  1276.1  124.89  3615.7  132.12  4099.7  115.47  4931.5  109.67
    4994  100.15  5102.4  100.98  5137.9  111.86  5244.2  104.32  5658.1  112.06
  5702.2   99.82  6103.7   101.3  6132.1  111.62    6331  100.48  6411.4  120.75
  6723.2   114.5  7063.8  125.73  7143.8     100  7283.8  100.28  7323.8  122.77
  7363.8  121.96  7413.8   101.9  8163.8  103.93  8293.8  116.81  8343.8  133.33
  8733.9  108.04  9143.9  109.93  9213.9  121.43 12653.9  117.65 14229.5  128.31
#Mann= 3 , 0 , 0
       0    .075       0  5658.1     .06       0  6132.1    .075       0
#XS Ineff= 3 ,-1
  8343.8 14229.5  133.33  7063.8  8343.7  125.73  6517.2  7063.7  121.72
Permanent Ineff=
       F       F       F
Bank Sta=5658.1,6132.1
XS Rating Curve= 0 ,0
Exp/Cntr=0.3,0.1

Type RM Length L Ch R = 1 ,237000  ,1142,1142,1142
BEGIN DESCRIPTION:
WFSJ Main 236.0
END DESCRIPTION:
XS GIS Cut Line= 3
      3839487.86     10092295.55      3837245.54     10087966.86
      3836905.42     10079405.51
#Sta/Elev= 30
     125  141.56  1568.4  124.27  3814.2  131.84  4473.7  115.27    4572  111.36
    4697  108.86  4848.4  110.92  4998.2   99.18  5135.9  110.98  5145.9  111.94
  5205.9  114.55    5306  117.08  5396.1  100.29  5576.4   100.2  5646.3  113.76
  5736.4  102.49  5827.5   112.5  5886.4  100.52  6266.8   99.74  6376.9  117.48
  6436.9  100.79  6667.1  112.68  6687.1  102.32  7467.7  104.18  7885.2  116.49
    8284  111.93 12163.9  124.15 12439.8  125.85 13481.8  129.73 13568.1  128.97
#Mann= 14 ,-1 , 0
     125     .05       0  4473.7     .05       0    4572     .09       0
    4697      .1       0  4848.4    .065       0  5145.9      .1       0
  5205.9      .1       0  5646.3     .08       0  5886.4     .08       0
  7885.2      .1       0    8284     .05       0 12163.9    .075       0
 12439.8      .1       0 13481.8     .12       0
#XS Ineff= 3 ,-1
  6376.9  7767.9  117.89    7768    9038  119.36    9039   12245  119.88
Permanent Ineff=
       F       F       F
Bank Sta=4848.4,5135.9
XS Rating Curve= 0 ,0
Exp/Cntr=0.3,0.1

Type RM Length L Ch R = 1 ,235858  ,858,858,858
BEGIN DESCRIPTION:
WFSJ Main 235.0
END DESCRIPTION:
XS GIS Cut Line= 3
      3839939.26     10091193.69      3837988.66     10087297.74
      3836988.05     10079454.69
#Sta/Elev= 30
     747  141.67  3535.6  118.84    3896  116.69  4129.7   115.3  4526.8  112.94
  4680.8  112.02  4753.6  111.59 4861.89  108.64    4990   98.86  4998.2   98.36
 5076.92  109.21  5227.8   111.4 5411.12  112.37  5665.9   110.4  5840.8  116.04
  5876.9    99.4  6088.2  113.32  6320.4  118.47  6413.6  102.92  6602.3  102.09
  6713.6   120.4  7816.2  108.74 10064.4  116.55   10242  128.97 10473.8  119.79
 10584.7  139.43 10887.1  118.19 10972.8  134.54 11280.3  118.66 13010.6  130.32
#Mann= 20 ,-1 , 0
     747     .05       0  3535.6     .05       0    3896     .12       0
  4129.7      .1       0  4526.8      .1       0  4680.8      .1       0
  4753.6      .1       0 4861.89     .07       0    4990     .07       0
 5076.92      .1       0  5227.8      .1       0 5411.12     .08       0
  5665.9     .05       0  5840.8      .1       0  6088.2     .05       0
  6413.6     .05       0  6602.3      .1       0  7816.2     .05       0
 10064.4     .05       0 10972.8     .12       0
#XS Ineff= 3 ,-1
  5621.9    5825  114.78  5826.5  6713.5  119.32  6713.6   10239   120.4
Permanent Ineff=
       F       F       F
#Block Obstruct= 1 ,-1
 10584.7 12873.1  139.43
Bank Sta=4861.89,5076.92
XS Rating Curve= 0 ,0
Exp/Cntr=0.3,0.1

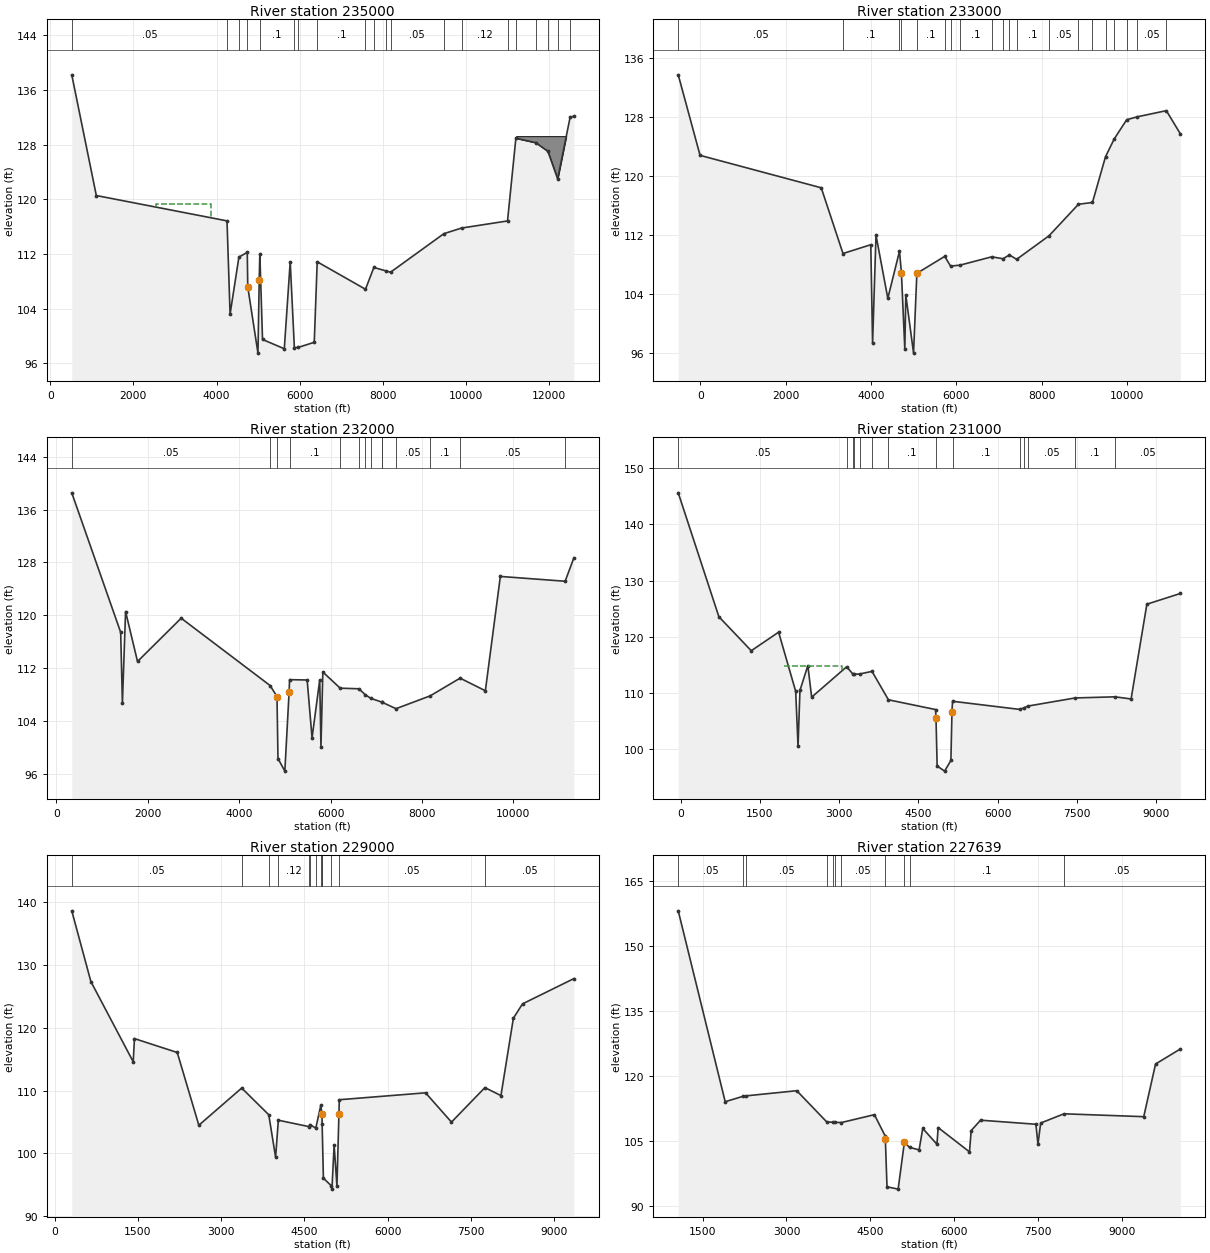
Type RM Length L Ch R = 1 ,235000  ,2000,2000,2000
BEGIN DESCRIPTION:
WFSJ Main 234.0
END DESCRIPTION:
XS GIS Cut Line= 3
      3840617.85     10090811.07      3838471.48     10086873.58
      3837139.78     10079388.11
#Sta/Elev= 30
   515.5  138.23  1106.5  120.56  4252.8  116.85  4326.9   103.2  4539.5  111.55
  4740.8  112.24  4752.3  107.19  4998.2   97.49 5028.24  108.24  5043.2  112.01
  5107.8   99.49  5632.3   98.13  5774.5  110.86  5874.4    98.3  5964.9   98.32
  6353.4   99.08  6424.5  110.86    7587  106.84  7788.2  110.03  8089.9  109.51
  8189.7  109.33  9474.4  114.98  9900.1   115.8 11006.3  116.84 11207.5  128.95
 11684.3   128.3 11977.6  127.04 12213.2  122.99 12514.9  132.07   12603  132.14
#Mann= 20 ,-1 , 0
   515.5     .05       0  4252.8      .1       0  4539.5      .1       0
  4740.8     .07       0  5043.2      .1       0  5874.4     .05       0
  5964.9      .1       0  6424.5      .1       0    7587     .05       0
  7788.2     .12       0  8089.9      .1       0  8189.7     .05       0
  9474.4      .1       0  9900.1     .12       0 11006.3     .05       0
 11207.5     .12       0 11684.3     .05       0 11977.6    .075       0
 12213.2     .05       0 12514.9     .12       0
#XS Ineff= 1 ,-1
    2550  3869.3  119.37
Permanent Ineff=
       F
#Block Obstruct= 1 ,-1
 11214.4   12534  129.25
Bank Sta=4752.3,5028.24
XS Rating Curve= 0 ,0
Exp/Cntr=0.3,0.1

Type RM Length L Ch R = 1 ,233000  ,1000,1000,1000
BEGIN DESCRIPTION:
WFSJ Main 232.0
END DESCRIPTION:
XS GIS Cut Line= 3
      3840779.09       10090720.      3839105.77     10085464.67
      3837700.98     10079376.33
#Sta/Elev= 30
  -515.3  133.73    -3.9  122.81  2835.4  118.41  3344.8   109.5  3996.3  110.69
  4038.3   97.32  4118.3  111.98  4395.1  103.42  4668.6  109.81  4714.1  106.87
  4793.9   96.49    4816  103.91  4998.2   95.99  5075.5  106.81  5728.2  109.11
  5865.4  107.79  6086.1  107.92  6828.8  109.05  7096.2  108.79  7243.1  109.31
  7413.6  108.71  8171.9   111.9  8862.1  116.18  9190.1  116.42  9495.5  122.62
  9699.2  125.03  9991.8  127.64 10242.7  128.04 10921.1  128.87 11248.3  125.74
#Mann= 20 ,-1 , 0
  -515.3     .05       0  3344.8      .1       0  4668.6     .12       0
  4714.1     .07       0  5075.5      .1       0  5728.2      .1       0
  5865.4     .05       0  6086.1      .1       0  6828.8     .05       0
  7096.2      .1       0  7243.1     .05       0  7413.6      .1       0
  8171.9     .05       0  8862.1     .12       0  9190.1     .12       0
  9495.5     .05       0  9699.2     .12       0  9991.8     .12       0
 10242.7     .05       0 10921.1    .075       0
#XS Ineff= 1 ,-1
    1595  2835.4  118.41
Permanent Ineff=
       F
Bank Sta=4714.1,5075.5
XS Rating Curve= 0 ,0
Exp/Cntr=0.3,0.1

Type RM Length L Ch R = 1 ,232000  ,1000,1000,1000
BEGIN DESCRIPTION:
WFSJ Main 231.0
END DESCRIPTION:
XS GIS Cut Line= 3
      3841779.09     10090126.27      3840009.62     10085810.43
      3838622.84     10079641.89
#Sta/Elev= 30
   335.5  138.54    1406  117.43  1443.5  106.67  1512.8  120.58  1774.3  113.02
  2729.7  119.57  4675.9  109.38  4826.4  107.72    4848   98.34  4998.2   96.43
  5091.6  108.41  5101.8  110.27  5486.5  110.22  5593.8  101.46  5761.6  110.24
  5788.6  100.15  5829.6  111.43  6209.7  108.98  6617.8  108.89  6761.4  107.98
    6884  107.43  7115.3  106.89  7121.2  106.87  7431.2  105.88  8179.2  107.82
  8833.4   110.5  9386.2  108.59  9714.2  125.89 11132.3  125.16 11322.5  128.69
#Mann= 14 ,-1 , 0
   335.5     .05       0  4675.9      .1       0  4826.4     .07       0
  5101.8      .1       0  6209.7     .05       0  6617.8      .1       0
  6761.4     .05       0    6884      .1       0  7115.3     .05       0
  7121.2      .1       0  7431.2     .05       0  8179.2      .1       0
  8833.4     .05       0 11132.3    .075       0
#XS Ineff= 1 ,-1
     830  2729.7  119.57
Permanent Ineff=
       F
Bank Sta=4826.4,5091.6
XS Rating Curve= 0 ,0
Exp/Cntr=0.3,0.1

Type RM Length L Ch R = 1 ,231000  ,2000,2000,2000
BEGIN DESCRIPTION:
WFSJ Main 230.0
END DESCRIPTION:
XS GIS Cut Line= 3
      3843482.23     10089266.93      3840644.78     10085094.76
      3839560.36     10080766.96
#Sta/Elev= 30
   -45.6  145.64   723.7  123.55  1337.2  117.48  1855.1  120.79  2178.4  110.24
    2223  100.44  2259.1  110.41  2408.8  114.82  2480.7   109.2  3143.4  114.62
  3265.5  113.28  3291.4  113.29  3387.6  113.33  3623.6   113.8  3934.8  108.73
  4827.4  106.99  4835.2  105.54  4857.2   96.93  4998.2   96.01  5117.2   97.91
  5137.8  106.51  5148.1  108.47  6416.7  107.02  6493.5  107.26  6575.1  107.61
  7470.1  109.06  8224.8  109.26  8529.5  108.88  8828.5  125.78  9461.6  127.69
#Mann= 14 ,-1 , 0
   -45.6     .05       0  3143.4    .075       0  3265.5     .05       0
  3291.4    .075       0  3387.6     .05       0  3623.6     .12       0
  3934.8      .1       0  4827.4     .07       0  5148.1      .1       0
  6416.7     .05       0  6493.5      .1       0  6575.1     .05       0
  7470.1      .1       0  8224.8     .05       0
#XS Ineff= 1 ,-1
    1960  3049.4  114.81
Permanent Ineff=
       F
Bank Sta=4835.2,5137.8
XS Rating Curve= 0 ,0
Exp/Cntr=0.3,0.1

Type RM Length L Ch R = 1 ,229000  ,1361,1361,1361
BEGIN DESCRIPTION:
WFSJ Main 228.0
END DESCRIPTION:
XS GIS Cut Line= 3
      3844232.23     10088548.18      3842185.14      10084325.3
      3839732.55     10080720.52
#Sta/Elev= 30
   307.1  138.62   651.7  127.36  1415.2  114.59  1437.4  118.28  2209.1  116.07
  2598.4  104.49  3371.2  110.41  3859.1  106.16  3982.3    99.4  4031.8  105.29
  4589.1  104.26  4595.4   104.6  4707.3  104.04  4796.9  107.65  4818.7  106.25
  4821.6  104.68  4844.2   96.07    4990   94.82  4998.2   94.32  5037.5  101.35
  5088.3   94.82 5124.27  106.29  5130.3  108.55  6686.3  109.65  7153.5  104.99
  7756.5  110.48  8045.5  109.21  8269.9  121.53  8434.6  123.81    9360  127.83
#Mann= 13 ,-1 , 0
   307.1     .05       0  3371.2     .12       0  3859.1      .1       0
  4031.8     .12       0  4589.1      .1       0  4595.4     .12       0
  4707.3     .05       0  4796.9     .12       0  4818.7      .1       0
  4821.6     .05       0    4990     .05       0  5130.3     .05       0
  7756.5     .05       0
Bank Sta=4818.7,5124.27
XS Rating Curve= 0 ,0
Exp/Cntr=0.3,0.1

Type RM Length L Ch R = 1 ,227639  ,2017,2017,2017
BEGIN DESCRIPTION:
WFSJ Main 227.0
END DESCRIPTION:
XS GIS Cut Line= 3
      3844857.23     10088345.05      3843107.22     10084470.05
      3840654.97     10080424.61
#Sta/Elev= 30
    1064  158.04  1904.2  113.99  2231.5  115.27  2275.7  115.34  3184.5  116.53
  3722.3  109.31  3832.1  109.26  3864.7  109.24  3982.2  109.18  4573.7     111
 4764.04106.1414  4769.6  105.32    4799   94.36  4998.2   93.82  5109.8  104.59
  5201.6  103.46  5373.1  102.88  5438.7  107.83  5692.8  104.17  5714.1  108.02
  6274.5  102.42  6305.4  107.33  6472.3  109.73    7463  108.79  7499.9  104.18
  7548.4  109.07  7965.1   111.2  9392.3  110.54  9603.7  122.69 10046.5  126.16
#Mann= 11 ,-1 , 0
    1064     .05       0  2231.5      .1       0  2275.7     .05       0
  3722.3      .1       0  3832.1     .05       0  3864.7      .1       0
  3982.2     .05       0 4764.04     .03       0  5109.8     .05       0
  5201.6      .1       0  7965.1     .05       0
Bank Sta=4769.6,5109.8
XS Rating Curve= 0 ,0
Exp/Cntr=0.3,0.1