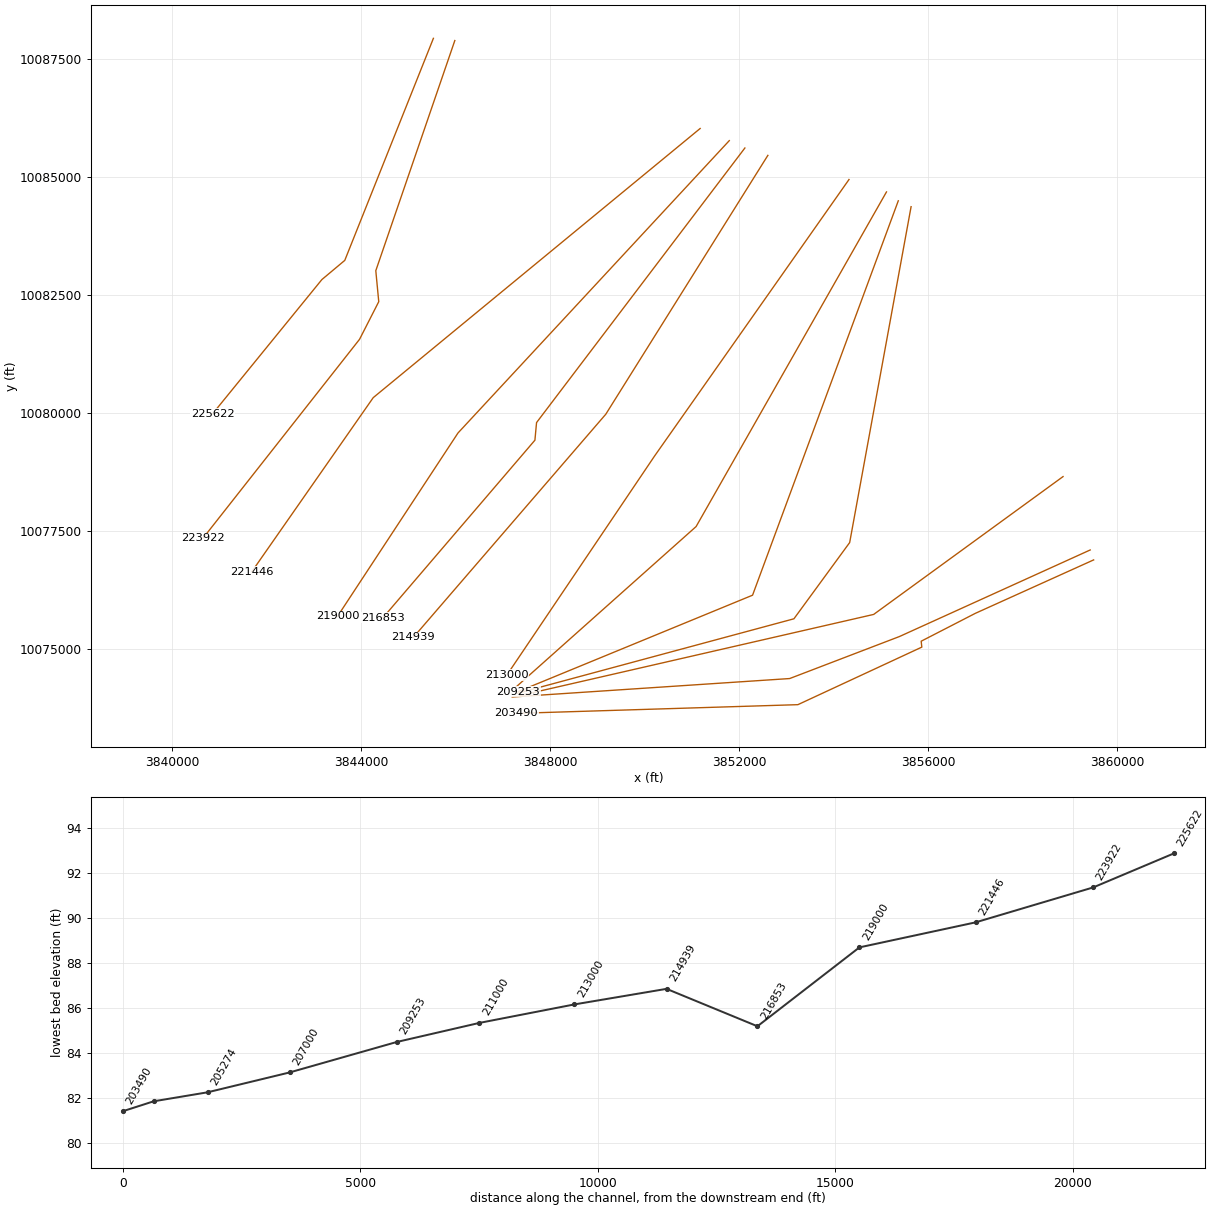
HEC-RAS study WFSJ Main.prj: WFSJ Main Base Level Engineering

--- WFSJ Main.g02 (geometry) --- (continued)

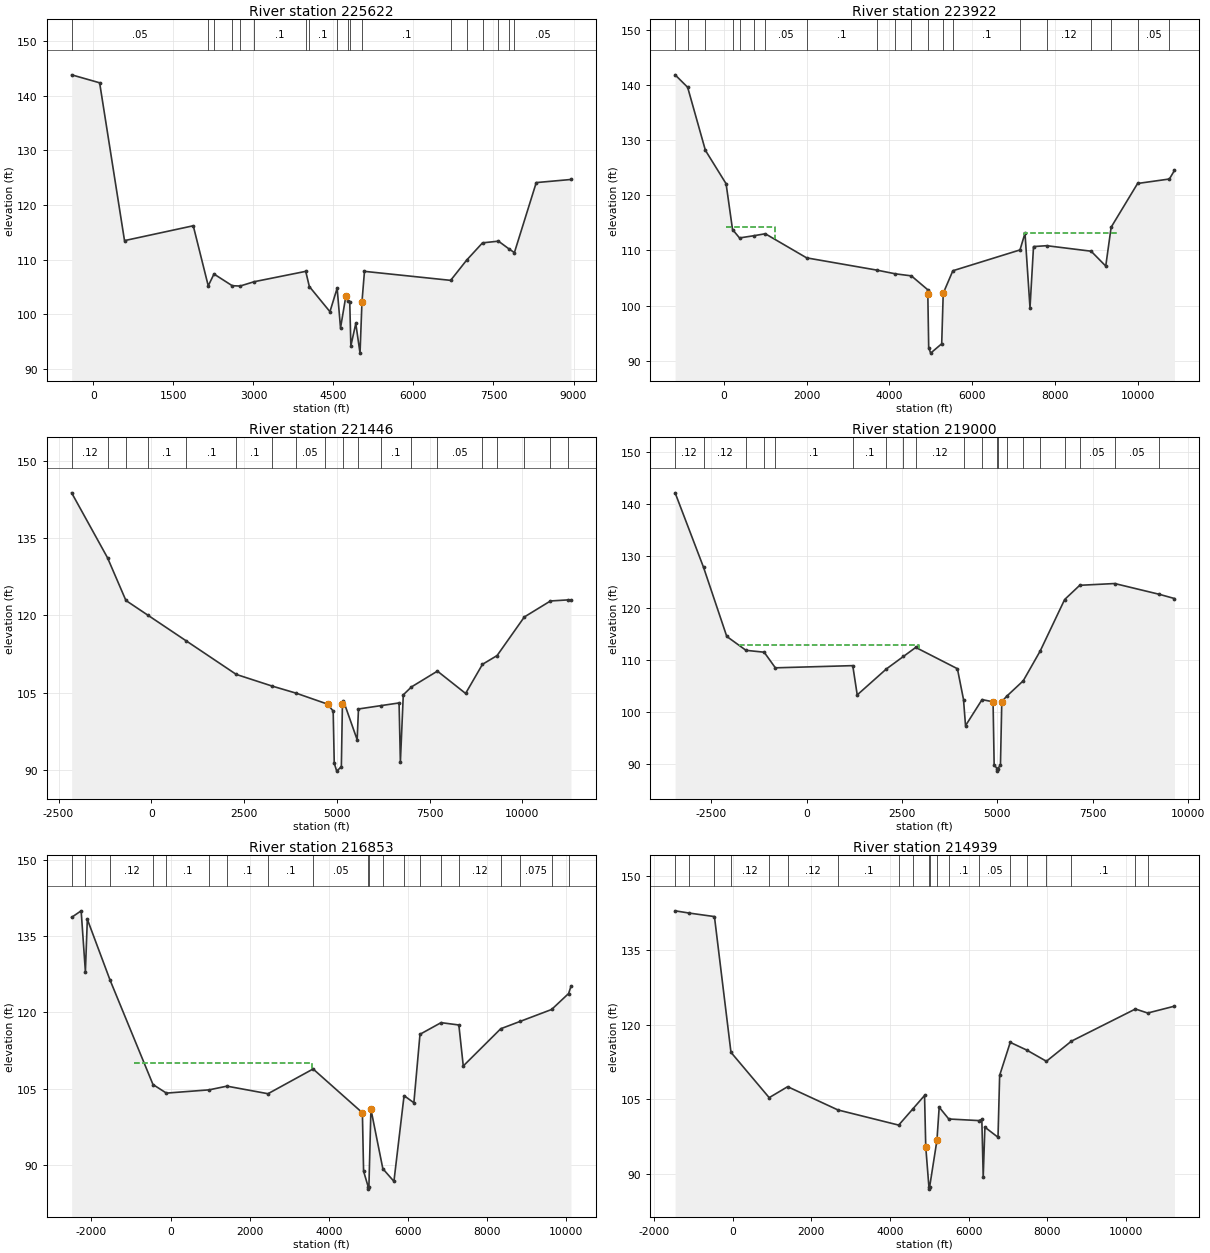
Type RM Length L Ch R = 1 ,225622  ,1700,1700,1700
BEGIN DESCRIPTION:
WFSJ Main 225.0
END DESCRIPTION:
XS GIS Cut Line= 4
      3845529.12     10087938.83       3843654.1     10083235.67
      3843169.72     10082829.42      3840857.38     10079985.86
#Sta/Elev= 30
  -407.7  143.85   117.1  142.39   583.5  113.48  1872.1   116.2    2153   105.2
  2260.5  107.36  2602.5  105.22  2750.3  105.16    3013  105.95  3980.5  107.85
    4048  105.07  4434.3  100.46  4569.2  104.77  4632.6   97.48    4734  103.39
  4777.5  102.49  4805.5  102.23  4826.4   94.19  4918.7    98.3  4998.2   92.87
 5034.53  102.25  5081.4  107.85  6696.8   106.2  6995.5  109.89  7294.2  113.07
    7593  113.38  7790.8  111.96  7891.7  111.28  8301.5  124.11  8952.7  124.68
#Mann= 18 ,-1 , 0
  -407.7     .05       0    2153      .1       0  2260.5     .05       0
  2602.5      .1       0  2750.3     .05       0    3013      .1       0
  3980.5     .05       0    4048      .1       0  4569.2     .05       0
  4777.5      .1       0  4805.5     .07       0 5034.53      .1       0
  6696.8     .12       0  6995.5     .05       0  7294.2     .12       0
    7593     .05       0  7790.8     .12       0  7891.7     .05       0
#XS Ineff= 1 ,-1
     400  1872.1   116.2
Permanent Ineff=
       F
Bank Sta=4734,5034.53
XS Rating Curve= 0 ,0
Exp/Cntr=0.3,0.1

Type RM Length L Ch R = 1 ,223922  ,2476,2476,2476
BEGIN DESCRIPTION:
WFSJ Main 223.0
END DESCRIPTION:
XS GIS Cut Line= 5
      3845982.23     10087891.95      3844310.35     10083016.92
      3844372.85     10082360.67       3843966.6      10081563.8
       3840655.5       10077352.
#Sta/Elev= 30
 -1176.1   141.9  -873.5  139.64  -444.5  128.19    55.7  122.12   211.1  113.81
   379.9  112.28   727.1  112.68  1002.4  113.04  2001.8  108.66  3701.7  106.43
  4146.3  105.76  4532.4  105.39  4922.9   102.9 4929.31  102.14  4950.7   92.36
  4998.2   91.36    5265   93.06 5301.55102.2279  5534.4  106.32  7156.2   110.1
  7277.4  113.14  7398.2   99.59  7483.2  110.71    7801  110.87  8874.9  109.87
  9228.3  107.17  9358.9  114.23  9997.9  122.17 10765.6  122.98 10888.8  124.54
#Mann= 20 ,-1 , 0
 -1176.1     .05       0  -873.5     .12       0  -444.5     .05       0
   211.1     .12       0   379.9     .12       0   727.1     .05       0
  1002.4     .05       0  2001.8      .1       0  3701.7     .05       0
  4146.3      .1       0  4532.4     .05       0  4922.9     .03       0
 5301.55     .05       0  5534.4      .1       0  7156.2     .05       0
    7801     .12       0  8874.9      .1       0  9358.9     .05       0
  9997.9     .05       0 10765.6     .05       0
#XS Ineff= 2 ,-1
  7263.5    9530  113.16      52  1228.2   114.3
Permanent Ineff=
       F       F
Bank Sta=4929.31,5301.55
XS Rating Curve= 0 ,0
Exp/Cntr=0.3,0.1

Type RM Length L Ch R = 1 ,221446  ,2446,2446,2446
BEGIN DESCRIPTION:
WFSJ Main 221.0
END DESCRIPTION:
XS GIS Cut Line= 3
      3851173.23      10086029.2      3844256.05     10080328.07
      3841685.61     10076640.22
#Sta/Elev= 30
 -2146.4  143.77 -1179.4  131.18  -683.6   122.9  -100.8  120.09   949.2  115.03
  2291.2  108.56  3266.7  106.28  3902.5  104.93 4752.45   102.8    4903  101.45
  4931.7   91.35  4998.2   89.81  5123.2   90.66  5151.9  102.77  5180.6  103.43
  5549.3    95.9  5584.8  101.86  6190.2  102.51    6679  103.03  6714.2   91.54
  6792.4   104.6  7011.2  106.13  7712.2   109.2  8472.3  104.87  8926.8  110.52
  9321.3  112.22 10055.3   119.7 10758.9   122.8 11232.3  123.01 11312.7  122.95
#Mann= 19 ,-1 , 0
 -2146.4     .12       0 -1179.4     .12       0  -683.6     .05       0
  -100.8      .1       0   949.2      .1       0  2291.2      .1       0
  3266.7     .12       0  3902.5     .05       0  4670.2     .07       0
  5180.6      .1       0  5584.8     .12       0  6190.2      .1       0
  7011.2     .12       0  7712.2     .05       0  8926.8     .12       0
  9321.3      .1       0 10055.3     .05       0 10758.9    .075       0
 11232.3    .075       0
Bank Sta=4752.45,5151.9
XS Rating Curve= 0 ,0
Exp/Cntr=0.3,0.1

Type RM Length L Ch R = 1 ,219000  ,2147,2147,2147
BEGIN DESCRIPTION:
WFSJ Main 219.0
END DESCRIPTION:
XS GIS Cut Line= 3
      3851789.73     10085772.11      3846049.65     10079579.71
      3843503.47     10075700.37
#Sta/Elev= 30
 -3443.6  142.15 -2698.3  127.83 -2090.2  114.57 -1586.3   111.9 -1110.2  111.54
  -817.3  108.54    1211  108.96    1328  103.34  2092.7  108.33  2539.5  110.73
  2861.7  112.46    3953  108.37  4112.8  102.45  4165.6   97.43    4599  102.44
  4887.3  102.01  4915.6   89.91    4990    89.2  4998.2    88.7    5010    89.2
  5080.7   89.82 5115.74102.0369  5240.8  103.06  5677.7  106.05  6121.2  111.76
  6762.9  121.66  7157.9  124.39  8073.4  124.73  9247.8  122.65  9640.3  121.85
#Mann= 20 ,-1 , 0
 -3443.6     .12       0 -2698.3     .12       0 -1586.3      .1       0
 -1110.2     .05       0  -817.3      .1       0    1211      .1       0
  2092.7     .12       0  2539.5     .05       0  2861.7     .12       0
  4112.8      .1       0    4599     .05       0    4990     .05       0
    5010     .05       0  5240.8     .12       0  5677.7     .12       0
  6121.2     .05       0  6762.9    .075       0  7157.9     .05       0
  8073.4     .05       0  9247.8     .05       0
#XS Ineff= 1 ,-1
   -1750  2948.3  112.92
Permanent Ineff=
       F
Bank Sta=4887.3,5115.74
XS Rating Curve= 0 ,0
Exp/Cntr=0.3,0.1

Type RM Length L Ch R = 1 ,216853  ,1914,1914,1914
BEGIN DESCRIPTION:
WFSJ Main 217.0
END DESCRIPTION:
XS GIS Cut Line= 4
       3852119.6     10085615.87      3847711.62     10079799.91
       3847676.9     10079426.64      3844463.35     10075667.95
#Sta/Elev= 30
 -2501.7   138.7 -2261.1  139.98   -2154     128 -2105.1  138.32 -1530.2  126.33
    -446  105.79  -107.1   104.1   971.2  104.74  1422.7  105.47  2459.7  103.98
  3599.8  108.85    4845  100.23  4875.1   88.74    4990    85.7  4998.2    85.2
    5010    85.7 5060.66  100.93  5362.1   89.21    5642   86.73  5898.1   103.6
  6145.9   102.2  6300.5  115.68  6833.3  117.97  7282.5  117.51    7394  109.44
  8340.7  116.77  8839.5  118.24  9626.2  120.56 10055.6   123.7   10116  125.13
#Mann= 20 ,-1 , 0
 -2501.7     .05       0   -2154     .05       0 -1530.2     .12       0
    -446     .12       0  -107.1      .1       0   971.2      .1       0
  1422.7      .1       0  2459.7      .1       0  3599.8     .05       0
    4990     .07       0    5010      .1       0  5362.1     .05       0
  5898.1     .05       0  6300.5     .12       0  6833.3      .1       0
  7282.5     .12       0  8340.7     .05       0  8839.5    .075       0
  9626.2     .05       0 10055.6     .05       0
#XS Ineff= 1 ,-1
    -930  3577.4  110.03
Permanent Ineff=
       F
Bank Sta=4845,5060.66
XS Rating Curve= 0 ,0
Exp/Cntr=0.3,0.1

Type RM Length L Ch R = 1 ,214939  ,1939,1939,1939
BEGIN DESCRIPTION:
WFSJ Main 215.0
END DESCRIPTION:
XS GIS Cut Line= 3
      3852605.72     10085459.63      3849176.86     10079977.41
      3845105.73     10075251.31
#Sta/Elev= 30
 -1466.2  142.93 -1109.3  142.48  -465.7  141.77   -45.1  114.42   926.8  105.29
    1397   107.5  2676.9  102.81  4221.6   99.76  4578.1  102.99  4879.6  105.73
  4910.2   95.38    4990   87.36  4998.2   86.86    5010   87.36  5194.5   96.68
  5251.9  103.37  5495.8  100.99  6259.4  100.67    6337   100.9  6372.1   89.31
  6414.9   99.34  6748.4   97.31  6790.2  109.78  7059.8  116.43    7476  114.89
  7979.9  112.62  8615.8  116.67 10244.2  123.15 10556.7  122.34 11237.8  123.72
#Mann= 20 ,-1 , 0
 -1466.2     .12       0 -1109.3     .12       0  -465.7     .05       0
   -45.1     .12       0   926.8     .05       0    1397     .12       0
  2676.9      .1       0  4221.6     .12       0  4578.1     .05       0
    4990     .05       0    5010     .05       0  5194.5     .12       0
  5495.8      .1       0  6259.4     .05       0  7059.8      .1       0
    7476     .12       0  7979.9     .12       0  8615.8      .1       0
 10244.2    .075       0 10556.7    .075       0
Bank Sta=4910.2,5194.5
XS Rating Curve= 0 ,0
Exp/Cntr=0.3,0.1

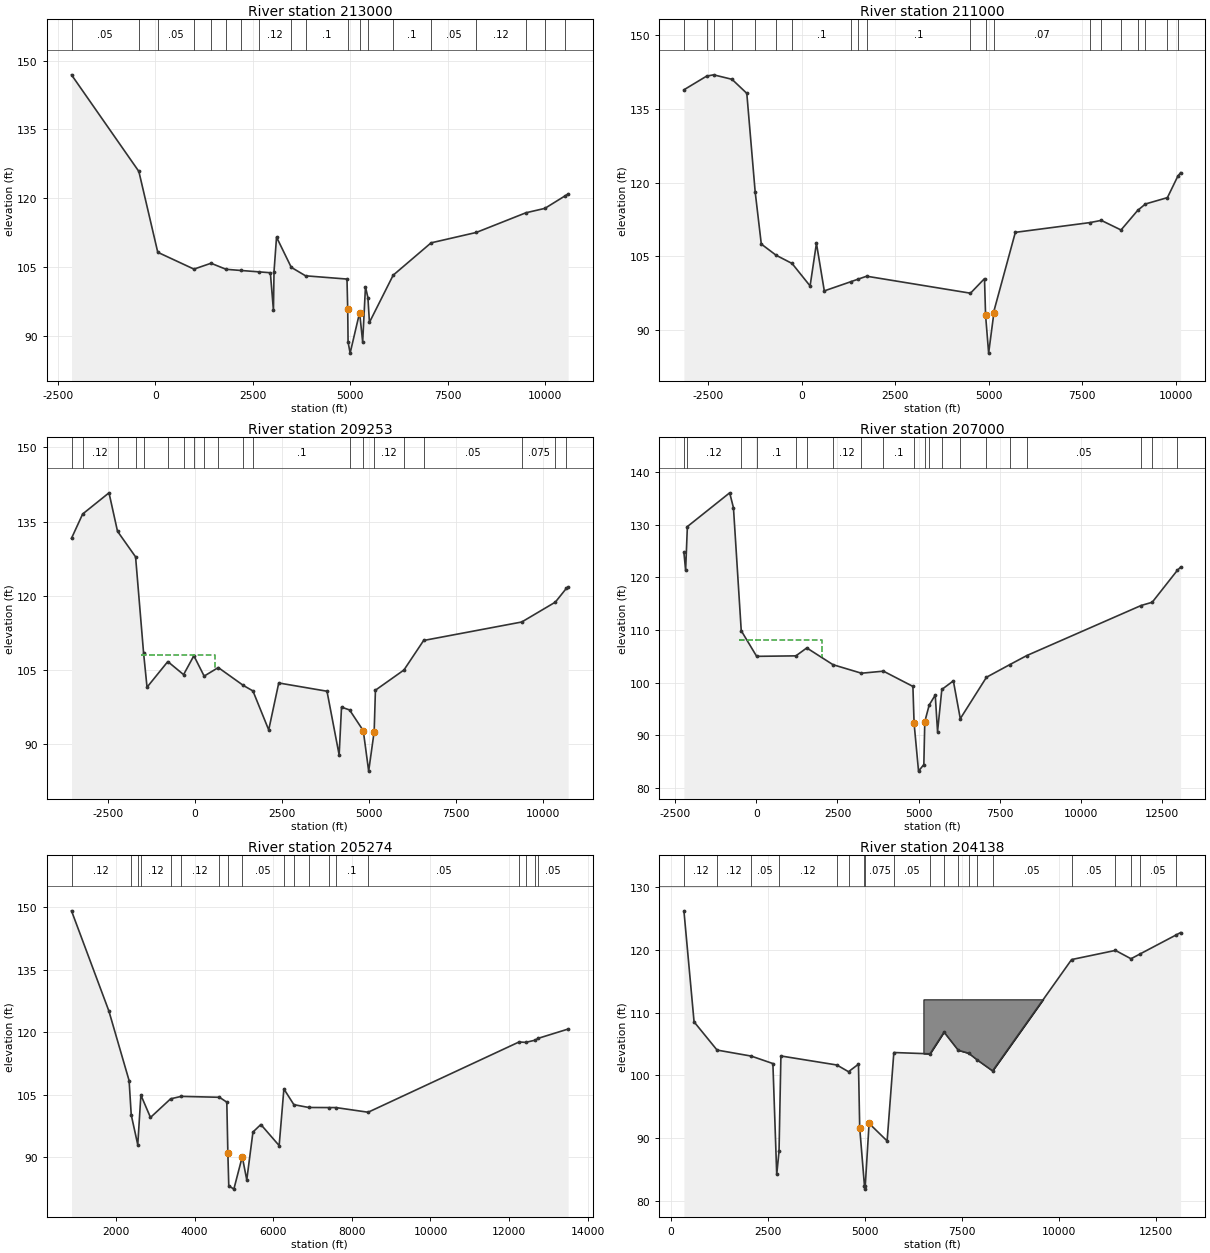
Type RM Length L Ch R = 1 ,213000  ,2000,2000,2000
BEGIN DESCRIPTION:
WFSJ Main 213.0
END DESCRIPTION:
XS GIS Cut Line= 3
      3854322.64     10084948.48      3850210.22     10079093.76
      3847084.23     10074452.63
#Sta/Elev= 30
 -2154.7  146.89  -425.3  125.81      60  108.17   989.3   104.5  1426.9  105.78
  1813.4  104.46  2201.1   104.2  2661.7   103.9  2950.3  103.71  3029.6   95.51
  3044.4  103.96  3109.1  111.48  3487.1  104.89    3854  103.04  4917.7  102.33
 4936.3795.71989  4945.8    88.6  4998.2   86.17  5242.1   95.03  5320.1    88.6
  5392.1  100.63  5455.1   98.27    5494   92.88    6103  103.17  7076.5  110.23
    8237   112.5  9510.4  116.79  9997.2  117.75 10510.1  120.45 10595.7   120.9
#Mann= 19 ,-1 , 0
 -2154.7     .05       0  -425.3     .12       0      60     .05       0
   989.3     .12       0  1426.9     .12       0  1813.4      .1       0
  2201.1      .1       0  2661.7     .12       0  3487.1     .12       0
    3854      .1       0 4936.37     .05       0  5242.1      .1       0
  5455.1     .12       0    6103      .1       0  7076.5     .05       0
    8237     .12       0  9510.4    .075       0  9997.2    .075       0
 10510.1     .05       0
#XS Ineff= 1 ,-1
    -200  3109.1  111.48
Permanent Ineff=
       F
Bank Sta=4936.37,5242.1
XS Rating Curve= 0 ,0
Exp/Cntr=0.3,0.1

Type RM Length L Ch R = 1 ,211000  ,1747,1747,1747
BEGIN DESCRIPTION:
WFSJ Main 211.0
END DESCRIPTION:
XS GIS Cut Line= 3
      3855115.47     10084685.26      3851087.52     10077597.56
      3847257.87     10074181.39
#Sta/Elev= 30
 -3152.3  138.83 -2544.7  141.61 -2357.6  141.87 -1866.7  140.96 -1470.5  138.11
 -1246.4  118.09 -1082.7   107.5  -684.3  105.22  -259.4  103.56   222.6   98.99
   392.1  107.66   602.6   97.99  1310.4   99.85  1502.4  100.36  1735.3  100.97
  4512.1   97.52  4887.3  100.48 4916.38   93.03  4998.2   85.35 5136.0693.39973
  5138.8   93.87  5712.4  109.88  7706.5  111.86  8010.9  112.31  8538.9  110.36
    8986  114.35  9191.8  115.64  9779.5  116.93 10057.6  121.28 10131.9     122
#Mann= 20 ,-1 , 0
 -3152.3     .05       0 -2544.7     .05       0 -2357.6     .12       0
 -1866.7     .05       0 -1246.4     .05       0  -684.3      .1       0
  -259.4      .1       0  1310.4     .12       0  1502.4     .05       0
  1735.3      .1       0  4512.1     .07       0 4916.38     .05       0
  5138.8     .07       0  7706.5     .12       0  8010.9     .05       0
  8538.9    .075       0    8986      .1       0  9191.8    .075       0
  9779.5     .05       0 10057.6     .05       0
#XS Ineff= 1 ,-1
   -1170   392.1  107.66
Permanent Ineff=
       F
Bank Sta=4916.38,5136.06
XS Rating Curve= 0 ,0
Exp/Cntr=0.3,0.1

Type RM Length L Ch R = 1 ,209253  ,2253,2253,2253
BEGIN DESCRIPTION:
WFSJ Main 209.0
END DESCRIPTION:
XS GIS Cut Line= 3
      3855365.48     10084497.78      3852282.15      10076143.6
      3847323.85     10074101.95
#Sta/Elev= 30
 -3538.5  131.62 -3217.5  136.54 -2461.2  140.82   -2217  133.04 -1697.6  127.86
 -1468.8  108.49 -1368.8  101.48  -772.2  106.67  -318.8  104.03   -23.5  107.85
   272.3  103.73   677.9  105.46  1398.2  101.84  1673.2  100.73  2126.6   92.84
  2414.9  102.34  3800.9  100.67  4150.1   87.77    4218   97.45  4449.8   96.88
  4843.1   92.69  4998.1    84.5    5156    92.5  5192.3  100.88  6010.6  104.96
  6577.1  110.94  9395.8  114.68 10360.1   118.7 10674.9  121.47 10728.7  121.69
#Mann= 20 ,-1 , 0
 -3538.5     .05       0 -3217.5     .12       0   -2217     .05       0
 -1697.6     .12       0 -1468.8      .1       0  -772.2     .12       0
  -318.8      .1       0   -23.5     .12       0   272.3      .1       0
   677.9      .1       0  1398.2     .05       0  1673.2      .1       0
  4449.8     .12       0  4843.1     .07       0    5156     .12       0
  6010.6     .05       0  6577.1     .05       0  9395.8    .075       0
 10360.1    .075       0 10674.9     .05       0
#XS Ineff= 1 ,-1
   -1550   583.2  108.05
Permanent Ineff=
       F
Bank Sta=4843.1,5156
XS Rating Curve= 0 ,0
Exp/Cntr=0.3,0.1

Type RM Length L Ch R = 1 ,207000  ,1726,1726,1726
BEGIN DESCRIPTION:
WFSJ Main 207.0
END DESCRIPTION:
XS GIS Cut Line= 4
      3855636.32      10084372.8       3854336.8     10077258.52
      3853157.15      10075643.6      3847293.06     10074061.65
#Sta/Elev= 30
   -2232  124.76 -2179.4  121.37 -2125.5  129.68  -821.9   136.1  -705.2  133.25
  -465.6  109.87     9.5  104.99  1218.7  105.08  1553.8  106.59  2362.9   103.4
  3237.9  101.78  3916.5  102.17  4824.6   99.27 4860.97   92.26  4998.1   83.15
  5161.6    84.4    5191   92.56  5326.9   95.73    5513   97.62  5584.1   90.67
    5716   98.69  6071.4  100.32  6284.8   93.13  7091.7  101.01  7808.8  103.41
  8335.4  105.14 11855.8  114.66 12199.3  115.28 12970.6  121.33 13073.6  121.96
#Mann= 20 ,-1 , 0
   -2232    .075       0 -2125.5     .12       0  -465.6      .1       0
     9.5      .1       0  1218.7     .12       0  1553.8      .1       0
  2362.9     .12       0  3237.9      .1       0  3916.5      .1       0
 4860.97     .07       0    5191      .1       0  5326.9     .05       0
    5716     .05       0  6284.8      .1       0  7091.7     .05       0
  7808.8      .1       0  8335.4     .05       0 11855.8      .1       0
 12199.3    .075       0 12970.6     .05       0
#XS Ineff= 1 ,-1
    -550  2008.8   108.1
Permanent Ineff=
       F
Bank Sta=4860.97,5191
XS Rating Curve= 0 ,0
Exp/Cntr=0.3,0.1

Type RM Length L Ch R = 1 ,205274  ,1136,1136,1136
BEGIN DESCRIPTION:
WFSJ Main 205.0
END DESCRIPTION:
XS GIS Cut Line= 3
      3858851.43      10078655.9      3854844.44     10075736.28
      3847362.32     10074017.65
#Sta/Elev= 30
   867.9  149.15  1818.7  125.08  2333.3  108.35  2387.5  100.12  2553.6   92.93
  2633.2  104.87  2877.2   99.49  3389.3  103.97  3659.3  104.56  4632.5  104.34
  4818.7  103.17  4845.7   90.95  4868.8   83.08  4998.1   82.27  5211.9   90.06
  5326.6   84.49  5483.9   95.99  5684.7    97.8  6150.6   92.73    6271  106.35
  6524.7  102.57  6903.8  101.89  7419.6  101.87  7594.5  101.87  8414.1  100.75
 12252.1  117.63 12422.7  117.54 12660.9  118.06 12739.8  118.51 13502.7  120.74
#Mann= 19 ,-1 , 0
   867.9     .12       0  2387.5     .05       0  2553.6      .1       0
  2633.2     .12       0  3389.3     .05       0  3659.3     .12       0
  4632.5     .05       0  4845.7     .03       0  5211.9     .05       0
    6271      .1       0  6524.7     .12       0  6903.8      .1       0
  7419.6     .12       0  7594.5      .1       0  8414.1     .05       0
 12252.1    .075       0 12422.7      .1       0 12660.9    .075       0
 12739.8     .05       0
Bank Sta=4845.7,5211.9
XS Rating Curve= 0 ,0
Exp/Cntr=0.3,0.1

Type RM Length L Ch R = 1 ,204138  ,648,648,648
BEGIN DESCRIPTION:
WFSJ Main 204.0
END DESCRIPTION:
XS GIS Cut Line= 4
      3859426.04     10077101.67      3855389.56     10075267.89
      3853067.51     10074378.14      3847197.27     10073987.51
#Sta/Elev= 30
   335.6  126.24   597.2  108.54    1190  104.04  2071.6  103.08  2629.2  101.89
    2728   84.21  2787.5   87.89  2835.9   103.1  4278.6  101.66    4579  100.59
  4835.3  101.79  4867.3   91.64    4990   82.37  4998.1   81.87    5010   82.37
  5108.9   92.35  5574.1   89.55  5747.3  103.65  6679.8  103.44  7040.6   106.9
  7406.7  104.01  7677.9  103.53  7897.9  102.46  8292.3  100.72 10329.6  118.47
 11459.7  119.93 11860.6   118.6 12080.8  119.32 13025.7   122.4   13139  122.77
#Mann= 20 ,-1 , 0
   335.6     .12       0    1190     .12       0  2071.6     .05       0
  2787.5     .12       0  4278.6     .12       0    4579      .1       0
    4990     .07       0    5010    .075       0  5747.3     .05       0
  6679.8    .075       0  7040.6     .05       0  7406.7    .075       0
  7677.9     .05       0  7897.9      .1       0  8292.3     .05       0
 10329.6     .05       0 11459.7    .075       0 11860.6    .075       0
 12080.8     .05       0 13025.7     .12       0
#Block Obstruct= 1 ,-1
    6509    9950  112.13
Bank Sta=4867.3,5108.9
XS Rating Curve= 0 ,0
Exp/Cntr=0.3,0.1

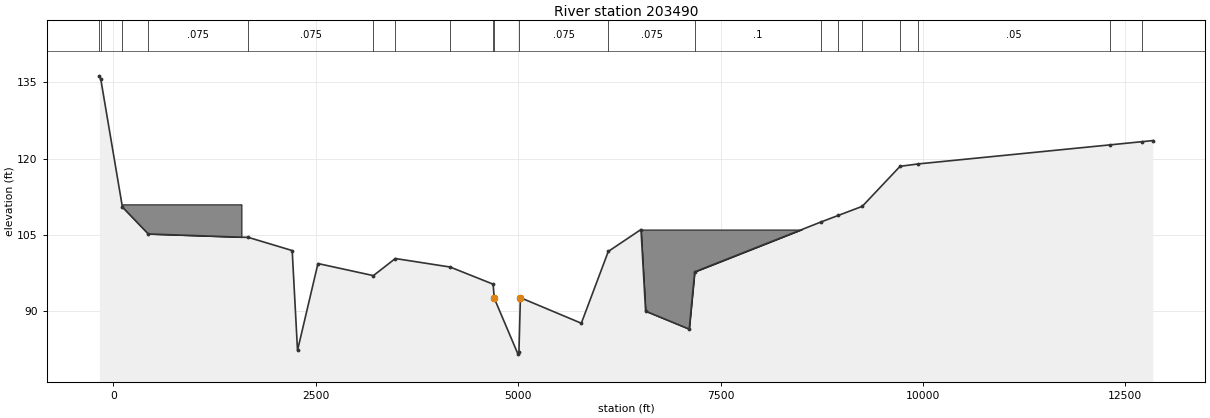
Type RM Length L Ch R = 1 ,203490  ,1564,1564,1564
BEGIN DESCRIPTION:
WFSJ Main 203.0
END DESCRIPTION:
XS GIS Cut Line= 6
      3859498.83     10076891.05       3856995.4     10075759.13
      3855849.56     10075168.85      3855863.45     10075043.85
      3853241.12     10073824.75      3847284.08     10073640.29
#Sta/Elev= 30
  -173.9   136.3  -155.6   135.6   111.2  110.42   430.4  105.12  1668.8  104.44
  2208.7  101.85  2274.5   82.17  2526.9   99.29  3211.7   96.91  3482.9  100.28
  4160.4    98.6  4691.2   95.22 4704.83   92.46  4998.1   81.43    5010   81.93
 5027.9592.55892  5780.6   87.52  6113.9  101.68  6517.7     106  6574.9    89.9
  7113.5   86.36  7181.6   97.65  8745.4  107.51  8955.9  108.78  9251.6  110.57
  9718.6  118.46  9941.6  118.93 12307.4  122.68 12701.7  123.31   12840  123.53
#Mann= 20 ,-1 , 0
  -173.9     .05       0  -155.6    .075       0   111.2    .075       0
   430.4    .075       0  1668.8    .075       0  3211.7     .05       0
  3482.9    .075       0  4160.4    .075       0  4691.2      .1       0
 4704.83     .07       0    5010    .075       0  6113.9    .075       0
  7181.6      .1       0  8745.4    .075       0  8955.9     .12       0
  9251.6    .075       0  9718.6    .075       0  9941.6     .05       0
 12307.4     .05       0 12701.7     .12       0
#Block Obstruct= 2 ,-1
      38  1581.7  110.96  6517.7    8560     106
Bank Sta=4704.83,5027.95
XS Rating Curve= 0 ,0
Exp/Cntr=0.3,0.1