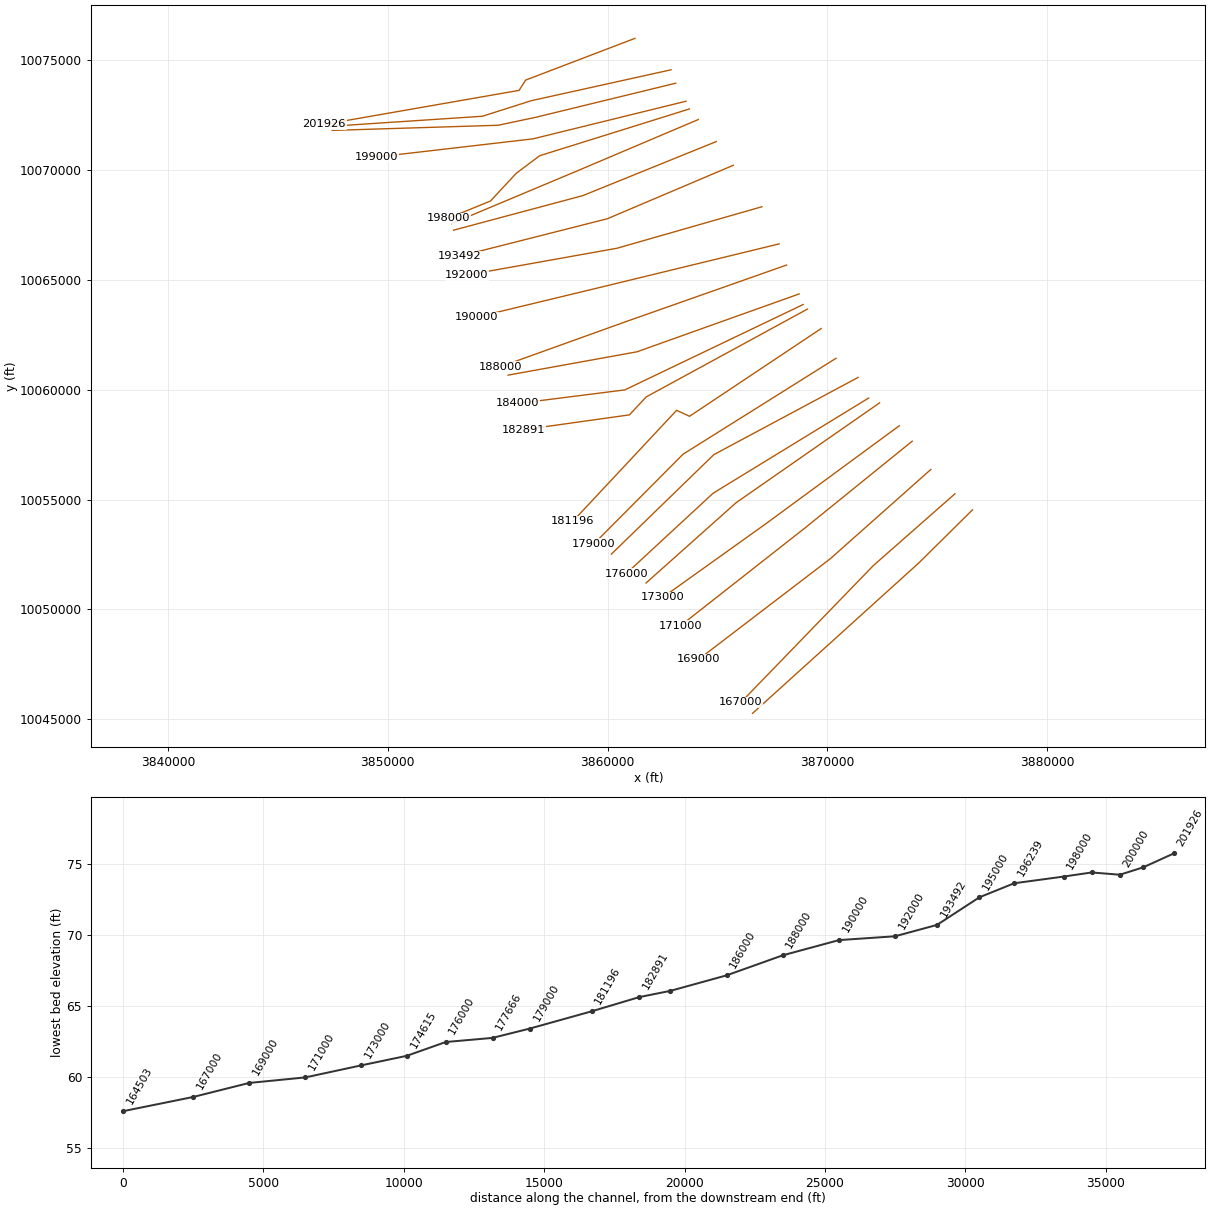
HEC-RAS study WFSJ Main.prj: WFSJ Main Base Level Engineering

--- WFSJ Main.g02 (geometry) --- (continued)

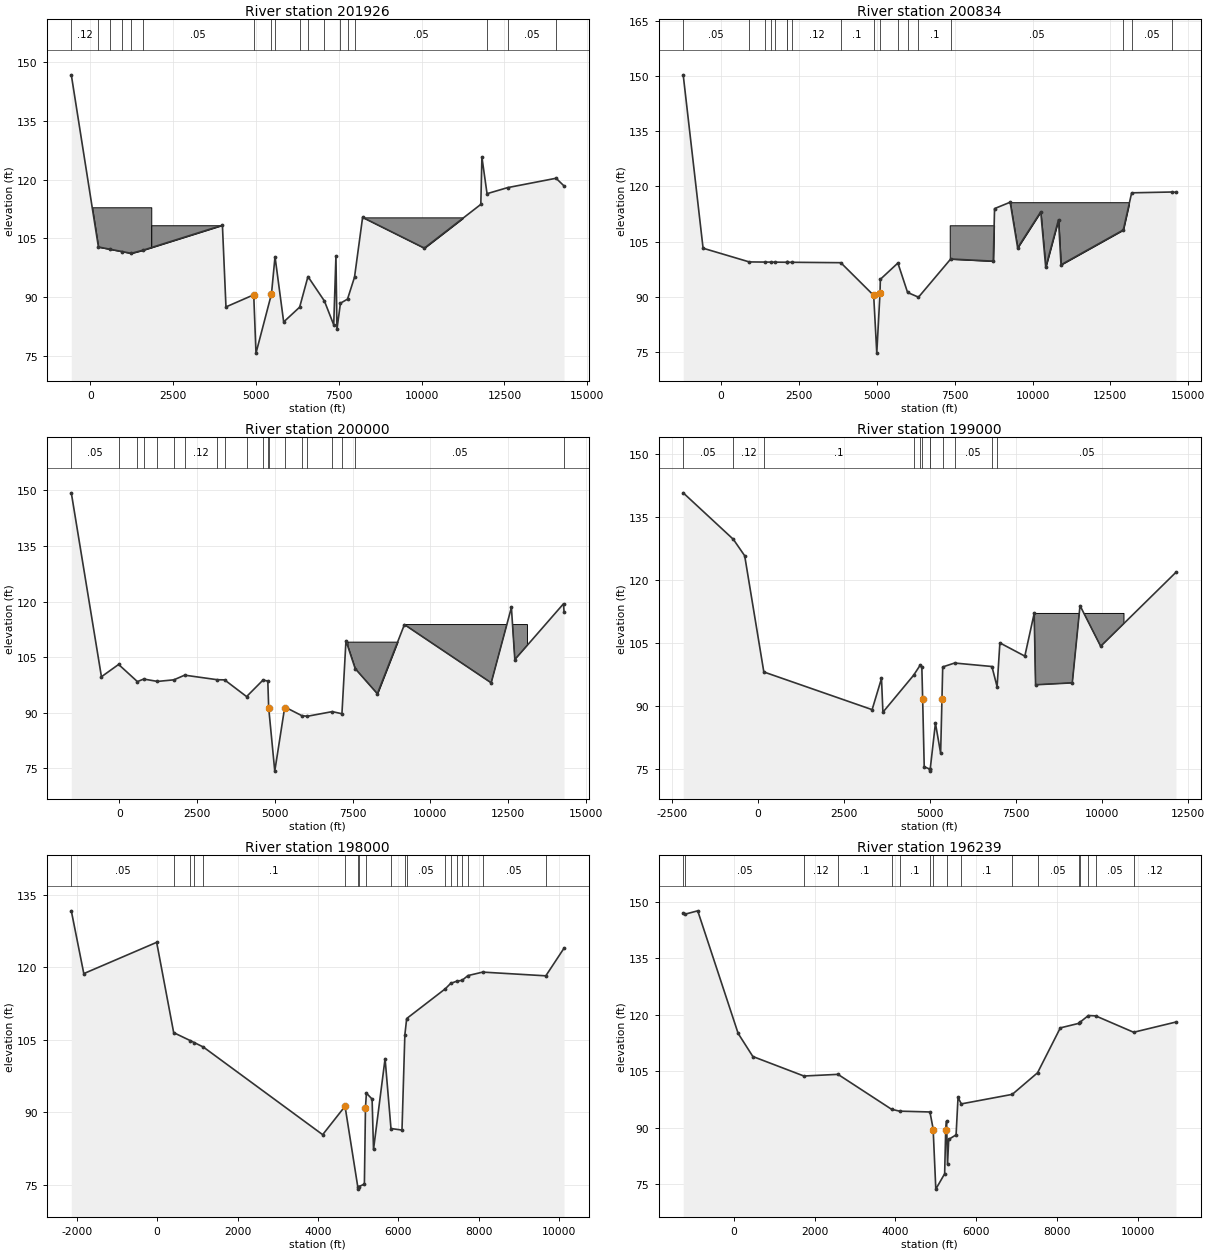
Type RM Length L Ch R = 1 ,201926  ,1092,1092,1092
BEGIN DESCRIPTION:
WFSJ Main 202.0
END DESCRIPTION:
XS GIS Cut Line= 4
      3861250.82     10076007.56      3856276.84     10074106.51
      3855977.36     10073637.76      3847111.54     10072088.52
#Sta/Elev= 30
  -579.6  146.71   239.3  102.82   592.7  102.24   956.9  101.65  1231.5   101.2
  1577.9  101.98  3984.1  108.36  4091.2   87.54  4929.7   90.63  4998.1   75.76
 5465.91   90.87  5572.6  100.35  5834.1   83.71  6316.6   87.48  6567.4   95.28
  7064.8   89.04  7345.6   82.96  7412.6  100.55    7443   81.84  7548.2   88.48
  7762.3   89.53  7973.8   95.14  8217.8  110.37 10082.4  102.53 11787.9  113.68
 11820.6  125.72 11975.9  116.41 12595.5  117.95 14060.4  120.34 14301.7  118.38
#Mann= 18 ,-1 , 0
  -579.6     .12       0   239.3      .1       0   592.7     .12       0
   956.9     .12       0  1231.5     .05       0  1577.9     .05       0
  4929.7     .05       0 5465.91     .05       0  5572.6      .1       0
  6316.6     .05       0  6567.4      .1       0  7064.8     .05       0
  7548.2      .1       0  7762.3      .1       0  7973.8     .05       0
 11975.9     .12       0 12595.5     .05       0 14060.4      .1       0
#Block Obstruct= 3 ,-1
  8217.8   11245  110.37     -65  1835.6  112.94    1836  3984.1  108.36
Bank Sta=4929.7,5465.91
XS Rating Curve= 0 ,0
Exp/Cntr=0.3,0.1

Type RM Length L Ch R = 1 ,200834  ,834,834,834
BEGIN DESCRIPTION:
WFSJ Main 201.0
END DESCRIPTION:
XS GIS Cut Line= 4
       3862891.4     10074575.25      3856537.25     10073169.01
      3854308.11     10072459.15      3847344.56     10071997.13
#Sta/Elev= 30
 -1219.5   150.3  -580.9  103.25   902.3   99.53    1410   99.49  1601.6   99.48
  1735.2   99.47  2108.4   99.44  2128.4   99.44  2288.2   99.43  3842.5   99.32
  4898.6   90.45  4998.1   74.78 5102.29   91.22  5112.7   94.81  5676.1   99.23
  5987.5   91.24  6337.9   89.96  7371.7  100.32  8740.5   99.74  8780.6     114
  9281.7  115.73  9522.3  103.35 10263.9  113.12 10424.2   98.06 10835.1  110.99
 10915.3   98.75 12915.8   108.2 13184.3  118.28 14466.2   118.5 14606.7  118.42
#Mann= 18 ,-1 , 0
 -1219.5     .05       0   902.3     .12       0    1410      .1       0
  1601.6     .12       0  1735.2      .1       0  2108.4     .12       0
  2128.4      .1       0  2288.2     .12       0  3842.5      .1       0
  4898.6     .05       0  5112.7     .07       0  5676.1      .1       0
  5987.5     .05       0  6337.9      .1       0  7371.7     .05       0
 12915.8     .12       0 13184.3     .05       0 14466.2     .12       0
#Block Obstruct= 2 ,-1
  7340.4    9085  109.47  9281.7   13100  115.73
Bank Sta=4898.6,5102.29
XS Rating Curve= 0 ,0
Exp/Cntr=0.3,0.1

Type RM Length L Ch R = 1 ,200000  ,1000,1000,1000
BEGIN DESCRIPTION:
WFSJ Main 200.0
END DESCRIPTION:
XS GIS Cut Line= 4
      3863099.79     10073963.29      3856738.23     10072412.29
      3855026.84     10072049.22      3847474.75     10071814.84
#Sta/Elev= 30
 -1547.9  149.31  -578.4   99.71   -25.9  103.03   578.7    98.4   780.5   99.09
  1224.5   98.45  1752.2   98.88  2099.3  100.14  3149.5   98.91  3383.5   98.87
  4091.5   94.36  4619.9   98.82 4774.02  98.549 4801.97   91.37  4998.1   74.26
  5315.6   91.35  5327.5   91.53  5863.3   89.24  6042.8   89.05  6848.8   90.31
    7159   89.73  7288.7  109.43    7585   101.9  8299.2   95.12  9169.6  113.78
   11961   98.07 12611.3  118.39 12721.3  104.34   14288   119.4 14305.2  117.17
#Mann= 20 ,-1 , 0
 -1547.9     .05       0   -25.9     .12       0   578.7      .1       0
   780.5     .12       0  1224.5      .1       0  1752.2      .1       0
  2099.3     .12       0  3149.5     .12       0  3383.5      .1       0
  4091.5     .12       0  4619.9      .1       0 4774.02     .05       0
 4801.97     .03       0  5327.5     .05       0  5863.3     .05       0
  6042.8      .1       0  6848.8     .05       0    7159      .1       0
    7585     .05       0   14288     .12       0
#Block Obstruct= 2 ,-1
  7338.8    9066  109.18  9169.6   13127  113.78
Bank Sta=4801.97,5315.6
XS Rating Curve= 0 ,0
Exp/Cntr=0.3,0.1

Type RM Length L Ch R = 1 ,199000  ,1000,1000,1000
BEGIN DESCRIPTION:
WFSJ Main 199.0
END DESCRIPTION:
XS GIS Cut Line= 3
      3863568.51     10073142.97      3856608.15     10071429.79
      3849506.01      10070603.9
#Sta/Elev= 30
 -2168.1  140.79  -709.6  129.69  -381.3  125.78   174.8   98.07  3321.7   89.08
  3593.8   96.52  3635.3   88.47  4528.3    97.3  4725.1   99.78  4766.5   99.22
 4790.34   91.56  4835.5   75.47    4990   74.92  4998.1   74.42    5010   74.92
  5161.4   85.86  5312.4   78.69 5351.43   91.73  5372.8   99.27  5718.7   100.2
  6802.8   99.37  6953.1   94.54  7033.9     105  7758.8  101.85  8030.6  112.03
  8070.8   95.01    9138   95.47  9362.7  113.89  9962.7  104.19   12150  121.84
#Mann= 12 ,-1 , 0
 -2168.1     .05       0  -709.6     .12       0   174.8      .1       0
  4528.3     .12       0  4725.1     .05       0  4766.5     .05       0
    4990     .05       0    5010     .05       0  5372.8      .1       0
  5718.7     .05       0  6802.8      .1       0  6953.1     .05       0
#Block Obstruct= 1 ,-1
  8030.6   10640  112.03
Bank Sta=4790.34,5351.43
XS Rating Curve= 0 ,0
Exp/Cntr=0.3,0.1

Type RM Length L Ch R = 1 ,198000  ,1761,1761,1761
BEGIN DESCRIPTION:
WFSJ Main 198.0
END DESCRIPTION:
XS GIS Cut Line= 5
      3863724.79     10072791.41      3856913.52     10070661.55
      3855847.15     10069861.72      3854675.27     10068598.69
      3852762.04     10067817.78
#Sta/Elev= 30
 -2136.5  131.72 -1825.4  118.73   -12.8   125.2   410.7  106.51   819.4  104.88
   921.5  104.46  1149.3  103.53  4117.1    85.4  4673.5   91.28    4990   74.63
  4998.1   74.13    5010   74.63    5155   75.17  5182.1   91.02    5205   93.99
  5346.6   92.77  5382.1   82.34  5669.6  101.13  5816.4   86.67  6090.4   86.35
  6161.7  106.06  6207.1  109.43  7168.5  115.59  7301.2   116.7  7446.7  117.14
  7585.8  117.34  7731.6  118.32    8099  119.04  9668.8  118.27 10122.4     124
#Mann= 19 ,-1 , 0
 -2136.5     .05       0   410.7     .12       0   819.4      .1       0
   921.5     .12       0  1149.3      .1       0  4673.5     .05       0
    4990     .05       0    5010     .05       0    5205      .1       0
  5816.4     .05       0  6161.7     .12       0  6207.1     .05       0
  7168.5     .12       0  7301.2     .05       0  7446.7    .075       0
  7585.8     .05       0  7731.6    .075       0    8099     .05       0
  9668.8     .12       0
Bank Sta=4673.5,5182.1
XS Rating Curve= 0 ,0
Exp/Cntr=0.3,0.1

Type RM Length L Ch R = 1 ,196239  ,1239,1239,1239
BEGIN DESCRIPTION:
WFSJ Main 196.0
END DESCRIPTION:
XS GIS Cut Line= 3
      3864128.43     10072309.64      3858672.67     10069991.92
      3852904.43     10067570.04
#Sta/Elev= 30
 -1248.1     147   -1195  146.77  -888.9  147.64   110.6  115.05   474.6  108.91
  1735.8  103.73  2579.1  104.17  3904.5   94.88  4101.7   94.39  4852.7   94.17
    4928   89.92  4933.489.29115  4998.1   73.66  5216.5   77.75 5242.9289.42747
    5264   91.74  5287.8   80.28  5316.9   86.88  5499.5   88.09  5547.1   98.02
  5629.2   96.32  6888.5   98.85  7513.5  104.59  8076.3  116.52  8530.9  117.72
  8570.9   118.1  8771.6  119.81  8949.3  119.72  9889.7  115.36 10935.6  118.08
#Mann= 17 ,-1 , 0
 -1248.1     .12       0   -1195     .05       0  1735.8     .12       0
  2579.1      .1       0  3904.5     .12       0  4101.7      .1       0
  4852.7     .05       0    4928     .05       0    5264      .1       0
  5629.2      .1       0  6888.5     .12       0  7513.5     .05       0
  8530.9    .075       0  8570.9     .05       0  8771.6    .075       0
  8949.3     .05       0  9889.7     .12       0
Bank Sta=4933.4,5242.92
XS Rating Curve= 0 ,0
Exp/Cntr=0.3,0.1

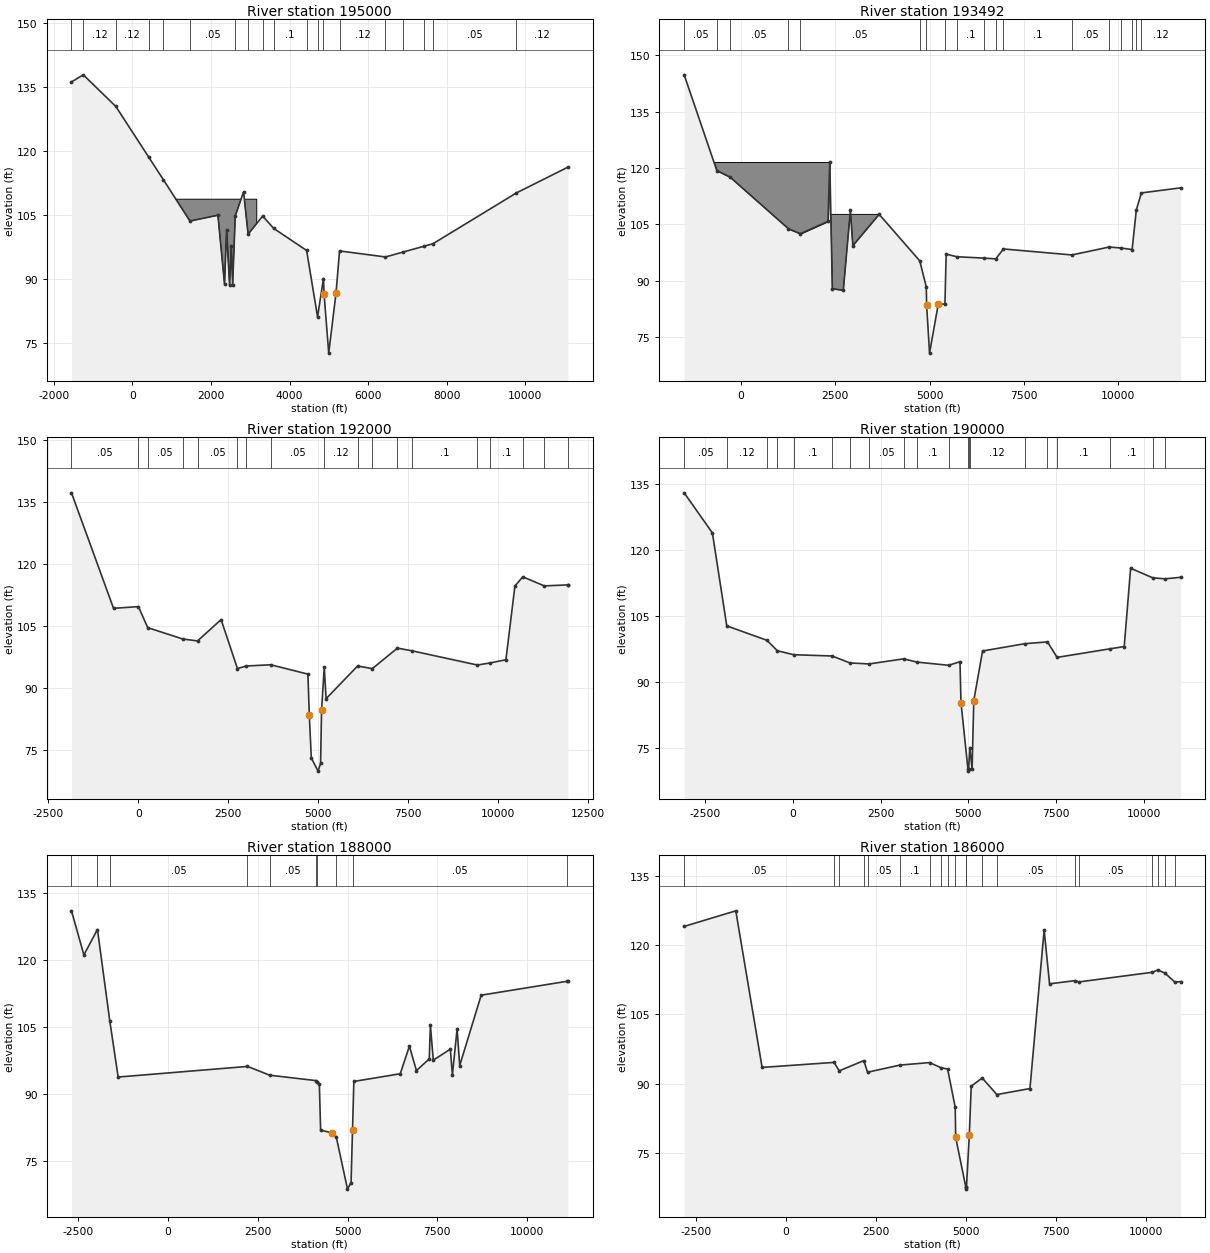
Type RM Length L Ch R = 1 ,195000  ,1508,1508,1508
BEGIN DESCRIPTION:
WFSJ Main 195.0
END DESCRIPTION:
XS GIS Cut Line= 3
      3864948.68     10071307.02      3858877.01      10068844.6
      3852995.59     10067270.57
#Sta/Elev= 30
   -1552  136.13 -1250.8  137.78  -422.3  130.37   416.3   118.5   786.7  113.26
  1464.6  103.57  2176.4  104.93  2344.5   88.84  2398.4  101.51    2474   88.58
  2516.6   97.71  2551.5   88.67  2617.7  104.76  2830.1   110.4  2945.1  100.49
  3314.8  104.73  3598.3  101.84  4434.9   96.69  4713.6   81.16  4863.6   90.08
  4880.4    86.4  4998.1   72.67    5184   86.76  5273.5   96.58  6442.8   95.17
  6879.2   96.29  7436.3   97.71  7653.4   98.27  9778.5  110.16 11088.4  116.18
#Mann= 19 ,-1 , 0
   -1552     .05       0 -1250.8     .12       0  -422.3     .12       0
   416.3      .1       0   786.7     .05       0  1464.6     .05       0
  2617.7      .1       0  2945.1     .05       0  3314.8     .12       0
  3598.3      .1       0  4434.9     .12       0  4713.6      .1       0
  4863.6     .05       0  5273.5     .12       0  6442.8      .1       0
  6879.2     .05       0  7436.3     .12       0  7653.4     .05       0
  9778.5     .12       0
#Block Obstruct= 1 ,-1
     940  3165.1  108.68
Bank Sta=4880.4,5184
XS Rating Curve= 0 ,0
Exp/Cntr=0.3,0.1

Type RM Length L Ch R = 1 ,193492  ,1492,1492,1492
BEGIN DESCRIPTION:
WFSJ Main 193.0
END DESCRIPTION:
XS GIS Cut Line= 3
      3865722.57     10070226.73      3859993.42     10067791.84
      3853274.66     10066086.11
#Sta/Elev= 30
 -1505.4   144.8  -639.9  119.32  -287.5  117.57  1258.7  103.83  1575.1  102.51
  2306.9  105.81  2354.2  121.61  2422.2   87.88  2712.4   87.42  2900.3  108.74
  2965.2   99.31  3663.5  107.66  4738.5   95.29  4911.2   88.37  4921.5   83.44
  4998.1   70.73  5228.3   83.75  5406.4   83.79  5438.2    97.1  5716.2   96.39
    6452   96.01  6754.4   95.82    6956   98.46  8770.3   96.86  9759.6   98.97
 10067.8   98.71 10366.8    98.3 10478.3  108.83 10612.2  113.37 11651.6  114.72
#Mann= 18 ,-1 , 0
 -1505.4     .05       0  -639.9      .1       0  -287.5     .05       0
  1258.7      .1       0  1575.1     .05       0  4738.5      .1       0
  4911.2     .05       0  5406.4     .12       0  5716.2      .1       0
    6452     .05       0  6754.4     .12       0    6956      .1       0
  8770.3     .05       0  9759.6     .12       0 10067.8      .1       0
 10366.8     .12       0 10478.3     .05       0 10612.2     .12       0
#Block Obstruct= 2 ,-1
    2376  3663.5  107.66    -900  2354.2  121.61
Bank Sta=4921.5,5228.3
XS Rating Curve= 0 ,0
Exp/Cntr=0.3,0.1

Type RM Length L Ch R = 1 ,192000  ,2000,2000,2000
BEGIN DESCRIPTION:
WFSJ Main 192.0
END DESCRIPTION:
XS GIS Cut Line= 3
      3867024.66     10068338.71      3860434.33     10066448.65
      3853601.49     10065226.96
#Sta/Elev= 30
   -1856  137.15  -687.3  109.25     3.4  109.67   262.6  104.59  1238.2  101.84
  1647.3  101.38  2301.9  106.53  2755.9   94.71  2998.9   95.32    3680   95.62
  4714.7   93.36  4753.6   83.42  4809.1   73.11  4998.1   69.93    5067   71.83
 5094.0584.61525  5169.1   95.04  5219.9   87.43  6094.3   95.31  6506.7    94.7
  7203.4   99.64  7601.5      99  9424.2   95.56  9780.3   96.06 10217.9   96.84
 10467.9  114.64 10686.8  116.86 11283.9  114.67 11929.6  114.91 11941.2  114.91
#Mann= 18 ,-1 , 0
   -1856     .05       0     3.4      .1       0   262.6     .05       0
  1238.2      .1       0  1647.3     .05       0  2755.9     .05       0
  2998.9      .1       0    3680     .05       0  5169.1     .12       0
  6094.3      .1       0  6506.7     .05       0  7203.4     .12       0
  7601.5      .1       0  9424.2     .05       0  9780.3      .1       0
 10686.8     .05       0 11283.9     .05       0 11929.6      .1       0
Bank Sta=4753.6,5094.05
XS Rating Curve= 0 ,0
Exp/Cntr=0.3,0.1

Type RM Length L Ch R = 1 ,190000  ,2000,2000,2000
BEGIN DESCRIPTION:
WFSJ Main 190.0
END DESCRIPTION:
XS GIS Cut Line= 3
      3867805.92       10066646.      3859938.21     10064731.89
       3854055.9     10063312.67
#Sta/Elev= 30
 -3097.2  133.01 -2292.5  123.89 -1882.7  102.72  -737.1   99.44  -440.6   97.06
    23.5   96.16  1118.3   95.87  1625.1   94.29  2172.3   94.06  3158.6   95.22
  3536.2   94.48  4441.5   93.75  4763.7   94.57 4792.18   85.27    4990   70.16
  4998.1   69.66    5010   70.16    5045   75.01  5109.2   70.16  5156.8   85.71
  5407.6   97.01  6605.1   98.66    7257   99.08  7531.3   95.55  9050.1   97.52
  9444.3   98.02    9627  115.85 10258.5  113.66 10609.2  113.43 11051.1  113.78
#Mann= 20 ,-1 , 0
 -3097.2     .05       0 -1882.7     .12       0  -737.1      .1       0
  -440.6     .05       0    23.5      .1       0  1118.3      .1       0
  1625.1     .05       0  2172.3     .05       0  3158.6      .1       0
  3536.2      .1       0  4441.5     .05       0    4990     .05       0
    5010     .05       0    5045     .12       0  6605.1      .1       0
    7257     .05       0  7531.3      .1       0  9050.1      .1       0
 10258.5     .12       0 10609.2     .05       0
Bank Sta=4792.18,5156.8
XS Rating Curve= 0 ,0
Exp/Cntr=0.3,0.1

Type RM Length L Ch R = 1 ,188000  ,2000,2000,2000
BEGIN DESCRIPTION:
WFSJ Main 188.0
END DESCRIPTION:
XS GIS Cut Line= 3
      3868144.44     10065682.46       3860889.5     10063124.74
      3855111.68     10061047.43
#Sta/Elev= 30
 -2692.6  131.01 -2347.1  121.12 -1969.2  126.82 -1625.5  106.32   -1392   93.73
  2210.8   96.11  2832.3   94.14  4119.9   92.93  4158.4   92.66  4212.9   92.28
  4249.2   81.83  4578.9   81.18  4683.6   80.35  4998.1   68.59  5097.4   70.06
 5137.6381.74817  5175.2   92.74  6468.2   94.47  6723.3  100.67  6918.6   95.18
  7276.6    97.8  7307.7  105.37  7388.8   97.52  7864.4   99.98  7920.5   94.21
  8051.6  104.48  8124.9   96.31  8723.3  112.09 11109.1   115.2 11139.9  115.31
#Mann= 10 ,-1 , 0
 -2692.6     .05       0 -1969.2     .12       0 -1625.5     .05       0
  2210.8      .1       0  2832.3     .05       0  4119.9     .12       0
  4158.4     .05       0  4683.6     .03       0 5137.63     .05       0
 11109.1     .12       0
Bank Sta=4578.9,5137.63
XS Rating Curve= 0 ,0
Exp/Cntr=0.3,0.1

Type RM Length L Ch R = 1 ,186000  ,2000,2000,2000
BEGIN DESCRIPTION:
WFSJ Main 186.0
END DESCRIPTION:
XS GIS Cut Line= 3
      3868717.39     10064367.36      3861339.03     10061731.95
      3855475.21     10060669.45
#Sta/Elev= 30
 -2834.9  124.02 -1400.3  127.39  -669.2   93.51  1330.9    94.6  1473.1   92.77
  2156.7   94.98  2260.9   92.47  3160.3   94.02  3985.9   94.56  4293.8   93.47
  4485.7   93.16  4696.7   84.89 4709.97   78.36    4990   67.68  4998.1   67.18
    5010   67.68  5088.3   78.89  5141.8   89.45  5447.3   91.23  5853.6   87.64
  6773.1   88.94  7167.6  123.24  7318.3   111.6  8035.8  112.29  8135.4  112.01
 10167.4  114.09 10325.6  114.59 10524.7  113.92 10798.1  111.97 10959.3  112.07
#Mann= 20 ,-1 , 0
 -2834.9     .05       0  1330.9      .1       0  1473.1      .1       0
  2156.7      .1       0  2260.9     .05       0  3160.3      .1       0
  3985.9     .12       0  4293.8      .1       0  4485.7      .1       0
  4696.7     .05       0    4990     .05       0    5010     .05       0
  5447.3    .075       0  5853.6     .05       0  8035.8    .075       0
  8135.4     .05       0 10167.4     .12       0 10325.6     .05       0
 10524.7      .1       0 10798.1     .12       0
Bank Sta=4709.97,5088.3
XS Rating Curve= 0 ,0
Exp/Cntr=0.3,0.1

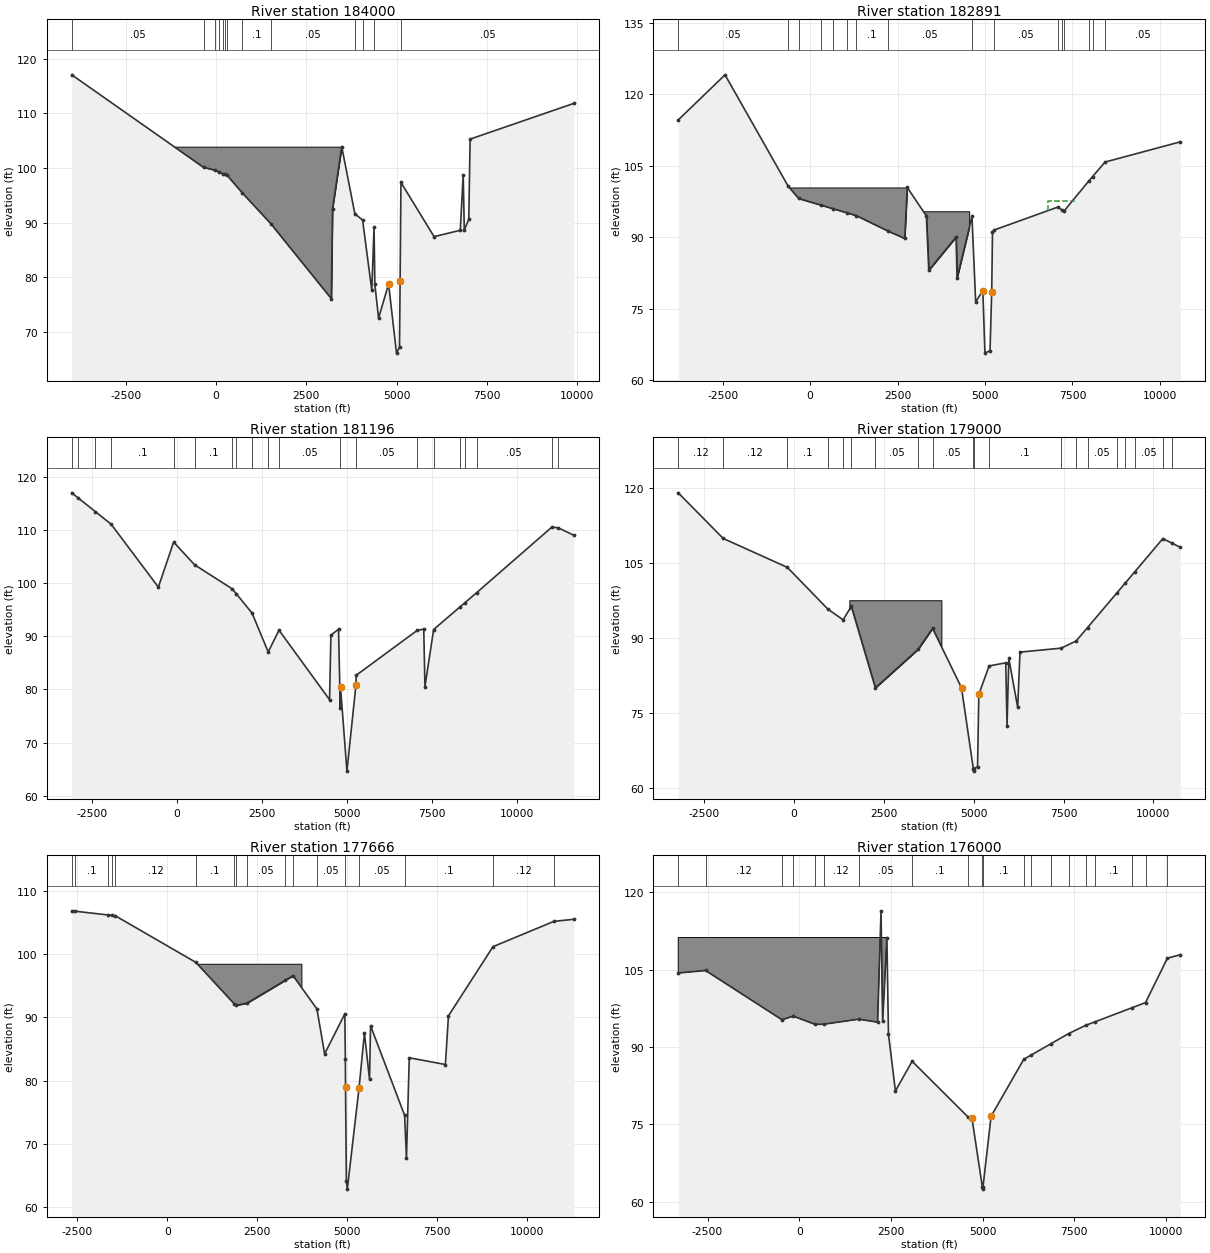
Type RM Length L Ch R = 1 ,184000  ,1109,1109,1109
BEGIN DESCRIPTION:
WFSJ Main 184.0
END DESCRIPTION:
XS GIS Cut Line= 3
       3868899.7      10063885.6      3860787.93     10059997.15
      3855917.93     10059380.38
#Sta/Elev= 30
 -3995.6  117.08  -345.8  100.13   -23.5   99.62      84   99.21   191.4   98.97
   254.2   98.83   298.8   98.73   728.5   95.43  1519.4   89.78  3192.5   76.06
  3226.2   92.56    3481  103.92  3843.9   91.63  4058.7   90.46  4313.3   77.62
  4375.7   89.17  4398.4   78.68  4501.1   72.51  4778.778.74182  4998.1   66.09
  5080.7   67.16 5097.55   79.22    5121   97.36  6038.3   87.43  6764.3    88.6
  6844.7   98.71  6874.9   88.68  6999.6   90.59  7036.2   105.3  9908.9  111.85
#Mann= 13 ,-1 , 0
 -3995.6     .05       0  -345.8      .1       0   -23.5     .12       0
      84      .1       0   191.4     .12       0   254.2      .1       0
   298.8     .12       0   728.5      .1       0  1519.4     .05       0
  3843.9     .12       0  4058.7     .05       0  4375.7     .03       0
    5121     .05       0
#XS Ineff= 1 ,-1
    5121    7150   97.36
Permanent Ineff=
       F
#Block Obstruct= 1 ,-1
   -1700    3481  103.92
Bank Sta=4778.7,5097.55
XS Rating Curve= 0 ,0
Exp/Cntr=0.3,0.1

Type RM Length L Ch R = 1 ,182891  ,1695,1695,1695
BEGIN DESCRIPTION:
WFSJ Main 183.0
END DESCRIPTION:
XS GIS Cut Line= 4
      3869094.97     10063677.25      3861764.25     10059679.86
      3860996.02     10058859.55      3856165.28     10058182.46
#Sta/Elev= 30
 -3768.4  114.57 -2431.2  124.04  -626.2  100.68  -327.4    98.1   302.9   96.73
   648.9   95.98  1060.8   95.08  1317.8   94.52  2218.7    91.3  2706.5   89.71
  2777.7  100.41  3324.4   94.44  3392.7   83.03  4172.2      90  4201.4   81.37
  4627.5   94.33  4733.5   76.43  4938.6   78.74  4998.1   65.65  5143.8   66.17
 5191.98   78.38  5214.6   91.03  5264.4   91.49  7089.7   96.31  7201.7   95.68
  7254.4   95.41  7974.9  101.83  8073.9  102.68  8432.5  105.74 10583.2  109.98
#Mann= 16 ,-1 , 0
 -3768.4     .05       0  -626.2     .12       0  -327.4      .1       0
   302.9     .12       0   648.9      .1       0  1060.8     .12       0
  1317.8      .1       0  2218.7     .05       0  4627.5     .03       0
  5264.4     .05       0  7089.7     .12       0  7201.7     .05       0
  7254.4     .12       0  7974.9     .05       0  8073.9     .12       0
  8432.5     .05       0
#XS Ineff= 1 ,-1
    6804    7575   97.49
Permanent Ineff=
       F
#Block Obstruct= 2 ,-1
    -815  2777.7  100.41  2777.8  4548.1   95.41
Bank Sta=4938.6,5191.98
XS Rating Curve= 0 ,0
Exp/Cntr=0.3,0.1

Type RM Length L Ch R = 1 ,181196  ,2196,2196,2196
BEGIN DESCRIPTION:
WFSJ Main 182.0
END DESCRIPTION:
XS GIS Cut Line= 4
      3869719.95     10062791.82      3863730.39     10058794.44
      3863144.46     10059067.88      3858418.79     10054009.12
#Sta/Elev= 30
 -3096.9  116.94 -2908.5  115.98 -2401.4   113.4 -1938.3  111.04  -549.1   99.22
  -100.5  107.69   515.8  103.42  1629.9   98.87  1745.4   97.96  2208.1   94.33
    2682   87.04  2999.5   91.13  4486.9   78.07  4526.2   90.19  4750.7   91.31
  4802.4   76.51  4809.7   80.37  4998.1   64.65  5262.6   80.81  5269.4   82.66
  7065.4   91.09  7257.7   91.33  7292.9   80.54  7549.2   91.26  8328.8   95.53
  8468.5   96.29  8816.1   98.19 11026.7   110.5 11207.4  110.38 11673.3  108.97
#Mann= 20 ,-1 , 0
 -3096.9     .12       0 -2908.5     .05       0 -2401.4     .12       0
 -1938.3      .1       0  -100.5     .12       0   515.8      .1       0
  1629.9     .12       0  1745.4     .05       0  2208.1    .075       0
    2682      .1       0  2999.5     .05       0  4802.4     .03       0
  5269.4     .05       0  7065.4      .1       0  7549.2     .12       0
  8328.8     .12       0  8468.5      .1       0  8816.1     .05       0
 11026.7    .075       0 11207.4     .05       0
Bank Sta=4809.7,5262.6
XS Rating Curve= 0 ,0
Exp/Cntr=0.3,0.1

Type RM Length L Ch R = 1 ,179000  ,1334,1334,1334
BEGIN DESCRIPTION:
WFSJ Main 179.0
END DESCRIPTION:
XS GIS Cut Line= 3
       3870397.1     10061437.69      3863434.37     10057066.93
      3859382.16     10052987.88
#Sta/Elev= 30
 -3220.9  119.09 -1968.8  109.96  -184.2  104.18   938.1   95.87  1366.2   93.69
  1595.2   96.38  2263.3   80.09    3453   87.79  3855.7   91.99  4661.2   80.11
    4990   63.94  4998.1   63.44    5010   63.94  5107.7   64.35  5143.1   78.79
  5429.6   84.48  5892.7   85.09    5928    72.5  5977.5   85.97    6225   76.17
  6288.6   87.24  7434.4   88.03  7850.8   89.46  8167.3   92.14  8984.3   99.07
  9210.1  100.98  9477.2  103.25 10263.8  109.94 10510.2  109.05 10749.7  108.19
#Mann= 20 ,-1 , 0
 -3220.9     .12       0 -1968.8     .12       0  -184.2      .1       0
   938.1      .1       0  1366.2     .05       0  1595.2      .1       0
  2263.3     .05       0    3453      .1       0  3855.7     .05       0
    4990     .05       0    5010     .05       0  5429.6      .1       0
  7434.4      .1       0  7850.8     .12       0  8167.3     .05       0
  8984.3     .05       0  9210.1     .12       0  9477.2     .05       0
 10263.8     .05       0 10510.2    .075       0
#Block Obstruct= 1 ,-1
    1540  4101.6   97.61
Bank Sta=4661.2,5143.1
XS Rating Curve= 0 ,0
Exp/Cntr=0.3,0.1

Type RM Length L Ch R = 1 ,177666  ,1666,1666,1666
BEGIN DESCRIPTION:
WFSJ Main 178.0
END DESCRIPTION:
XS GIS Cut Line= 3
      3871399.67     10060565.28      3864837.17     10057049.65
      3860175.67     10052518.37
#Sta/Elev= 30
 -2655.6  106.91 -2579.7  106.86 -1640.5  106.25   -1548  106.19 -1444.6  106.12
     790   98.74  1852.4   92.19  1910.1   91.94  2206.6   92.26    3279   95.91
  3490.3   96.63  4153.7   91.35  4368.2   84.23  4929.1   90.57  4943.3   83.42
  4948.4   78.97  4971.6   64.05  4998.1   62.78    5323  78.797  5473.7   87.51
  5615.1   80.19  5643.4   88.68  6590.3   74.47  6640.7   67.64  6718.4   83.61
  7722.5   82.54  7807.4   90.26  9045.1  101.23 10736.7  105.24 11290.2  105.57
#Mann= 17 ,-1 , 0
 -2655.6     .12       0 -2579.7      .1       0 -1640.5     .12       0
   -1548      .1       0 -1444.6     .12       0     790      .1       0
  1852.4     .12       0  1910.1      .1       0  2206.6     .05       0
    3279     .12       0  3490.3     .05       0  4153.7     .05       0
  4943.3     .03       0    5323     .05       0  6590.3      .1       0
  9045.1     .12       0 10736.7     .05       0
#Block Obstruct= 1 ,-1
     610  3722.3   98.52
Bank Sta=4948.4,5323
XS Rating Curve= 0 ,0
Exp/Cntr=0.3,0.1

Type RM Length L Ch R = 1 ,176000  ,1385,1385,1385
BEGIN DESCRIPTION:
WFSJ Main 176.0
END DESCRIPTION:
XS GIS Cut Line= 3
      3871881.46     10059627.79      3864805.66     10055293.44
       3860852.8     10051632.99
#Sta/Elev= 30
 -3297.8  104.32 -2553.5  104.81  -469.7   95.27  -166.1   95.98   442.3   94.36
   666.3   94.41  1626.9   95.39    2136    94.8  2229.9  116.36  2273.7   95.02
  2389.8  111.19  2432.4   92.49  2621.9   81.49  3076.8   87.24  4591.8   76.52
    4709   76.19    4990   62.99  4998.1   62.49    5010   62.99 5229.72   76.59
  6120.2   87.62  6319.3   88.43  6864.6   90.65  7340.5   92.59  7811.5    94.2
  8064.2   94.88  9082.4   97.63    9440    98.6 10034.9  107.19 10387.4  107.86
#Mann= 20 ,-1 , 0
 -3297.8      .1       0 -2553.5     .12       0  -469.7      .1       0
  -166.1     .12       0   442.3      .1       0   666.3     .12       0
  1626.9     .05       0  3076.8      .1       0  4591.8     .05       0
    4990     .07       0    5010      .1       0  6120.2     .05       0
  6319.3     .12       0  6864.6      .1       0  7340.5     .12       0
  7811.5      .1       0  8064.2      .1       0  9082.4     .12       0
    9440     .05       0 10034.9     .05       0
#Block Obstruct= 1 ,-1
 -3297.8  2389.8  111.19
Bank Sta=4709,5229.72
XS Rating Curve= 0 ,0
Exp/Cntr=0.3,0.1

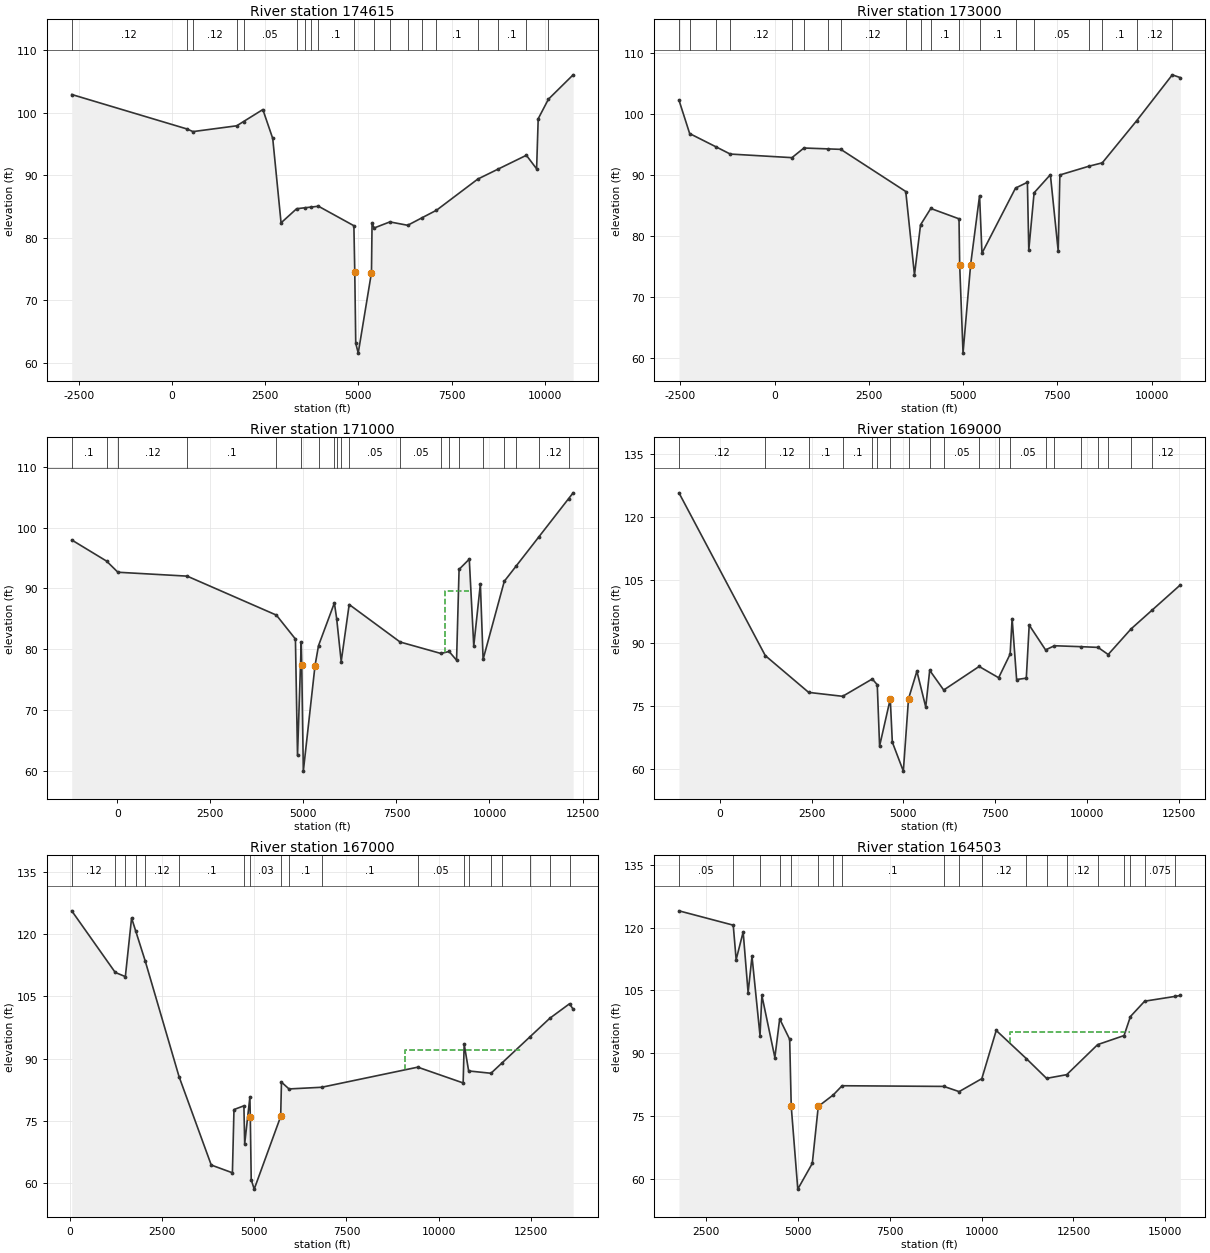
Type RM Length L Ch R = 1 ,174615  ,1615,1615,1615
BEGIN DESCRIPTION:
WFSJ Main 175.0
END DESCRIPTION:
XS GIS Cut Line= 3
      3872376.26     10059406.44      3865852.79     10054862.15
      3861752.05     10051204.03
#Sta/Elev= 30
 -2684.3  102.93   401.3   97.42   567.9   96.99  1740.6   97.92  1922.6    98.6
  2440.4  100.52  2705.7   95.89  2929.1   82.38  3346.6   84.64  3560.7   84.79
  3742.7   84.91  3932.1   85.04    4882   81.92 4905.73   74.46  4931.7   63.11
  4998.1   61.52 5353.5474.41957  5369.1   82.29    5426   81.56  5846.5   82.53
  6324.5   81.99  6717.7   83.22  7097.2    84.4  8204.7   89.39  8740.2   90.96
  9507.4    93.2  9781.8   91.03  9824.4   99.05 10097.5  102.17 10761.2  106.08
#Mann= 19 ,-1 , 0
 -2684.3     .12       0   401.3      .1       0   567.9     .12       0
  1740.6     .12       0  1922.6     .05       0  3346.6      .1       0
  3560.7     .05       0  3742.7     .12       0  3932.1      .1       0
    4882     .03       0    5426     .12       0  5846.5      .1       0
  6324.5     .12       0  6717.7      .1       0  7097.2      .1       0
  8204.7     .12       0  8740.2      .1       0  9507.4     .05       0
 10097.5     .12       0
Bank Sta=4905.73,5353.54
XS Rating Curve= 0 ,0
Exp/Cntr=0.3,0.1

Type RM Length L Ch R = 1 ,173000  ,2000,2000,2000
BEGIN DESCRIPTION:
WFSJ Main 173.0
END DESCRIPTION:
XS GIS Cut Line= 3
      3873274.64     10058364.74       3867204.5     10053902.34
      3862519.43     10050552.24
#Sta/Elev= 30
 -2533.9  102.34 -2249.7   96.85 -1547.2   94.66 -1173.4   93.49   462.6    92.9
   779.4   94.48  1407.9   94.34  1757.4   94.26  3479.7   87.35  3710.9   73.67
  3871.1   81.88  4142.8   84.57  4891.4   82.87 4909.09   75.35  4998.1   60.85
  5199.3   75.36  5436.4   86.67  5499.9   77.23  6389.6   87.91  6704.7   88.86
  6741.3   77.75  6882.2   87.14  7313.9   90.11  7521.5   77.57  7565.2   90.06
  8338.2    91.5    8690   92.05  9599.7   98.94 10546.2  106.48 10759.6  106.02
#Mann= 19 ,-1 , 0
 -2533.9     .05       0 -2249.7     .12       0 -1547.2      .1       0
 -1173.4     .12       0   462.6      .1       0   779.4     .12       0
  1407.9      .1       0  1757.4     .12       0  3479.7      .1       0
  3871.1     .05       0  4142.8      .1       0  4891.4     .07       0
  5436.4      .1       0  6389.6      .1       0  6882.2     .05       0
  8338.2     .12       0    8690      .1       0  9599.7     .12       0
 10546.2      .1       0
Bank Sta=4909.09,5199.3
XS Rating Curve= 0 ,0
Exp/Cntr=0.3,0.1

Type RM Length L Ch R = 1 ,171000  ,2000,2000,2000
BEGIN DESCRIPTION:
WFSJ Main 171.0
END DESCRIPTION:
XS GIS Cut Line= 3
      3873860.62     10057661.64       3869024.6     10053742.64
      3863326.77     10049263.21
#Sta/Elev= 30
 -1224.6   97.96  -288.7   94.49      16   92.66  1877.1   92.02  4274.2   85.62
  4785.8   81.69  4841.8   62.58  4942.4   81.21 4955.37   77.47  4998.1      60
  5312.8   77.34  5406.5   80.61  5832.4   87.61  5893.8   85.05  6015.7   77.99
  6230.2   87.36  7599.4    81.2  8695.8   79.32  8915.4   79.65  9115.6   78.21
  9183.1   93.13  9457.2   94.81  9577.5   80.55  9755.5   90.74  9828.6   78.36
 10398.4   91.18 10718.1   93.69 11320.7   98.42   12124  104.73 12247.8   105.7
#Mann= 20 ,-1 , 0
 -1224.6      .1       0  -288.7      .1       0      16     .12       0
  1877.1      .1       0  4274.2     .05       0  4942.4     .03       0
  5406.5     .05       0  5832.4     .12       0  5893.8      .1       0
  6015.7     .05       0  6230.2     .05       0  7599.4     .05       0
  8695.8      .1       0  8915.4      .1       0  9183.1     .05       0
  9828.6      .1       0 10398.4      .1       0 10718.1      .1       0
 11320.7     .12       0   12124      .1       0
#XS Ineff= 2 ,-1
  8794.8    9457   89.57  9457.2   10870   94.81
Permanent Ineff=
       F       F
Bank Sta=4955.37,5312.8
XS Rating Curve= 0 ,0
Exp/Cntr=0.3,0.1

Type RM Length L Ch R = 1 ,169000  ,2000,2000,2000
BEGIN DESCRIPTION:
WFSJ Main 169.0
END DESCRIPTION:
XS GIS Cut Line= 3
      3874711.29      10056376.9      3870140.21     10052312.51
      3864147.09     10047726.75
#Sta/Elev= 30
 -1116.7  125.71  1235.9   87.05  2418.5   78.31  3344.1   77.38  4151.7    81.5
  4287.3   80.12  4350.8   65.57  4641.8   76.77  4697.9   66.49  4998.1   59.61
  5138.7   76.78  5367.2   83.34  5608.3   74.84  5716.3   83.55  6097.9   78.87
  7063.4   84.47  7595.1   81.79  7908.2   87.41  7962.3   95.83  8084.7   81.37
  8348.6   81.69  8427.5    94.3  8873.7    88.4    9115   89.39  9834.7   89.17
 10303.1      89 10579.7   87.31 11202.5   93.38 11770.1    97.8 12546.3  103.84
#Mann= 20 ,-1 , 0
 -1116.7     .12       0  1235.9     .12       0  2418.5      .1       0
  3344.1      .1       0  4151.7     .12       0  4287.3     .05       0
  4641.8     .03       0  5138.7     .05       0  5716.3      .1       0
  6097.9     .05       0  7063.4     .05       0  7595.1     .12       0
  7908.2     .05       0  8873.7     .05       0    9115      .1       0
  9834.7     .05       0 10303.1      .1       0 10579.7     .12       0
 11202.5      .1       0 11770.1     .12       0
#XS Ineff= 1 ,-1
  7962.3   11670   95.83
Permanent Ineff=
       F
Bank Sta=4641.8,5138.7
XS Rating Curve= 0 ,0
Exp/Cntr=0.3,0.1

Type RM Length L Ch R = 1 ,167000  ,2497,2497,2497
BEGIN DESCRIPTION:
WFSJ Main 167.0
END DESCRIPTION:
XS GIS Cut Line= 3
      3875805.07     10055265.82      3872088.42     10051992.78
       3866075.3     10045774.81
#Sta/Elev= 30
    47.6  125.59    1227  110.77  1502.2  109.76  1671.2  123.87  1785.9  120.66
  2040.2  113.54  2957.9   85.72  3832.4   64.42  4406.4   62.55    4449   77.77
  4718.5   78.67  4739.4   69.52 4880.7380.77588 4891.76   75.99  4916.8   60.87
  4998.1   58.62  5715.8    76.1  5737.2   84.36  5942.2   82.73    6827   83.13
  9435.5   87.97 10666.2   84.17 10694.2   93.52 10815.1   87.06 11420.9    86.5
 11728.4   89.05 12467.5   95.18 13017.3   99.74 13552.5  103.23 13649.9  101.91
#Mann= 19 ,-1 , 0
    47.6     .12       0    1227      .1       0  1502.2     .12       0
  1785.9     .05       0  2040.2     .12       0  2957.9      .1       0
  4718.5     .05       0 4880.73     .03       0  5737.2     .05       0
  5942.2      .1       0    6827      .1       0  9435.5     .05       0
 10694.2      .1       0 10815.1     .05       0 11420.9      .1       0
 11728.4     .12       0 12467.5     .05       0 13017.3    .075       0
 13552.5     .05       0
#XS Ineff= 1 ,-1
  9082.1   12250   92.15
Permanent Ineff=
       F
Bank Sta=4891.76,5715.8
XS Rating Curve= 0 ,0
Exp/Cntr=0.3,0.1

Type RM Length L Ch R = 1 ,164503  ,1519,1519,1519
BEGIN DESCRIPTION:
WFSJ Main 165.0
END DESCRIPTION:
XS GIS Cut Line= 3
      3876603.69     10054536.66       3874173.1     10052127.77
      3866595.13     10045265.93
#Sta/Elev= 30
    1764     124  3241.5  120.58  3320.7  112.36  3511.6  118.96  3645.9  104.48
    3752  113.14  3970.2   94.24  4020.7  103.82  4374.3   89.01  4505.5   98.22
  4777.3   93.35  4819.7   77.36  4998.1   57.62    5393   63.76  5555.8   77.35
  5966.1   80.11  6204.2   82.28  8972.6   82.12    9389   80.88 10006.2   83.97
 10398.4   95.47 11218.1   88.75 11768.4   84.04 12316.5   84.92   13159   92.09
 13877.3   94.25 14050.9   98.79 14438.5  102.45 15265.9  103.59 15409.1  103.81
#Mann= 19 ,-1 , 0
    1764     .05       0  3241.5     .12       0  3970.2     .12       0
  4505.5     .05       0  4819.7     .03       0  5555.8     .05       0
  5966.1     .12       0  6204.2      .1       0  8972.6      .1       0
    9389      .1       0 10006.2     .12       0 11218.1      .1       0
 11768.4     .12       0 12316.5     .12       0   13159      .1       0
 13877.3     .12       0 14050.9     .05       0 14438.5    .075       0
 15265.9    .075       0
#XS Ineff= 1 ,-1
   10766   14050   94.99
Permanent Ineff=
       F
Bank Sta=4819.7,5555.8
XS Rating Curve= 0 ,0
Exp/Cntr=0.3,0.1