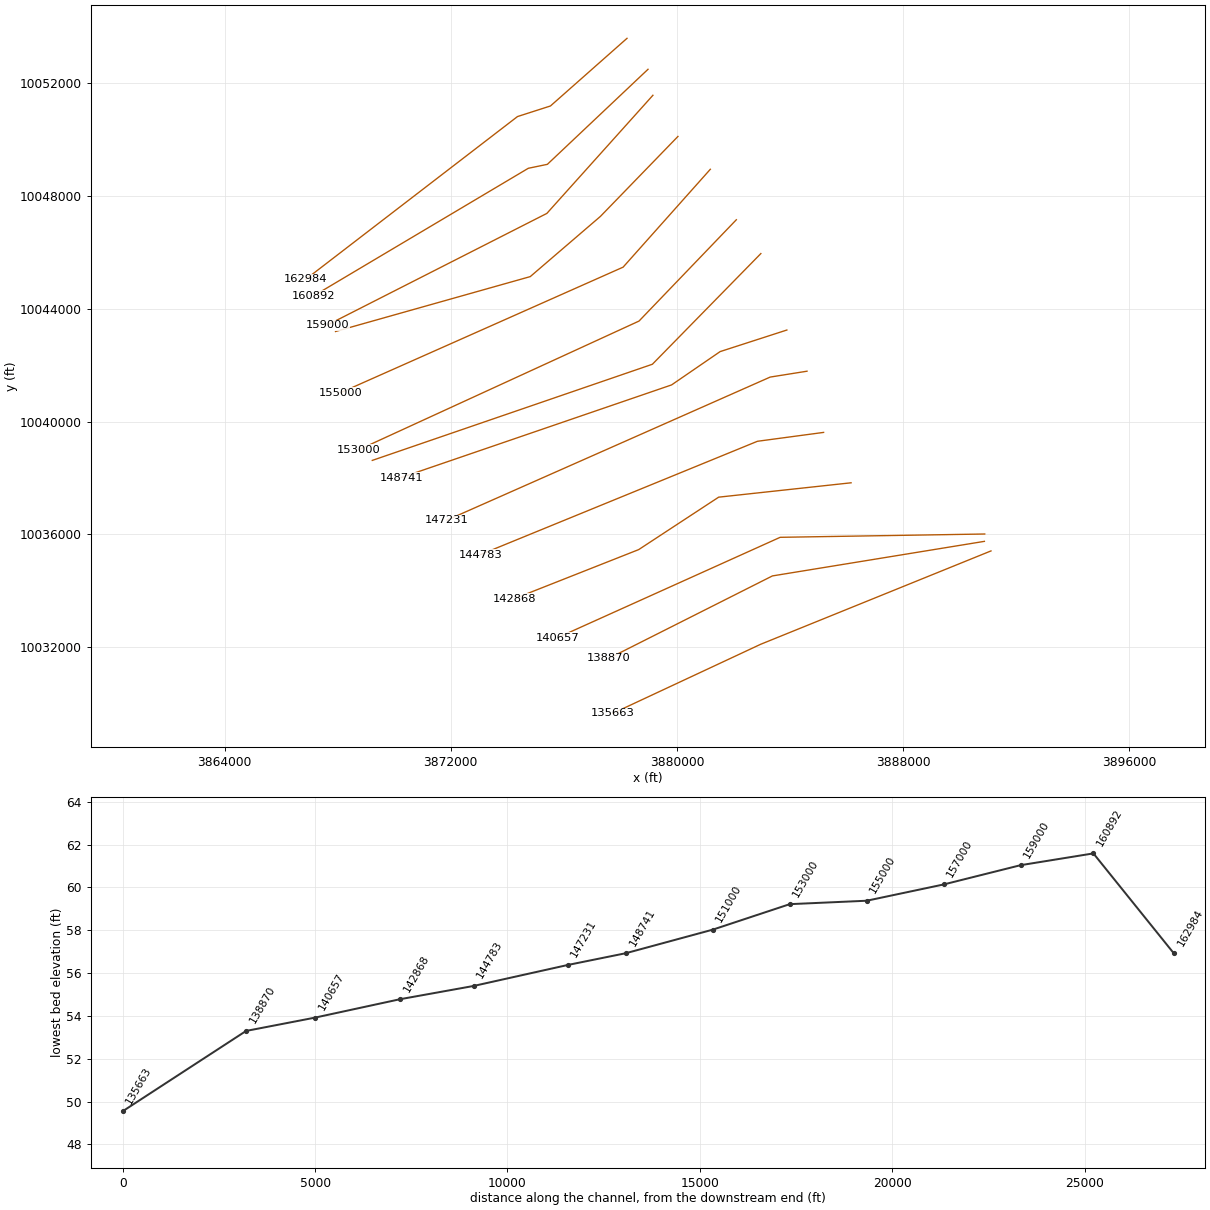
HEC-RAS study WFSJ Main.prj: WFSJ Main Base Level Engineering

--- WFSJ Main.g02 (geometry) --- (continued)

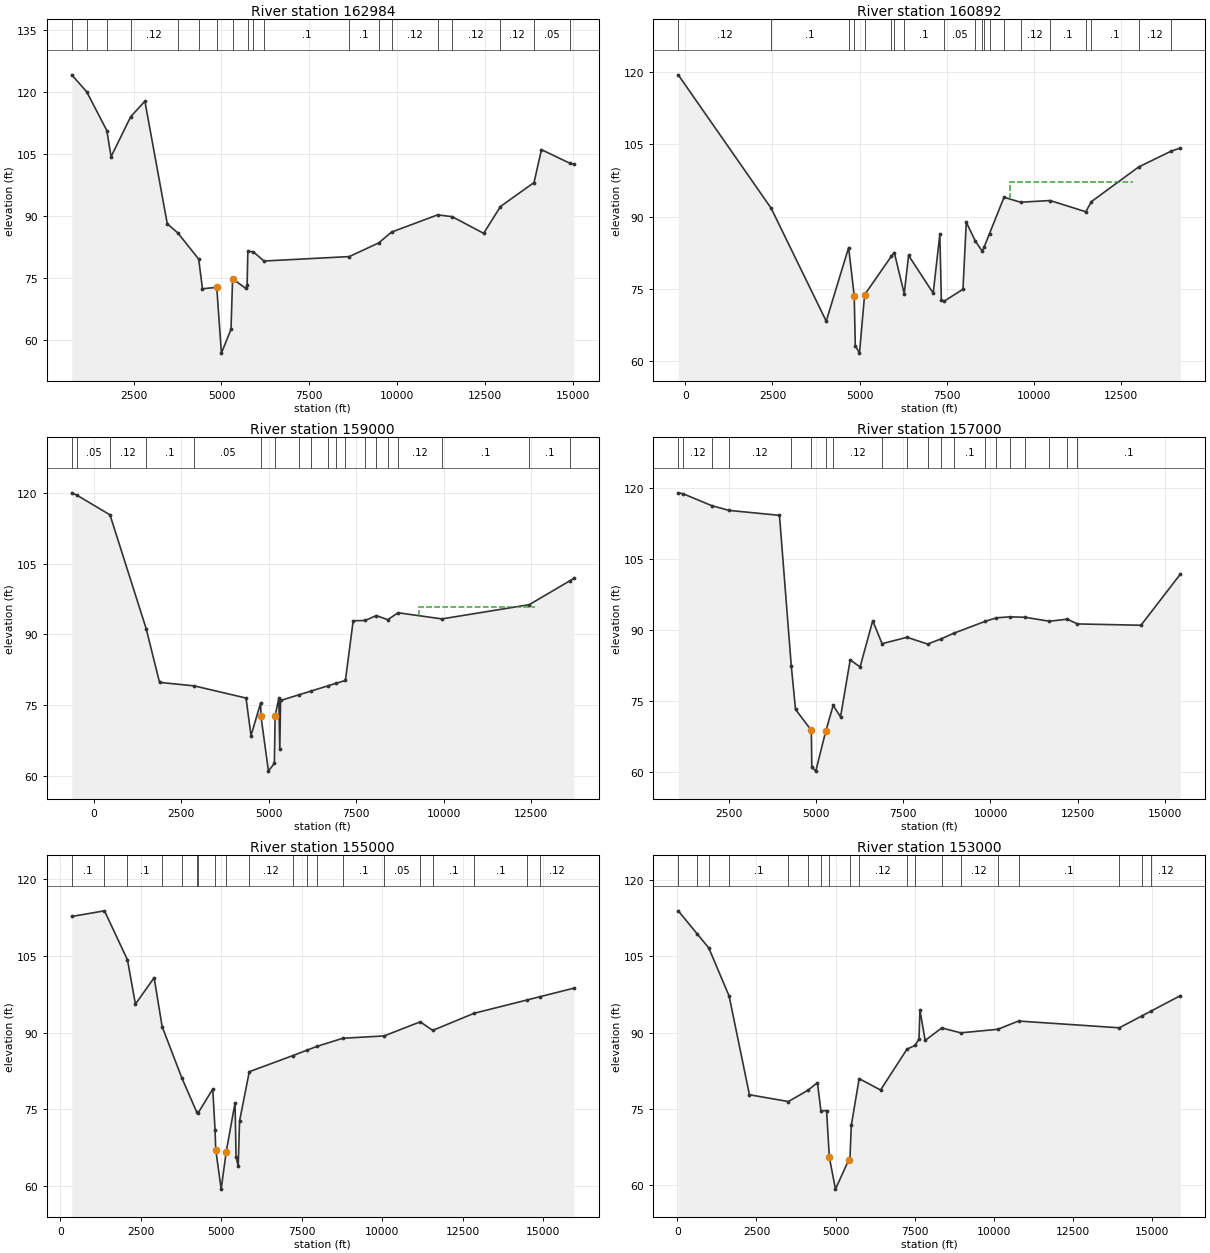
Type RM Length L Ch R = 1 ,162984  ,2092,2092,2092
BEGIN DESCRIPTION:
WFSJ Main 163.0
END DESCRIPTION:
XS GIS Cut Line= 4
      3878235.58     10053573.93      3875527.27     10051178.12
       3874360.6     10050803.12       3866861.7     10045033.14
#Sta/Elev= 30
   734.9  124.17  1161.6  120.05  1734.2   110.7  1854.3  104.38  2413.4  114.05
  2817.9   117.8  3455.5   88.18    3758   85.95  4350.8   79.64    4458   72.47
  4864.9   72.82  4998.1   56.92  5270.9   62.68  5316.6   74.91  5686.6   72.58
  5730.1    73.3  5750.9   81.52    5907    81.4  6210.5   79.18  8639.9   80.25
  9478.4   83.55  9845.4   86.17 11154.2   90.32 11569.7    89.9 12468.9   85.87
 12947.9   92.35 13903.4   98.14 14115.3  106.09 14923.7  102.81 15038.1  102.55
#Mann= 19 ,-1 , 0
   734.9     .05       0  1161.6     .12       0  1734.2     .12       0
  2413.4     .12       0    3758      .1       0  4350.8     .05       0
  4864.9     .03       0  5316.6     .05       0  5750.9      .1       0
    5907     .12       0  6210.5      .1       0  8639.9      .1       0
  9478.4     .12       0  9845.4     .12       0 11154.2      .1       0
 11569.7     .12       0 12947.9     .12       0 13903.4     .05       0
 14923.7     .05       0
Bank Sta=4864.9,5316.6
XS Rating Curve= 0 ,0
Exp/Cntr=0.3,0.1

Type RM Length L Ch R = 1 ,160892  ,1892,1892,1892
BEGIN DESCRIPTION:
WFSJ Main 161.0
END DESCRIPTION:
XS GIS Cut Line= 4
      3878979.17     10052477.53      3875417.85     10049111.07
      3874742.37     10048970.47       3867155.6      10044456.6
#Sta/Elev= 30
  -206.9  119.46    2463    91.7    4043   68.24  4686.6   83.54  4846.9   73.51
  4877.6   63.15  4998.1   61.59 5145.56   73.74  5912.6   81.72  5997.8   82.51
  6282.8   73.96  6408.2    81.9  7115.1   74.06    7306   86.31  7348.8    72.7
  7426.5   72.38  7970.1   74.87  8065.2   88.82  8321.7   84.94  8527.2   82.74
  8579.2   83.68  8732.7   86.46  9149.3      94  9624.6   92.97 10472.5   93.32
 11497.1   90.99   11658   93.09 13015.1   100.3 13949.2  103.59 14211.7  104.23
#Mann= 20 ,-1 , 0
  -206.9     .12       0    2463      .1       0  4686.6     .05       0
  4846.9     .03       0 5145.56     .05       0  5912.6      .1       0
  5997.8     .05       0  6282.8      .1       0  7426.5     .05       0
  8321.7     .12       0  8527.2      .1       0  8579.2     .05       0
  8732.7     .12       0  9149.3     .05       0  9624.6     .12       0
 10472.5      .1       0 11497.1     .05       0   11658      .1       0
 13015.1     .12       0 13949.2      .1       0
#XS Ineff= 2 ,-1
  8065.2    8930   88.82  9319.7   12860   97.09
Permanent Ineff=
       F       F
Bank Sta=4846.9,5145.56
XS Rating Curve= 0 ,0
Exp/Cntr=0.3,0.1

Type RM Length L Ch R = 1 ,159000  ,2000,2000,2000
BEGIN DESCRIPTION:
WFSJ Main 159.0
END DESCRIPTION:
XS GIS Cut Line= 3
      3879152.84     10051557.44      3875399.55     10047372.46
      3867625.45     10043415.49
#Sta/Elev= 30
  -621.5     120  -469.9  119.48   470.1  115.34    1503   91.25    1886   79.84
  2878.7    79.1  4357.4   76.52  4499.5   68.56  4775.3    75.5  4782.8   72.75
  4998.1   61.04  5166.5   62.71  5188.7   72.76  5293.6   76.44  5322.2    65.7
  5344.5   76.01  5881.4   77.24  6200.9   77.97  6697.4   79.11  6941.1   79.67
  7196.7   80.25  7418.5   92.89  7764.5   92.96  8078.3      94  8406.6   93.12
  8701.8   94.59  9952.9   93.29 12448.3    96.3 13599.7  101.33 13723.2  101.87
#Mann= 19 ,-1 , 0
  -621.5     .12       0  -469.9     .05       0   470.1     .12       0
    1503      .1       0  2878.7     .05       0  4775.3     .03       0
  5188.7     .05       0  5881.4     .12       0  6200.9     .05       0
  6697.4     .12       0  6941.1      .1       0  7196.7     .12       0
  7764.5     .05       0  8078.3     .12       0  8406.6      .1       0
  8701.8     .12       0  9952.9      .1       0 12448.3      .1       0
 13599.7     .12       0
#XS Ineff= 1 ,-1
  9286.8   12600   95.78
Permanent Ineff=
       F
Bank Sta=4782.8,5188.7
XS Rating Curve= 0 ,0
Exp/Cntr=0.3,0.1

Type RM Length L Ch R = 1 ,157000  ,2000,2000,2000
BEGIN DESCRIPTION:
WFSJ Main 157.0
END DESCRIPTION:
XS GIS Cut Line= 4
      3880038.25      10050099.1      3877297.09     10047268.69
      3874811.82     10045133.67       3867921.2     10043189.71
#Sta/Elev= 30
  1059.8  118.88  1207.7  118.66  2016.1  116.18  2515.5  115.17  3958.2  114.13
  4296.3   82.38  4417.9   73.17  4870.6   68.75  4884.7   60.95  4998.1   60.14
  5281.3   68.51  5496.4   74.02  5707.1    71.6  5983.7   83.62  6266.8   82.13
  6628.9   91.88  6896.7   87.04  7609.1   88.39  8201.3   86.96  8585.9   88.06
  8955.8   89.26  9854.2   91.77 10172.5    92.5 10550.5    92.7 10983.6   92.62
 11686.6   91.78 12200.3   92.21 12490.5   91.21 14309.9   90.93   15436  101.71
#Mann= 20 ,-1 , 0
  1059.8     .05       0  1207.7     .12       0  2016.1     .12       0
  2515.5     .12       0  4296.3     .05       0  4870.6     .03       0
  5281.3     .05       0  5496.4     .12       0  6896.7     .05       0
  7609.1     .12       0  8201.3     .05       0  8585.9     .12       0
  8955.8      .1       0  9854.2      .1       0 10172.5     .12       0
 10550.5      .1       0 10983.6      .1       0 11686.6      .1       0
 12200.3     .12       0 12490.5      .1       0
#XS Ineff= 1 ,-1
  6628.9    9960   91.88
Permanent Ineff=
       F
Bank Sta=4870.6,5281.3
XS Rating Curve= 0 ,0
Exp/Cntr=0.3,0.1

Type RM Length L Ch R = 1 ,155000  ,2000,2000,2000
BEGIN DESCRIPTION:
WFSJ Main 155.0
END DESCRIPTION:
XS GIS Cut Line= 3
      3881184.04     10048935.86      3878097.98     10045468.91
      3868093.82     10041019.24
#Sta/Elev= 30
   358.5  112.72  1374.5  113.82  2087.9  104.23  2335.1   95.57  2916.2  100.73
  3164.2   91.19    3773   81.19  4237.2   74.47  4275.8   74.22  4736.5   78.96
  4807.6   71.01  4828.5   67.13  4998.1   59.38  5151.3   66.58  5428.9   76.27
  5459.8   65.73  5527.3   63.84  5568.4    72.7  5870.7   82.35  7226.1   85.51
  7669.6   86.58  7981.2   87.33  8776.6   88.89 10059.2   89.35 11179.5   92.11
 11565.1   90.43 12853.2   93.78 14501.5   96.39 14901.8   97.03 15949.1   98.69
#Mann= 20 ,-1 , 0
   358.5      .1       0  1374.5     .05       0  2087.9      .1       0
  3164.2      .1       0    3773     .12       0  4237.2     .12       0
  4275.8     .05       0  4807.6     .03       0  5151.3     .05       0
  5870.7     .12       0  7226.1     .12       0  7669.6     .05       0
  7981.2      .1       0  8776.6      .1       0 10059.2     .05       0
 11179.5     .05       0 11565.1      .1       0 12853.2      .1       0
 14501.5     .12       0 14901.8     .12       0
Bank Sta=4828.5,5151.3
XS Rating Curve= 0 ,0
Exp/Cntr=0.3,0.1

Type RM Length L Ch R = 1 ,153000  ,2000,2000,2000
BEGIN DESCRIPTION:
WFSJ Main 153.0
END DESCRIPTION:
XS GIS Cut Line= 3
      3882104.19     10047147.68      3878660.37     10043558.69
      3868754.29      10039005.7
#Sta/Elev= 30
      26  113.94   622.7  109.43   990.8  106.65  1634.2    97.2  2277.2   77.78
  3508.5   76.44  4118.1   78.62  4427.3   80.16  4538.5   74.61  4717.3   74.66
 4803.64    65.5  4998.1   59.22    5421   65.02    5454   64.92    5498   71.74
  5747.1   80.95  6423.5   78.71  7262.4   86.76  7516.9   87.48  7639.4   88.76
  7667.9   94.48  7834.3   88.46  8359.4   90.91  8959.7   89.95 10133.2   90.65
 10785.7   92.27 13973.8   90.94   14697   93.31 14990.8   94.27 15902.3   97.26
#Mann= 19 ,-1 , 0
      26      .1       0   622.7      .1       0   990.8     .12       0
  1634.2      .1       0  3508.5     .12       0  4118.1     .12       0
  4538.5      .1       0  4802.2     .03       0    5454     .05       0
  5747.1     .12       0  7262.4     .12       0  7516.9     .05       0
  8359.4     .05       0  8959.7     .12       0 10133.2     .12       0
 10785.7      .1       0 13973.8     .12       0   14697     .05       0
 14990.8     .12       0
Bank Sta=4803.64,5421
XS Rating Curve= 0 ,0
Exp/Cntr=0.3,0.1

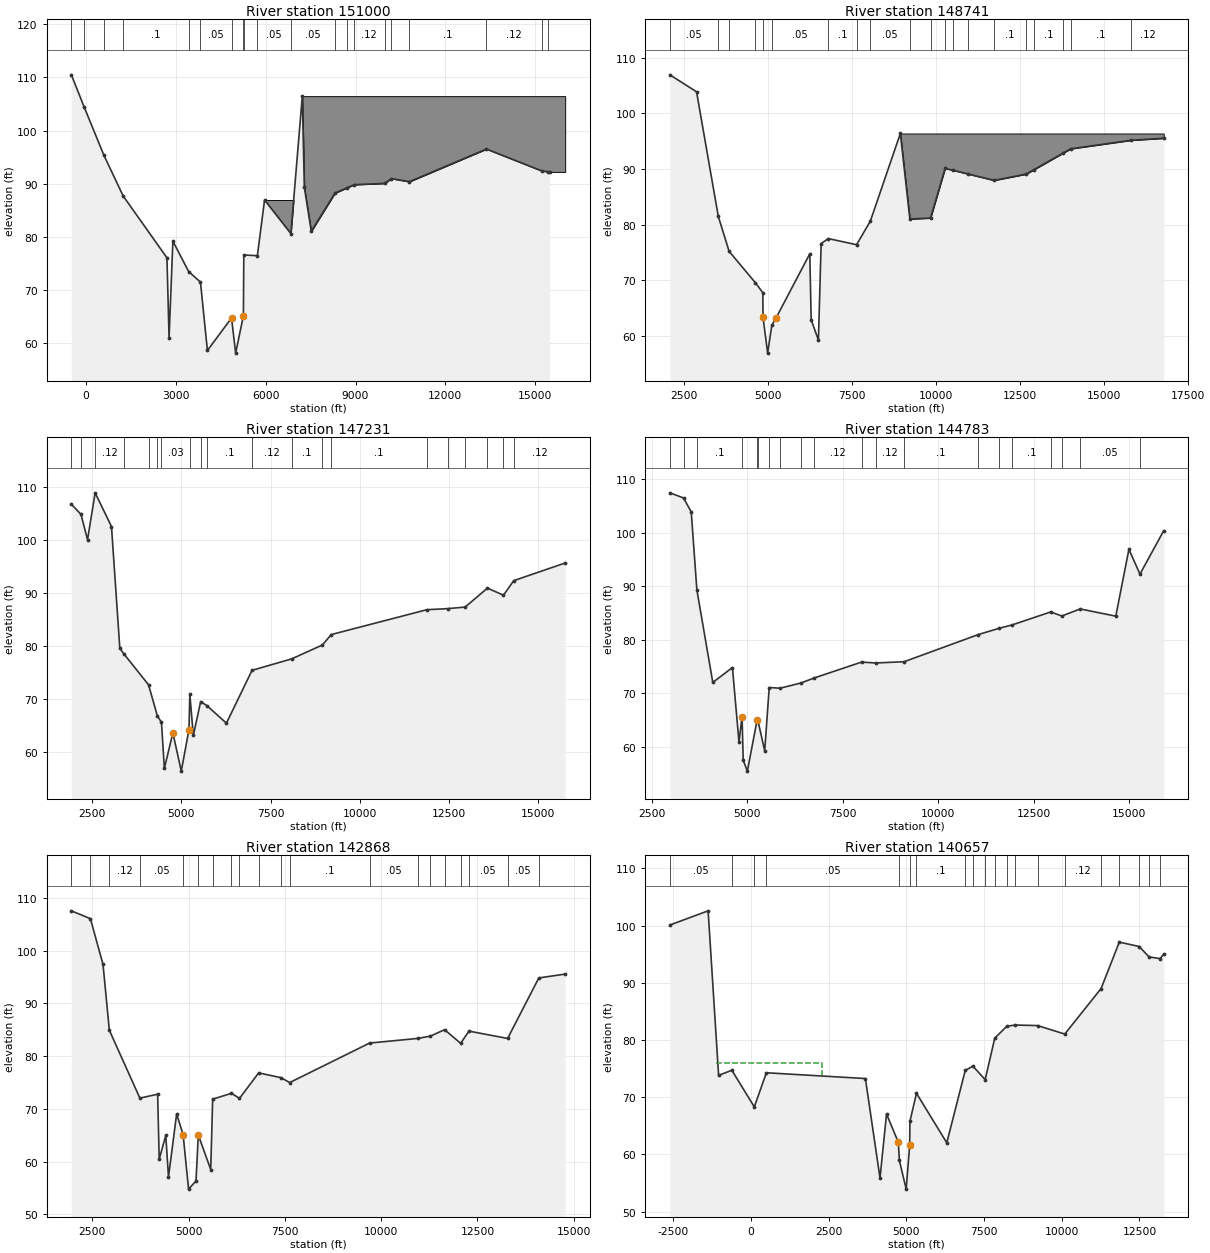
Type RM Length L Ch R = 1 ,151000  ,2259,2259,2259
BEGIN DESCRIPTION:
WFSJ Main 151.0
END DESCRIPTION:
XS GIS Cut Line= 3
      3882972.26     10045949.78      3879133.97     10042029.41
      3869222.54     10038623.49
#Sta/Elev= 30
  -486.5   110.5   -61.8  104.47   593.1   95.42  1241.6   87.67  2704.9      76
  2775.6   60.95  2902.9   79.15  3429.1   73.41  3823.3   71.43  4055.6   58.53
  4861.7   64.66  4998.1   58.03 5256.91   65.06  5270.8   76.53  5723.1    76.4
  5963.8    86.9  6841.6   80.57  7223.7  106.48  7291.5   89.26  7523.1      81
  8313.9    88.2  8725.8   89.23  8946.2   89.79  9975.3   90.03 10197.5   90.94
   10798   90.35 13372.4   96.51 15221.6   92.38 15431.2   92.23 15480.3    92.2
#Mann= 20 ,-1 , 0
  -486.5     .05       0   -61.8     .05       0   593.1      .1       0
  1241.6      .1       0  3429.1      .1       0  3823.3     .05       0
  4861.7     .03       0 5256.91     .05       0  5270.8      .1       0
  5723.1     .05       0  6841.6     .05       0  8313.9     .12       0
  8725.8      .1       0  8946.2     .12       0  9975.3      .1       0
 10197.5     .12       0   10798      .1       0 13372.4     .12       0
 15221.6      .1       0 15431.2     .12       0
#Block Obstruct= 2 ,-1
  7223.7   16000  106.48  5963.8    7223    86.9
Bank Sta=4861.7,5256.91
XS Rating Curve= 0 ,0
Exp/Cntr=0.3,0.1

Type RM Length L Ch R = 1 ,148741  ,1510,1510,1510
BEGIN DESCRIPTION:
WFSJ Main 149.0
END DESCRIPTION:
XS GIS Cut Line= 4
       3883892.4     10043241.45      3881531.29     10042477.56
      3879812.54     10041297.01      3870247.06     10038015.93
#Sta/Elev= 30
  2092.3  106.93  2884.8  103.88  3530.4   81.51  3852.2   75.22  4633.2   69.58
  4855.1   67.79  4860.5    63.4  4998.1   56.93    5121    61.9 5249.87  63.274
  6250.3   74.77  6292.2   62.91  6507.4   59.26    6588   76.62  6800.8   77.51
  7640.5   76.41  8048.5   80.61  8942.5   96.39  9224.9   81.03  9839.6    81.2
 10272.7   90.13 10505.4   89.79 10956.3   89.12 11730.7   87.97 12681.5    89.1
 12903.4   89.86 13788.5    92.9 14003.1   93.64 15799.7   95.17 16771.6   95.54
#Mann= 20 ,-1 , 0
  2092.3     .05       0  3530.4     .12       0  3852.2      .1       0
  4633.2     .05       0  4855.1     .03       0    5121     .05       0
  6800.8      .1       0  7640.5     .12       0  8048.5     .05       0
  9224.9     .05       0  9839.6     .05       0 10272.7     .05       0
 10505.4     .12       0 10956.3      .1       0 11730.7      .1       0
 12681.5     .12       0 12903.4      .1       0 13788.5     .12       0
 14003.1      .1       0 15799.7     .12       0
#Block Obstruct= 1 ,-1
  8942.5   16771   96.39
Bank Sta=4860.5,5249.87
XS Rating Curve= 0 ,0
Exp/Cntr=0.3,0.1

Type RM Length L Ch R = 1 ,147231  ,2448,2448,2448
BEGIN DESCRIPTION:
WFSJ Main 147.0
END DESCRIPTION:
XS GIS Cut Line= 3
      3884605.29     10041782.93      3883302.12     10041574.78
      3871862.87      10036506.1
#Sta/Elev= 30
  1919.2  106.82  2188.3  104.91  2372.3  100.13  2585.4  108.98  3043.1  102.61
  3276.4   79.62  3385.6   78.58  4081.6   72.69  4328.5   66.81  4443.2    65.6
    4524   56.88  4762.3   63.61  4998.1   56.38 5212.76   64.22  5237.4   70.88
    5336   63.12  5540.5   69.51  5716.8   68.76  6262.4   65.44  6979.7   75.43
  8091.7    77.6  8950.7   80.22  9198.7   82.19 11876.5   86.89 12456.7   87.09
 12949.6   87.39 13573.9   90.97 14022.5   89.63 14310.1   92.38 15750.8   95.72
#Mann= 20 ,-1 , 0
  1919.2     .12       0  2188.3     .12       0  2585.4     .12       0
  3385.6      .1       0  4081.6      .1       0  4328.5     .05       0
  4443.2     .03       0  5237.4     .05       0  5540.5     .12       0
  5716.8      .1       0  6979.7     .12       0  8091.7      .1       0
  8950.7     .05       0  9198.7      .1       0 11876.5      .1       0
 12456.7     .12       0 12949.6     .12       0 13573.9     .12       0
 14022.5      .1       0 14310.1     .12       0
Bank Sta=4762.3,5212.76
XS Rating Curve= 0 ,0
Exp/Cntr=0.3,0.1

Type RM Length L Ch R = 1 ,144783  ,1915,1915,1915
BEGIN DESCRIPTION:
WFSJ Main 145.0
END DESCRIPTION:
XS GIS Cut Line= 3
      3885192.46     10039614.88      3882850.74     10039300.48
      3873059.03     10035290.05
#Sta/Elev= 30
  2967.7  107.46  3324.6   106.5  3527.3  103.88  3674.9   89.29  4092.3   71.99
  4606.9   74.78  4778.4   60.85  4859.1   65.61  4889.4   57.45  4998.1    55.4
 5252.5564.92963  5278.2   64.75  5452.7    59.2    5571   71.04  5852.3   70.91
  6400.8   71.88  6750.9   72.83  7992.4    75.8  8362.6   75.63  9108.1   75.87
 11048.2   80.94 11583.6   82.09 11938.5   82.75 12945.5   85.17 13241.2   84.42
 13722.6   85.74 14654.8   84.39 14999.2   96.89 15288.7   92.25 15911.6  100.38
#Mann= 20 ,-1 , 0
  2967.7     .12       0  3324.6     .05       0  3674.9      .1       0
  4859.1     .07       0 5252.55      .1       0  5278.2      .1       0
    5571     .12       0  5852.3      .1       0  6400.8      .1       0
  6750.9     .12       0  7992.4      .1       0  8362.6     .12       0
  9108.1      .1       0 11048.2     .12       0 11583.6     .05       0
 11938.5      .1       0 12945.5      .1       0 13241.2      .1       0
 13722.6     .05       0 15288.7     .12       0
Bank Sta=4859.1,5252.55
XS Rating Curve= 0 ,0
Exp/Cntr=0.3,0.1

Type RM Length L Ch R = 1 ,142868  ,2211,2211,2211
BEGIN DESCRIPTION:
WFSJ Main 143.0
END DESCRIPTION:
XS GIS Cut Line= 4
      3886165.18     10037830.17      3881479.21     10037321.31
      3878649.35     10035463.67      3874257.02     10033727.58
#Sta/Elev= 30
  1955.1  107.53    2450  106.04  2777.2   97.36  2941.2    84.9  3734.3   72.03
  4195.5   72.77  4235.8   60.45  4406.8   64.96  4477.2   57.06  4688.4   69.02
 4856.48   65.13  4998.1   54.78  5191.3   56.33  5251.7   65.04  5573.6   58.49
  5623.9   71.83  6112.2   72.94  6320.1   71.98  6818.2   76.81  7395.2   75.91
    7624   74.98  9700.3   82.47 10954.1   83.35   11276   83.78 11646.2      85
 12063.3   82.41 12277.9   84.73 13281.3   83.34 14092.2   94.81 14776.7   95.54
#Mann= 20 ,-1 , 0
  1955.1     .12       0    2450     .05       0  2941.2     .12       0
  3734.3     .05       0 4856.48     .03       0  5251.7     .05       0
  5623.9      .1       0  6112.2     .12       0  6320.1      .1       0
  6818.2     .12       0  7395.2     .05       0    7624      .1       0
  9700.3     .05       0 10954.1     .12       0   11276     .05       0
 11646.2     .12       0 12063.3      .1       0 12277.9     .05       0
 13281.3     .05       0 14092.2     .05       0
Bank Sta=4856.48,5251.7
XS Rating Curve= 0 ,0
Exp/Cntr=0.3,0.1

Type RM Length L Ch R = 1 ,140657  ,1787,1787,1787
BEGIN DESCRIPTION:
WFSJ Main 141.0
END DESCRIPTION:
XS GIS Cut Line= 3
      3890894.78     10036015.93      3883655.16     10035898.74
       3875777.6     10032344.07
#Sta/Elev= 30
 -2601.6  100.11 -1372.1  102.59 -1034.5   73.81    -609   74.71   113.7    68.3
   501.4   74.27  3686.2   73.26  4156.2   55.86  4366.2   67.06    4747   62.09
  4778.6   58.94  4998.1   53.92 5110.1161.62156  5118.7   65.78  5329.4   70.68
  6303.9   62.02  6897.5   74.67  7142.8   75.43  7538.1   73.07  7846.9   80.32
  8236.3   82.41  8509.6   82.62  9225.2   82.52 10098.5   81.04 11266.9      89
 11853.1   97.12 12491.3   96.35 12810.4   94.53 13165.7   94.23 13281.4   95.02
#Mann= 20 ,-1 , 0
 -2601.6     .05       0    -609      .1       0   113.7     .05       0
   501.4     .05       0  4778.6     .03       0  5118.7     .05       0
  5329.4      .1       0  6897.5     .05       0  7142.8      .1       0
  7538.1     .12       0  7846.9     .05       0  8236.3     .12       0
  8509.6      .1       0  9225.2     .05       0 10098.5     .12       0
 11266.9     .05       0 11853.1     .05       0 12491.3     .05       0
 12810.4      .1       0 13165.7     .05       0
#XS Ineff= 1 ,-1
   -1125    2286   75.97
Permanent Ineff=
       F
Bank Sta=4747,5110.11
XS Rating Curve= 0 ,0
Exp/Cntr=0.3,0.1

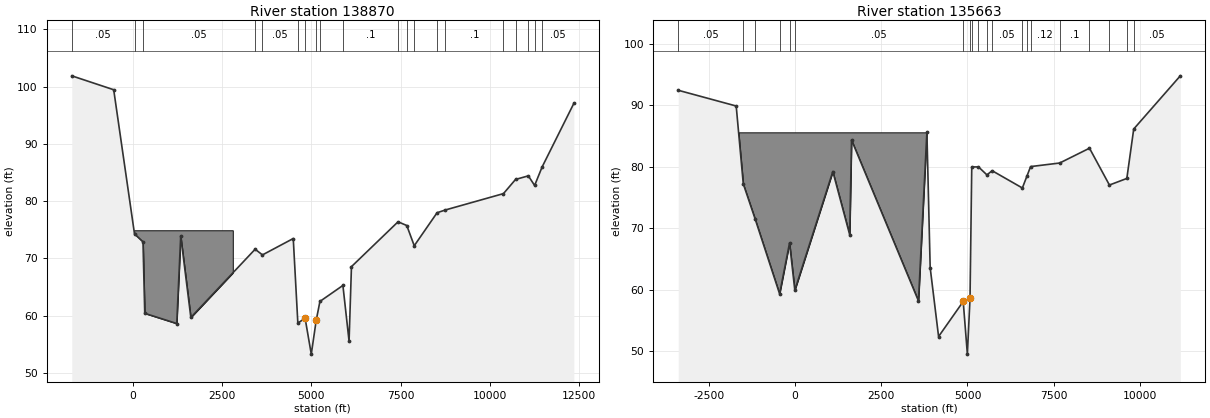
Type RM Length L Ch R = 1 ,138870  ,3207,3207,3207
BEGIN DESCRIPTION:
WFSJ Main 139.0
END DESCRIPTION:
XS GIS Cut Line= 3
      3890881.74     10035755.52      3883381.73     10034531.55
      3877602.85     10031616.08
#Sta/Elev= 30
 -1714.9  101.88  -539.7   99.45    43.6   74.28   281.2    72.9   330.6   60.42
  1227.4   58.64  1338.9   73.91  1622.6    59.7  3424.4   71.61  3629.7   70.62
  4492.7   73.48  4621.5   58.71  4824.4   59.58  4998.1    53.3 5137.0359.23381
  5240.6    62.5  5884.5   65.29  6057.1   55.56    6124   68.57  7429.8    76.4
  7674.7   75.75  7883.7   72.22  8523.7   77.98  8759.1   78.47 10384.4   81.32
 10722.5   83.79 11081.5   84.42 11257.6   82.74 11468.3   85.98   12357   97.07
#Mann= 20 ,-1 , 0
 -1714.9     .05       0    43.6      .1       0   281.2     .05       0
  3424.4      .1       0  3629.7     .05       0  4621.5     .05       0
  4824.4     .03       0 5137.03     .05       0  5240.6     .12       0
  5884.5      .1       0  7429.8     .05       0  7674.7     .12       0
  7883.7      .1       0  8523.7     .12       0  8759.1      .1       0
 10384.4     .05       0 10722.5     .12       0 11081.5     .05       0
 11257.6     .12       0 11468.3     .05       0
#Block Obstruct= 1 ,-1
    -230  2797.9   74.92
Bank Sta=4824.4,5137.03
XS Rating Curve= 0 ,0
Exp/Cntr=0.3,0.1

Type RM Length L Ch R = 1 ,135663  ,2663,2663,2663
BEGIN DESCRIPTION:
WFSJ Main 137.0
END DESCRIPTION:
XS GIS Cut Line= 3
      3891116.08     10035416.96      3882965.06     10032109.68
       3877731.8     10029662.28
#Sta/Elev= 30
 -3394.6   92.46 -1712.1    89.9 -1506.7   77.24 -1163.7   71.55  -452.1   59.35
  -163.5   67.62   -10.7   59.94  1092.9   79.25  1582.7   68.96  1636.3   84.37
  3578.3   58.21  3823.2   85.62  3918.5   63.61  4162.3   52.41  4877.5   58.11
    4998   49.55  5075.1   58.64  5125.4   79.99  5320.3      80    5566    78.7
  5716.9   79.38  6594.1   76.57  6724.3   78.46  6833.7   80.05  7677.5   80.63
  8542.9   83.04  9121.3   77.05  9626.8   78.12  9826.6   86.16 11179.1   94.81
#Mann= 20 ,-1 , 0
 -3394.6     .05       0 -1506.7      .1       0 -1163.7     .05       0
  -452.1     .05       0  -163.5      .1       0   -10.7     .05       0
  4877.5     .03       0  5075.1     .05       0  5125.4     .05       0
  5320.3     .12       0    5566     .12       0  5716.9     .05       0
  6594.1     .12       0  6724.3     .05       0  6833.7     .12       0
  7677.5      .1       0  8542.9      .1       0  9121.3     .05       0
  9626.8    .075       0  9826.6     .05       0
#Block Obstruct= 1 ,-1
   -1750  3823.2   85.62
Bank Sta=4877.5,5075.1
XS Rating Curve= 0 ,0
Exp/Cntr=0.3,0.1