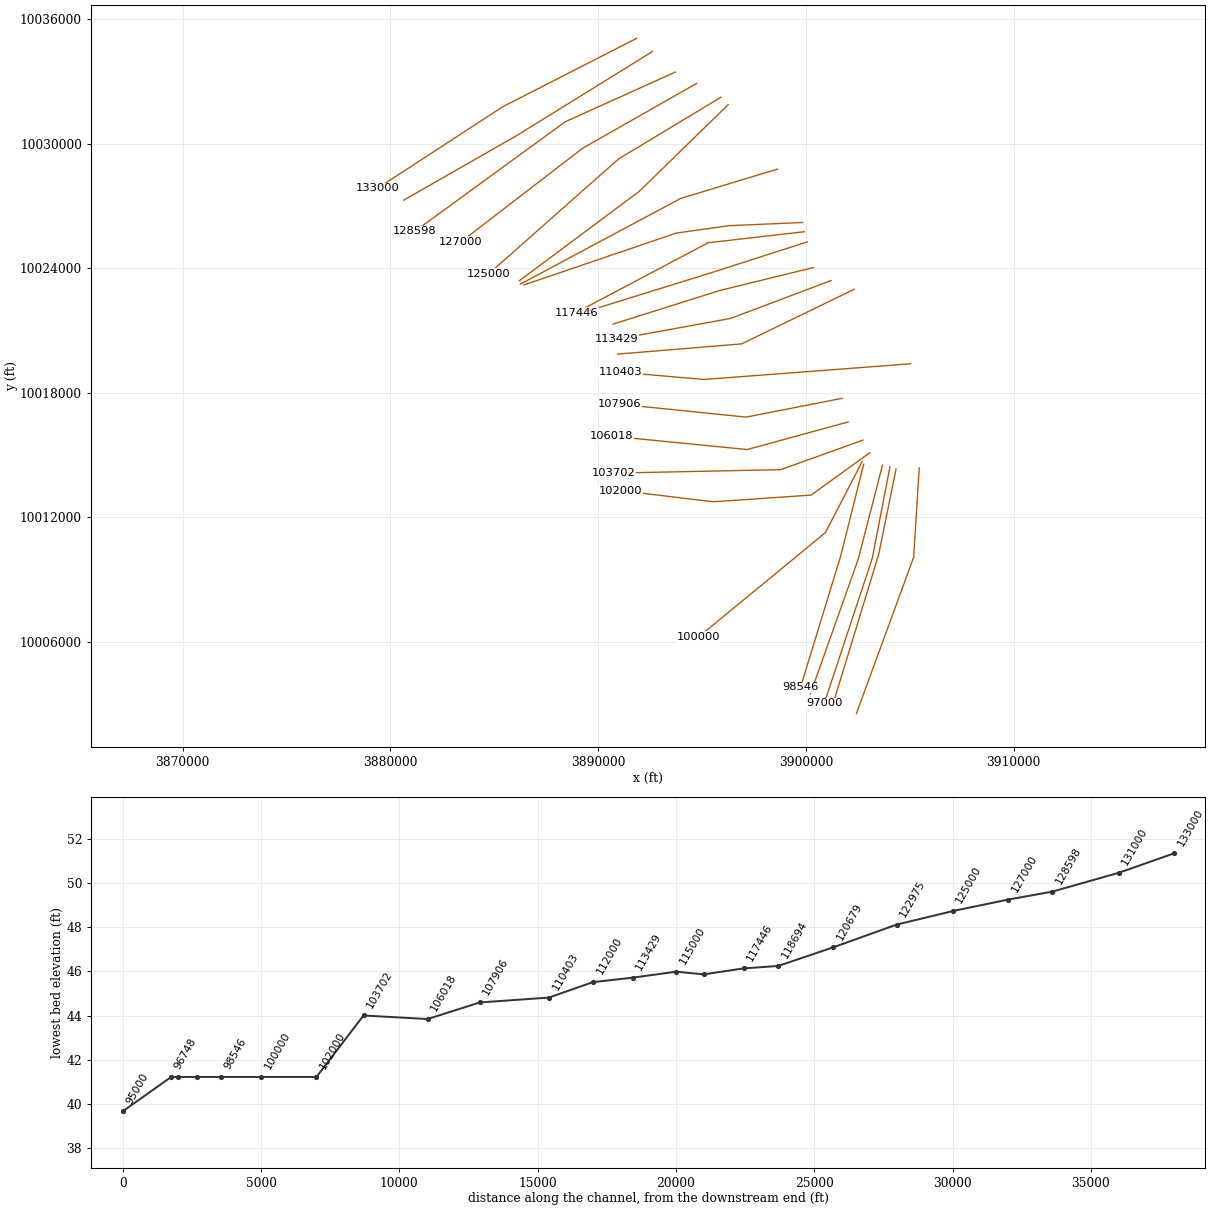
HEC-RAS study WFSJ Main.prj: WFSJ Main Base Level Engineering

--- WFSJ Main.g02 (geometry) --- (continued)

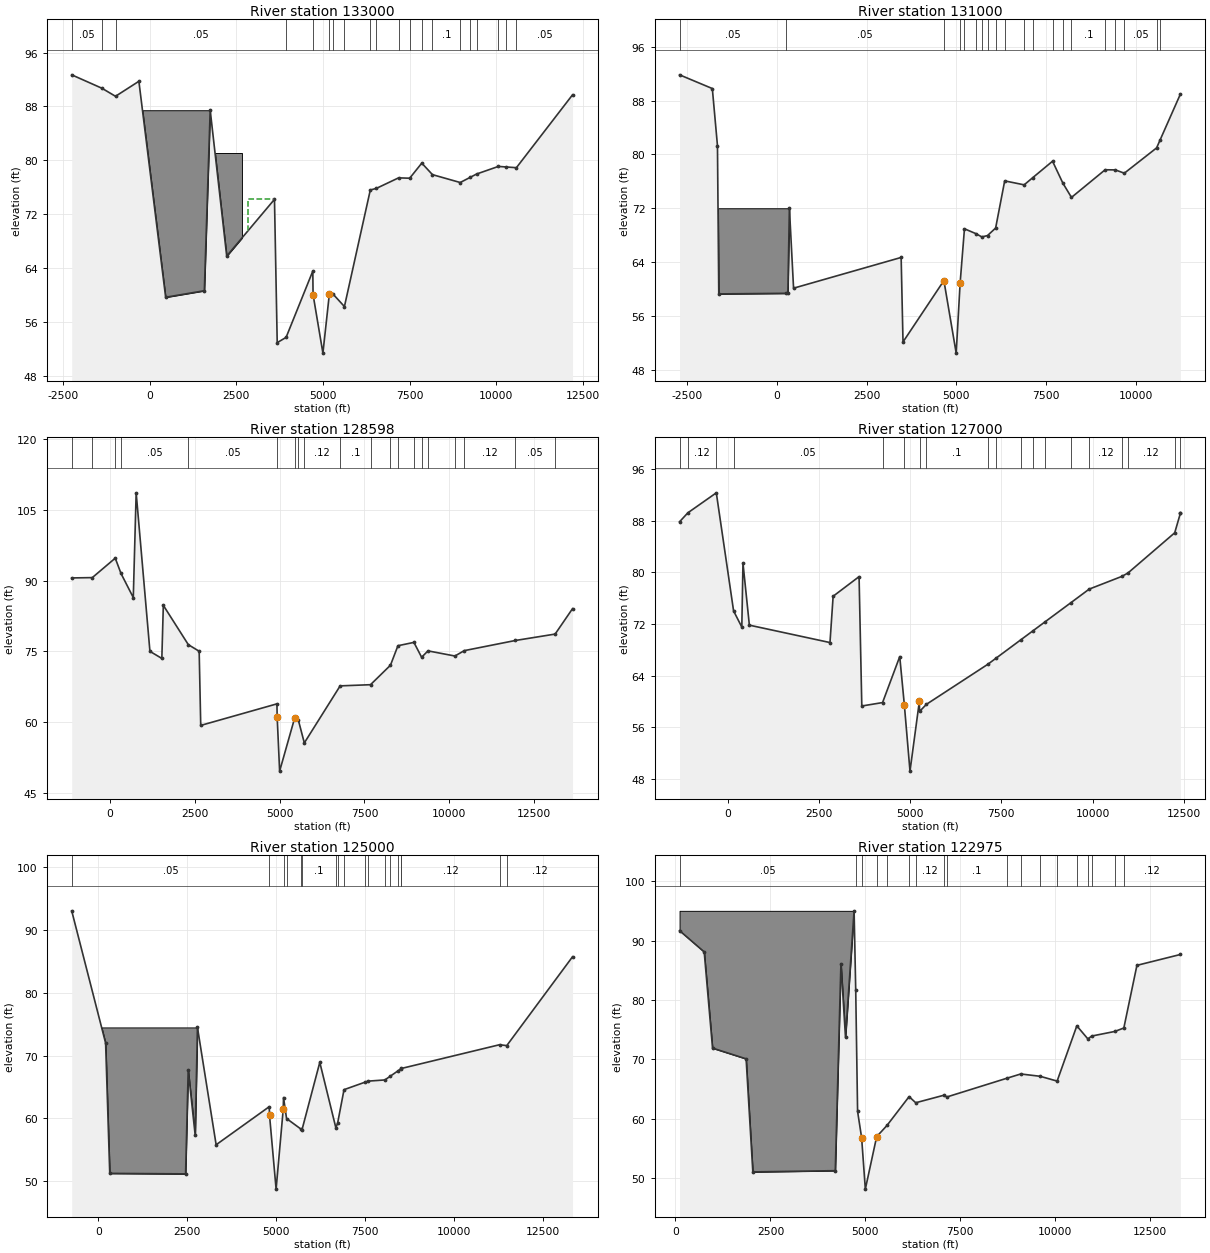
Type RM Length L Ch R = 1 ,133000  ,2000,2000,2000
BEGIN DESCRIPTION:
WFSJ Main 133.0
END DESCRIPTION:
XS GIS Cut Line= 3
      3891852.24     10035080.18      3885403.31     10031781.77
      3879377.57     10027852.24
#Sta/Elev= 30
 -2243.5   92.69 -1373.8    90.7    -981    89.5  -307.1   91.73   464.7   59.64
  1580.3   60.61  1748.8   87.43  2224.9   65.76  3601.8   74.19  3680.7    52.9
  3936.9   53.68  4706.8   63.53  4714.1   60.05    4998   51.34 5184.63   60.16
  5276.1   60.19  5618.2   58.26  6364.3   75.58  6539.9   75.82  7178.5   77.38
  7499.7   77.33  7848.1   79.57  8155.8   77.86  8955.7   76.69  9237.2   77.44
  9427.4   77.95 10056.5   79.08 10280.6      79 10575.4   78.89 12193.8   89.72
#Mann= 20 ,-1 , 0
 -2243.5     .05       0 -1373.8     .12       0    -981     .05       0
  3936.9     .05       0  4706.8     .03       0 5184.63     .05       0
  5276.1     .05       0  5618.2     .05       0  6364.3     .12       0
  6539.9     .05       0  7178.5     .12       0  7499.7      .1       0
  7848.1     .12       0  8155.8      .1       0  8955.7     .12       0
  9237.2     .05       0  9427.4     .12       0 10056.5     .12       0
 10280.6     .12       0 10575.4     .05       0
#XS Ineff= 1 ,-1
    2844  3601.8   74.19
Permanent Ineff=
       F
#Block Obstruct= 2 ,-1
    -298  1748.8   87.43    1750  2663.5   81.08
Bank Sta=4714.1,5184.63
XS Rating Curve= 0 ,0
Exp/Cntr=0.3,0.1

Type RM Length L Ch R = 1 ,131000  ,2402,2402,2402
BEGIN DESCRIPTION:
WFSJ Main 131.0
END DESCRIPTION:
XS GIS Cut Line= 3
      3892624.81     10034450.84      3886066.14     10030386.69
      3880641.41      10027284.5
#Sta/Elev= 30
 -2715.8   91.82 -1801.8   89.78 -1658.6   81.29   -1622   59.26   255.4   59.35
     304   59.36   347.5   71.99   463.3   60.11  3463.1   64.68  3515.1   52.12
  4655.2   61.24    4998   50.46 5108.4160.92697  5228.5   68.94  5541.5   68.23
  5713.7   67.73  5871.4   67.93  6097.7   69.05  6350.5   76.06  6893.1   75.47
  7128.9   76.52  7684.8   78.98  7972.9   75.72  8212.5    73.6  9151.3   77.71
  9436.3   77.69  9686.3    77.2 10586.3   80.96 10687.1   82.18 11249.1   88.95
#Mann= 20 ,-1 , 0
 -2715.8     .05       0   255.4     .05       0  4655.2     .03       0
 5108.41     .05       0  5228.5      .1       0  5541.5     .12       0
  5713.7      .1       0  5871.4      .1       0  6097.7      .1       0
  6350.5     .12       0  6893.1     .05       0  7128.9     .05       0
  7684.8     .12       0  7972.9     .12       0  8212.5      .1       0
  9151.3     .12       0  9436.3     .05       0  9686.3     .05       0
 10586.3    .075       0 10687.1     .05       0
#Block Obstruct= 1 ,-1
   -1760   347.5   71.99
Bank Sta=4655.2,5108.41
XS Rating Curve= 0 ,0
Exp/Cntr=0.3,0.1

Type RM Length L Ch R = 1 ,128598  ,1598,1598,1598
BEGIN DESCRIPTION:
WFSJ Main 129.0
END DESCRIPTION:
XS GIS Cut Line= 3
      3893709.89     10033452.58      3888412.11     10031059.33
      3881177.45     10025782.14
#Sta/Elev= 30
 -1133.1   90.56  -525.5   90.63     151   94.75   320.4   91.51   682.7    86.4
   767.5   108.6  1173.5      75  1524.6    73.5  1568.5   84.75  2306.3   76.41
  2625.4   75.02  2671.6    59.3  4918.8   63.87    4925   61.16    4998   49.61
  5440.5   60.85    5550   60.43  5726.1   55.59  6782.6   67.68  7677.8   67.93
  8266.5   72.06  8486.3   76.19  8957.7    76.9  9184.8   73.75  9372.6    75.1
   10167   74.01 10442.6   75.15 11948.7    77.3 13121.9   78.66   13635   84.05
#Mann= 20 ,-1 , 0
 -1133.1     .12       0  -525.5      .1       0     151     .12       0
   320.4     .05       0  2306.3     .05       0  4918.8     .03       0
  5440.5     .05       0    5550     .05       0  5726.1     .12       0
  6782.6      .1       0  7677.8     .12       0  8266.5     .12       0
  8486.3     .05       0  8957.7     .12       0  9184.8      .1       0
  9372.6     .12       0   10167      .1       0 10442.6     .12       0
 11948.7     .05       0 13121.9     .05       0
Bank Sta=4925,5440.5
XS Rating Curve= 0 ,0
Exp/Cntr=0.3,0.1

Type RM Length L Ch R = 1 ,127000  ,2000,2000,2000
BEGIN DESCRIPTION:
WFSJ Main 127.0
END DESCRIPTION:
XS GIS Cut Line= 3
      3894739.98     10032907.15      3889252.05     10029783.15
       3883384.9     10025265.18
#Sta/Elev= 30
 -1314.8    87.8 -1087.2   89.19  -307.8   92.28   165.5   74.02   390.9   71.52
   422.6   81.41   597.8   71.82  2806.2   69.13  2892.6   76.29  3603.1   79.32
    3678   59.32  4246.7   59.85  4717.2   66.96  4843.7   59.48    4998   49.25
  5254.4   60.02  5260.7   58.48  5448.3   59.58  7130.6   65.77  7359.5   66.73
  8040.3   69.58  8358.1   70.91  8706.7   72.37  9403.2   75.28  9906.4   77.39
 10798.2   79.35 10968.5   79.88   12250    86.1 12403.8   89.09 12405.1   89.12
#Mann= 19 ,-1 , 0
 -1314.8      .1       0 -1087.2     .12       0  -307.8      .1       0
   165.5     .05       0  4246.7     .05       0  4843.7     .03       0
  5260.7     .05       0  5448.3      .1       0  7130.6     .05       0
  7359.5     .12       0  8040.3     .12       0  8358.1     .12       0
  8706.7     .12       0  9403.2     .05       0  9906.4     .12       0
 10798.2      .1       0 10968.5     .12       0   12250     .05       0
 12403.8     .12       0
#XS Ineff= 1 ,-1
    -175  3603.1   79.32
Permanent Ineff=
       F
Bank Sta=4843.7,5254.4
XS Rating Curve= 0 ,0
Exp/Cntr=0.3,0.1

Type RM Length L Ch R = 1 ,125000  ,2025,2025,2025
BEGIN DESCRIPTION:
WFSJ Main 125.0
END DESCRIPTION:
XS GIS Cut Line= 3
       3895906.6     10032240.46      3890981.84     10029269.33
       3884741.4     10023741.75
#Sta/Elev= 30
  -751.6   93.08   202.1   72.01   318.6   51.24  2451.9   51.16  2525.7   67.72
  2721.7   57.34  2785.8    74.5  3311.2    55.8  4806.1   61.87  4812.3   60.55
    4998   48.73  5198.8   61.48  5206.7   63.33    5292   59.98  5708.9   58.25
  5726.3   58.19  6227.1   68.93    6679    58.5  6728.6   59.25  6908.7   64.58
  7493.4   65.76  7583.1   65.94  8058.6   66.13  8205.5   66.71  8429.8   67.59
  8515.7   67.93  8523.4   67.96 11282.6   71.74 11486.3    71.6 13336.5   85.76
#Mann= 18 ,-1 , 0
  -751.6     .05       0  4806.1     .03       0  5206.7     .05       0
    5292     .05       0  5708.9     .12       0  5726.3      .1       0
    6679     .12       0  6728.6     .05       0  6908.7      .1       0
  7493.4     .12       0  7583.1      .1       0  8058.6     .12       0
  8205.5     .05       0  8429.8     .12       0  8515.7     .05       0
  8523.4     .12       0 11282.6      .1       0 11486.3     .12       0
#Block Obstruct= 1 ,-1
    -175  2785.8    74.5
Bank Sta=4812.3,5198.8
XS Rating Curve= 0 ,0
Exp/Cntr=0.3,0.1

Type RM Length L Ch R = 1 ,122975  ,2296,2296,2296
BEGIN DESCRIPTION:
WFSJ Main 123.0
END DESCRIPTION:
XS GIS Cut Line= 3
      3896260.75     10031886.28      3891969.11      10027698.8
      3886205.33     10023402.72
#Sta/Elev= 30
     107   91.69   756.2    88.1   975.5   71.89  1859.4   70.08  2036.3   51.02
  4207.1   51.23  4355.7   86.12  4475.9   73.73  4702.2   95.03  4744.7   81.74
  4794.1   61.22  4900.3   56.79    4998   48.12  5296.2   56.96  5567.5   58.85
  6150.1   63.71  6324.6   62.68    7062   63.94  7147.4   63.66  8723.4   66.81
  9089.9   67.53  9600.2   67.14 10046.9   66.33 10565.9   75.64 10856.8   73.44
 10956.4   73.92 11566.7    74.7 11803.3   75.28 12147.9   85.84 13291.8   87.67
#Mann= 18 ,-1 , 0
     107     .05       0  4744.7     .05       0  4900.3     .04       0
  5296.2     .05       0  5567.5     .05       0  6150.1     .05       0
  6324.6     .12       0    7062     .12       0  7147.4      .1       0
  8723.4     .12       0  9089.9      .1       0  9600.2     .12       0
 10046.9      .1       0 10565.9     .12       0 10856.8     .05       0
 10956.4     .12       0 11566.7     .05       0 11803.3     .12       0
#Block Obstruct= 1 ,-1
     107  4702.2   95.03
Bank Sta=4900.3,5296.2
XS Rating Curve= 0 ,0
Exp/Cntr=0.3,0.1

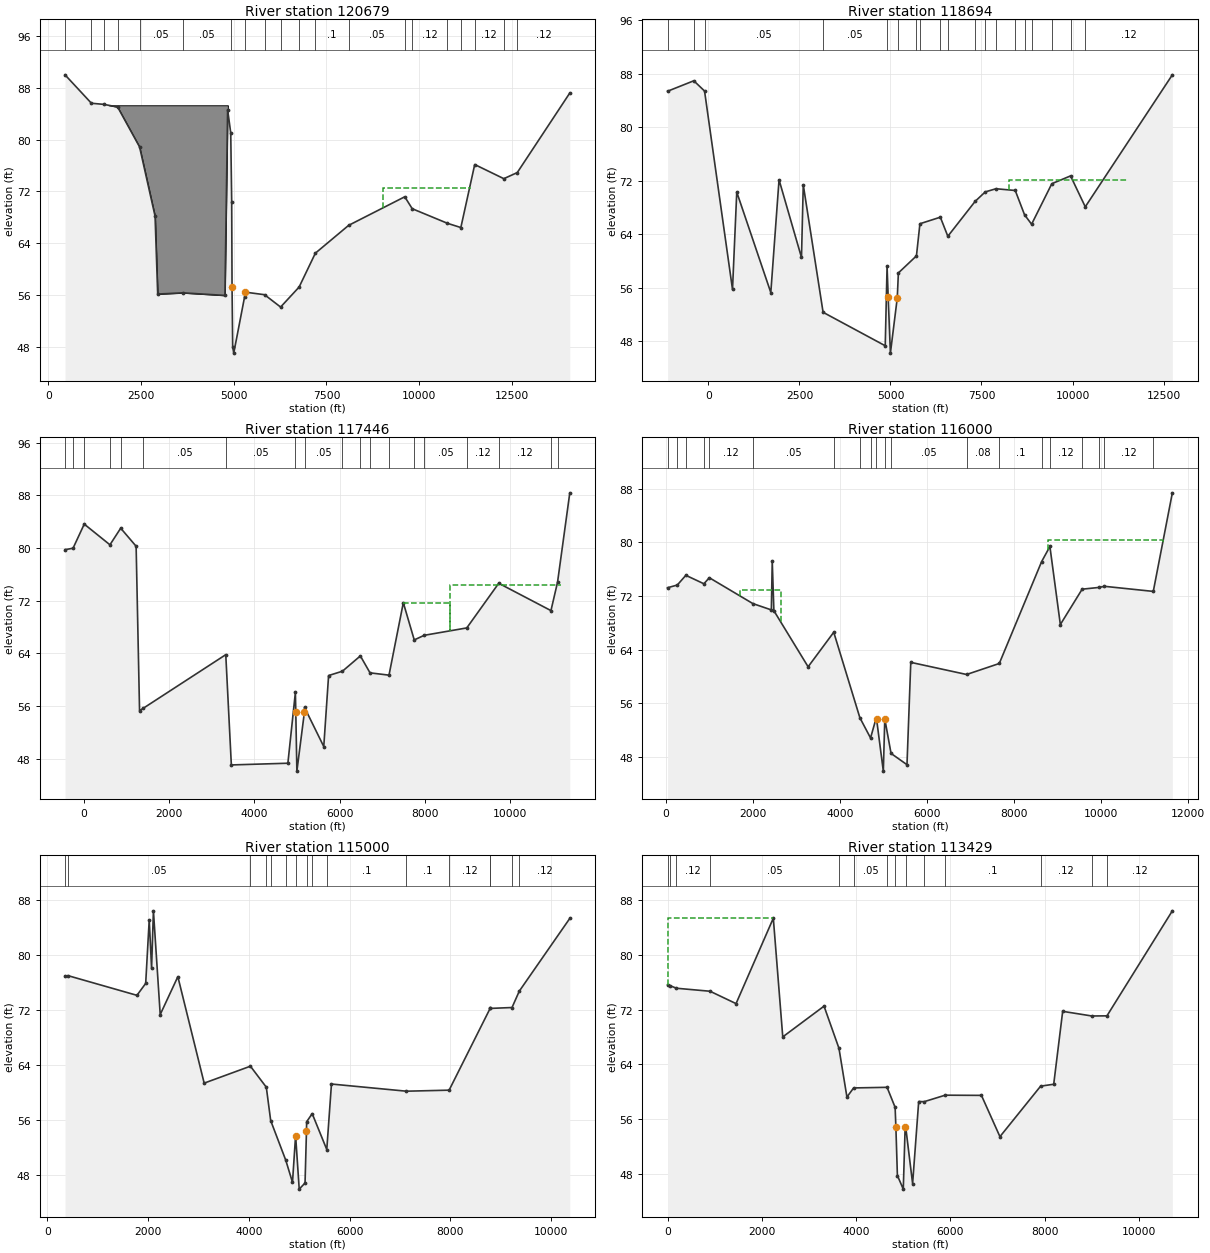
Type RM Length L Ch R = 1 ,120679  ,1985,1985,1985
BEGIN DESCRIPTION:
WFSJ Main 121.0
END DESCRIPTION:
XS GIS Cut Line= 3
      3898635.81     10028782.14      3893969.11     10027365.47
      3886261.79     10023241.01
#Sta/Elev= 30
   446.1   89.97  1157.9   85.59  1489.6   85.42  1864.5   85.02  2457.3   78.86
  2875.3    68.2  2946.3   56.19    3624   56.38  4760.1   55.98  4833.2   84.59
  4916.8   81.02  4942.6   70.41 4952.27   57.34  4969.1   48.11    4998   47.09
 5288.7955.70863  5303.5   56.49    5830   56.09  6262.2   54.19  6761.6   57.27
  7200.1   62.49  8098.2   66.78  9611.9   71.18  9813.3   69.34 10764.7   67.09
   11125   66.44 11499.5   76.15 12284.6   73.97 12647.7   74.91 14064.6   87.17
#Mann= 20 ,-1 , 0
   446.1     .12       0  1157.9     .05       0  1489.6      .1       0
  1864.5     .12       0  2457.3     .05       0    3624     .05       0
  4916.8     .03       0 5288.79     .05       0    5830      .1       0
  6262.2      .1       0  6761.6     .05       0  7200.1      .1       0
  8098.2     .05       0  9611.9     .05       0  9813.3     .12       0
 10764.7      .1       0   11125     .05       0 11499.5     .12       0
 12284.6      .1       0 12647.7     .12       0
#XS Ineff= 1 ,-1
    9013   11400    72.6
Permanent Ineff=
       F
#Block Obstruct= 1 ,-1
     900  4838.8   85.28
Bank Sta=4952.27,5303.5
XS Rating Curve= 0 ,0
Exp/Cntr=0.3,0.1

Type RM Length L Ch R = 1 ,118694  ,1248,1248,1248
BEGIN DESCRIPTION:
WFSJ Main 119.0
END DESCRIPTION:
XS GIS Cut Line= 4
      3899849.35     10026207.92      3896322.84       10026056.
      3893760.78      10025698.8      3886427.43     10023198.79
#Sta/Elev= 30
 -1122.2   85.38  -402.4   86.94  -106.8   85.41     661   55.77   777.8   70.31
  1712.9    55.3  1939.2   72.15  2555.5   60.54  2604.5   71.39  3149.1   52.35
    4856   47.35  4906.5   59.22 4936.36   54.71    4998   46.25  5186.454.49432
    5217   58.23  5713.2   60.78  5808.7   65.58  6369.6   66.56  6575.3   63.71
  7326.1   68.93    7604   70.34  7898.3   70.81  8426.9   70.55  8682.3   66.92
    8876   65.51  9431.4   71.56    9946   72.73 10350.3   68.11 12742.2   87.83
#Mann= 19 ,-1 , 0
 -1122.2     .05       0  -402.4     .12       0  -106.8     .05       0
  3149.1     .05       0  4906.5     .03       0    5217     .05       0
  5713.2      .1       0  5808.7      .1       0  6369.6      .1       0
  6575.3     .05       0  7326.1     .12       0    7604     .12       0
  7898.3     .12       0  8426.9     .05       0  8682.3      .1       0
    8876     .12       0  9431.4      .1       0    9946     .12       0
 10350.3     .12       0
#XS Ineff= 3 ,-1
     145  1939.2   72.15  1939.3  2604.5   71.39  8251.6   11500   72.05
Permanent Ineff=
       F       F       F
Bank Sta=4936.36,5186.4
XS Rating Curve= 0 ,0
Exp/Cntr=0.3,0.1

Type RM Length L Ch R = 1 ,117446  ,1446,1446,1446
BEGIN DESCRIPTION:
WFSJ Main 118.0
END DESCRIPTION:
XS GIS Cut Line= 3
      3899925.24     10025763.03      3895292.03     10025231.35
      3888946.22     10021869.59
#Sta/Elev= 30
  -442.6   79.76  -254.5   79.98     8.3   83.64   611.3    80.5   863.8   83.02
  1225.7   80.28  1306.2   55.31  1394.8   55.69  3329.4   63.82  3460.2   47.08
  4786.8   47.34  4962.8   58.09  4972.6   55.07    4998   46.14 5174.0455.05132
  5177.1   55.81    5629   49.87  5742.2   60.65  6067.4   61.31  6487.6   63.63
  6714.5   61.06  7159.7   60.71  7495.6   71.71  7752.1   66.06  7986.7   66.76
  8984.9   67.88  9734.7   74.66   10960   70.51   11115   74.83 11402.3   88.39
#Mann= 19 ,-1 , 0
  -442.6     .05       0  -254.5     .05       0     8.3     .12       0
   611.3      .1       0   863.8     .12       0  1394.8     .05       0
  3329.4     .05       0  4962.8     .03       0  5177.1     .05       0
  6067.4     .12       0  6487.6     .05       0  6714.5      .1       0
  7159.7     .05       0  7752.1     .12       0  7986.7     .05       0
  8984.9     .12       0  9734.7     .12       0   10960      .1       0
   11115     .12       0
#XS Ineff= 2 ,-1
  7495.6    8589   71.71  8589.2   11186   74.37
Permanent Ineff=
       F       F
Bank Sta=4972.6,5174.04
XS Rating Curve= 0 ,0
Exp/Cntr=0.3,0.1

Type RM Length L Ch R = 1 ,116000  ,1000,1000,1000
BEGIN DESCRIPTION:
WFSJ Main 116.0
END DESCRIPTION:
XS GIS Cut Line= 3
      3900066.32     10025272.58       3895348.1     10023756.89
      3889011.41     10021791.45
#Sta/Elev= 30
    44.3   73.22   267.3   73.62   463.4   75.07   877.9   73.81  1002.7   74.71
  2003.6   70.85  2426.9   69.91  2447.5   77.19  2484.9   69.79  3271.1   61.43
  3859.5   66.58  4459.6   53.83  4704.7   50.81  4832.2   53.75  4843.6    53.6
    4998   45.87  5031.5   53.66  5175.5   48.51  5541.2   46.83  5628.5   62.09
  6910.4   60.28  7660.5   61.92  8632.6   77.11  8822.8   79.37  9062.6   67.73
  9563.1      73  9960.2   73.27   10074   73.43 11196.6   72.67 11634.5   87.37
#Mann= 20 ,-1 , 0
    44.3     .05       0   267.3      .1       0   463.4     .12       0
   877.9      .1       0  1002.7     .12       0  2003.6     .05       0
  3859.5     .05       0  4459.6      .1       0  4704.7     .05       0
  4832.2     .04       0  5031.5     .05       0  5175.5     .05       0
  6910.4     .08       0  7660.5      .1       0  8632.6     .12       0
  8822.8     .12       0  9563.1     .12       0  9960.2     .05       0
   10074     .12       0 11196.6     .12       0
#XS Ineff= 2 ,-1
  8784.3   11411   80.35    1704  2650.7   72.83
Permanent Ineff=
       F       F
Bank Sta=4843.6,5031.5
XS Rating Curve= 0 ,0
Exp/Cntr=0.3,0.1

Type RM Length L Ch R = 1 ,115000  ,1571,1571,1571
BEGIN DESCRIPTION:
WFSJ Main 115.0
END DESCRIPTION:
XS GIS Cut Line= 3
      3900352.81     10024035.61      3895836.29      10022926.1
      3890715.69      10021310.9
#Sta/Elev= 30
   349.2    76.9   407.2   76.99  1776.5   74.13  1950.4   75.86  2020.6    85.1
  2067.3   78.07  2103.7    86.4  2238.7   71.34  2588.8   76.84  3111.3   61.38
  4029.2   63.84  4344.8   60.79  4431.7   55.94  4731.3   50.18  4864.5   46.98
  4926.3   53.77    4998   45.99  5113.7   46.88 5142.2954.47886  5145.2   55.77
  5255.7   56.95  5545.2   51.74    5638   61.25    7125   60.21  7973.7   60.36
  8787.6   72.23  8788.1   72.23  9222.3   72.36  9366.7   74.74 10369.3    85.3
#Mann= 16 ,-1 , 0
   349.2     .12       0   407.2     .05       0  4029.2     .12       0
  4344.8     .05       0  4431.7     .12       0  4731.3      .1       0
  4926.3     .05       0  5145.2      .1       0  5255.7     .12       0
  5545.2      .1       0    7125      .1       0  7973.7     .12       0
  8787.6      .1       0  8788.1     .12       0  9222.3      .1       0
  9366.7     .12       0
Bank Sta=4926.3,5142.29
XS Rating Curve= 0 ,0
Exp/Cntr=0.3,0.1

Type RM Length L Ch R = 1 ,113429  ,1429,1429,1429
BEGIN DESCRIPTION:
WFSJ Main 113.0
END DESCRIPTION:
XS GIS Cut Line= 3
      3901212.13     10023410.59      3896381.44     10021587.69
      3890907.43     10020587.63
#Sta/Elev= 30
   -11.2   75.65    48.6   75.48     177   75.12   891.8   74.68  1443.9   72.87
  2235.9   85.37  2436.6      68  3313.8    72.5  3631.2   66.33  3800.4    59.2
    3943   60.53  4653.5   60.62  4824.5   57.69 4840.91   54.77    4873   47.71
    4998   45.72  5038.1   54.88  5048.9   54.84  5196.3   46.53  5325.6   58.54
  5442.3   58.52  5888.9   59.47  6659.2   59.44  7052.2    53.4  7916.8   60.79
  8195.1   61.07  8385.7   71.74  9004.6   71.06  9326.8   71.08 10716.6   86.45
#Mann= 14 ,-1 , 0
   -11.2     .12       0    48.6     .05       0     177     .12       0
   891.8     .05       0  3631.2      .1       0    3943     .05       0
  4653.5     .07       0  4824.5     .05       0  5048.9     .07       0
  5442.3     .12       0  5888.9      .1       0  7916.8     .12       0
  9004.6      .1       0  9326.8     .12       0
#XS Ineff= 2 ,-1
    2300  3313.8    72.5   -11.2  2235.9   85.37
Permanent Ineff=
       F       F
Bank Sta=4840.91,5038.1
XS Rating Curve= 0 ,0
Exp/Cntr=0.3,0.1

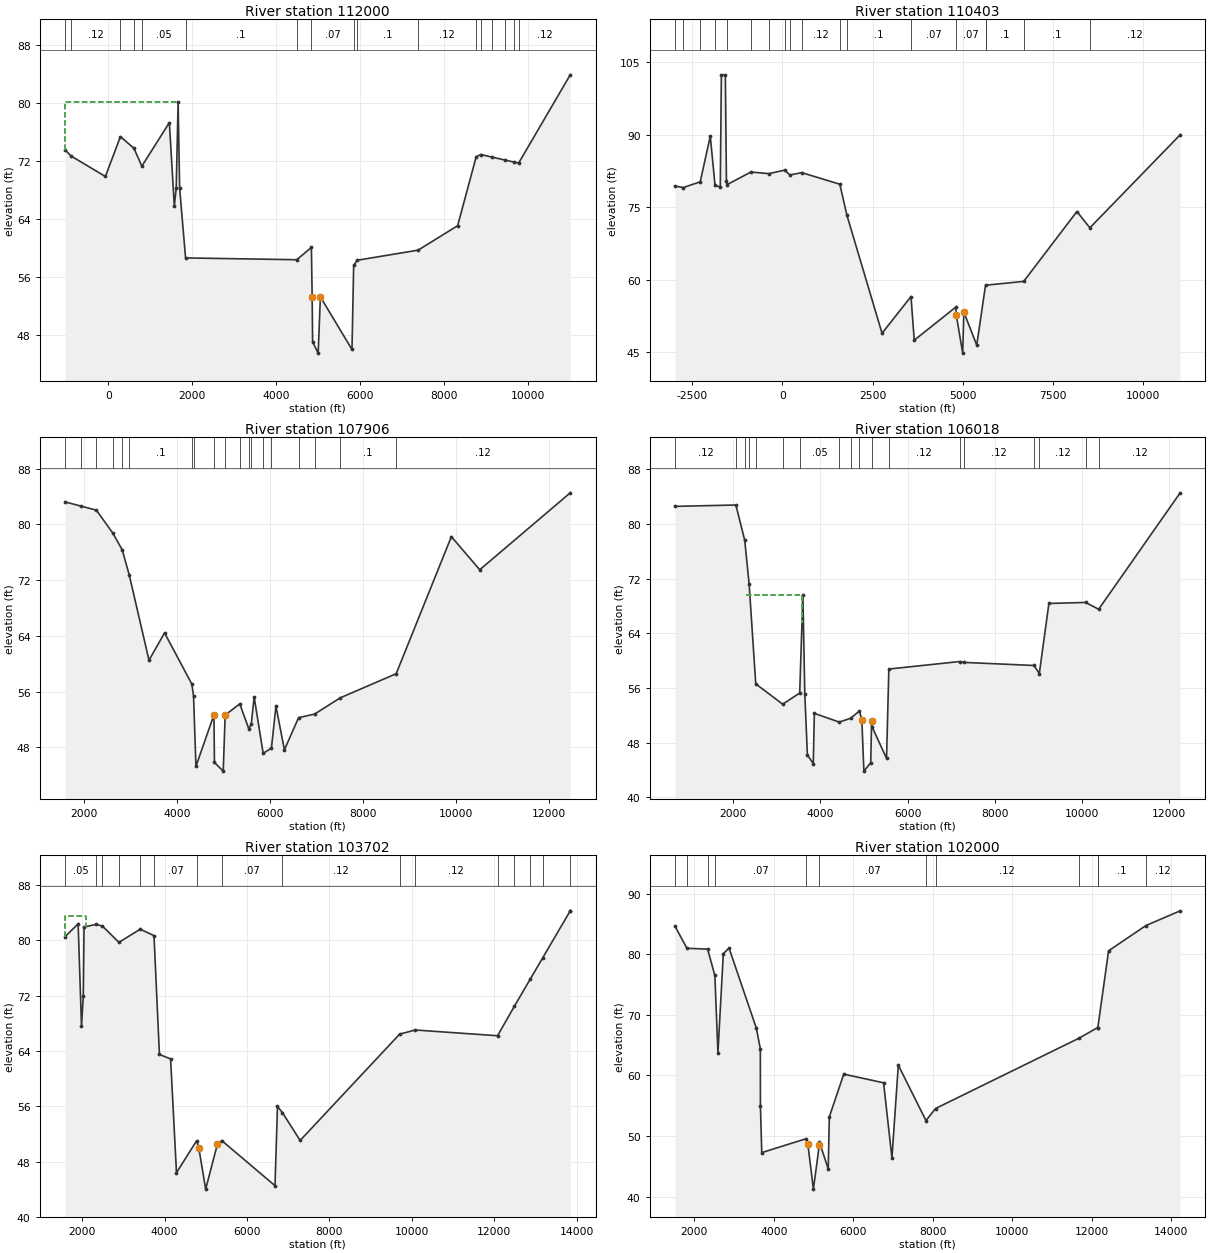
Type RM Length L Ch R = 1 ,112000  ,1597,1597,1597
BEGIN DESCRIPTION:
WFSJ Main 112.0
END DESCRIPTION:
XS GIS Cut Line= 3
      3902331.94     10022993.93      3896908.23     10020358.96
      3890927.82     10019865.92
#Sta/Elev= 30
 -1029.9   73.55    -891    72.7   -68.7   69.86   288.5   75.36   611.5   73.74
   798.2   71.28  1453.9   77.28  1572.3   65.78  1617.4   68.28  1662.5   80.12
  1698.5   68.26  1840.1   58.64  4487.1   58.39 4836.5560.07992 4854.45   53.26
  4865.4   47.06    4998   45.52  5050.6   53.27  5803.1   46.02  5843.2   57.63
  5929.6   58.32  7378.7   59.71  8318.9   63.08  8760.3   72.57  8870.3   72.89
  9139.7   72.53  9457.3   72.11  9649.6   71.86  9770.8    71.7 11000.7   83.87
#Mann= 17 ,-1 , 0
 -1029.9     .05       0    -891     .12       0   288.5     .05       0
   611.5     .12       0   798.2     .05       0  1840.1      .1       0
  4487.1     .12       0 4836.55     .07       0  5843.2      .1       0
  5929.6      .1       0  7378.7     .12       0  8760.3      .1       0
  8870.3     .12       0  9139.7      .1       0  9457.3     .12       0
  9649.6      .1       0  9770.8     .12       0
#XS Ineff= 1 ,-1
   -1029  1662.5   80.12
Permanent Ineff=
       F
Bank Sta=4854.45,5050.6
XS Rating Curve= 0 ,0
Exp/Cntr=0.3,0.1

Type RM Length L Ch R = 1 ,110403  ,2497,2497,2497
BEGIN DESCRIPTION:
WFSJ Main 111.0
END DESCRIPTION:
XS GIS Cut Line= 3
       3905040.3     10019400.19      3895105.39     10018644.98
      3891082.83     10018992.25
#Sta/Elev= 30
 -2976.8   79.37 -2746.8   79.05 -2276.2   80.24 -1997.7   89.69 -1866.2   79.51
 -1720.7   79.17 -1690.6  102.36 -1580.3  102.33 -1550.2   80.51 -1537.7   79.64
  -873.1   82.26  -376.1   81.93    61.9   82.65   211.6   81.65   535.4   82.14
  1592.2   79.74  1789.5   73.31  2762.2   48.93  3564.5   56.51  3654.7   47.49
    4808   54.34  4818.1   52.76    4998   44.82  5028.7   53.33    5387   46.46
  5630.4   58.86    6688   59.65  8162.9    74.1  8522.1   70.73 11024.3   89.96
#Mann= 18 ,-1 , 0
 -2976.8     .05       0 -2746.8    .075       0 -2276.2     .05       0
 -1866.2    .075       0 -1537.7     .05       0  -873.1      .1       0
  -376.1    .075       0    61.9      .1       0   211.6     .05       0
   535.4     .12       0  1592.2     .05       0  1789.5      .1       0
  3564.5     .07       0    4808     .07       0  5630.4      .1       0
  5630.4      .1       0    6688      .1       0  8522.1     .12       0
Bank Sta=4818.1,5028.7
XS Rating Curve= 0 ,0
Exp/Cntr=0.3,0.1

Type RM Length L Ch R = 1 ,107906  ,1888,1888,1888
BEGIN DESCRIPTION:
WFSJ Main 108.0
END DESCRIPTION:
XS GIS Cut Line= 3
      3901747.51     10017738.05      3897122.27     10016831.34
      3891013.31     10017456.12
#Sta/Elev= 30
  1599.7   83.24  1950.2   82.62  2272.9   82.05  2627.5   78.74    2827   76.37
  2977.9   72.78    3403   60.51  3737.7   64.44  4323.3    57.1  4360.4   55.38
  4411.9   45.29  4799.1   52.69  4809.3   45.84    4998    44.6  5039.7   52.65
  5353.6   54.25  5547.7   50.67  5599.9   51.33  5662.4   55.25  5856.1   47.15
  6033.7    47.9  6130.7   53.93  6312.7   47.66  6616.8   52.27  6962.4   52.79
  7512.4   55.12  8713.9   58.58  9899.4   78.25 10509.2    73.5 12453.8   84.54
#Mann= 19 ,-1 , 0
  1599.7      .1       0  1950.2    .075       0  2272.9     .05       0
  2627.5     .12       0    2827     .05       0  2977.9      .1       0
  4323.3      .1       0  4360.4     .05       0  4799.1     .03       0
  5039.7     .05       0  5353.6     .12       0  5547.7      .1       0
  5599.9     .12       0  5856.1      .1       0  6033.7     .12       0
  6616.8      .1       0  6962.4     .12       0  7512.4      .1       0
  8713.9     .12       0
Bank Sta=4799.1,5039.7
XS Rating Curve= 0 ,0
Exp/Cntr=0.3,0.1

Type RM Length L Ch R = 1 ,106018  ,2316,2316,2316
BEGIN DESCRIPTION:
WFSJ Main 106.0
END DESCRIPTION:
XS GIS Cut Line= 3
      3902037.53     10016598.04      3897174.35     10015268.84
      3890663.92      10015911.2
#Sta/Elev= 30
     666   82.57  2063.1   82.77  2265.5   77.62  2366.7   71.22  2518.8   56.61
  3136.3   53.64  3525.9   55.27  3599.5   69.55 3643.18   55.15  3702.9   46.21
  3837.9   44.95  3861.7    52.3  4432.7   51.02  4693.9   51.58  4896.2   52.65
  4951.251.31457    4998   43.85  5154.5   45.08  5175.2   51.22  5183.7   50.35
  5517.3   45.72  5570.3   58.78  7197.7   59.88  7297.1   59.75  8897.8    59.3
  9020.3   58.12    9240   68.37 10082.1   68.52 10380.5   67.52 12249.6   84.55
#Mann= 18 ,-1 , 0
     666     .12       0  2063.1     .05       0  2265.5      .1       0
  2366.7     .12       0  2518.8      .1       0  3136.3      .1       0
  3525.9     .05       0  4432.7      .1       0  4693.9     .07       0
  4896.2     .05       0  5183.7     .07       0  5570.3     .12       0
  7197.7      .1       0  7297.1     .12       0  8897.8      .1       0
  9020.3     .12       0 10082.1      .1       0 10380.5     .12       0
#XS Ineff= 1 ,-1
    2290  3578.7   69.63
Permanent Ineff=
       F
Bank Sta=4951.2,5175.2
XS Rating Curve= 0 ,0
Exp/Cntr=0.3,0.1

Type RM Length L Ch R = 1 ,103702  ,1702,1702,1702
BEGIN DESCRIPTION:
WFSJ Main 104.0
END DESCRIPTION:
XS GIS Cut Line= 3
       3902745.1      10015722.4      3898786.76     10014298.79
      3890733.03     10014133.16
#Sta/Elev= 30
  1585.1   80.54  1902.8   82.38  1984.3   67.61  2028.5      72  2045.7   81.92
  2334.8   82.31  2491.6   82.07  2892.7   79.71  3409.6   81.61  3744.1   80.68
  3875.7   63.49  4146.8   62.85  4289.7   46.39  4780.9   51.02  4834.1   49.89
    4998   44.01  5282.5   50.51    5389   51.03  6680.8   44.51  6740.8   55.97
  6860.3   55.09  7290.9   51.05  9705.6   66.43 10083.1   67.03 12082.5    66.2
 12488.5   70.44 12879.1   74.42 13179.4   77.48 13841.7   84.22 13847.1   84.27
#Mann= 16 ,-1 , 0
  1585.1     .05       0  2334.8      .1       0  2491.6     .05       0
  2892.7     .05       0  3409.6      .1       0  3744.1     .07       0
  4780.9     .05       0    5389     .07       0  6860.3     .12       0
  9705.6      .1       0 10083.1     .12       0 12082.5      .1       0
 12488.5     .12       0 12879.1      .1       0 13179.4     .12       0
 13841.7     .05       0
#XS Ineff= 1 ,-1
    1586  2101.9   83.45
Permanent Ineff=
       F
Bank Sta=4834.1,5282.5
XS Rating Curve= 0 ,0
Exp/Cntr=0.3,0.1

Type RM Length L Ch R = 1 ,102000  ,2000,2000,2000
BEGIN DESCRIPTION:
WFSJ Main 102.0
END DESCRIPTION:
XS GIS Cut Line= 4
      3903074.94     10015114.75      3900248.19     10013073.37
      3895529.73     10012752.25      3891061.95     10013291.74
#Sta/Elev= 30
  1513.2   84.66  1815.2      81  2335.2   80.87  2517.6   76.52  2595.1   63.75
  2730.8   80.13    2875   81.03    3562   67.81  3662.6    64.4 3664.55   54.96
  3698.2   47.26  4815.4   49.56  4858.7   48.64    4998   41.23  5148.148.58382
  5150.7   48.99  5371.2   44.57  5399.2   53.17  5762.1   60.22  6764.4   58.79
  6974.9   46.38  7135.3    61.7  7831.7   52.55    8072   54.54 11675.9   66.13
 12156.6   67.92   12158   67.92 12428.1   80.59 13368.5   84.76 14229.6   87.19
#Mann= 12 ,-1 , 0
  1513.2    .075       0  1815.2      .1       0  2335.2    .075       0
  2517.6     .07       0  4815.4     .05       0  5150.7     .07       0
  7831.7      .1       0    8072     .12       0 11675.9      .1       0
 12156.6     .12       0   12158      .1       0 13368.5     .12       0
#XS Ineff= 2 ,-1
  7135.3   11000    61.7    1565    2875   81.03
Permanent Ineff=
       F       F
Bank Sta=4858.7,5148.1
XS Rating Curve= 0 ,0
Exp/Cntr=0.3,0.1

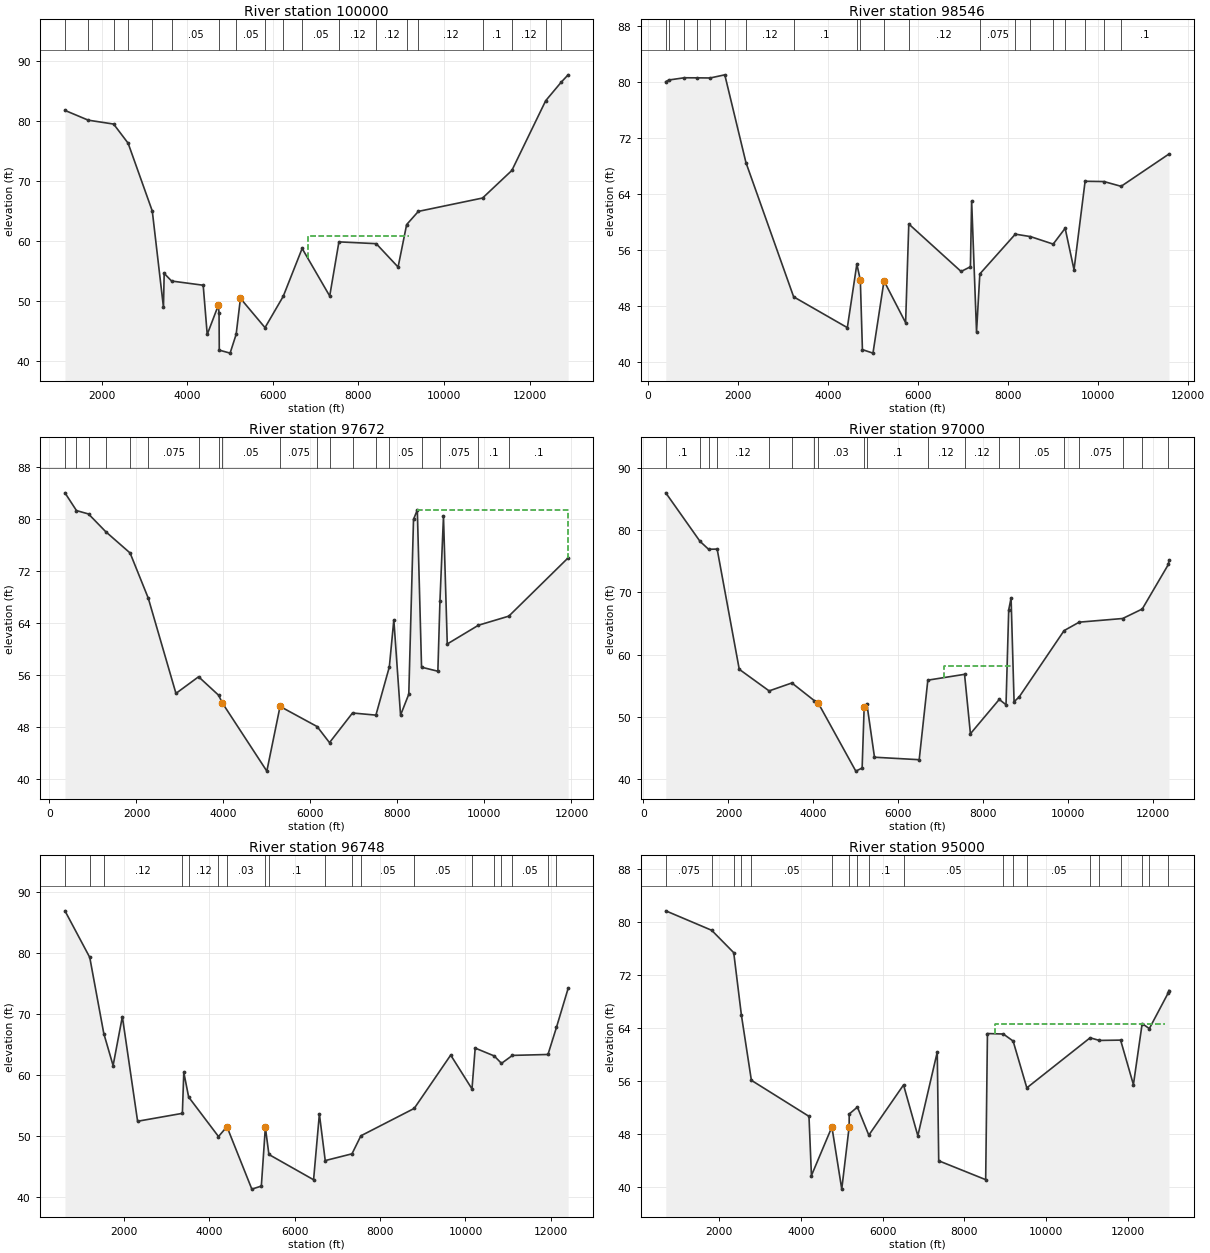
Type RM Length L Ch R = 1 ,100000  ,1454,1454,1454
BEGIN DESCRIPTION:
WFSJ Main 100.0
END DESCRIPTION:
XS GIS Cut Line= 3
      3902712.35     10014692.97      3900934.24     10011261.39
      3894831.62     10006239.11
#Sta/Elev= 30
  1135.1    81.7  1680.6   80.07  2273.5   79.42  2612.6   76.23  3177.7   64.92
  3439.3   48.87  3455.8   54.52  3629.8   53.25  4368.3   52.55  4462.5   44.34
 4722.82   49.22  4739.2   47.84  4744.6   41.73  4997.6   41.23  5139.3   44.37
  5239.7   50.36  5814.1   45.48  6239.6   50.69  6682.4   58.68  7327.3   50.75
  7542.8   59.78    8415   59.48  8926.4   55.58  9126.6   62.66  9400.2   64.86
 10902.4   67.09 11587.7   71.69 12378.2   83.31 12744.6   86.43 12903.5   87.63
#Mann= 19 ,-1 , 0
  1135.1      .1       0  1680.6     .05       0  2273.5      .1       0
  2612.6     .05       0  3177.7     .12       0  3629.8     .05       0
  4739.2     .05       0  5139.3     .05       0  5814.1      .1       0
  6239.6     .12       0  6682.4     .05       0  7542.8     .12       0
    8415     .12       0  9126.6     .05       0  9400.2     .12       0
 10902.4      .1       0 11587.7     .12       0 12378.2     .05       0
 12744.6     .12       0
#XS Ineff= 1 ,-1
  6808.7    9170    60.7
Permanent Ineff=
       F
Bank Sta=4722.82,5239.7
XS Rating Curve= 0 ,0
Exp/Cntr=0.3,0.1

Type RM Length L Ch R = 1 ,98546   ,874,874,874
BEGIN DESCRIPTION:
WFSJ Main 99.0
END DESCRIPTION:
XS GIS Cut Line= 3
      3902781.79     10014564.45      3901670.69     10010120.06
      3899740.38     10003815.32
#Sta/Elev= 30
   395.7      80   462.5   80.23   808.8   80.55  1085.7   80.54  1381.7   80.52
  1706.7   80.97  2176.1   68.45  3235.7   49.27  4428.2   44.87  4639.5   53.94
  4716.8   51.66  4763.2   41.73  4997.6   41.23  5242.6   51.54  5722.3   45.58
    5793   59.67  6954.2   52.89  7161.6   53.56  7188.8   62.96  7297.5   44.24
  7370.6   52.54  8158.8   58.22  8495.5   57.87  8999.6    56.8  9265.3   59.06
  9462.4   53.14  9708.7   65.77 10127.3   65.73 10508.5   65.05 11570.5   69.66
#Mann= 20 ,-1 , 0
   395.7    .075       0   462.5      .1       0   808.8     .05       0
  1085.7    .075       0  1381.7      .1       0  1706.7    .075       0
  2176.1     .12       0  3235.7      .1       0  4639.5     .07       0
  4716.8     .05       0  5242.6     .07       0    5793     .12       0
  7370.6    .075       0  8158.8      .1       0  8495.5    .075       0
  8999.6     .05       0  9265.3    .075       0  9708.7    .075       0
 10127.3    .075       0 10508.5      .1       0
#XS Ineff= 2 ,-1
    5793    7188   59.67  7188.8    9740   62.96
Permanent Ineff=
       F       F
Bank Sta=4716.8,5242.6
XS Rating Curve= 0 ,0
Exp/Cntr=0.3,0.1

Type RM Length L Ch R = 1 ,97672   ,672,672,672
BEGIN DESCRIPTION:
WFSJ Main 98.0
END DESCRIPTION:
XS GIS Cut Line= 3
      3903685.88     10014512.43      3902522.68     10009998.53
      3900213.66     10003488.13
#Sta/Elev= 30
   355.8   84.02   620.7   81.29   897.3   80.77  1294.4   78.04  1853.4   74.77
  2271.8   67.82  2907.9   53.18  3428.5   55.74  3888.9    52.9  3975.6    51.7
  4997.6   41.23  5301.7   51.18  6154.3   48.08  6438.3   45.61  6967.4   50.17
  7505.2   49.84  7813.9   57.25  7917.5    64.5  8071.8   49.84  8261.2   53.06
    8370   79.94  8457.3   81.38  8554.6   57.21  8929.7   56.59  8977.8   67.38
  9058.8    80.4  9146.1   60.78    9862   63.66   10561   65.06 11924.9   74.02
#Mann= 19 ,-1 , 0
   355.8      .1       0   620.7    .075       0   897.3      .1       0
  1294.4      .1       0  1853.4      .1       0  2271.8    .075       0
  3428.5      .1       0  3888.9     .07       0  3975.6     .05       0
  5301.7    .075       0  6154.3     .05       0  6438.3     .05       0
  6967.4      .1       0  7505.2      .1       0  7813.9     .05       0
  8554.6     .05       0  8977.8    .075       0    9862      .1       0
   10561      .1       0
#XS Ineff= 2 ,-1
  7917.5    8450    64.5  8457.3   11925   81.38
Permanent Ineff=
       F       F
Bank Sta=3975.6,5301.7
XS Rating Curve= 0 ,0
Exp/Cntr=0.3,0.1

Type RM Length L Ch R = 1 ,97000   ,252,252,252
BEGIN DESCRIPTION:
WFSJ Main 97.0
END DESCRIPTION:
XS GIS Cut Line= 3
      3904045.68     10014439.49      3903198.75     10010045.16
      3900885.96     10003050.61
#Sta/Elev= 30
   524.8   86.05  1330.5   78.24  1532.4   76.96  1734.3   76.99  2254.5   57.63
  2957.5   54.15  3492.7   55.43  4020.9   52.58 4116.88   52.15  4997.6   41.23
  5146.4   41.73  5193.9   51.48  5257.1   52.09  5437.1   43.47  6489.4   43.07
  6692.7   55.88  7556.7   56.82  7694.9   47.25  8373.6   52.78  8532.7   51.92
  8595.9   67.19  8651.9   69.11  8722.3    52.4  8845.5   53.21  9899.3   63.86
 10254.7   65.22 11278.1   65.81   11739   67.34 12356.5   74.55   12367   75.25
#Mann= 19 ,-1 , 0
   524.8      .1       0  1330.5    .075       0  1532.4     .05       0
  1734.3     .12       0  2957.5      .1       0  3492.7     .12       0
  4020.9     .05       0 4116.88     .03       0  5193.9     .05       0
  5257.1      .1       0  6692.7     .12       0  7556.7     .12       0
  8373.6     .05       0  8845.5     .05       0  9899.3      .1       0
 10254.7    .075       0 11278.1      .1       0   11739      .1       0
 12356.5    .075       0
#XS Ineff= 2 ,-1
  8651.9   12205   69.11  7079.2    8650   58.23
Permanent Ineff=
       F       F
Bank Sta=4116.88,5193.9
XS Rating Curve= 0 ,0
Exp/Cntr=0.3,0.1

Type RM Length L Ch R = 1 ,96748   ,1748,1748,1748
BEGIN DESCRIPTION:
WFSJ Main 96.0
END DESCRIPTION:
XS GIS Cut Line= 3
      3904337.35      10014328.4      3903504.02     10010217.28
      3901288.73      10002960.3
#Sta/Elev= 30
   621.5   86.95  1202.3    79.3  1531.2   66.79  1748.9   61.53  1965.6   69.57
  2322.7   52.38  3371.1   53.68  3404.3   60.41  3517.9   56.36  4216.8   49.87
  4414.4   51.49  4997.6   41.23    5220   41.73  5314.1   51.37  5397.5   46.92
  6443.3   42.77  6579.2   53.56    6716   45.92  7342.7   47.03  7550.9   49.99
  8799.8   54.49    9654   63.25 10152.7   57.69 10227.4    64.4 10673.1   63.11
 10843.3   61.89 11099.9    63.2 11931.8   63.35 12130.2    67.8 12403.8   74.21
#Mann= 19 ,-1 , 0
   621.5     .12       0  1202.3     .05       0  1531.2     .12       0
  3371.1     .05       0  3517.9     .12       0  4216.8     .05       0
  4414.4     .03       0  5314.1     .05       0  5397.5      .1       0
    6716     .12       0  7342.7     .12       0  7550.9     .05       0
  8799.8     .05       0 10152.7     .05       0 10673.1     .05       0
 10843.3      .1       0 11099.9     .05       0 11931.8     .05       0
 12130.2    .075       0
#XS Ineff= 3 ,-1
    1430  1965.6   69.57    1966  3404.3   60.41    9654   12000   63.25
Permanent Ineff=
       F       F       F
Bank Sta=4414.4,5314.1
XS Rating Curve= 0 ,0
Exp/Cntr=0.3,0.1

Type RM Length L Ch R = 1 ,95000   ,2000,2000,2000
BEGIN DESCRIPTION:
WFSJ Main 95.0
END DESCRIPTION:
XS GIS Cut Line= 3
      3905455.41     10014380.52      3905185.77     10010077.86
      3902434.59      10002557.6
#Sta/Elev= 30
   688.9    81.7  1813.6   78.76    2353   75.38  2540.4   65.97    2785   56.11
  4195.2   50.67  4255.3   41.73  4756.3   49.07  4997.6   39.68 5178.41   49.07
    5180   51.02  5380.7   52.07    5660   47.83  6509.9   55.41    6860   47.74
  7335.4   60.37  7371.3   43.96  8521.1   41.11  8564.3   63.17  8953.3    63.1
  9192.7   62.04  9528.6   54.97 11078.1   62.53 11303.9   62.13 11824.1   62.18
 12137.9   55.46   12352   64.67 12527.6   63.92 12990.4   69.31 13007.7   69.67
#Mann= 19 ,-1 , 0
   688.9    .075       0  1813.6     .05       0    2353     .05       0
  2540.4     .12       0    2785     .05       0  4756.3     .03       0
    5180     .05       0  5380.7     .12       0    5660      .1       0
  6509.9     .05       0  8953.3     .12       0  9192.7     .05       0
  9528.6     .05       0 11078.1     .05       0 11303.9     .05       0
 11824.1     .05       0   12352    .075       0 12527.6     .05       0
 12990.4      .1       0
#XS Ineff= 2 ,-1
  7335.4    8599   60.37  8744.7   12900   64.59
Permanent Ineff=
       F       F
Bank Sta=4756.3,5178.41
XS Rating Curve= 0 ,0
Exp/Cntr=0.3,0.1