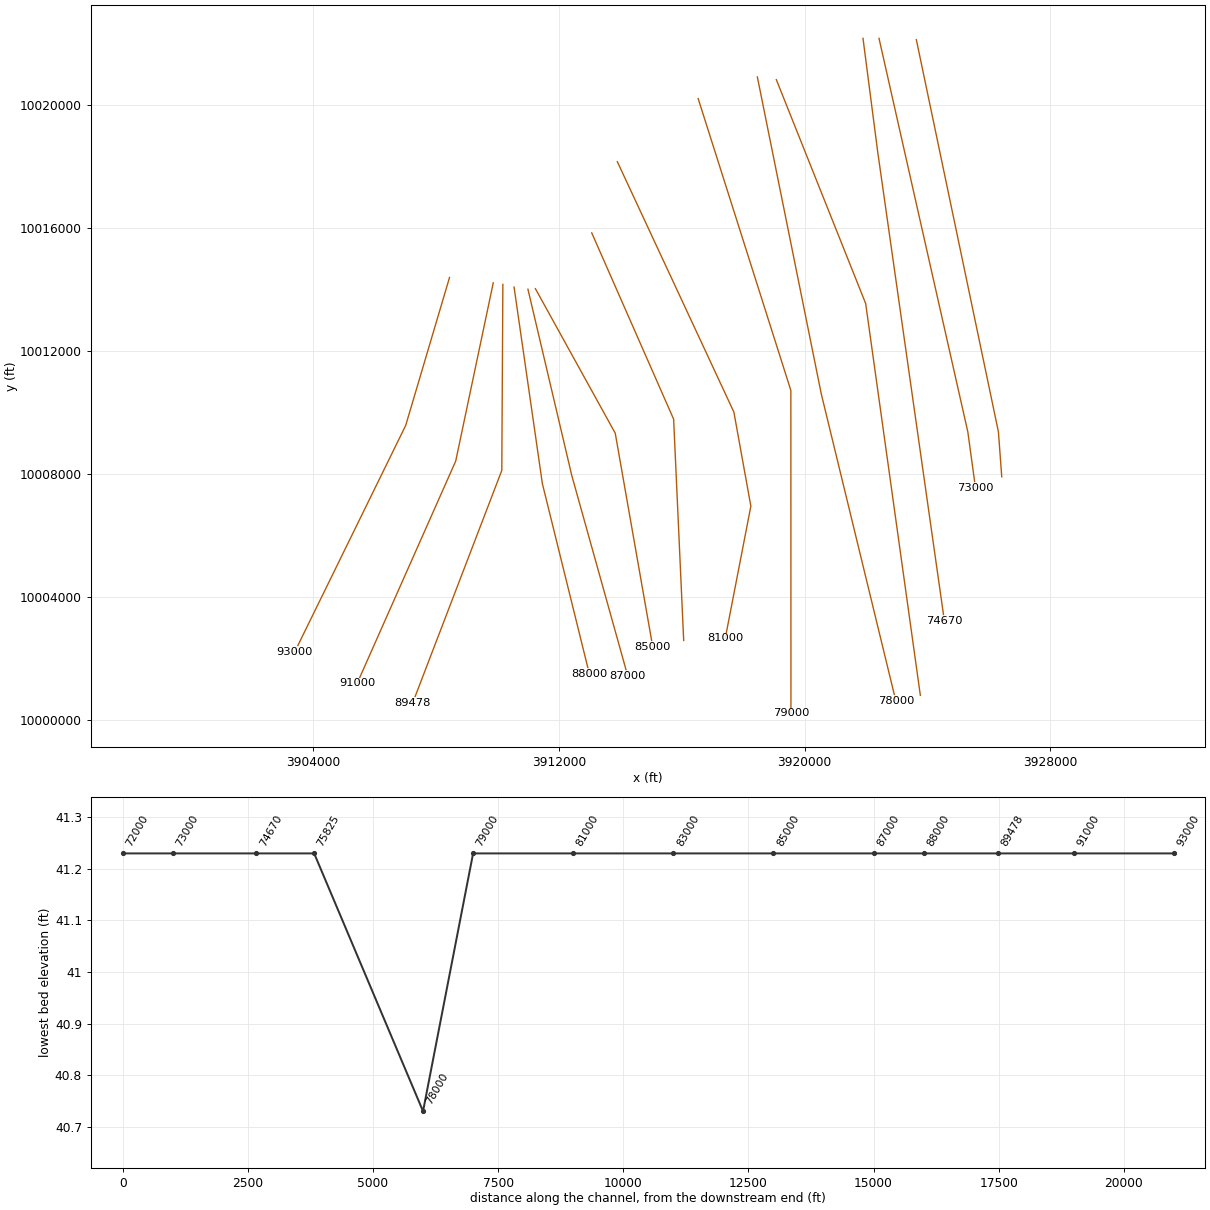
HEC-RAS study WFSJ Main.prj: WFSJ Main Base Level Engineering

--- WFSJ Main.g02 (geometry) --- (continued)

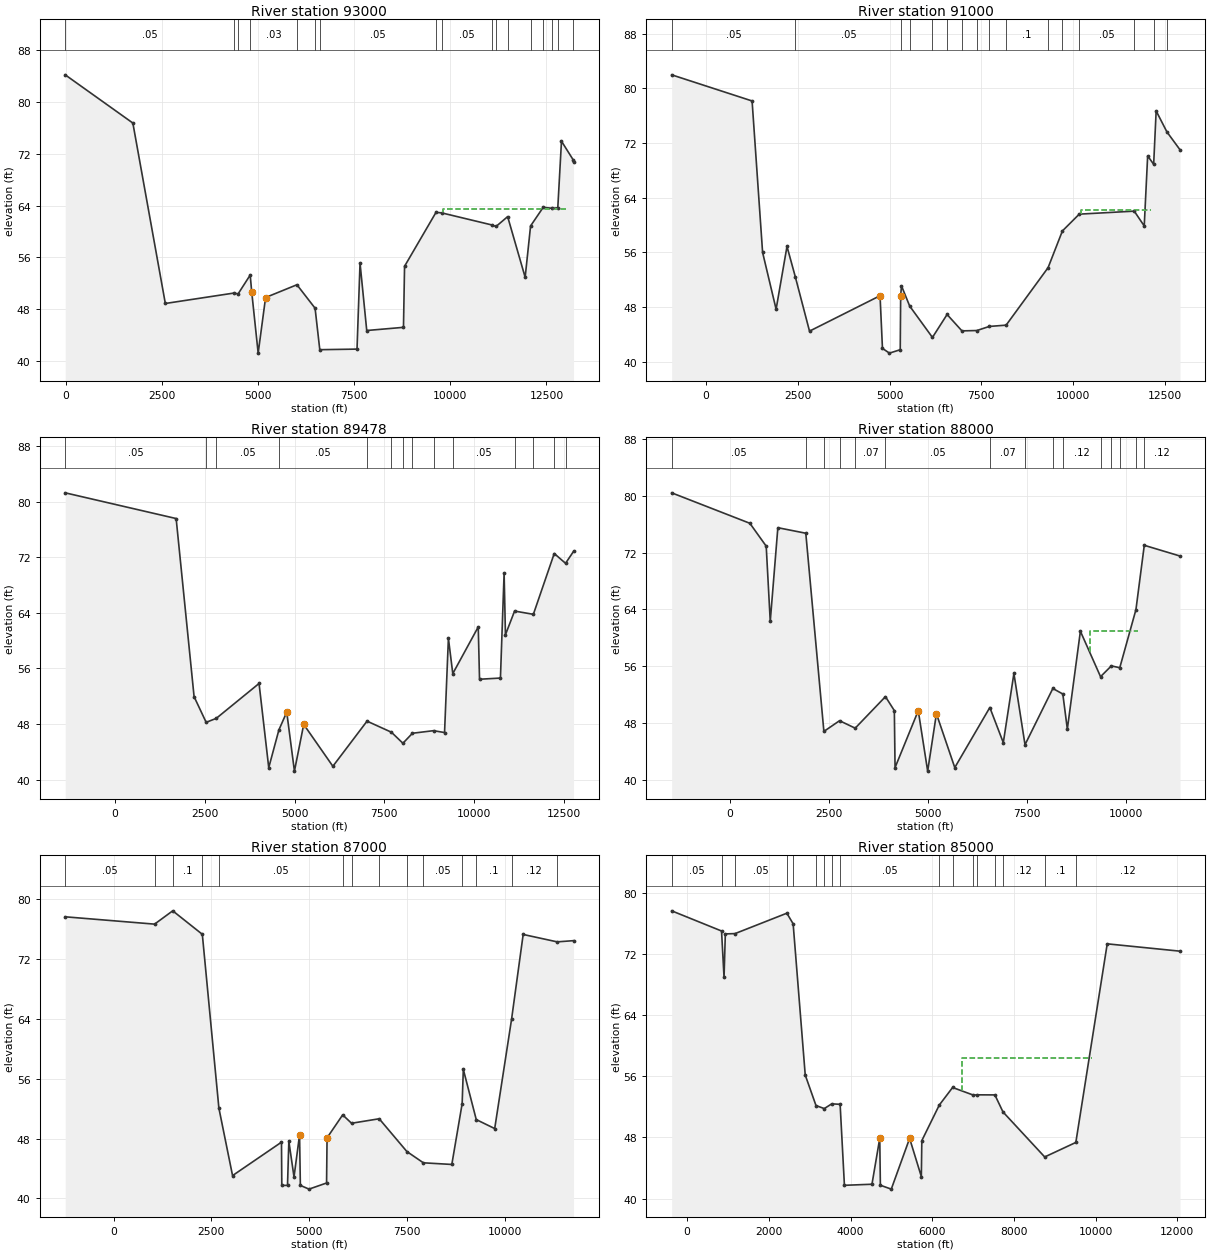
Type RM Length L Ch R = 1 ,93000   ,2000,2000,2000
BEGIN DESCRIPTION:
WFSJ Main 93.0
END DESCRIPTION:
XS GIS Cut Line= 3
      3908441.53     10014397.86       3907015.5     10009579.87
      3903406.78      10002210.3
#Sta/Elev= 30
   -24.6   84.17  1736.1   76.73  2581.3   48.89    4357   50.49  4476.5   50.38
  4790.2   53.28  4829.9   50.66  4997.6   41.23  5190.7   49.81  6006.4   51.78
  6478.9   48.16  6601.4   41.76  7570.3   41.85    7649   55.12  7823.4   44.72
  8779.7   45.21  8807.8   54.63  9626.3   62.95  9774.2   62.87 11077.4   61.01
   11189   60.77 11490.8   62.29 11946.7   52.93 12087.6   60.85 12416.9   63.73
 12655.8   63.57 12796.1   63.66 12891.9   73.93 13191.6    71.1 13205.7   70.72
#Mann= 17 ,-1 , 0
   -24.6     .05       0    4357    .075       0  4476.5     .05       0
  4790.2     .03       0  6006.4     .05       0  6478.9      .1       0
  6601.4     .05       0  9626.3     .12       0  9774.2     .05       0
 11077.4    .075       0   11189    .075       0 11490.8     .05       0
 12087.6    .075       0 12416.9      .1       0 12655.8      .1       0
 12796.1    .075       0 13191.6      .1       0
#XS Ineff= 1 ,-1
  9803.5   13000   63.48
Permanent Ineff=
       F
Bank Sta=4829.9,5190.7
XS Rating Curve= 0 ,0
Exp/Cntr=0.3,0.1

Type RM Length L Ch R = 1 ,91000   ,1522,1522,1522
BEGIN DESCRIPTION:
WFSJ Main 91.0
END DESCRIPTION:
XS GIS Cut Line= 3
      3909865.13     10014224.23      3908643.07     10008418.65
      3905438.07     10001186.07
#Sta/Elev= 30
  -932.8      82  1257.3   78.17  1543.5   55.98  1911.3   47.66  2207.7   56.86
  2432.8   52.44  2821.2   44.45    4742   49.64  4807.7   41.92  4997.6   41.23
    5292   41.73  5303.6   49.66  5326.2   51.08  5549.4   48.12    6169   43.53
  6567.8   46.89  6972.2   44.49  7378.8   44.54  7717.3   45.14  8175.6   45.33
  9318.3   53.75  9708.5   59.13 10166.9   61.59 11664.9   62.03 11936.9   59.86
 12030.1   70.13 12193.7   68.89 12261.4   76.71 12554.3   73.64 12910.9   71.02
#Mann= 16 ,-1 , 0
  -932.8     .05       0  2432.8     .05       0  5326.2      .1       0
  5549.4      .1       0    6169     .05       0  6567.8     .12       0
  6972.2     .12       0  7378.8      .1       0  7717.3     .12       0
  8175.6      .1       0  9318.3     .12       0  9708.5     .05       0
 10166.9     .05       0 11664.9     .05       0 12193.7     .05       0
 12554.3      .1       0
#XS Ineff= 1 ,-1
 10225.7   12115   62.23
Permanent Ineff=
       F
Bank Sta=4742,5303.6
XS Rating Curve= 0 ,0
Exp/Cntr=0.3,0.1

Type RM Length L Ch R = 1 ,89478   ,1478,1478,1478
BEGIN DESCRIPTION:
WFSJ Main 90.0
END DESCRIPTION:
XS GIS Cut Line= 3
      3910177.63     10014172.16      3910142.91     10008113.11
      3907244.05     10000544.84
#Sta/Elev= 30
 -1389.4   81.27  1701.7   77.57  2201.7   51.94  2537.9   48.25  2819.4   48.82
  4011.8   53.84  4281.8   41.73  4564.8   47.16  4783.1   49.72  4997.6   41.23
  5256.3   47.95  6068.6   41.93  7020.4   48.42  7699.2   46.83    8020   45.24
  8286.4   46.68  8873.2   47.05  9180.2   46.78  9287.8   60.34  9409.8   55.26
 10119.4   61.98 10154.8   54.45 10737.5   54.62   10840   69.73   10877   60.85
 11131.5   64.26 11654.9   63.79 12236.6   72.54 12551.5   71.13 12774.2   72.84
#Mann= 14 ,-1 , 0
 -1389.4     .05       0  2537.9      .1       0  2819.4     .05       0
  4564.8     .05       0  7020.4     .12       0  7699.2     .12       0
    8020     .05       0  8286.4      .1       0  8873.2     .05       0
  9409.8     .05       0 11131.5     .12       0 11654.9     .12       0
 12236.6    .075       0 12551.5     .05       0
#XS Ineff= 1 ,-1
 10119.4   10805   61.98
Permanent Ineff=
       F
Bank Sta=4783.1,5256.3
XS Rating Curve= 0 ,0
Exp/Cntr=0.3,0.1

Type RM Length L Ch R = 1 ,88000   ,1000,1000,1000
BEGIN DESCRIPTION:
WFSJ Main 88.0
END DESCRIPTION:
XS GIS Cut Line= 3
      3910542.21     10014085.38      3911463.47     10007683.32
      3912990.12     10001498.56
#Sta/Elev= 30
   -1468   80.42   506.9   76.13   919.6   72.91  1021.7   62.32  1213.6   75.51
  1919.4   74.73  2376.3   46.82  2771.8   48.33  3167.2   47.28  3931.4   51.72
  4155.9   49.75  4173.8   41.73  4759.8   49.74  4997.6   41.23  5218.6   49.31
  5682.1   41.73  6567.4   50.19  6907.8   45.24  7175.6   54.98  7456.1   44.95
  8158.9   52.87  8410.7   52.09    8525   47.15  8854.6   60.93  9363.8   54.53
  9636.9   56.05  9849.4   55.79 10257.6   63.97 10468.3   73.03 11370.4   71.52
#Mann= 15 ,-1 , 0
   -1468     .05       0  1919.4     .05       0  2376.3     .05       0
  2771.8     .05       0  3167.2     .07       0  3931.4     .05       0
  6567.4     .07       0  7456.1     .05       0  8158.9     .05       0
  8410.7     .12       0  9363.8      .1       0  9636.9     .05       0
  9849.4      .1       0 10257.6     .05       0 10468.3     .12       0
#XS Ineff= 1 ,-1
  9091.7   10300   60.96
Permanent Ineff=
       F
Bank Sta=4759.8,5218.6
XS Rating Curve= 0 ,0
Exp/Cntr=0.3,0.1

Type RM Length L Ch R = 1 ,87000   ,2000,2000,2000
BEGIN DESCRIPTION:
WFSJ Main 87.0
END DESCRIPTION:
XS GIS Cut Line= 3
      3910993.61     10014015.85      3912421.94     10007943.48
      3914240.14     10001429.05
#Sta/Elev= 30
 -1238.1   77.65  1047.7   76.67  1511.9   78.45  2268.8   75.31  2692.7   52.06
  3042.1   43.04  4293.6   47.51    4302   41.73  4447.7   41.73  4481.8   47.64
  4614.1   42.86  4755.9   48.49  4776.5   41.73  4997.6   41.23  5446.8   42.05
  5459.3   48.09    5859   51.16  6085.4   50.04  6792.9   50.64  7500.5   46.26
  7922.7   44.75  8650.3   44.53  8914.6   52.66  8944.5   57.24  9275.4   50.53
  9747.2   49.33 10178.3   63.94 10475.3   75.29   11344    74.3 11763.4   74.46
#Mann= 14 ,-1 , 0
 -1238.1     .05       0  1047.7     .12       0  1511.9      .1       0
  2268.8     .12       0  2692.7     .05       0    5859     .12       0
  6085.4     .12       0  6792.9     .12       0  7500.5     .12       0
  7922.7     .05       0  8914.6     .12       0  9275.4      .1       0
 10178.3     .12       0   11344     .05       0
#XS Ineff= 1 ,-1
  8944.5   10100   57.24
Permanent Ineff=
       F
Bank Sta=4755.9,5459.3
XS Rating Curve= 0 ,0
Exp/Cntr=0.3,0.1

Type RM Length L Ch R = 1 ,85000   ,2000,2000,2000
BEGIN DESCRIPTION:
WFSJ Main 85.0
END DESCRIPTION:
XS GIS Cut Line= 3
      3911236.67     10014033.23      3913835.59     10009325.23
      3915056.11     10002366.55
#Sta/Elev= 30
  -377.7   77.65     843   75.01   904.1   68.93   935.7   74.63  1173.3   74.67
  2441.9   77.34  2595.5   75.95  2891.6   56.16  3154.8   52.17  3357.4   51.77
  3540.4   52.39 3745.45   52.33  3850.8   41.73    4525   41.87 4715.57   47.88
  4730.8   41.74  4997.6   41.23  5446.6   47.87  5733.4   42.87  5745.4   47.58
 6172.73   52.23    6499   54.53  7009.4   53.53  7094.8   53.57  7533.9   53.56
  7732.2   51.33  8753.1   45.44  9515.2   47.34 10283.6   73.33 12064.9   72.37
#Mann= 17 ,-1 , 0
  -377.7     .05       0     843     .12       0  1173.3     .05       0
  2441.9    .075       0  2595.5     .05       0  3154.8     .07       0
  3357.4     .05       0  3540.4     .05       0 3745.45     .05       0
 6172.73     .07       0    6499     .05       0  7009.4     .12       0
  7094.8     .05       0  7533.9     .05       0  7732.2     .12       0
  8753.1      .1       0  9515.2     .12       0
#XS Ineff= 1 ,-1
  6740.3    9915   58.39
Permanent Ineff=
       F
Bank Sta=4715.57,5446.6
XS Rating Curve= 0 ,0
Exp/Cntr=0.3,0.1

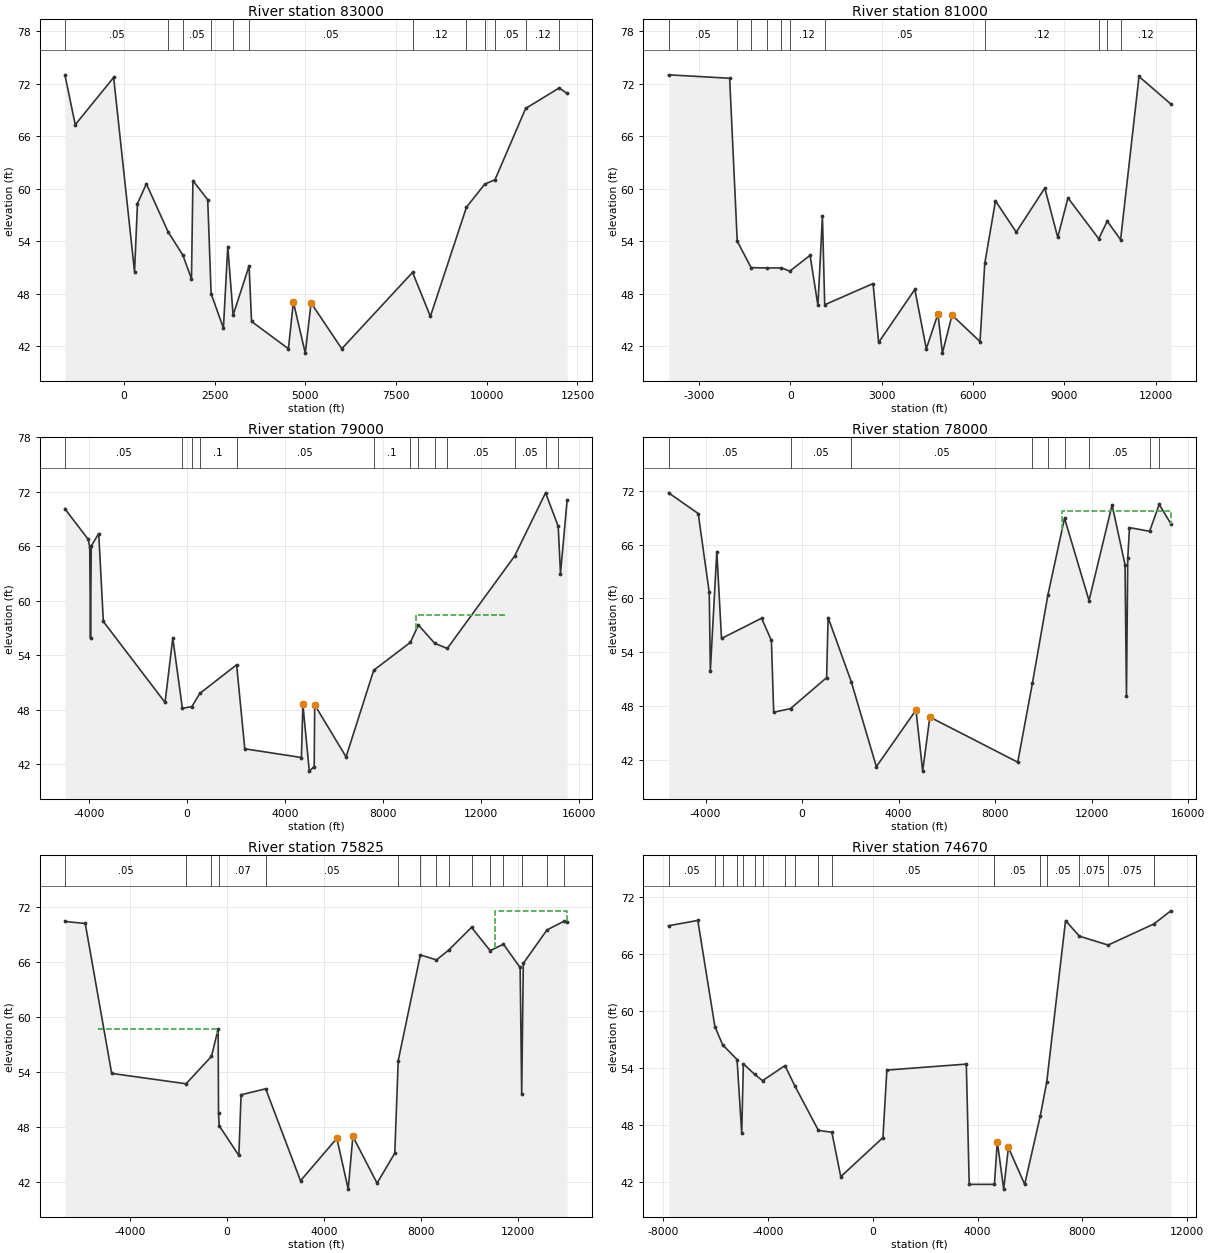
Type RM Length L Ch R = 1 ,83000   ,2000,2000,2000
BEGIN DESCRIPTION:
WFSJ Main 83.0
END DESCRIPTION:
XS GIS Cut Line= 3
        3913070.     10015851.52      3915735.68     10009783.64
      3916063.02     10002575.47
#Sta/Elev= 30
 -1627.6   73.03 -1342.3   67.33  -283.7   72.73   291.9   50.52   372.8   58.32
   617.3   60.57  1219.5   55.07    1625   52.42  1861.4   49.71  1900.8   60.94
  2309.1   58.76  2402.6   48.02  2741.9   44.09    2862   53.41  3009.3   45.57
  3448.9   51.19  3517.4   44.85  4533.1   41.73  4669.7   47.07  4997.6   41.23
  5157.9   46.97  6003.6   41.73  7955.6   50.46  8446.1   45.42  9440.9    57.9
  9942.6   60.53 10227.5   61.05 11072.5   69.19 11997.3   71.53 12215.6    70.9
#Mann= 12 ,-1 , 0
 -1627.6     .05       0  1219.5     .05       0    1625     .05       0
  2402.6     .12       0  3009.3      .1       0  3448.9     .05       0
  7955.6     .12       0  9440.9     .05       0  9942.6      .1       0
 10227.5     .05       0 11072.5     .12       0 11997.3     .05       0
#XS Ineff= 1 ,-1
    -130  1900.8   60.94
Permanent Ineff=
       F
Bank Sta=4669.7,5157.9
XS Rating Curve= 0 ,0
Exp/Cntr=0.3,0.1

Type RM Length L Ch R = 1 ,81000   ,2000,2000,2000
BEGIN DESCRIPTION:
WFSJ Main 81.0
END DESCRIPTION:
XS GIS Cut Line= 4
      3913903.34      10018169.2      3917696.76     10010014.44
      3918249.39     10006949.92      3917416.23     10002645.25
#Sta/Elev= 30
 -3993.9      73 -1988.7   72.61 -1739.9   54.01 -1284.4   50.99  -763.9   50.95
    -288   50.96   -15.3   50.59   652.4   52.39   909.6   46.68  1057.9   56.85
  1132.5   46.75  2720.7   49.17  2903.5   42.45  4091.8    48.5    4469   41.73
  4851.6   45.71  4997.6   41.23  5314.7   45.57  6232.9   42.55  6388.6   51.47
    6741   58.61  7421.8   55.04  8360.6   60.08    8785   54.45  9121.1   58.95
 10131.4   54.29 10410.5   56.29 10849.5   54.18 11453.6   72.81 12498.5   69.67
#Mann= 11 ,-1 , 0
 -3993.9     .05       0 -1739.9      .1       0 -1284.4     .12       0
  -763.9     .12       0    -288      .1       0   -15.3     .12       0
  1132.5     .05       0  6388.6     .12       0 10131.4      .1       0
 10410.5     .12       0 10849.5     .12       0
#XS Ineff= 1 ,-1
    6741   11100   58.61
Permanent Ineff=
       F
Bank Sta=4851.6,5314.7
XS Rating Curve= 0 ,0
Exp/Cntr=0.3,0.1

Type RM Length L Ch R = 1 ,79000   ,1000,1000,1000
BEGIN DESCRIPTION:
WFSJ Main 79.0
END DESCRIPTION:
XS GIS Cut Line= 3
      3916533.52     10020226.57      3919551.55     10010718.68
      3919554.37     10000200.48
#Sta/Elev= 30
 -4975.4   70.12 -4019.6   66.74 -3962.4   65.92 -3930.9   55.91 -3899.5   66.03
 -3595.2    67.4 -3406.4   57.71  -888.4   48.79  -573.6   55.89    -181   48.14
   207.5   48.34   529.7   49.79  2031.6   52.94  2364.7   43.69  4675.6   42.73
  4734.9   48.58  4997.6   41.23  5197.6   41.73  5217.6   48.53  6497.6    42.8
  7625.9   52.34  9122.2   55.41  9447.7   57.33 10112.7   55.31 10628.3   54.74
 13374.3   64.91 14637.8   71.88 15154.3    68.2 15247.6   62.99 15518.2   71.06
#Mann= 13 ,-1 , 0
 -4975.4     .05       0    -181     .12       0   207.5      .1       0
   529.7      .1       0  2031.6     .05       0  7625.9      .1       0
  9122.2     .05       0  9447.7     .05       0 10112.7     .05       0
 10628.3     .05       0 13374.3     .05       0 14637.8    .075       0
 15154.3     .05       0
#XS Ineff= 1 ,-1
  9367.6   13000   58.47
Permanent Ineff=
       F
Bank Sta=4734.9,5217.6
XS Rating Curve= 0 ,0
Exp/Cntr=0.3,0.1

Type RM Length L Ch R = 1 ,78000   ,2175,2175,2175
BEGIN DESCRIPTION:
WFSJ Main 78.0
END DESCRIPTION:
XS GIS Cut Line= 3
      3918460.61      10020929.7      3920541.11     10010607.18
      3922965.83     10000617.12
#Sta/Elev= 30
 -5530.1   71.78 -4303.1   69.47 -3845.9   60.67 -3800.2   51.94 -3532.1   65.22
 -3337.8   55.53 -1676.4   57.79 -1269.9   55.31 -1175.6    47.3    -477   47.71
  1017.6   51.16  1078.8   57.87  2037.7   50.72  3078.2   41.23  4720.6   47.54
  4997.6   40.73  5294.4   46.76  8937.2   41.73  9546.8   50.57 10186.1   60.37
 10875.5   68.95 11891.7   59.76 12846.6   70.43 13382.6   63.76 13441.8    49.1
 13495.8   64.46 13567.1    67.9 14400.9   67.49 14798.8   70.49 15280.1   68.34
#Mann= 9 ,-1 , 0
 -5530.1     .05       0    -477     .05       0  2037.7     .05       0
  9546.8     .12       0 10186.1     .05       0 10875.5    .075       0
 11891.7     .05       0 14400.9    .075       0 14798.8      .1       0
#XS Ineff= 2 ,-1
 -4000.1  1078.8   57.87 10768.6   15300    69.8
Permanent Ineff=
       F       F
Bank Sta=4720.6,5294.4
XS Rating Curve= 0 ,0
Exp/Cntr=0.3,0.1

Type RM Length L Ch R = 1 ,75825   ,1155,1155,1155
BEGIN DESCRIPTION:
WFSJ Main 77.0
END DESCRIPTION:
XS GIS Cut Line= 3
       3919078.3     10020841.63      3921986.28     10013549.96
      3923765.79     10000789.59
#Sta/Elev= 30
 -6698.5   70.42 -5858.2    70.2 -4767.5   53.85 -1696.1   52.72  -647.5   55.71
  -371.1    58.7  -356.8   49.52  -328.9   48.15     483    44.9     575   51.52
 1590.91   52.17  3028.5   42.14  4528.8   46.77  4997.6   41.23  5189.2   46.98
  6188.8   41.88  6919.9   45.15  7062.9   55.25    7975   66.77  8641.7   66.23
  9148.3    67.3 10087.7   69.78 10857.2   67.24 11404.5   67.94 12095.4    65.4
 12160.2   51.56 12226.7   65.85 13201.3   69.49 13913.8   70.46 14035.5    70.4
#Mann= 15 ,-1 , 0
 -6698.5     .05       0 -1696.1     .05       0  -647.5    .075       0
  -328.9     .07       0 1590.91     .05       0  7062.9     .07       0
    7975    .075       0  8641.7    .075       0  9148.3    .075       0
 10087.7    .075       0 10857.2     .05       0 11404.5     .05       0
 12160.2     .05       0 13201.3     .05       0 13913.8      .1       0
#XS Ineff= 2 ,-1
   -5350  -419.7   58.72 11048.1   14100   71.58
Permanent Ineff=
       F       F
Bank Sta=4528.8,5189.2
XS Rating Curve= 0 ,0
Exp/Cntr=0.3,0.1

Type RM Length L Ch R = 1 ,74670   ,1670,1670,1670
BEGIN DESCRIPTION:
WFSJ Main 75.0
END DESCRIPTION:
XS GIS Cut Line= 3
      3921899.47     10022187.15      3922376.91     10018497.88
      3924547.05     10003220.08
#Sta/Elev= 30
 -7780.2   68.93 -6666.5   69.49 -6015.1   58.33 -5719.5   56.41 -5170.1   54.86
 -4991.1    47.1 -4929.8   54.41 -4497.5    53.3 -4197.3   52.64   -3342   54.22
 -2967.2   52.09 -2067.5   47.41 -1554.7   47.21 -1215.1   42.54   393.3   46.65
   542.4   53.75  3572.5   54.38  3683.6   41.73  4644.2   41.73  4754.2   46.22
  4997.6   41.23  5178.5   45.61  5797.2   41.73 6395.3148.96438  6640.1   52.51
  7357.1   69.47  7886.8   67.83  8979.3    66.9   10733   69.13   11371    70.5
#Mann= 17 ,-1 , 0
 -7780.2     .05       0 -6015.1     .12       0 -5719.5      .1       0
 -5170.1     .12       0 -4929.8      .1       0 -4497.5     .12       0
 -4197.3     .05       0   -3342      .1       0 -2967.2     .05       0
 -2067.5     .12       0 -1554.7     .05       0  4644.2     .05       0
 6395.31     .05       0  6640.1     .05       0  7886.8    .075       0
  8979.3    .075       0   10733     .05       0
#XS Ineff= 1 ,-1
   -5650  3572.5   54.38
Permanent Ineff=
       F
Bank Sta=4754.2,5178.5
XS Rating Curve= 0 ,0
Exp/Cntr=0.3,0.1

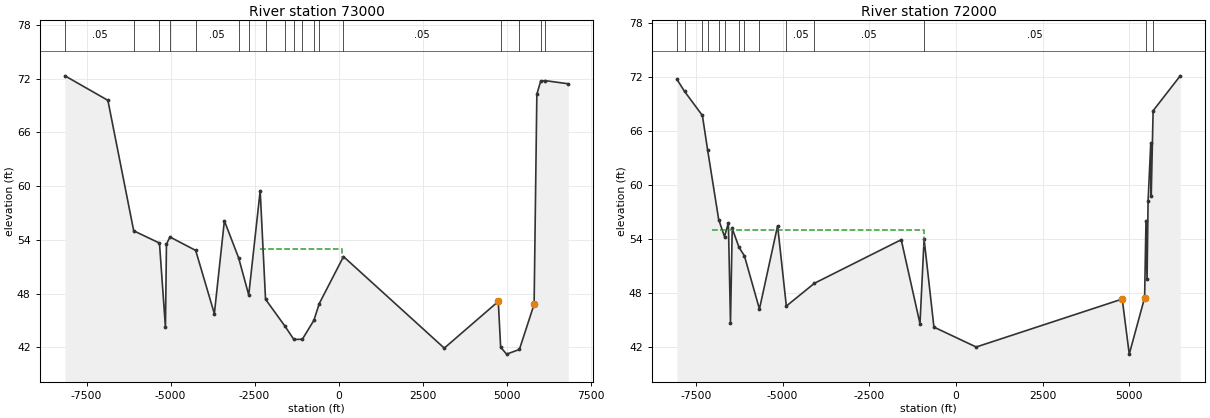
Type RM Length L Ch R = 1 ,73000   ,1000,1000,1000
BEGIN DESCRIPTION:
WFSJ Main 73.0
END DESCRIPTION:
XS GIS Cut Line= 3
      3922420.32     10022187.08      3925311.65      10009367.7
      3925559.62     10007551.55
#Sta/Elev= 30
 -8141.4   72.33 -6864.1   69.59   -6096   55.01 -5329.5   53.64 -5152.1   44.22
 -5121.4   53.53 -5017.4   54.32 -4252.4   52.82 -3696.5   45.75 -3398.5   56.13
   -2974   51.98   -2674   47.84 -2333.1   59.49   -2174   47.36   -1595   44.35
 -1332.1   42.87 -1078.9   42.89  -735.3   45.01  -575.3   46.88  145.45   52.13
  3144.1    41.9  4750.5   47.12  4820.9      42  4997.6   41.23  5378.5   41.75
  5816.6    46.8  5897.9   70.27    6014   71.76  6154.5   71.79    6833   71.44
#Mann= 18 ,-1 , 0
 -8141.4     .05       0   -6096     .12       0 -5329.5      .1       0
 -5017.4     .12       0 -4252.4     .05       0   -2974    .075       0
   -2674     .05       0   -2174     .05       0   -1595      .1       0
 -1332.1     .05       0 -1078.9     .05       0  -735.3     .12       0
  -575.3     .05       0  145.45     .05       0  4820.9     .05       0
  5378.5     .05       0    6014     .12       0  6154.5     .05       0
#XS Ineff= 2 ,-1
   -6500 -2333.1   59.49   -2330    94.1   53.03
Permanent Ineff=
       F       F
Bank Sta=4750.5,5816.6
XS Rating Curve= 0 ,0
Exp/Cntr=0.3,0.1

Type RM Length L Ch R = 1 ,72000   ,1000,1000,1000
BEGIN DESCRIPTION:
WFSJ Main 72.0
END DESCRIPTION:
XS GIS Cut Line= 3
      3923635.59     10022143.71      3926307.06     10009370.69
      3926415.43       10007906.
#Sta/Elev= 30
 -8049.4   71.71 -7830.6   70.38 -7314.8    67.7 -7165.3   63.91 -6844.3   56.15
 -6676.6   54.26 -6565.3   55.79 -6504.4   44.72 -6454.4   55.17 -6257.5   53.07
 -6102.7   52.13 -5669.1   46.23 -5145.2   55.47 -4893.4   46.56 -4083.8   49.09
 -1579.7   53.92 -1038.3   44.61 -920.13      54  -636.4   44.23   582.1   42.02
  4795.3   47.34  4997.6   41.23  5440.8   47.49  5480.5   56.04    5511   49.51
  5541.1   58.21  5618.4   64.63  5631.3   58.72  5686.1   68.23  6468.7    72.1
#Mann= 14 ,-1 , 0
 -8049.4    .075       0 -7830.6     .05       0 -7314.8    .075       0
 -7165.3      .1       0 -6844.3      .1       0 -6676.6     .05       0
 -6257.5     .12       0 -6102.7      .1       0 -5669.1     .05       0
 -4893.4     .05       0 -4083.8     .05       0 -920.13     .05       0
  5480.5     .05       0  5686.1     .05       0
#XS Ineff= 1 ,-1
   -7050    -931   54.96
Permanent Ineff=
       F
Bank Sta=4795.3,5440.8
XS Rating Curve= 0 ,0
Exp/Cntr=0.3,0.1