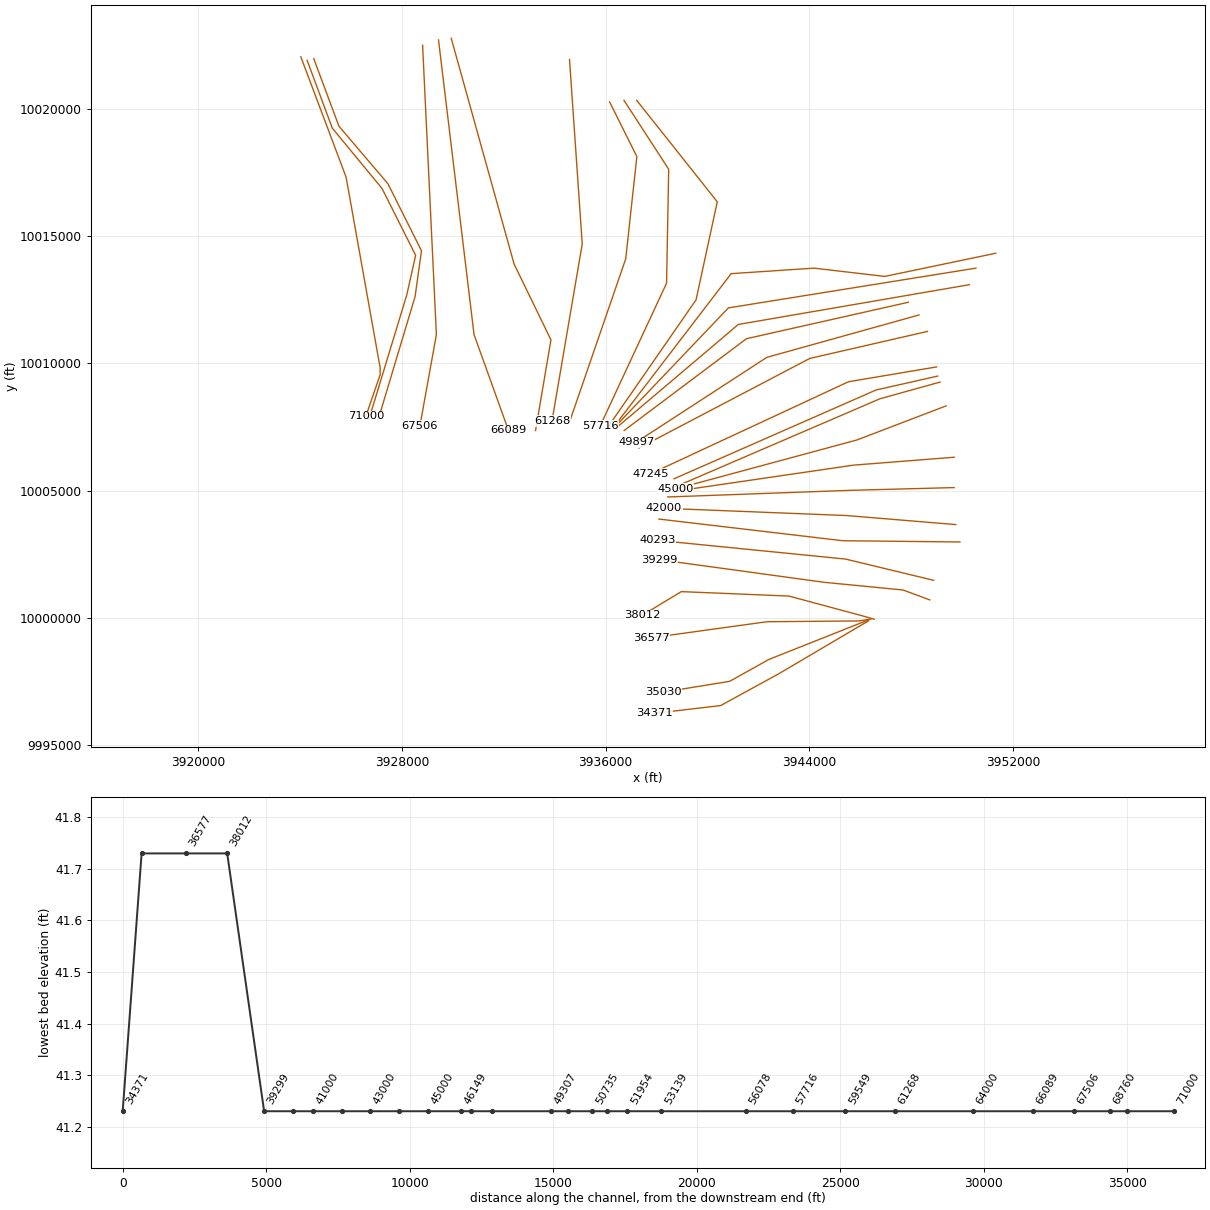
HEC-RAS study WFSJ Main.prj: WFSJ Main Base Level Engineering

--- WFSJ Main.g02 (geometry) --- (continued)

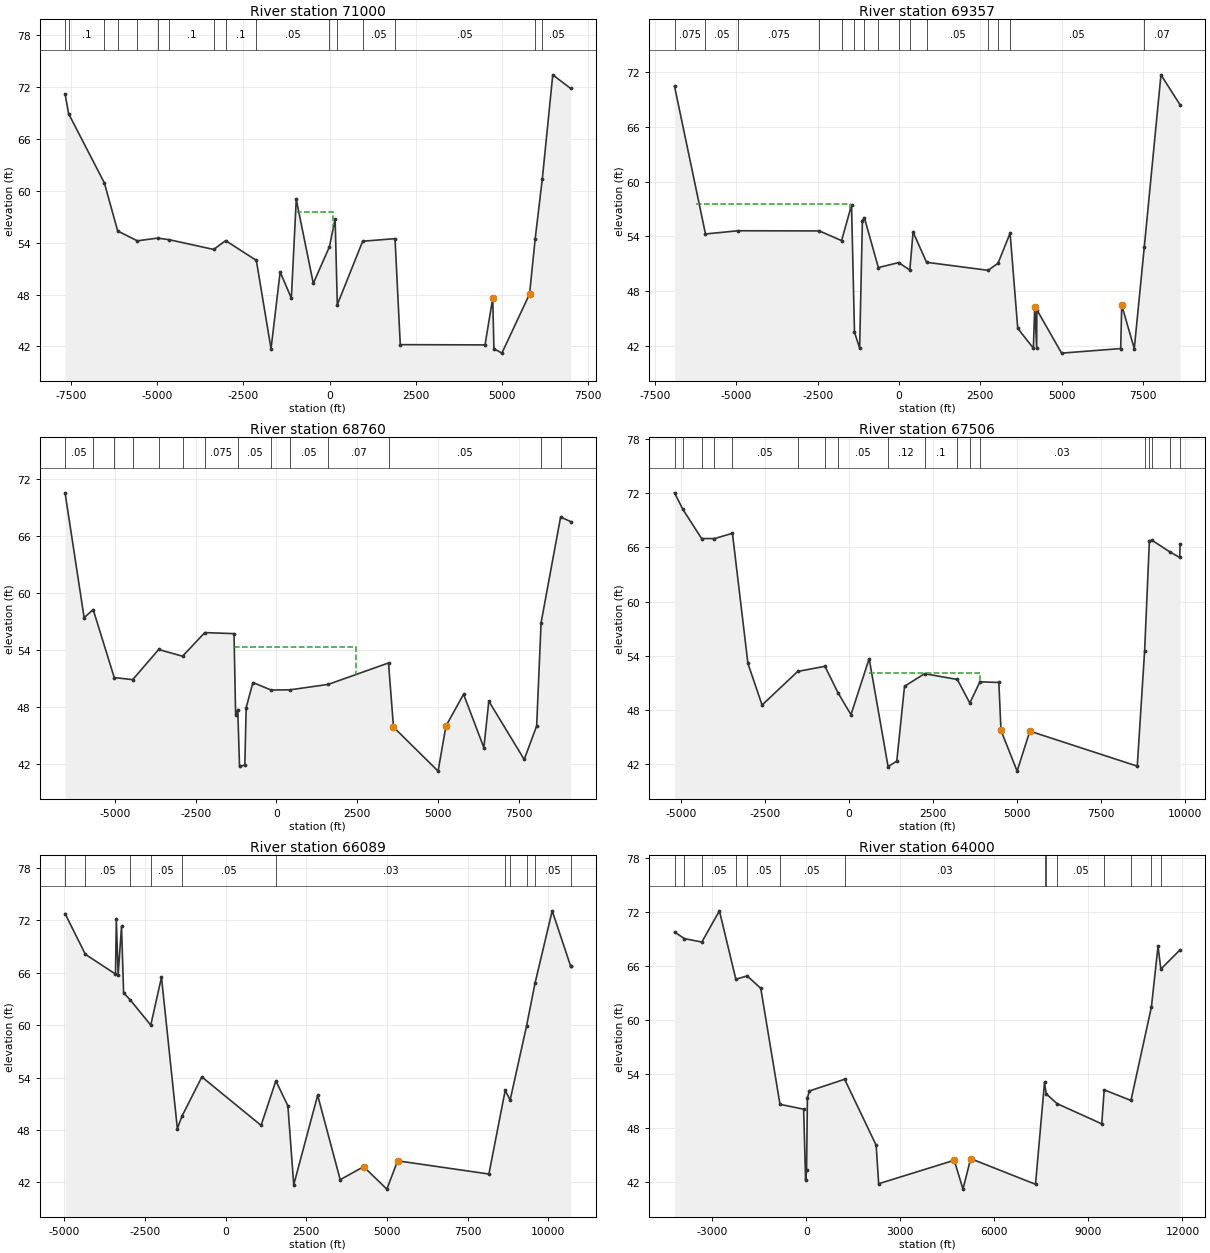
Type RM Length L Ch R = 1 ,71000   ,1643,1643,1643
BEGIN DESCRIPTION:
WFSJ Main 71.0
END DESCRIPTION:
XS GIS Cut Line= 5
       3924026.2     10022056.94      3925805.73       10017326.
      3927143.93     10009827.12       3927142.2     10009551.71
      3926582.31     10007928.27
#Sta/Elev= 30
 -7671.9   71.18   -7567   68.88 -6532.3    60.9 -6144.8   55.34   -5576   54.21
 -4989.9   54.52 -4652.3   54.34 -3361.7   53.21 -3015.3   54.23 -2124.6   51.95
 -1698.1   41.74 -1433.6   50.61   -1109   47.58  -966.7   58.99  -472.4   49.29
      -4   53.53   160.8   56.74   224.3   46.83   959.7   54.16  1897.8   54.46
  2050.2   42.21  4508.4   42.18  4731.9   47.58  4766.8   41.74  4997.6   41.23
    5800   48.06 5963.64   54.46  6170.3   61.37  6473.2   73.39  6992.7   71.81
#Mann= 16 ,-1 , 0
 -7671.9      .1       0   -7567      .1       0 -6532.3    .075       0
 -6144.8      .1       0   -5576      .1       0 -4989.9    .075       0
 -4652.3      .1       0 -3361.7    .075       0 -3015.3      .1       0
 -2124.6     .05       0      -4    .075       0   224.3     .05       0
   959.7     .05       0  1897.8     .05       0 5963.64     .05       0
  6170.3     .05       0
#XS Ineff= 3 ,-1
   -6580  -966.7   58.99    -965   101.7   57.59     102  1897.8   54.46
Permanent Ineff=
       F       F       F
Bank Sta=4731.9,5800
XS Rating Curve= 0 ,0
Exp/Cntr=0.3,0.1

Type RM Length L Ch R = 1 ,69357   ,597,597,597
BEGIN DESCRIPTION:
WFSJ Main 70.0
END DESCRIPTION:
XS GIS Cut Line= 6
      3924274.65      10021917.5      3925264.23     10019248.22
      3927217.36     10016878.43      3928537.67     10014250.83
      3928183.33     10012671.49      3926709.54     10007828.92
#Sta/Elev= 30
 -6898.5   70.43   -5947   54.27 -4939.6   54.62 -2446.6    54.6 -1764.9   53.54
 -1458.4   57.43 -1367.4   43.53 -1209.5   41.77 -1124.8   55.73 -1063.9   56.05
  -633.9   50.59    -7.7   51.14   332.7   50.31   433.3   54.47   847.9   51.17
  2738.8   50.29  3043.9   51.06    3415   54.36  3649.7   43.94  4130.3   41.77
  4171.9    46.3  4231.2   41.84  4236.4   45.98  4997.6   41.23    6814   41.73
  6845.4   46.48  7231.2   41.73    7538    52.8  8051.3   71.68  8640.8   68.39
#Mann= 15 ,-1 , 0
 -6898.5    .075       0   -5947     .05       0 -4939.6    .075       0
 -2446.6     .05       0 -1764.9     .05       0 -1367.4    .075       0
 -1063.9     .05       0  -633.9     .05       0    -7.7     .05       0
   332.7    .075       0   847.9     .05       0  2738.8    .075       0
  3043.9     .07       0    3415     .05       0    7538     .07       0
#XS Ineff= 2 ,-1
   -6250 -1493.5    57.6   -1492    3415   54.36
Permanent Ineff=
       F       F
Bank Sta=4171.9,6845.4
XS Rating Curve= 0 ,0
Exp/Cntr=0.5,0.3

Type RM Length L Ch R = 1 ,68760   ,1254,1254,1254
BEGIN DESCRIPTION:
WFSJ Main 69.0
END DESCRIPTION:
XS GIS Cut Line= 6
      3924535.06     10021982.62      3925524.65     10019326.35
      3927451.73     10017060.72      3928766.84     10014430.52
       3928515.1     10012627.13      3927061.11     10007776.87
#Sta/Elev= 30
 -6536.9   70.56 -5948.3   57.41 -5667.4   58.25 -5016.3   51.09 -4446.8   50.87
 -3641.7   54.05 -2903.6   53.34 -2217.2   55.83 -1312.7   55.72 -1263.2   47.18
   -1197   47.71 -1142.4   41.73  -978.8   41.86  -937.1   47.92  -727.9   50.57
  -171.4   49.78   420.3    49.8  1599.1   50.37  3464.2   52.63  3618.3   45.87
  4997.6   41.23  5240.5   45.99  5785.6   49.33  6412.2   43.71  6566.3    48.6
  7660.2   42.46  8044.9   45.99  8182.4   56.87  8785.8   68.01  9097.1   67.53
#Mann= 14 ,-1 , 0
 -6536.9     .05       0 -5667.4     .05       0 -5016.3    .075       0
 -4446.8    .075       0 -3641.7      .1       0 -2903.6      .1       0
 -2217.2    .075       0   -1197     .05       0  -171.4     .05       0
   420.3     .05       0  1599.1     .07       0  3464.2     .05       0
  8182.4       0       0  8785.8     .05       0
#XS Ineff= 2 ,-1
   -6130 -1312.7   55.72   -1311    2459   54.32
Permanent Ineff=
       F       F
Bank Sta=3618.3,5240.5
XS Rating Curve= 0 ,0
Exp/Cntr=0.5,0.3

Type RM Length L Ch R = 1 ,67506   ,1417,1417,1417
BEGIN DESCRIPTION:
WFSJ Main 68.0
END DESCRIPTION:
XS GIS Cut Line= 3
      3928810.93     10022510.06       3929352.6     10011135.03
      3928706.77     10007551.69
#Sta/Elev= 30
   -5186   72.05 -4939.7   70.23 -4381.1   66.99 -3999.2   66.98   -3465   67.57
 -3004.5   53.16 -2584.1   48.55 -1524.8   52.27  -714.7   52.84  -327.3   49.91
    58.9   47.48   599.5   53.69  1161.7   41.73  1420.5   42.34  1650.7   50.63
  2245.8   52.02  3220.6   51.38  3591.1   48.77  3891.4   51.12  4453.9   51.05
 4518.18   45.73  4997.6   41.23  5374.9   45.66  8568.4   41.78  8786.9   54.53
  8929.1   66.75  9013.7   66.78  9529.2   65.53    9829   64.89    9843   66.39
#Mann= 18 ,-1 , 0
   -5186    .075       0 -4939.7      .1       0 -4381.1    .075       0
 -3999.2     .05       0   -3465     .05       0 -1524.8     .05       0
  -714.7    .075       0  -327.3     .05       0  1161.7     .12       0
  2245.8      .1       0  3220.6     .05       0  3591.1     .05       0
  3891.4     .03       0  8786.9     .05       0  8929.1      .1       0
  9013.7     .05       0  9529.2     .05       0    9829    .075       0
#XS Ineff= 2 ,-1
   -3070   599.5   53.69     600  3896.4   52.11
Permanent Ineff=
       F       F
Bank Sta=4518.18,5374.9
XS Rating Curve= 0 ,0
Exp/Cntr=0.3,0.1

Type RM Length L Ch R = 1 ,66089   ,2089,2089,2089
BEGIN DESCRIPTION:
WFSJ Main 67.0
END DESCRIPTION:
XS GIS Cut Line= 3
      3929435.94     10022718.32      3930831.77     10011135.03
      3932185.59     10007365.14
#Sta/Elev= 30
 -4976.6   72.78   -4347   68.12 -3413.7   65.86 -3387.9   72.11 -3331.6   65.77
 -3226.8   71.33 -3162.4   63.71 -2961.6   62.92 -2320.3   60.01 -1987.9   65.49
 -1495.6   48.16 -1356.7   49.55  -736.7   54.08  1099.3   48.53  1557.6   53.63
  1930.2   50.77  2111.6   41.73  2853.3   51.98  3551.9   42.31  4278.9    43.8
  4997.6   41.23  5331.5  44.471    8161   42.96 8665.91   52.53  8820.1   51.44
  9326.9   59.89  9589.9    64.8 10123.6    73.1 10694.2   66.78 10696.1   66.77
#Mann= 11 ,-1 , 0
 -4976.6     .05       0   -4347     .05       0 -2961.6    .075       0
 -2320.3     .05       0 -1356.7     .05       0  1557.6     .03       0
 8665.91     .05       0  8820.1    .075       0  9326.9    .075       0
  9589.9     .05       0 10694.2    .075       0
#XS Ineff= 2 ,-1
   -1700  1557.6   53.63    1558  2853.3   51.98
Permanent Ineff=
       F       F
Bank Sta=4278.9,5331.5
XS Rating Curve= 0 ,0
Exp/Cntr=0.3,0.1

Type RM Length L Ch R = 1 ,64000   ,2732,2732,2732
BEGIN DESCRIPTION:
WFSJ Main 64.0
END DESCRIPTION:
XS GIS Cut Line= 4
      3929935.93     10022780.88      3932404.34     10013909.28
       3933852.6      10010926.7       3933248.6     10007365.16
#Sta/Elev= 30
 -4208.6   69.83 -3895.5   69.09 -3336.5   68.71 -2776.4   72.18 -2250.8   64.57
 -1889.3   64.94 -1456.2   63.56    -843   50.66     -88   50.12   -25.7   42.25
     5.4   43.32    32.1   51.39    98.8   52.15  1219.9   53.45  2226.7   46.11
  2306.5   41.83 4718.27   44.44  4997.6   41.23  5242.6   44.62  7312.3   41.77
  7599.3   53.09  7653.5   51.82  8004.4   50.73  9426.9   48.49  9504.3   52.27
 10358.7   51.09 11010.8   61.48 11222.2   68.25 11312.1    65.7   11928   67.85
#Mann= 14 ,-1 , 0
 -4208.6     .12       0 -3895.5     .05       0 -3336.5     .05       0
 -2250.8    .075       0 -1889.3     .05       0    -843     .05       0
  1219.9     .03       0  7599.3     .05       0  7653.5     .05       0
  8004.4     .05       0  9504.3     .05       0 10358.7     .05       0
 11010.8    .075       0 11312.1     .05       0
#XS Ineff= 2 ,-1
   -1170  1219.9   53.45  7599.3   10650   53.09
Permanent Ineff=
       F       F
Bank Sta=4718.27,5242.6
XS Rating Curve= 0 ,0
Exp/Cntr=0.3,0.1

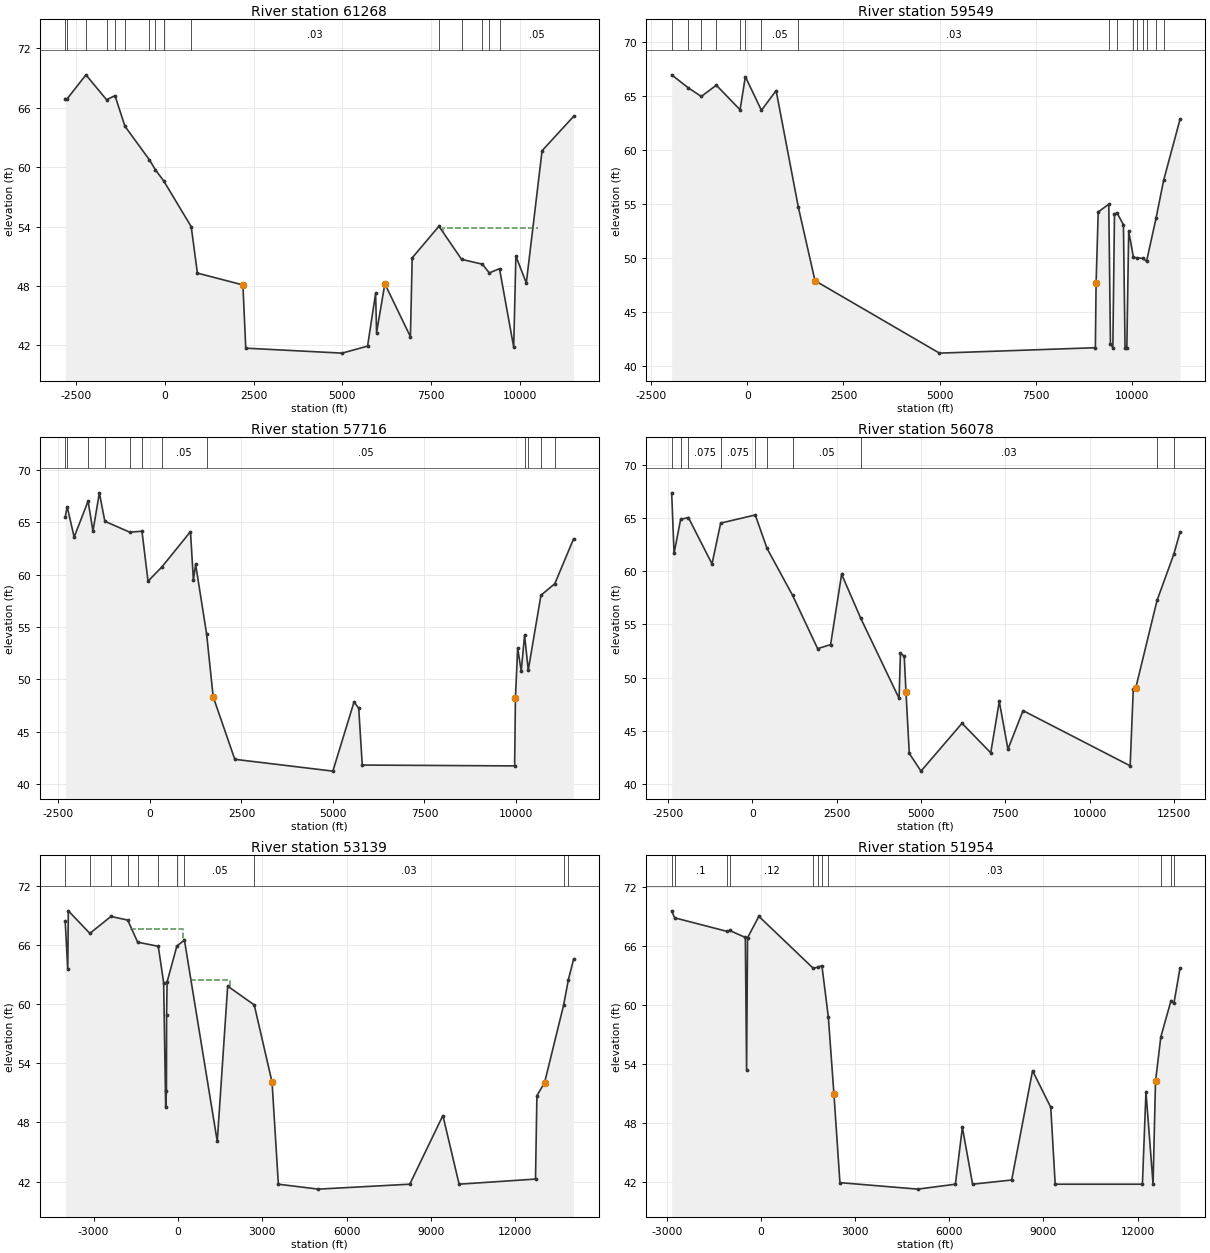
Type RM Length L Ch R = 1 ,61268   ,1719,1719,1719
BEGIN DESCRIPTION:
WFSJ Main 62.0
END DESCRIPTION:
XS GIS Cut Line= 3
      3934581.77      10021947.5      3935081.77     10014697.53
      3933894.27     10007739.22
#Sta/Elev= 30
 -2807.2    66.9 -2763.4   66.83 -2222.9    69.3 -1642.5   66.79 -1403.6    67.2
 -1124.9   64.12  -432.5   60.72  -267.4   59.73   -25.6   58.57   744.6   53.98
   918.1    49.3  2201.1   48.11  2281.3   41.73  4997.6   41.23  5714.3   41.94
  5941.1   47.26  5967.9   43.29  6201.3   48.22  6921.5   42.89  6972.2   50.84
  7725.5   54.03  8363.7   50.69  8949.4    50.2  9145.4   49.32  9432.6   49.75
    9833   41.83  9893.9   51.01 10188.1   48.31 10632.5   61.65 11518.9    65.1
#Mann= 15 ,-1 , 0
 -2807.2    .075       0 -2763.4     .05       0 -2222.9     .05       0
 -1642.5     .05       0 -1403.6    .075       0 -1124.9     .05       0
  -432.5    .075       0  -267.4     .05       0   -25.6     .05       0
   744.6     .03       0  7725.5     .05       0  8363.7     .05       0
  8949.4    .075       0  9145.4     .05       0  9432.6     .05       0
#XS Ineff= 1 ,-1
  7840.7   10515    53.9
Permanent Ineff=
       F
Bank Sta=2201.1,6201.3
XS Rating Curve= 0 ,0
Exp/Cntr=0.3,0.1

Type RM Length L Ch R = 1 ,59549   ,1833,1833,1833
BEGIN DESCRIPTION:
WFSJ Main 60.0
END DESCRIPTION:
XS GIS Cut Line= 4
      3936157.27     10020279.34       3937227.6     10018135.03
       3936790.1      10014114.2      3934582.32     10007699.14
#Sta/Elev= 30
 -1969.1   66.96 -1537.6   65.76 -1198.9   64.96  -807.4      66  -189.3   63.73
     -52   66.79   365.8   63.68   748.5    65.5  1326.7   54.72  1759.3   47.93
  4997.6   41.23  9054.6   41.73 9073.37 47.7088  9128.7   54.29  9403.6   54.99
  9446.5   42.12  9509.4   41.73  9551.7   54.06  9615.1   54.21  9784.7    53.1
  9826.6   41.73  9873.1   41.73  9921.8    52.5 10045.1   50.08 10149.8   50.04
 10283.9   49.99 10386.8   49.73 10635.3   53.74 10830.2    57.2 11256.4   62.84
#Mann= 16 ,-1 , 0
 -1969.1    .075       0 -1537.6     .05       0 -1198.9    .075       0
  -807.4    .075       0  -189.3     .05       0     -52    .075       0
   365.8     .05       0  1326.7     .03       0  9403.6     .05       0
  9615.1    .075       0 10045.1     .05       0 10149.8    .075       0
 10283.9     .05       0 10386.8    .075       0 10635.3     .05       0
 10830.2     .05       0
#XS Ineff= 1 ,-1
  9165.4   10820   54.36
Permanent Ineff=
       F
Bank Sta=1759.3,9073.37
XS Rating Curve= 0 ,0
Exp/Cntr=0.3,0.1

Type RM Length L Ch R = 1 ,57716   ,1638,1638,1638
BEGIN DESCRIPTION:
WFSJ Main 58.0
END DESCRIPTION:
XS GIS Cut Line= 4
       3936721.5     10020344.44       3938477.6     10017635.03
      3938394.27     10013155.86      3935790.08     10007551.65
#Sta/Elev= 30
   -2315   65.49 -2262.3   66.52 -2070.1    63.6 -1690.1   67.04 -1556.5   64.17
 -1381.5   67.83 -1232.3   65.11  -552.5   64.07  -217.7   64.16   -51.9   59.38
   329.5   60.76  1107.7   64.12  1187.7   59.48  1247.8   61.01  1547.8   54.36
  1727.8   48.34  2317.9   42.36  4997.6   41.23  5575.4   47.83  5703.9   47.26
  5800.9   41.81  9964.1   41.73  9986.2   48.23 10047.5   52.98 10144.5   50.79
 10236.1   54.24 10335.9   50.88 10683.3   58.04 11060.7   59.14 11573.4   63.42
#Mann= 12 ,-1 , 0
   -2315     .05       0 -2262.3     .05       0 -1690.1     .05       0
 -1232.3     .05       0  -552.5     .05       0  -217.7    .075       0
   329.5     .05       0  1547.8     .05       0 10236.1    .075       0
 10335.9     .05       0 10683.3    .075       0 11060.7     .05       0
Bank Sta=1727.8,9986.2
XS Rating Curve= 0 ,0
Exp/Cntr=0.3,0.1

Type RM Length L Ch R = 1 ,56078   ,2939,2939,2939
BEGIN DESCRIPTION:
WFSJ Main 56.0
END DESCRIPTION:
XS GIS Cut Line= 4
      3937220.66      10020344.4      3940385.93     10016354.47
       3939552.6     10012500.31      3936115.49     10007535.59
#Sta/Elev= 30
 -2395.7   67.35 -2324.5   61.68 -2129.6   64.86 -1899.8   65.03 -1199.7   60.68
  -942.5   64.51    83.2   65.27   431.3   62.14  1189.6   57.73  1932.7   52.73
  2317.3    53.1  2644.1   59.71  3212.3   55.57    4348   48.06  4388.9   52.32
  4501.4   51.99  4552.4   48.66  4650.9   42.89  4997.6   41.23  6214.3   45.72
  7066.5   42.95  7319.9   47.77  7576.7   43.29    8024   46.91 11200.6   41.73
 11293.7   48.96 11365.3   49.02 11997.8   57.25 12494.8   61.58 12678.9   63.65
#Mann= 10 ,-1 , 0
 -2395.7    .075       0 -2129.6     .05       0 -1899.8    .075       0
  -942.5    .075       0    83.2    .075       0   431.3     .05       0
  1189.6     .05       0  3212.3     .03       0 11997.8    .075       0
 12494.8     .05       0
#XS Ineff= 1 ,-1
     570  2644.1   59.71
Permanent Ineff=
       F
Bank Sta=4552.4,11365.3
XS Rating Curve= 0 ,0
Exp/Cntr=0.3,0.1

Type RM Length L Ch R = 1 ,53139   ,1185,1185,1185
BEGIN DESCRIPTION:
WFSJ Main 54.0
END DESCRIPTION:
XS GIS Cut Line= 5
      3951326.55     10014333.12      3946964.58     10013421.66
       3944186.8     10013747.18      3940931.59     10013530.17
      3936331.88     10007520.16
#Sta/Elev= 30
 -4008.6   68.42   -3918   63.52 -3897.6   69.47 -3131.4   67.18 -2382.2    68.9
 -1784.7   68.53 -1432.2   66.29    -698   65.87  -506.9   62.19  -434.3    49.6
    -407   51.21  -401.9    58.9  -383.3   62.26   -37.2   65.89   232.6    66.5
  1400.8   46.07  1771.3   61.83    2717   59.92 3349.6852.08987    3574   41.73
  4997.4   41.23  8249.3   41.73  9427.2    48.7 10004.7   41.73 12722.2   42.25
   12772   50.7113045.45   52.0413720.87   59.89 13891.8   62.48   14075   64.54
#Mann= 11 ,-1 , 0
 -4008.6     .12       0 -3131.4      .1       0 -2382.2     .12       0
 -1784.7      .1       0 -1432.2     .12       0    -698      .1       0
   -37.2     .12       0   232.6     .05       0    2717     .03       0
13720.87     .05       0 13891.8    .075       0
#XS Ineff= 2 ,-1
   -1690   182.6   67.65     445  1859.5   62.48
Permanent Ineff=
       F       F
Bank Sta=3349.68,13045.45
XS Rating Curve= 0 ,0
Exp/Cntr=0.3,0.1

Type RM Length L Ch R = 1 ,51954   ,693,693,693
BEGIN DESCRIPTION:
Mapping XS d13458fd
END DESCRIPTION:
XS GIS Cut Line= 3
      3950545.33     10013747.19      3940823.09     10012184.68
      3936440.42     10007585.05
#Sta/Elev= 30
 -2846.1   69.56 -2752.9   68.85 -1095.8   67.48  -996.6   67.56  -498.9   66.85
  -458.4   53.37    -428   66.82   -67.3      69  1670.4    63.7  1805.6   63.83
    1942   63.97 2146.59   58.75  2325.2   50.91    2516   41.89  4997.4   41.23
  6195.9   41.73  6418.8   47.51    6744   41.73  7990.2   42.16  8655.2   53.28
  9235.2   49.56  9376.7   41.73 12156.5   41.73 12269.4   51.16 12495.9   41.73
 12573.6    52.2 12743.4   56.73   13069   60.43 13159.6   60.13 13354.2   63.74
#Mann= 11 ,-1 , 0
 -2846.1     .12       0 -2752.9      .1       0 -1095.8     .05       0
  -996.6     .12       0  1670.4     .12       0  1805.6     .05       0
    1942     .05       0 2146.59     .03       0 12743.4     .05       0
   13069     .05       0 13159.6    .075       0
Bank Sta=2325.2,12573.6
XS Rating Curve= 0 ,0
Exp/Cntr=0.3,0.1

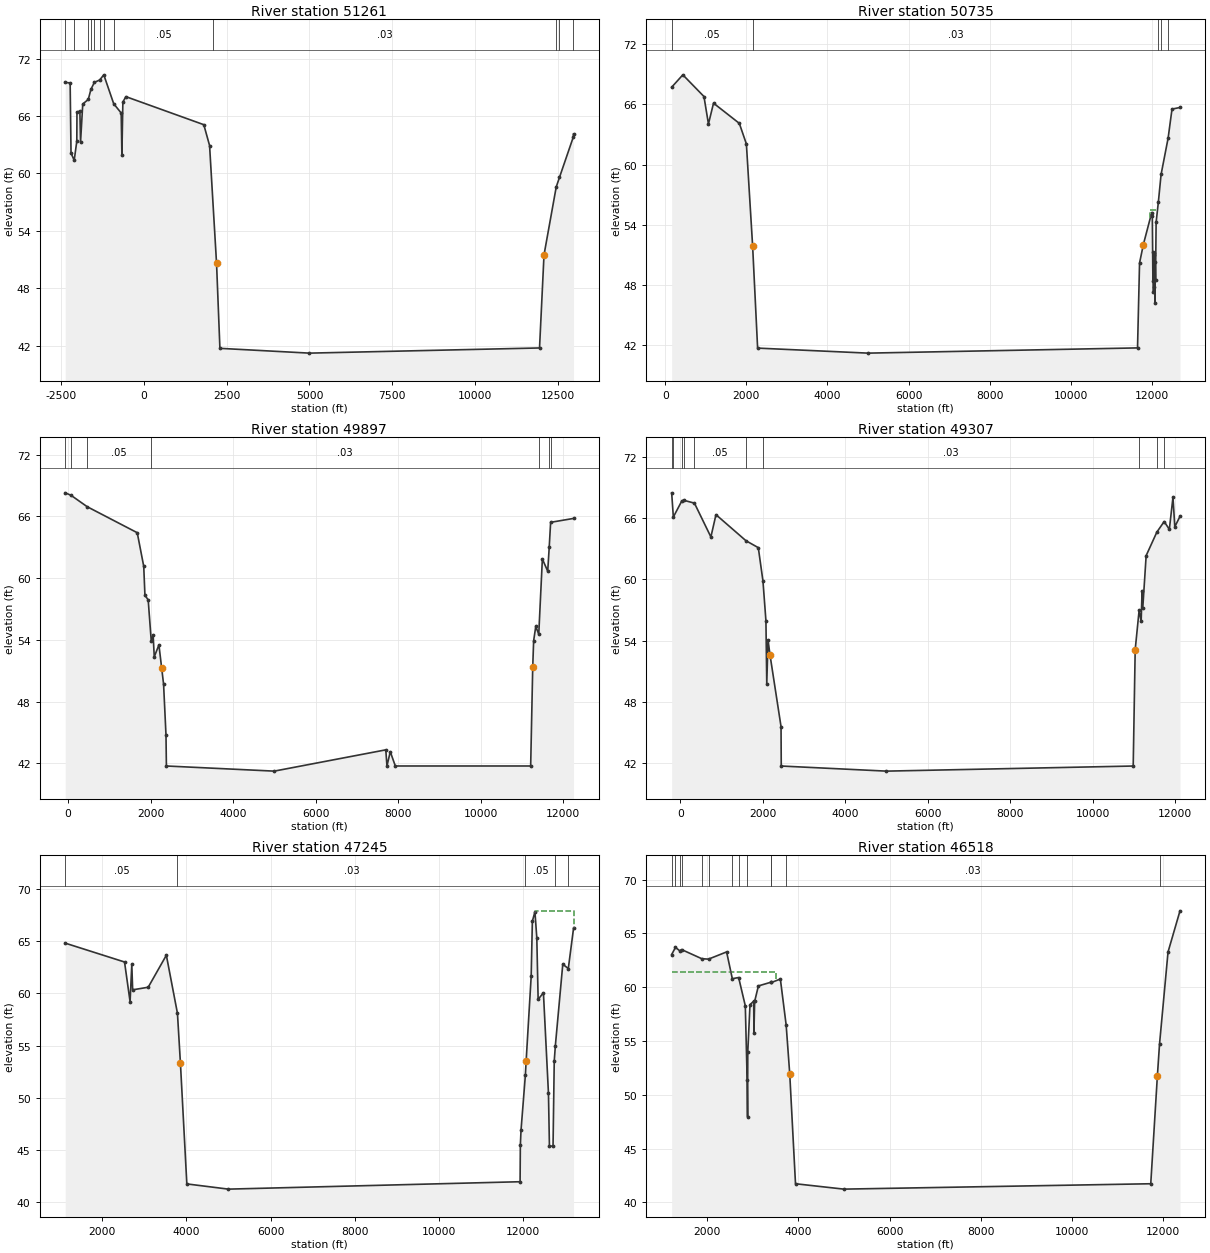
Type RM Length L Ch R = 1 ,51261   ,526,526,526
BEGIN DESCRIPTION:
WFSJ Main 52.0
END DESCRIPTION:
XS GIS Cut Line= 3
      3950284.86     10013096.13      3941213.71     10011533.64
      3936519.28     10007551.71
#Sta/Elev= 30
   -2381   69.52 -2231.8   69.46 -2205.2   62.13 -2109.1   61.38 -2030.6   63.37
 -2025.5   66.42 -1937.6   66.52 -1917.3   63.29 -1850.9   67.26 -1683.8   67.74
 -1602.8    68.8 -1500.1   69.52 -1339.1   69.77 -1214.9   70.31  -915.5   67.29
  -689.4   66.32  -668.1   61.94  -638.7   67.47  -547.4   68.03  1806.9    65.1
  1981.6   62.92  2192.4    50.6  2293.9   41.73  4997.4   41.23 11952.2   41.77
 12087.4   51.49 12456.5   58.59 12555.3    59.6 12969.8   63.78 12979.5   64.13
#Mann= 12 ,-1 , 0
   -2381     .12       0 -2109.1     .05       0 -1683.8     .12       0
 -1602.8     .05       0 -1500.1     .12       0 -1339.1     .05       0
 -1214.9     .12       0  -915.5     .05       0  2090.9     .03       0
 12456.5     .05       0 12555.3     .05       0 12969.8    .075       0
Bank Sta=2192.4,12087.4
XS Rating Curve= 0 ,0
Exp/Cntr=0.3,0.1

Type RM Length L Ch R = 1 ,50735   ,838,838,838
BEGIN DESCRIPTION:
WFSJ Main 51.0
END DESCRIPTION:
XS GIS Cut Line= 3
      3947894.31     10012405.87      3941531.77     10010972.53
      3936728.83     10007365.11
#Sta/Elev= 30
   159.8    67.7     435   68.93   955.7   66.77  1066.1   64.04  1191.5   66.11
    1827    64.1  2001.3   62.05    2155   51.89    2278   41.73  4997.4   41.23
 11641.8   41.75 11691.7    50.2 11785.5   52.04 11991.7   55.22 12006.3   54.91
 12020.8   48.44 12027.1   51.28 12035.4   47.35 12041.7   50.98   12050   47.86
 12056.2   51.22 12070.8   46.26 12077.1   50.34 12085.4   48.55   12100   54.24
 12156.2    56.3 12222.3   59.01 12396.6   62.65 12491.6   65.52 12688.6   65.68
#Mann= 5 ,-1 , 0
   159.8     .05       0    2155     .03       0 12156.2     .05       0
 12222.3    .075       0 12396.6     .05       0
#XS Ineff= 1 ,-1
 11956.3   12130   55.52
Permanent Ineff=
       F
Bank Sta=2155,11785.5
XS Rating Curve= 0 ,0
Exp/Cntr=0.3,0.1

Type RM Length L Ch R = 1 ,49897   ,590,590,590
BEGIN DESCRIPTION:
WFSJ Main 50.0
END DESCRIPTION:
XS GIS Cut Line= 3
      3948310.97     10011905.87      3942331.77      10010239.2
      3937206.93     10006905.97
#Sta/Elev= 30
   -67.8    68.3    72.7   68.06   464.9   66.95  1678.1   64.42  1835.6   61.15
  1864.6   58.33  1943.4   57.89    2017   53.92  2063.6   54.45  2090.5   52.35
  2203.5   53.51  2271.2   51.22  2316.5   49.69    2375   44.74  2384.8   41.73
  4997.4   41.23  7702.4    43.3  7730.6   41.73  7811.1   43.12  7933.4   41.73
 11213.9   41.7311263.64   51.32   11286   53.91 11337.3    55.3 11409.8   54.55
 11497.4   61.86 11627.2   60.68 11663.5   63.01 11697.8   65.43 12252.8   65.81
#Mann= 7 ,-1 , 0
   -67.8      .1       0    72.7    .075       0   464.9     .05       0
    2017     .03       0 11409.8     .05       0 11663.5    .075       0
 11697.8     .05       0
Bank Sta=2271.2,11263.64
XS Rating Curve= 0 ,0
Exp/Cntr=0.3,0.1

Type RM Length L Ch R = 1 ,49307   ,2062,2062,2062
BEGIN DESCRIPTION:
WFSJ Main 49.0
END DESCRIPTION:
XS GIS Cut Line= 3
      3948644.25     10011260.02      3944019.27     10010197.53
      3937311.91     10006677.21
#Sta/Elev= 30
  -207.2   68.48  -166.7   66.11    41.6   67.71    95.5   67.74   344.5   67.47
   743.3   64.16   866.5   66.34  1593.4   63.79  1892.5   63.11  2005.4   59.84
  2077.2   55.96  2097.7   49.79  2128.2   54.07  2176.1   52.61  2443.5   45.59
  2448.6   41.73  4997.4   41.23 10979.1   41.7311027.27   53.12 11122.2   56.96
 11171.9   55.91   11194    58.9 11210.4   57.16 11292.9   62.33 11551.9   64.63
 11729.8   65.67   11855    64.9 11943.2   68.05 11987.3   65.15 12113.3   66.18
#Mann= 10 ,-1 , 0
  -207.2     .05       0  -166.7    .075       0    41.6      .1       0
    95.5    .075       0   344.5     .05       0  1593.4     .05       0
  2005.4     .03       0 11122.2     .05       0 11551.9    .075       0
 11729.8     .05       0
Bank Sta=2176.1,11027.27
XS Rating Curve= 0 ,0
Exp/Cntr=0.3,0.1

Type RM Length L Ch R = 1 ,47245   ,727,727,727
BEGIN DESCRIPTION:
WFSJ Main 48.0
END DESCRIPTION:
XS GIS Cut Line= 3
      3948998.39     10009864.19       3945540.1     10009280.86
      3937766.27       10005663.
#Sta/Elev= 30
  1119.6   64.83  2529.8   63.02  2661.6   59.21  2702.2    62.8  2722.5   60.35
  3092.5    60.6  3523.6   63.67  3787.3    58.1  3858.3    53.3  4010.4   41.73
  4997.4   41.23   11931   41.94 11937.2   45.43 11953.1   46.88 12057.1    52.2
 12074.4   53.49 12194.4   61.63 12222.8   66.94   12284   67.84 12328.1   65.35
   12360   59.43 12485.5   60.07 12605.4   50.41 12628.3   45.37 12714.1   45.35
 12742.7   53.51 12768.5   54.96 12945.8   62.81   13077   62.39 13201.2   66.25
#Mann= 5 ,-1 , 0
  1119.6     .05       0  3787.3     .03       0 12057.1     .05       0
 12768.5    .075       0   13077     .05       0
#XS Ineff= 2 , 0
                        12273.86           67.93
Permanent Ineff=
       F       F
Bank Sta=3858.3,12074.4
XS Rating Curve= 0 ,0
Exp/Cntr=0.3,0.1

Type RM Length L Ch R = 1 ,46518   ,369,369,369
BEGIN DESCRIPTION:
WFSJ Main 47.0
END DESCRIPTION:
XS GIS Cut Line= 3
      3949043.36     10009503.44      3946621.44     10008956.56
      3938687.43     10005466.98
#Sta/Elev= 30
  1221.6   63.04  1305.3    63.7  1400.2   63.38  1438.5    63.5  1881.9   62.65
  2029.4   62.61  2426.7   63.28  2551.9   60.79  2690.4    60.9  2836.8   58.27
  2877.6   51.33  2886.2   47.96  2891.3      54  2939.7   58.38  3020.9    58.7
  3026.1   55.78  3041.8   58.68  3123.8   60.12  3404.9   60.47  3410.9   60.44
  3605.7   60.76  3733.1   56.48  3811.7   51.92  3937.8   41.73  4997.4   41.23
 11730.5   41.73   11876   51.77 11922.7    54.7 12109.4   63.27   12372    67.1
#Mann= 13 ,-1 , 0
  1221.6    .075       0  1305.3      .1       0  1400.2    .075       0
  1438.5     .05       0  1881.9    .075       0  2029.4     .05       0
  2551.9    .075       0  2690.4     .05       0  2877.6    .075       0
  3404.9     .05       0  3410.9     .05       0  3733.1     .03       0
 11922.7     .05       0
#XS Ineff= 2 , 0
         3507.95   61.45
Permanent Ineff=
       F       F
Bank Sta=3811.7,11876
XS Rating Curve= 0 ,0
Exp/Cntr=0.3,0.1

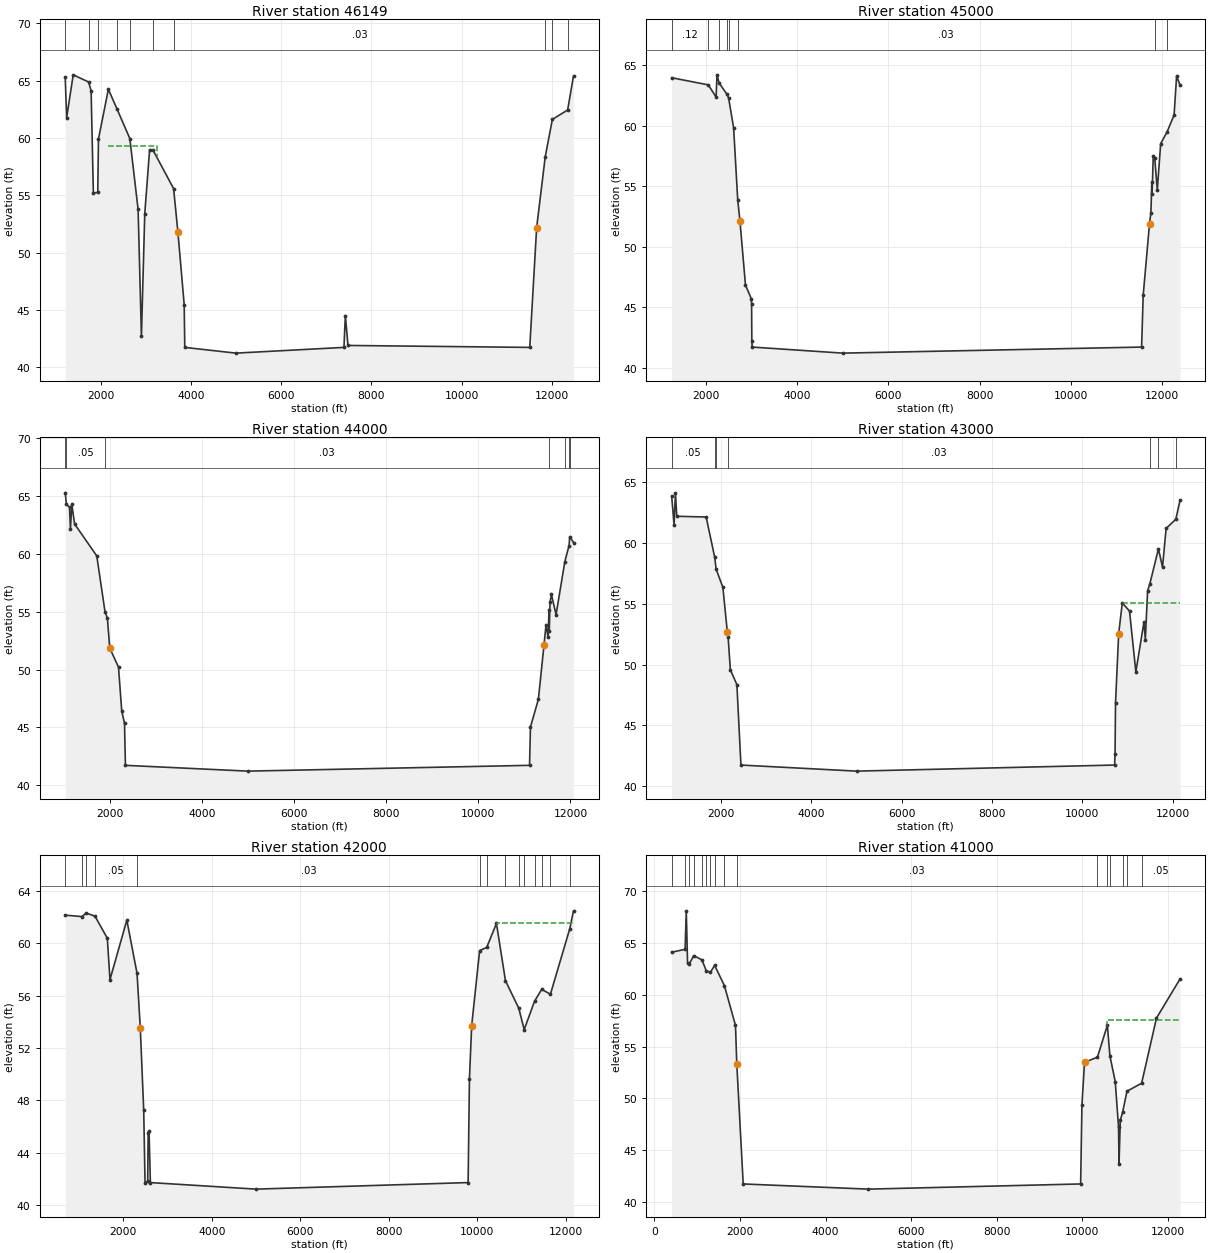
Type RM Length L Ch R = 1 ,46149   ,1149,1149,1149
BEGIN DESCRIPTION:
WFSJ Main 46.0
END DESCRIPTION:
XS GIS Cut Line= 3
       3949138.8     10009269.06      3946769.01     10008609.33
      3938687.39     10005128.42
#Sta/Elev= 30
  1217.3   65.34  1249.4   61.78  1394.7   65.52  1736.9   64.89  1791.1   64.11
  1841.1   55.22  1938.3   55.25  1954.3   59.92  2173.3   64.26    2369    62.5
  2648.8   59.96  2832.1   53.77  2905.7   42.69  2979.3   53.39  3086.7   58.99
    3166   58.92  3618.1   55.59  3713.7   51.79  3852.7   45.46  3865.7   41.73
  4997.4   41.23  7391.3   41.73  7422.6   44.51  7480.6    41.9   11507   41.73
 11659.5   52.18 11850.3   58.38 12007.9   61.63   12346   62.45 12476.6   65.42
#Mann= 10 ,-1 , 0
  1217.3      .1       0  1736.9    .075       0  1954.3     .05       0
    2369    .075       0  2648.8     .12       0    3166     .05       0
  3618.1     .03       0 11850.3     .05       0 12007.9    .075       0
   12346      .1       0
#XS Ineff= 2 ,-1
    1580  2173.3   64.26    2175  3244.8   59.32
Permanent Ineff=
       F       F
Bank Sta=3713.7,11659.5
XS Rating Curve= 0 ,0
Exp/Cntr=0.3,0.1

Type RM Length L Ch R = 1 ,45000   ,1000,1000,1000
BEGIN DESCRIPTION:
WFSJ Main 45.0
END DESCRIPTION:
XS GIS Cut Line= 3
      3949376.45     10008332.24      3945874.03     10006992.82
       3938742.8     10005066.19
#Sta/Elev= 30
  1250.2   63.97  2052.9   63.38  2223.8   62.37  2243.2   64.21  2288.6   63.54
  2462.4    62.6  2497.6    62.3  2607.2   59.84  2697.3   53.88  2746.7   52.11
    2867   46.85  2993.8   45.73  3001.2   45.31  3006.5   42.21  3015.2   41.73
  4997.4   41.23 11545.8   41.73 11580.5   46.01 11718.7    51.9 11749.8   52.84
 11769.6   55.38 11774.8   54.36 11801.6   57.53 11832.7   57.38 11889.3    54.7
 11963.9   58.53   12102   59.48 12257.4   60.89 12312.5    64.1 12386.9   63.38
#Mann= 8 ,-1 , 0
  1250.2     .12       0  2052.9     .05       0  2288.6     .12       0
  2462.4     .05       0  2497.6     .05       0  2697.3     .03       0
 11832.7     .05       0   12102      .1       0
Bank Sta=2746.7,11718.7
XS Rating Curve= 0 ,0
Exp/Cntr=0.3,0.1

Type RM Length L Ch R = 1 ,44000   ,1000,1000,1000
BEGIN DESCRIPTION:
WFSJ Main 44.0
END DESCRIPTION:
XS GIS Cut Line= 3
      3949691.14     10006314.02      3945735.39     10006002.48
      3938742.84     10004979.39
#Sta/Elev= 30
    1032   65.26  1058.7   64.27  1125.6   64.01  1145.6   62.15  1175.7   64.28
  1235.9   62.57  1717.4   59.81  1895.2   55.01  1948.1   54.43  1998.3   51.86
  2188.9   50.21  2259.1   46.43  2319.3   45.36  2339.3   41.73  4997.4   41.23
 11111.9   41.73 11132.1   45.04 11303.9   47.43 11425.2   52.09 11469.5   53.85
 11516.2   52.78 11534.3   55.18 11539.4   53.29 11556.6    55.8 11586.9   56.49
   11688   54.74 11878.8   59.33 11970.2   60.71 11984.3   61.47   12067   60.97
#Mann= 7 ,-1 , 0
    1032      .1       0  1058.7     .05       0  1895.2     .03       0
 11539.4     .05       0 11878.8      .1       0 11970.2    .075       0
 11984.3      .1       0
Bank Sta=1998.3,11425.2
XS Rating Curve= 0 ,0
Exp/Cntr=0.3,0.1

Type RM Length L Ch R = 1 ,43000   ,1000,1000,1000
BEGIN DESCRIPTION:
WFSJ Main 43.0
END DESCRIPTION:
XS GIS Cut Line= 3
      3949691.12     10005120.45      3945596.76     10005012.13
       3938440.9     10004751.59
#Sta/Elev= 30
   904.2   63.85   957.5   61.51   987.5   64.13  1017.5    62.2  1667.7   62.14
  1858.1   58.81  1887.8   57.86  2037.9   56.35  2137.9   52.64  2153.7   52.29
  2203.5   49.57    2348   48.35    2438   41.73  4997.4   41.23 10712.7   41.73
 10722.7   42.65 10732.7   46.81 10802.7   52.54 10882.8   55.07 11042.9    54.4
   11183    49.4 11363.1   53.51 11393.1   52.05 11443.2   56.07 11493.2   56.64
 11683.3   59.52 11773.4   58.02 11853.4    61.2 12068.5   61.96 12160.6    63.5
#Mann= 7 ,-1 , 0
   904.2     .05       0  1858.1     .12       0  1887.8     .05       0
  2153.7     .03       0 11493.2     .05       0 11683.3    .075       0
 12068.5     .12       0
#XS Ineff= 2 , 0
                        10881.82           55.09
Permanent Ineff=
       F       F
Bank Sta=2137.9,10802.7
XS Rating Curve= 0 ,0
Exp/Cntr=0.3,0.1

Type RM Length L Ch R = 1 ,42000   ,1000,1000,1000
BEGIN DESCRIPTION:
WFSJ Main 42.0
END DESCRIPTION:
XS GIS Cut Line= 3
      3949756.26     10003666.45      3945458.12     10004021.79
      3938287.08     10004306.64
#Sta/Elev= 30
   687.2   62.13    1063   62.02  1162.2   62.29  1360.7   62.05  1638.8   60.37
    1699   57.21  2080.3   61.75  2311.1   57.68  2384.1   53.54  2461.6   47.25
  2491.7   41.73  2551.9   41.82    2562   45.49    2582   45.68  2612.2   41.73
  4997.4   41.23    9794   41.73  9824.1   49.65  9874.1   53.69 10054.3   59.43
 10214.4   59.67 10434.6    61.5   10638   57.13 10938.6   55.03 11061.4    53.4
 11296.3   55.57 11456.8   56.47 11654.4    56.1 12092.4    61.1 12176.7   62.46
#Mann= 14 ,-1 , 0
   687.2      .1       0    1063     .05       0  1162.2     .12       0
  1360.7     .05       0  2311.1     .03       0 10054.3     .05       0
 10214.4     .05       0   10638      .1       0 10938.6     .12       0
 11061.4    .075       0 11296.3      .1       0 11456.8    .075       0
 11654.4     .05       0 12092.4     .12       0
#XS Ineff= 2 , 0
                        10444.32           61.52
Permanent Ineff=
       F       F
Bank Sta=2384.1,9874.1
XS Rating Curve= 0 ,0
Exp/Cntr=0.3,0.1

Type RM Length L Ch R = 1 ,41000   ,707,707,707
BEGIN DESCRIPTION:
WFSJ Main 41.0
END DESCRIPTION:
XS GIS Cut Line= 3
      3949918.97     10002982.86      3945321.42     10003031.19
      3938092.28      10003883.4
#Sta/Elev= 30
   402.2   64.12   715.5    64.4   743.3   68.12   773.3   63.09   814.1   62.99
   916.7   63.79  1110.1   63.38  1208.7   62.34  1307.4   62.18    1406   62.85
  1633.4    60.9  1893.4   57.05  1923.4   53.33  2073.4   41.73  4997.4   41.23
  9957.7   41.73  9987.9   49.34 10048.3   53.48 10350.4   53.98   10582   57.06
 10641.5    54.1 10766.4   51.61 10843.8    47.2 10854.4   43.67   10884   47.87
 10940.7    48.7 11040.4   50.69 11382.5   51.46 11729.9   57.76 12279.2   61.53
#Mann= 16 ,-1 , 0
   402.2      .1       0   715.5     .12       0   814.1      .1       0
   916.7     .12       0  1110.1      .1       0  1208.7     .12       0
  1307.4     .05       0    1406      .1       0  1633.4     .05       0
  1923.4     .03       0 10350.4     .05       0   10582    .075       0
 10641.5     .05       0 10940.7    .075       0 11040.4     .05       0
 11382.5     .05       0
#XS Ineff= 2 , 0
                        10571.59           57.61
Permanent Ineff=
       F       F
Bank Sta=1923.4,10048.3
XS Rating Curve= 0 ,0
Exp/Cntr=0.3,0.1

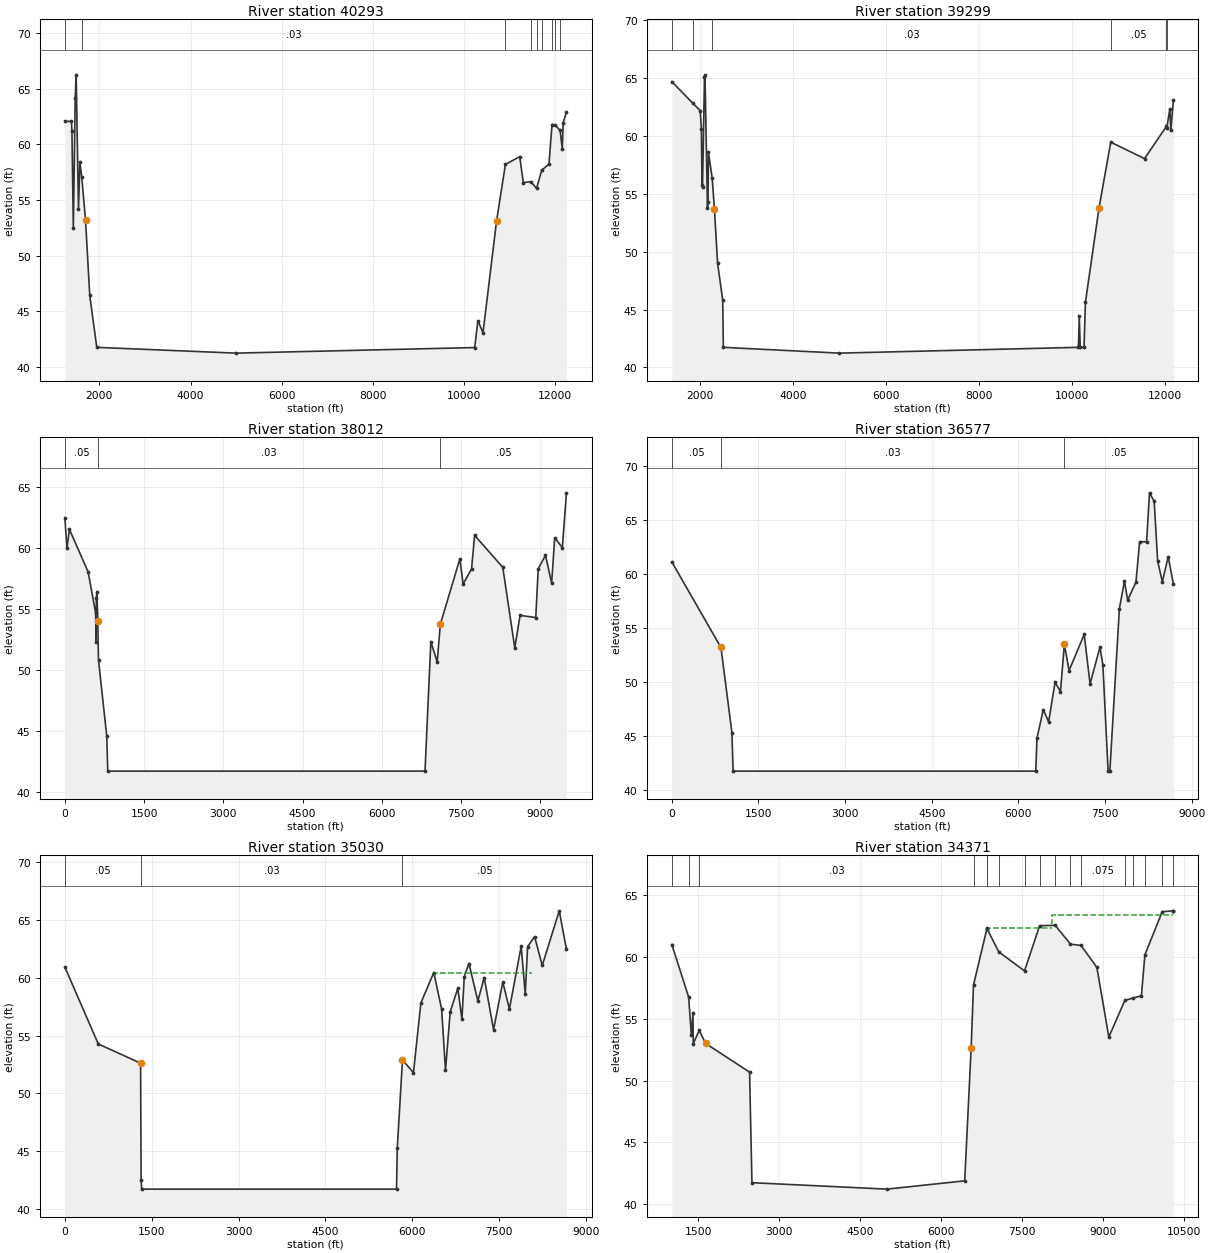
Type RM Length L Ch R = 1 ,40293   ,994,994,994
BEGIN DESCRIPTION:
WFSJ Main 40.0
END DESCRIPTION:
XS GIS Cut Line= 3
      3948888.19     10001474.61      3945426.82     10002310.12
       3938026.7     10003047.96
#Sta/Elev= 30
  1244.9   62.07  1389.3   62.05  1399.6    61.2  1430.4   52.48  1471.6   64.12
  1492.1   66.24  1543.6   54.17  1574.4   58.41  1615.6   57.03  1697.9   53.19
  1790.5   46.41  1944.8   41.75  4997.4   41.23 10231.4   41.73 10301.8   44.14
 10413.3   43.06 10710.2    53.1 10904.7   58.19 11218.4   58.89 11296.7   56.56
 11463.5   56.64 11587.3   56.03 11700.8   57.67 11859.5   58.22 11926.9   61.77
   11987   61.75 12104.3   61.25 12150.9   59.58   12171   61.94 12242.5   62.89
#Mann= 9 ,-1 , 0
  1244.9     .05       0  1615.6     .03       0 10904.7     .05       0
 11463.5    .075       0 11587.3     .05       0 11700.8    .075       0
 11926.9     .05       0   11987    .075       0 12104.3     .05       0
Bank Sta=1697.9,10710.2
XS Rating Curve= 0 ,0
Exp/Cntr=0.3,0.1

Type RM Length L Ch R = 1 ,39299   ,1287,1287,1287
BEGIN DESCRIPTION:
WFSJ Main 39.0
END DESCRIPTION:
XS GIS Cut Line= 4
      3948736.28     10000704.22      3947683.76     10001094.84
      3944569.62     10001398.66      3938092.33     10002288.34
#Sta/Elev= 30
  1391.9   64.69  1843.9   62.82  2002.2   62.19  2027.2    60.6  2040.9    55.8
  2051.5   55.57  2094.2   65.07  2104.9   65.28  2158.2   53.77  2168.4   54.31
  2179.5   58.57  2259.5   56.36  2307.5   53.71  2375.6   49.01  2486.5    45.8
  2499.5   41.73  4997.4   41.23 10137.1   41.73 10157.2   44.42 10176.6   41.73
 10258.7   41.73 10288.5   45.61 10581.2   53.78 10833.5   59.46 11560.3   58.04
 12030.5   60.82 12040.4   60.71 12105.4   62.35 12125.6    60.5 12181.6   63.09
#Mann= 6 ,-1 , 0
  1391.9     .05       0  1843.9     .05       0  2259.5     .03       0
 10833.5     .05       0 12030.5    .075       0 12040.4     .05       0
Bank Sta=2307.5,10581.2
XS Rating Curve= 0 ,0
Exp/Cntr=0.3,0.1

Type RM Length L Ch R = 1 ,38012   ,1435,1435,1435
XS GIS Cut Line= 5
      3946550.51       9999944.9      3946097.49     10000076.27
      3943202.43     10000856.12      3938972.57     10001030.91
      3937440.23     10000101.27
#Sta/Elev= 30
       0   62.45    39.7   59.99    86.1   61.52   440.2   58.04   583.1   54.66
   588.3   52.31   595.6   55.89   605.9   56.41   623.1   53.98     637   50.79
   792.4   44.63   812.4   41.73  6817.4   41.73  6927.5   52.32  7047.6   50.67
  7107.6   53.76  7477.9   59.11    7538   57.04  7698.1   58.28  7756.4   61.03
  8289.5   58.41    8516   51.82  8617.1   54.48  8913.8    54.3  8960.2   58.29
  9097.9    59.4  9214.2   57.12  9272.4   60.83  9416.6   60.03  9494.2   64.51
#Mann= 3 , 0 , 0
       0     .05       0   623.1     .03       0  7107.6     .05       0
Bank Sta=623.1,7107.6
XS Rating Curve= 0 ,0
Exp/Cntr=0.3,0.1

Type RM Length L Ch R = 1 ,36577   ,1547,1547,1547
XS GIS Cut Line= 4
      3946421.28      9999955.74      3945965.57      9999879.14
      3942334.37      9999847.01      3937787.93      9999217.67
#Sta/Elev= 30
       0   61.09   849.8   53.18  1039.8    45.3  1059.8   41.73  6300.8   41.73
    6321   44.78  6430.5   47.42  6522.9   46.29    6634   49.95  6727.8    49.1
 6795.45   53.47  6876.5   51.04  7138.7   54.38  7240.5    49.8  7411.3    53.2
  7461.8   51.59  7552.6   41.73  7582.9   41.73  7748.1   56.78  7835.3   59.31
  7891.7   57.55  8035.3   59.23  8097.8   62.97  8218.9   62.95  8269.4   67.49
  8350.2   66.71  8410.7   61.16  8491.5   59.25  8592.5   61.58  8683.2   59.04
#Mann= 3 , 0 , 0
       0     .05       0   849.8     .03       0 6795.45     .05       0
#XS Ineff= 1 ,-1
  7138.7    7890   54.38
Permanent Ineff=
       F
Bank Sta=849.8,6795.45
XS Rating Curve= 0 ,0
Exp/Cntr=0.3,0.1

Type RM Length L Ch R = 1 ,35030   ,659,659,659
XS GIS Cut Line= 5
      3946373.53      9999934.04      3945994.53      9999787.74
      3942417.27      9998366.54      3940869.53      9997503.26
      3938265.36      9997080.08
#Sta/Elev= 30
       0   60.91   576.8   54.27  1308.2   52.61  1317.3   42.53  1327.2   41.73
  5730.4   41.73  5743.4   45.27  5833.2   52.89  6022.9   51.79    6151   57.81
  6373.9   60.44  6509.8   57.28  6576.5   51.99  6657.5   57.04  6789.2   59.08
  6860.2    56.4  6900.7   60.09  6981.7   61.22  7135.6   57.99  7245.2      60
  7407.2    55.5  7566.5   59.62  7680.8   57.29  7884.5   62.71  7954.3   58.59
  7994.9   62.67  8116.4   63.54  8248.1   61.05  8541.9   65.77    8666   62.46
#Mann= 3 , 0 , 0
       0     .05       0  1308.2     .03       0  5833.2     .05       0
#XS Ineff= 1 ,-1
  6386.7    8075   60.44
Permanent Ineff=
       F
Bank Sta=1308.2,5833.2
XS Rating Curve= 0 ,0
Exp/Cntr=0.3,0.1

Type RM Length L Ch R = 1 ,34371   ,216,216,216
BEGIN DESCRIPTION:
WFSJ Main 35.0
END DESCRIPTION:
XS GIS Cut Line= 4
      3946317.65      9999876.71      3942801.99      9997802.04
      3940519.01      9996552.04      3937918.18      9996244.58
#Sta/Elev= 30
    1007   60.99  1318.8   56.74  1367.5   53.71  1398.8   55.47  1404.6   52.99
  1515.9   54.05  1632.9      53  2448.5   50.68    2493   41.75  4997.4   41.23
  6439.6    41.9    6559   52.63  6602.7   57.72    6853    62.3  6853.9   62.26
  7072.6   60.39    7549   58.86  7829.5   62.51  8117.9   62.54  8401.6   61.02
    8598   60.91  8891.4   59.14  9112.9   53.52    9411   56.48  9566.8   56.67
  9717.1   56.85  9782.1   60.16   10103   63.64 10300.7   63.71 10310.9   63.67
#Mann= 17 ,-1 , 0
    1007     .12       0  1318.8     .05       0  1515.9     .03       0
  6602.7     .05       0    6853     .05       0  6853.9    .075       0
  7072.6     .05       0    7549     .05       0  7829.5     .05       0
  8117.9     .12       0  8401.6     .05       0    8598    .075       0
    9411     .05       0  9566.8    .075       0  9782.1     .05       0
   10103    .075       0 10300.7     .05       0
#XS Ineff= 2 ,-1
  6883.8    8055   62.31  8055.6   10310   63.34
Permanent Ineff=
       F       F
Bank Sta=1632.9,6559
XS Rating Curve= 0 ,0
Exp/Cntr=0.3,0.1