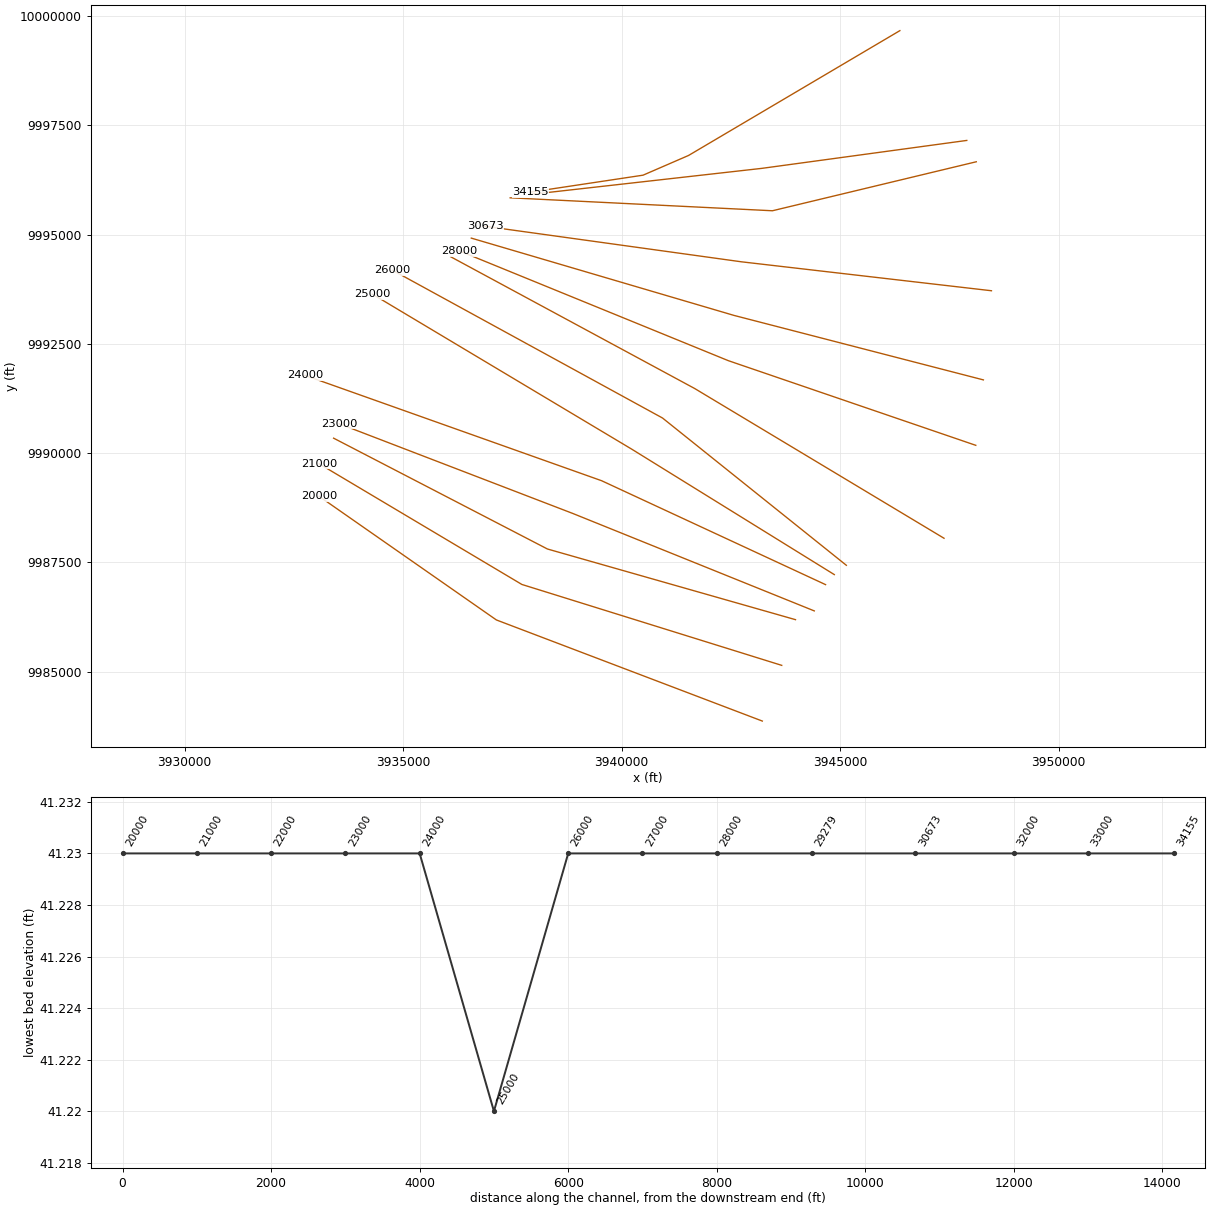
HEC-RAS study WFSJ Main.prj: WFSJ Main Base Level Engineering

--- WFSJ Main.g02 (geometry) --- (continued)

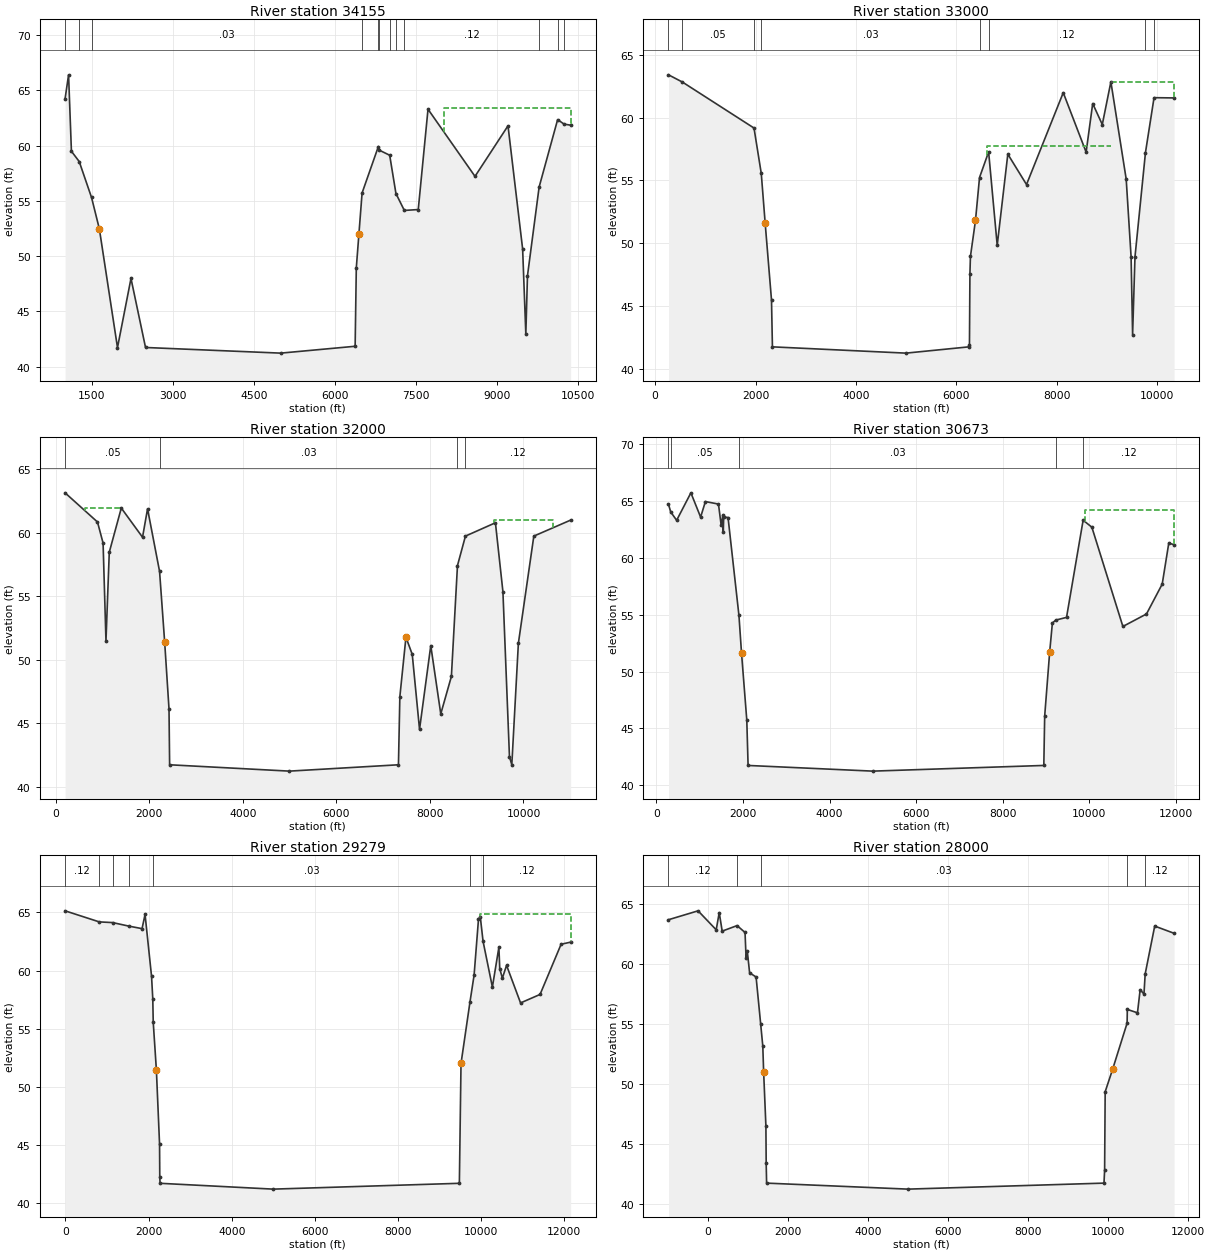
Type RM Length L Ch R = 1 ,34155   ,1155,1155,1155
BEGIN DESCRIPTION:
WFSJ Main 34.0
END DESCRIPTION:
XS GIS Cut Line= 4
       3946369.7      9999668.36      3941534.63      9996812.46
      3940492.97      9996361.07      3937918.18      9995973.32
#Sta/Elev= 30
  1006.5   64.22  1071.3   66.39    1124   59.48  1268.3   58.55  1496.4    55.3
  1640.9   52.46  1976.5   41.73  2226.2   47.98  2495.3   41.74  4997.4   41.23
  6373.8   41.85  6395.2   48.93  6444.1   52.03  6502.4   55.71  6803.8   59.91
  6811.4    59.6  7013.1   59.12  7128.6   55.66  7284.1   54.13  7541.5   54.21
  7722.1   63.28  8591.7   57.21  9202.3   61.78  9473.1   50.64    9532   42.96
  9562.5   48.22  9778.3   56.25 10120.4   62.34 10241.4   61.93 10361.1   61.84
#Mann= 12 ,-1 , 0
  1006.5      .1       0  1268.3     .05       0  1496.4     .03       0
  6502.4     .05       0  6803.8      .1       0  6811.4     .05       0
  7013.1      .1       0  7128.6     .05       0  7284.1     .12       0
  9778.3     .05       0 10120.4     .12       0 10241.4     .05       0
#XS Ineff= 2 ,-1
  6803.8    8024   59.91  8025.4   10361   63.39
Permanent Ineff=
       F       F
Bank Sta=1640.9,6444.1
XS Rating Curve= 0 ,0
Exp/Cntr=0.3,0.1

Type RM Length L Ch R = 1 ,33000   ,1000,1000,1000
BEGIN DESCRIPTION:
WFSJ Main 33.0
END DESCRIPTION:
XS GIS Cut Line= 3
      3947900.75      9997156.03      3943210.99      9996516.93
      3937907.29      9995919.06
#Sta/Elev= 30
   266.9    63.4   545.7   62.82  1970.2   59.16  2114.9   55.54  2192.3   51.59
  2318.6   45.46    2337   41.73  4997.4   41.23    6251   41.73  6261.8   41.85
  6271.1   47.56  6281.2   48.93 6381.82    51.8  6462.3   55.22  6643.5   57.26
  6814.6   49.82  7025.9   57.08  7398.2   54.66    8130   61.98  8585.7   57.24
  8716.5   61.11  8907.7   59.44  9078.8   62.84  9383.9   55.09  9481.3    48.9
  9511.5   42.71  9558.7   48.89  9767.8   57.21  9938.5   61.58 10337.3   61.56
#Mann= 8 ,-1 , 0
   266.9     .12       0   545.7     .05       0  1970.2     .05       0
  2114.9     .03       0  6462.3     .05       0  6643.5     .12       0
  9767.8     .05       0  9938.5     .12       0
#XS Ineff= 2 ,-1
  6616.4    9077    57.7  9078.8   10400   62.84
Permanent Ineff=
       F       F
Bank Sta=2192.3,6381.82
XS Rating Curve= 0 ,0
Exp/Cntr=0.3,0.1

Type RM Length L Ch R = 1 ,32000   ,1327,1327,1327
BEGIN DESCRIPTION:
WFSJ Main 32.0
END DESCRIPTION:
XS GIS Cut Line= 3
      3948117.83      9996667.76      3943453.25      9995546.72
      3937452.17      9995843.07
#Sta/Elev= 30
   202.6   63.16   895.7   60.86  1015.1    59.2  1076.8   51.49  1147.5   58.48
  1404.4   61.96  1858.4   59.66  1965.4    61.9  2222.3   56.97 2331.3551.40046
  2424.1   46.13  2437.3   41.73  4997.4   41.23  7328.2   41.73  7358.3    47.1
  7488.4   51.78  7623.1   50.43  7778.8   44.52  8019.1   51.12  8232.6   45.74
  8459.6   48.69  8589.8   57.43    8760   59.75  9400.8    60.8    9561   55.38
  9701.1   42.36  9751.2   41.73  9891.4    51.3 10221.8   59.75 11008.4   61.01
#Mann= 4 ,-1 , 0
   202.6     .05       0  2222.3     .03       0  8589.8     .05       0
    8760     .12       0
#XS Ineff= 2 ,-1
     630  1404.4   61.96  9380.7   10640   61.01
Permanent Ineff=
       F       F
Bank Sta=2331.35,7488.4
XS Rating Curve= 0 ,0
Exp/Cntr=0.3,0.1

Type RM Length L Ch R = 1 ,30673   ,1394,1394,1394
BEGIN DESCRIPTION:
WFSJ Main 31.0
END DESCRIPTION:
XS GIS Cut Line= 3
      3948464.99      9993716.37       3942746.7      9994378.26
      3936876.51      9995192.06
#Sta/Elev= 30
   278.6   64.72   330.6   64.05     467   63.32     796   65.74  1020.7    63.6
  1131.4   64.97  1433.4   64.75  1496.2   62.87  1534.1   63.77  1544.1   62.28
  1554.2   63.62  1654.9   63.56  1906.5   54.94  1966.9   51.59  2087.7   45.73
  2117.9   41.73  4997.4   41.23  8951.5   41.73  8971.7   46.08 9087.44   51.74
  9149.5   54.27  9226.3   54.53  9476.5   54.77  9860.2   63.33 10062.1   62.71
 10778.9   53.97   11324   55.07 11687.5    57.7 11838.9    61.3 11961.4   61.18
#Mann= 5 ,-1 , 0
   278.6      .1       0   330.6     .05       0  1906.5     .03       0
  9226.3     .05       0  9860.2     .12       0
#XS Ineff= 2 , 0
                            9900           64.21
Permanent Ineff=
       F       F
Bank Sta=1966.9,9087.44
XS Rating Curve= 0 ,0
Exp/Cntr=0.3,0.1

Type RM Length L Ch R = 1 ,29279   ,1279,1279,1279
BEGIN DESCRIPTION:
WFSJ Main 29.0
END DESCRIPTION:
XS GIS Cut Line= 3
       3948280.6      9991676.42      3942573.09      9993152.13
      3936562.36      9994920.63
#Sta/Elev= 30
    -8.9   65.13     813   64.18  1135.5   64.12  1520.5   63.82  1842.8    63.6
  1915.1   64.82  2071.1   59.51    2101   57.57  2111.7   55.57  2187.8   51.45
  2263.9   45.09  2269.1   42.23  2276.6   41.73  4997.4   41.23  9475.4   41.73
 9515.11   52.02  9729.7   57.28  9829.8   59.61    9935   64.39  9978.8   64.61
 10045.5   62.51 10269.8   58.58 10426.1      62   10447   60.15 10510.3   59.35
 10610.4   60.45 10947.3   57.22 11416.4   57.95 11922.5   62.26 12151.8   62.44
#Mann= 7 ,-1 , 0
    -8.9     .12       0     813      .1       0  1135.5     .12       0
  1520.5     .05       0  2111.7     .03       0  9729.7     .05       0
 10045.5     .12       0
#XS Ineff= 2 , 0
                         9963.64           64.82
Permanent Ineff=
       F       F
Bank Sta=2187.8,9515.11
XS Rating Curve= 0 ,0
Exp/Cntr=0.3,0.1

Type RM Length L Ch R = 1 ,28000   ,1000,1000,1000
BEGIN DESCRIPTION:
WFSJ Main 28.0
END DESCRIPTION:
XS GIS Cut Line= 3
      3948106.91      9990179.05      3942445.03      9992115.91
      3936291.72      9994627.34
#Sta/Elev= 30
    -984   63.66  -245.2    64.4   207.9   62.82   283.3   64.25   357.3   62.71
   729.6   63.17     928    62.6   953.8   60.51   985.1   61.02  1042.4   59.24
  1204.2   58.89  1318.9   54.97  1371.9   53.13    1393   50.97  1449.3   46.49
  1456.4   43.38    1467   41.73  4997.4   41.23  9895.6   41.73  9911.3   42.81
  9925.1   49.34 10109.5   51.19   10473   55.05 10478.4   56.19 10732.2   55.91
 10799.2   57.84 10894.2   57.47 10924.7   59.15 11162.6   63.13 11646.1   62.53
#Mann= 5 ,-1 , 0
    -984     .12       0   729.6     .05       0  1318.9     .03       0
   10473     .05       0 10924.7     .12       0
Bank Sta=1393,10109.5
XS Rating Curve= 0 ,0
Exp/Cntr=0.3,0.1

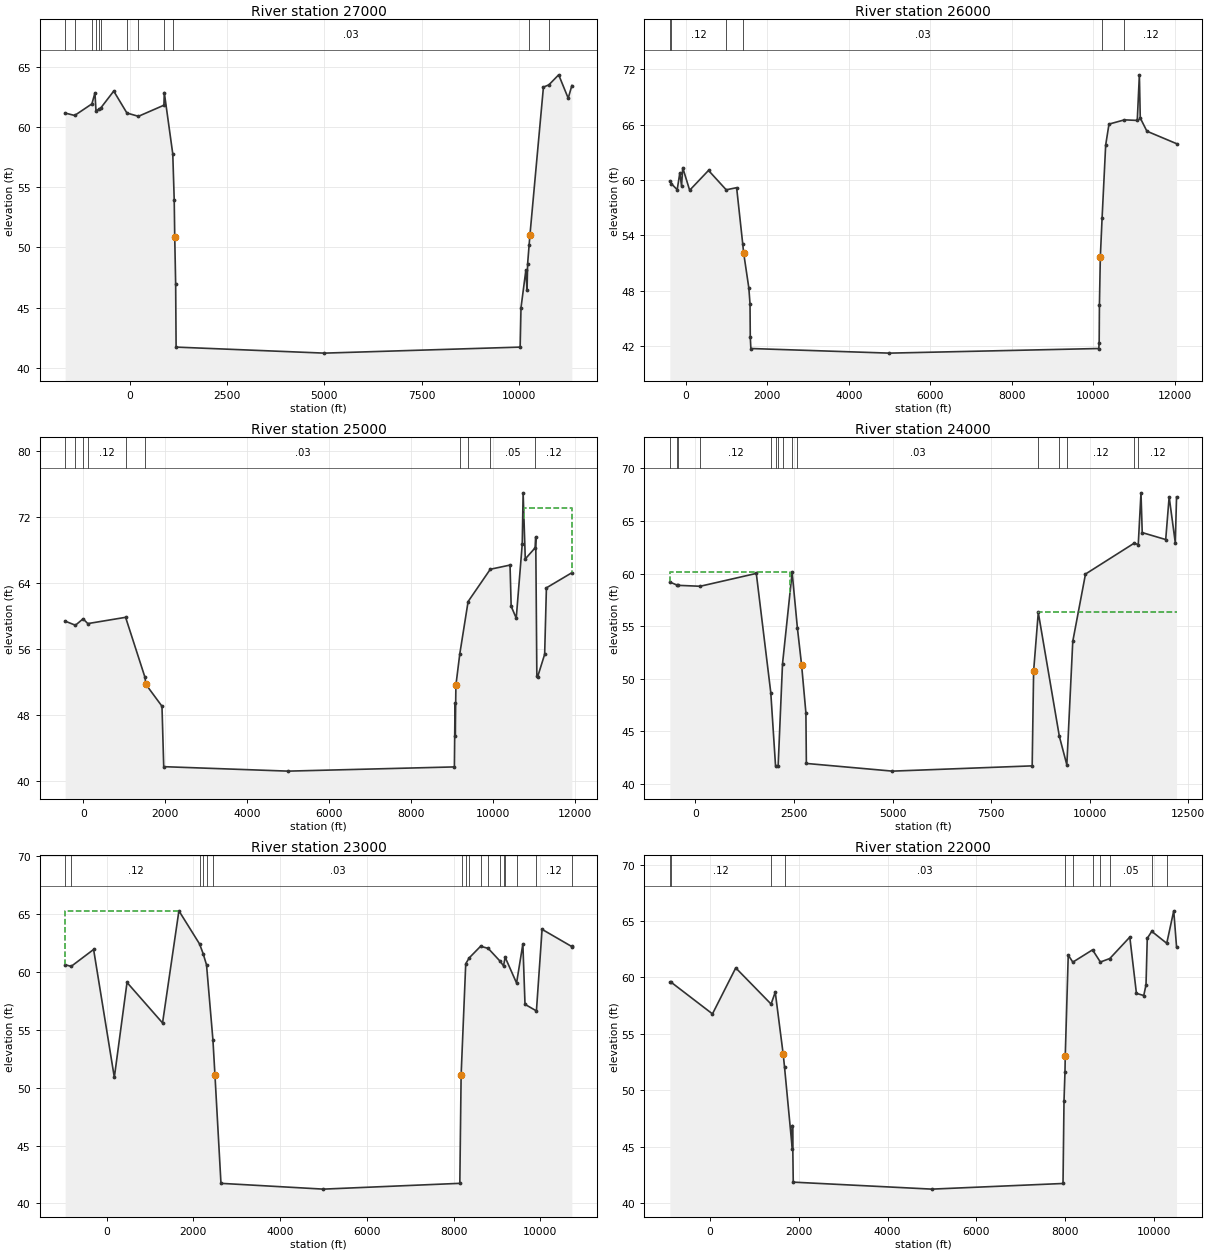
Type RM Length L Ch R = 1 ,27000   ,1000,1000,1000
BEGIN DESCRIPTION:
WFSJ Main 27.0
END DESCRIPTION:
XS GIS Cut Line= 3
      3947379.92      9988052.32      3941673.97      9991479.15
      3936085.81      9994496.84
#Sta/Elev= 30
 -1655.9   61.14 -1411.1   60.94  -968.7    61.9  -890.3   62.81  -863.7   61.32
  -788.9   61.46  -746.1   61.54  -408.4   62.96   -69.5   61.14   226.1   60.87
     880   61.79   889.4   62.84  1107.3   57.75  1144.3   53.93  1157.7   50.83
  1181.1   46.97  1192.8   41.73  4997.4   41.23   10024   41.73 10045.9      45
 10171.5   48.13 10200.7   46.44 10215.3   48.62 10253.4   50.17 10275.3   51.03
 10621.2   63.29 10761.6   63.48 11012.9   64.31 11257.7   62.37 11350.9   63.42
#Mann= 12 ,-1 , 0
 -1655.9      .1       0 -1411.1     .12       0  -968.7     .05       0
  -863.7     .12       0  -788.9     .05       0  -746.1     .12       0
   -69.5      .1       0   226.1     .12       0   889.4     .05       0
  1107.3     .03       0 10253.4     .05       0 10761.6     .12       0
Bank Sta=1157.7,10275.3
XS Rating Curve= 0 ,0
Exp/Cntr=0.3,0.1

Type RM Length L Ch R = 1 ,26000   ,1000,1000,1000
BEGIN DESCRIPTION:
WFSJ Main 26.0
END DESCRIPTION:
XS GIS Cut Line= 3
      3945144.73      9987433.79      3940938.67      9990803.63
      3934762.71      9994183.89
#Sta/Elev= 30
  -389.5   59.88  -351.7   59.59  -208.8   58.94  -144.8   60.75  -101.6   59.35
   -73.2   61.33    96.9   58.88   559.4   61.03   993.2   58.93  1249.3   59.16
  1399.7   53.03  1420.5   52.11  1548.6   48.29  1577.4   46.57  1583.8   42.98
  1598.2   41.73  4997.4   41.23 10132.7   41.73 10142.3   42.37 10148.8   46.48
 10170.6   51.62 10214.3   55.91 10301.9   63.78 10383.1   66.05 10762.8   66.51
   11077   66.45 11128.5   71.39 11150.3   66.71 11313.4   65.28 12040.5   63.93
#Mann= 6 ,-1 , 0
  -389.5     .05       0  -351.7     .12       0   993.2     .05       0
  1399.7     .03       0 10214.3     .05       0 10762.8     .12       0
Bank Sta=1420.5,10170.6
XS Rating Curve= 0 ,0
Exp/Cntr=0.3,0.1

Type RM Length L Ch R = 1 ,25000   ,1000,1000,1000
BEGIN DESCRIPTION:
WFSJ Main 25.0
END DESCRIPTION:
XS GIS Cut Line= 3
      3944869.39      9987220.72      3940242.06      9990086.18
      3934303.51      9993636.49
#Sta/Elev= 30
  -442.7   59.39    -191   58.89    -4.4   59.67   110.3   59.09  1032.6   59.85
  1505.3   52.58  1526.6   51.73  1920.1   49.08  1962.6   41.76  4997.4   41.22
  9053.4   41.73    9069   49.43  9074.8   45.46  9090.4   51.63  9185.7   55.44
    9388   61.76  9928.7   65.67 10410.9   66.18 10438.5   61.19 10562.3   59.75
 10708.9   68.73 10730.3   74.93 10782.8   66.92 11023.3   68.27 11037.7   69.59
 11064.9    52.8 11086.6   52.68 11255.5   55.37 11298.3   63.42 11918.9   65.25
#Mann= 10 ,-1 , 0
  -442.7      .1       0    -191     .12       0    -4.4      .1       0
   110.3     .12       0  1032.6     .05       0  1505.3     .03       0
  9185.7     .05       0    9388     .12       0  9928.7     .05       0
 11023.3     .12       0
#XS Ineff= 2 , 0
                        10751.14           73.08
Permanent Ineff=
       F       F
Bank Sta=1526.6,9090.4
XS Rating Curve= 0 ,0
Exp/Cntr=0.3,0.1

Type RM Length L Ch R = 1 ,24000   ,1000,1000,1000
BEGIN DESCRIPTION:
WFSJ Main 24.0
END DESCRIPTION:
XS GIS Cut Line= 3
      3944668.93      9986991.53      3939545.46      9989368.73
      3932757.42      9991779.43
#Sta/Elev= 30
  -648.1    59.2  -464.1   58.91  -453.3   58.89   121.5    58.8    1545   60.02
  1912.1    48.7  2032.9   41.73  2098.9   41.73  2209.5   51.41  2453.9   60.11
  2586.9   54.85  2693.9   51.31    2803   46.76  2814.6   41.96  4997.4   41.23
  8541.8   41.73  8578.4   50.74  8696.5   56.31  9230.7   44.54  9420.6   41.83
  9571.2   53.56  9893.7   59.96   11127   62.89   11232   62.76 11301.6   67.68
 11332.8    63.9 11928.4   63.24 12015.7    67.3 12171.1   62.94 12203.4    67.3
#Mann= 15 ,-1 , 0
  -648.1      .1       0  -464.1     .12       0  -453.3      .1       0
   121.5     .12       0  1912.1      .1       0  2032.9     .12       0
  2098.9     .05       0  2209.5     .12       0  2453.9     .05       0
  2586.9     .03       0  8696.5     .05       0  9230.7     .05       0
  9420.6     .12       0   11127     .05       0   11232     .12       0
#XS Ineff= 2 , 0
            2400   60.18    8700           56.34
Permanent Ineff=
       F       F
Bank Sta=2693.9,8578.4
XS Rating Curve= 0 ,0
Exp/Cntr=0.3,0.1

Type RM Length L Ch R = 1 ,23000   ,1000,1000,1000
BEGIN DESCRIPTION:
WFSJ Main 23.0
END DESCRIPTION:
XS GIS Cut Line= 3
      3944411.07      9986389.98      3938887.53      9988618.89
      3933541.41      9990671.99
#Sta/Elev= 30
  -956.3   60.62  -816.5   60.48  -299.6   61.94   178.2   50.89   470.6   59.09
  1290.1   55.59 1667.05   65.28  2144.3   62.41  2226.5   61.57  2303.8   60.61
  2451.6   54.12  2497.9    51.1  2636.8   41.73  4997.4   41.23  8143.9   41.73
 8173.86   51.09  8280.2   60.71  8359.8   61.21  8623.2   62.22  8799.4   62.03
  9074.1   60.92  9151.3   60.52  9188.7   61.27  9452.2   59.04  9597.5   62.42
  9646.8    57.2    9910   56.63 10040.3   63.68 10721.5    62.2 10726.8   62.15
#Mann= 17 ,-1 , 0
  -956.3      .1       0  -816.5     .12       0  2144.3      .1       0
  2226.5     .12       0  2303.8     .05       0  2451.6     .03       0
  8198.5     .05       0  8280.2    .075       0  8359.8     .05       0
  8623.2    .075       0  8799.4     .05       0  9074.1    .075       0
  9151.3     .05       0  9188.7    .075       0  9452.2     .05       0
    9910     .12       0 10721.5     .05       0
#XS Ineff= 2 , 0
         1659.09   65.28
Permanent Ineff=
       F       F
Bank Sta=2497.9,8173.86
XS Rating Curve= 0 ,0
Exp/Cntr=0.3,0.1

Type RM Length L Ch R = 1 ,22000   ,1000,1000,1000
BEGIN DESCRIPTION:
WFSJ Main 22.0
END DESCRIPTION:
XS GIS Cut Line= 3
      3943981.39      9986189.46      3938303.71        9987807.
      3933411.94      9990342.66
#Sta/Elev= 30
  -903.6   59.58  -875.3   59.58    56.7   56.77   581.1   60.85  1377.2   57.64
  1470.8    58.7 1650.26   53.18  1679.7   52.06  1854.1   44.81  1859.3   46.87
  1876.3   41.85  4997.4   41.23  7952.6   41.73  7974.8   49.03  7996.9   51.65
  8002.7      53  8070.3   61.98  8173.9   61.36  8617.5   62.45  8793.9   61.37
  9006.9   61.68    9457   63.58  9606.2   58.59  9771.1    58.4  9821.9   59.34
    9850   63.47  9951.3   64.09 10288.9   63.03 10446.7   65.91 10509.9   62.71
#Mann= 11 ,-1 , 0
  -903.6      .1       0  -875.3     .12       0  1377.2     .05       0
  1679.7     .03       0  7996.9     .05       0  8173.9    .075       0
  8617.5     .05       0  8793.9    .075       0  9006.9     .05       0
  9951.3     .12       0 10288.9     .05       0
Bank Sta=1650.26,8002.7
XS Rating Curve= 0 ,0
Exp/Cntr=0.3,0.1

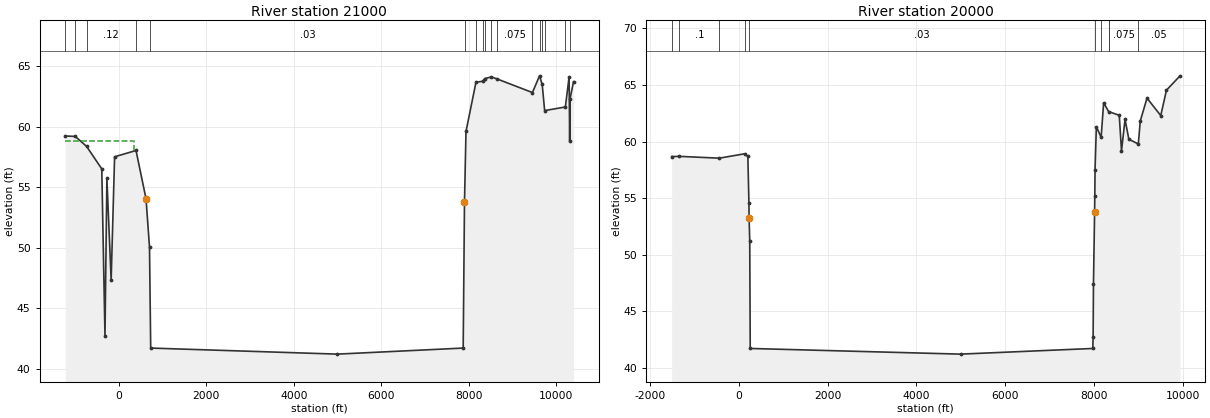
Type RM Length L Ch R = 1 ,21000   ,1000,1000,1000
BEGIN DESCRIPTION:
WFSJ Main 21.0
END DESCRIPTION:
XS GIS Cut Line= 3
      3943666.29      9985143.88       3937719.9      9986995.12
      3933082.24      9989755.52
#Sta/Elev= 30
 -1227.9   59.23  -998.3   59.19    -739   58.37  -391.7   56.51  -318.3   42.76
  -274.9   55.72  -177.3   47.35   -98.4   57.51   391.4   58.03   620.2   54.05
   699.9   50.05   727.2   41.73  4997.4   41.23  7873.5   41.73 7903.41   53.77
  7937.7    59.6  8165.6   63.66  8315.2   63.74  8369.1   63.96  8515.5    64.1
  8642.6   63.94  9457.4   62.81    9619   64.19  9680.2   63.49  9736.4   61.32
 10210.1   61.62 10295.9    64.1   10309   58.81 10317.6    62.3   10397   63.71
#Mann= 17 ,-1 , 0
 -1227.9     .12       0  -998.3      .1       0    -739     .12       0
   391.4     .05       0   699.9     .03       0 7919.32     .05       0
  8165.6    .075       0  8315.2     .05       0  8369.1    .075       0
  8515.5     .05       0  8642.6    .075       0  9457.4     .05       0
    9619    .075       0  9680.2     .05       0  9736.4    .075       0
 10210.1     .05       0 10317.6    .075       0
#XS Ineff= 2 , 0
          341.42   58.84
Permanent Ineff=
       F       F
Bank Sta=620.2,7903.41
XS Rating Curve= 0 ,0
Exp/Cntr=0.3,0.1

Type RM Length L Ch R = 1 ,20000   ,759,759,759
BEGIN DESCRIPTION:
WFSJ Main 20.0
END DESCRIPTION:
XS GIS Cut Line= 3
      3943222.29      9983869.14      3937136.08      9986183.23
       3933082.3      9989010.63
#Sta/Elev= 30
 -1511.3   58.67 -1341.1   58.69  -438.2   58.53   134.9   58.92   205.2   58.68
  229.55   54.54  233.2853.22231   247.7   51.26   258.7   41.73  4997.4   41.23
  7977.7   41.73  7984.9   42.76  7992.6   47.39 8018.31   53.77 8022.73   55.19
  8028.3   57.53    8058   61.31  8165.3   60.37    8222   63.42  8334.4   62.64
  8573.6   62.32  8624.2   59.17  8704.2   61.96  8789.6    60.2  9003.3   59.78
  9047.3   61.81  9199.1   63.83  9508.9   62.29  9637.1   64.53  9942.4    65.8
#Mann= 10 ,-1 , 0
 -1511.3     .12       0 -1341.1      .1       0  -438.2     .12       0
   134.9     .05       0  229.55     .03       0 8022.73     .05       0
  8165.3    .075       0  8334.4      .1       0  8334.4    .075       0
  9003.3     .05       0
Bank Sta=233.28,8018.31
XS Rating Curve= 0 ,0
Exp/Cntr=0.3,0.1