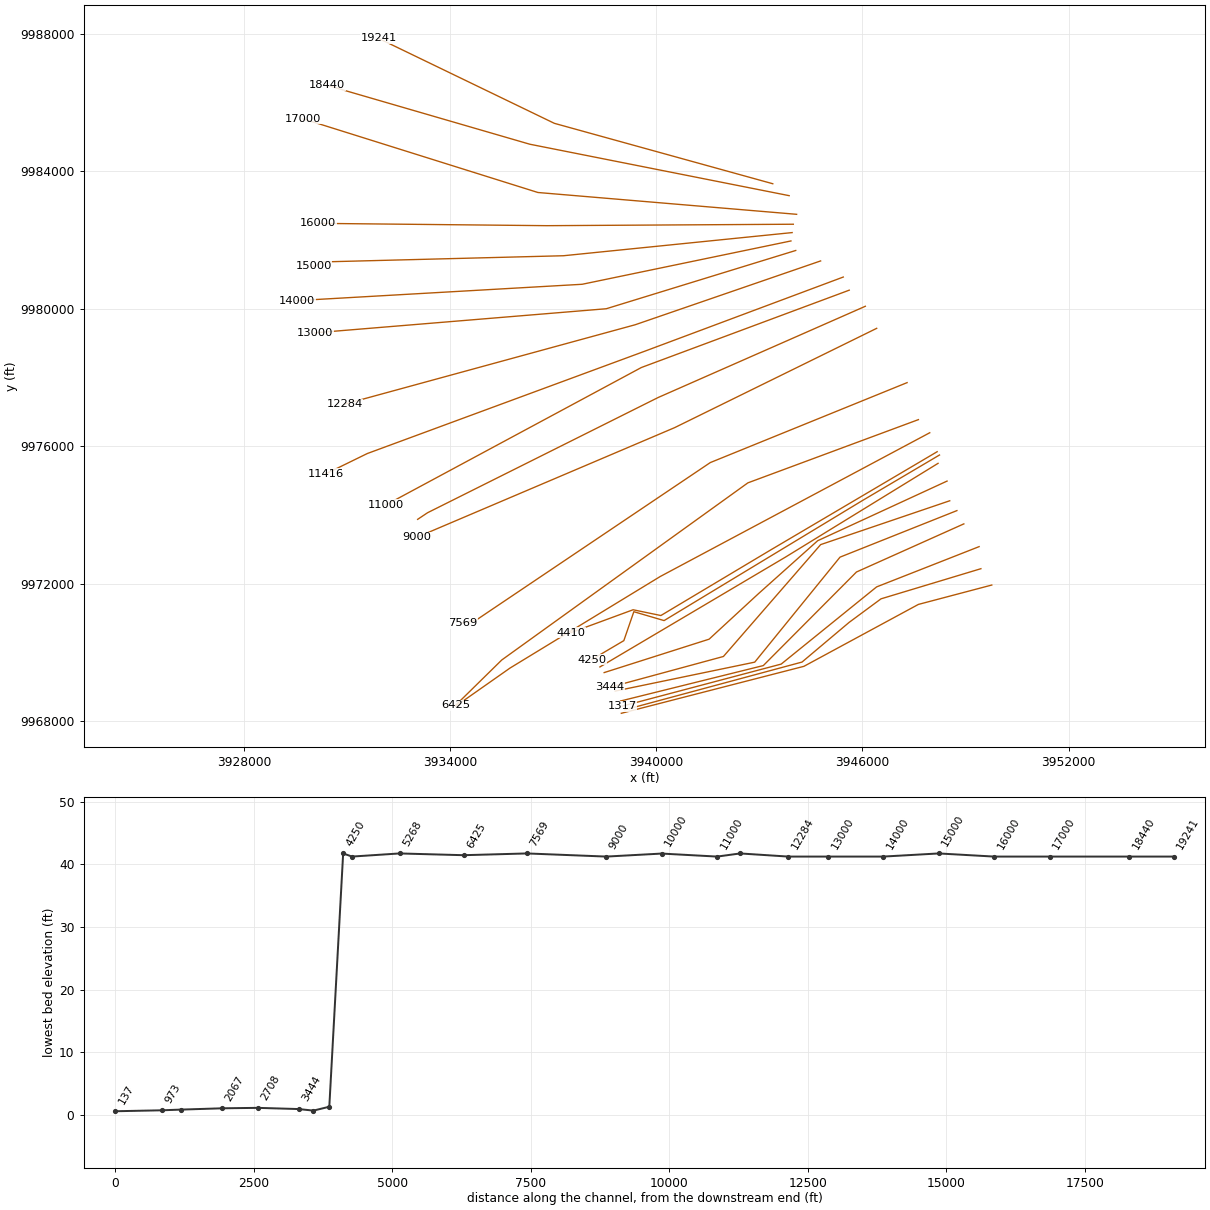
HEC-RAS study WFSJ Main.prj: WFSJ Main Base Level Engineering

--- WFSJ Main.g02 (geometry) --- (continued)

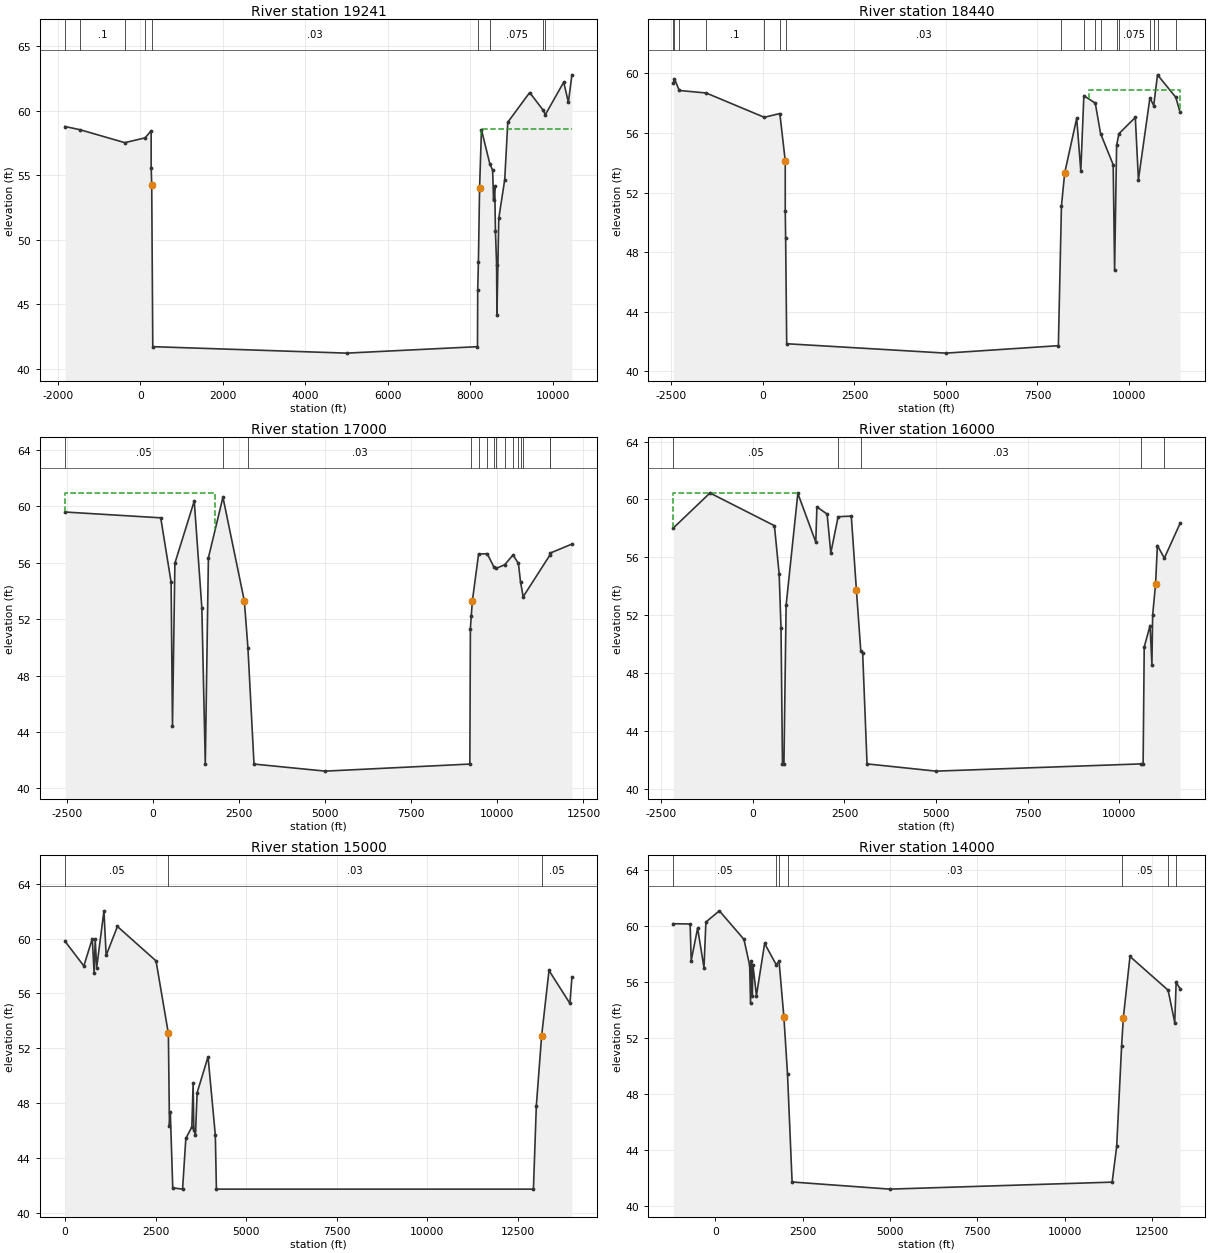
Type RM Length L Ch R = 1 ,19241   ,801,801,801
BEGIN DESCRIPTION:
WFSJ Main 19.0
END DESCRIPTION:
XS GIS Cut Line= 3
      3943390.71      9983639.97      3937032.19      9985397.78
      3931911.72      9987871.23
#Sta/Elev= 30
 -1824.9   58.77 -1461.7   58.52  -378.5   57.52   112.5   57.89   260.2   58.44
     261   55.57   273.8   54.26   299.7   41.73  4997.4   41.23  8170.2   41.73
  8175.8   46.13  8192.8   48.31    8221   54.03  8266.2   58.52  8469.6   55.88
  8537.4   55.39    8560   53.06  8588.2   54.15  8605.2   50.72  8633.4   48.07
  8641.7   44.19  8686.1   51.66  8830.5   54.66  8904.6    59.1  9435.5    61.4
  9767.9   60.01  9813.4   59.68 10260.2    62.2 10373.2   60.64 10458.7   62.77
#Mann= 9 ,-1 , 0
 -1824.9     .12       0 -1461.7      .1       0  -378.5     .12       0
   112.5     .05       0   273.8     .03       0  8192.8     .05       0
  8469.6    .075       0  9767.9    .075       0  9813.4     .05       0
#XS Ineff= 2 , 0
                         8261.36           58.54
Permanent Ineff=
       F       F
Bank Sta=273.8,8221
XS Rating Curve= 0 ,0
Exp/Cntr=0.3,0.1

Type RM Length L Ch R = 1 ,18440   ,1440,1440,1440
BEGIN DESCRIPTION:
WFSJ Main 18.0
END DESCRIPTION:
XS GIS Cut Line= 3
      3943868.12      9983292.75      3936316.05      9984790.15
      3930413.26      9986504.56
#Sta/Elev= 30
 -2449.6   59.33 -2419.4   59.65 -2285.9   58.86 -1551.2   58.69    35.8   57.06
     461   57.31  609.09   54.13   609.1   50.74   619.3   48.98   648.6   41.86
  4997.4   41.23    8071   41.73  8154.7    51.1    8244   53.33  8571.9   56.99
    8684   53.46  8767.3   58.51  9079.7   58.01  9223.3   55.97  9568.5   53.88
  9607.3    46.8  9662.2   55.17  9725.1   55.96 10173.1   57.05   10258   52.87
 10571.9   58.36 10675.8   57.85 10779.6   59.91 11279.9    58.4 11396.2    57.4
#Mann= 17 ,-1 , 0
 -2449.6     .12       0 -2419.4     .05       0 -2285.9     .12       0
 -1551.2      .1       0    35.8     .12       0     461     .05       0
   619.3     .03       0  8154.7     .05       0  8767.3    .075       0
  9079.7     .05       0  9223.3    .075       0  9662.2     .05       0
  9725.1    .075       0 10571.9     .05       0 10675.8    .075       0
 10779.6     .05       0 11279.9    .075       0
#XS Ineff= 2 , 0
                         8903.93           58.87
Permanent Ineff=
       F       F
Bank Sta=609.09,8244
XS Rating Curve= 0 ,0
Exp/Cntr=0.3,0.1

Type RM Length L Ch R = 1 ,17000   ,1000,1000,1000
BEGIN DESCRIPTION:
WFSJ Main 17.0
END DESCRIPTION:
XS GIS Cut Line= 3
      3944085.18      9982750.21      3936554.08      9983384.93
      3929718.86      9985527.98
#Sta/Elev= 30
 -2557.8   59.58   219.3   59.17   520.4   54.62   560.5   44.41   630.8   55.96
  1192.8   60.36  1413.6    52.8  1513.9   41.73  1604.2   56.34  2026.4   60.63
  2647.9   53.28  2752.2   49.97  2928.9   41.73  4997.4   41.23  9198.5   41.73
  9214.8   51.33  9240.4   52.24  9271.9   53.29  9452.4    56.6  9703.3   56.63
  9899.8   55.68  9968.9    55.6   10208   55.84   10453   56.54 10610.5   55.94
 10670.5   54.63 10747.6   53.58 11532.1   56.56   11540   56.68 12163.3   57.31
#Mann= 15 ,-1 , 0
 -2557.8     .05       0  2026.4     .05       0  2752.2     .03       0
  9240.4     .05       0  9452.4     .12       0  9703.3     .05       0
  9899.8     .12       0  9968.9     .05       0   10208    .075       0
   10453     .05       0 10610.5    .075       0 10670.5     .05       0
 10747.6    .075       0 11532.1     .05       0   11540    .075       0
#XS Ineff= 2 , 0
          1799.5   60.94
Permanent Ineff=
       F       F
Bank Sta=2647.9,9271.9
XS Rating Curve= 0 ,0
Exp/Cntr=0.3,0.1

Type RM Length L Ch R = 1 ,16000   ,1000,1000,1000
BEGIN DESCRIPTION:
WFSJ Main 16.0
END DESCRIPTION:
XS GIS Cut Line= 3
      3943989.33      9982461.43      3936814.65      9982419.48
      3930148.59      9982486.89
#Sta/Elev= 30
 -2174.8   58.03 -1173.3   60.45   586.7   58.19   716.7   54.84   766.7   51.14
   806.7   41.73   846.7   41.73   906.7    52.7  1226.7   60.42  1716.7   57.06
  1746.7   59.49  2026.7   58.99  2126.7    56.3  2326.8   58.81  2686.8   58.85
  2826.8   53.72  2945.6   49.54  2996.8   49.41  3116.8   41.73  4997.4   41.23
10601.73   41.73 10657.1   41.73 10687.1   49.81 10847.1   51.29 10897.1   48.57
 10917.1      52 10997.1   54.17 11047.1   56.82 11237.1   55.95 11666.4   58.35
#Mann= 5 ,-1 , 0
 -2174.8     .05       0  2326.8     .05       0  2945.6     .03       0
10601.73     .05       0 11237.1     .12       0
#XS Ineff= 2 , 0
         1227.27   60.46
Permanent Ineff=
       F       F
Bank Sta=2826.8,10997.1
XS Rating Curve= 0 ,0
Exp/Cntr=0.3,0.1

Type RM Length L Ch R = 1 ,15000   ,1000,1000,1000
XS GIS Cut Line= 4
      3943954.65      9982218.37      3937296.48      9981544.57
      3930319.27      9981365.72      3930024.06      9981232.95
#Sta/Elev= 30
       0   59.79   516.9      58   750.6   59.99   800.9   57.47     831   59.93
   871.2   57.88  1072.2   62.02  1132.6   58.77  1444.1   60.88  2510.2   58.37
  2851.3   53.08  2881.4   46.35  2904.8   47.37  2971.9   41.82  3243.3   41.73
  3333.7   45.43  3499.3   46.26  3534.8   49.44  3554.9   46.05  3599.2   45.66
  3645.3   48.76  3946.9   51.38  4147.9   45.67    4178   41.73 12932.9   41.73
 13012.9   47.79   13158  52.872   13363   57.67 13940.4   55.27 13995.4   57.17
#Mann= 3 , 0 , 0
       0     .05       0  2851.3     .03       0   13158     .05       0
#XS Ineff= 1 ,-1
    2800  3946.9   51.38
Permanent Ineff=
       F
Bank Sta=2851.3,13158
XS Rating Curve= 0 ,0
Exp/Cntr=0.3,0.1

Type RM Length L Ch R = 1 ,14000   ,1000,1000,1000
BEGIN DESCRIPTION:
WFSJ Main 14.0
END DESCRIPTION:
XS GIS Cut Line= 3
      3943919.94      9981975.32       3937841.5      9980714.14
      3929544.98      9980239.21
#Sta/Elev= 30
 -1207.9   60.19  -725.8   60.17  -695.1   57.56  -511.3   59.87  -329.1   57.05
  -273.8   60.31   111.7   61.11   816.4   59.07   979.8   57.21  1004.4   54.51
  1030.9   57.54  1054.5   55.02  1071.7   57.27  1173.9   55.06  1408.8   58.78
    1738   57.27  1821.6   57.51  1960.3   53.51 2064.3749.43361  2195.2   41.74
  4997.4   41.23   11364   41.73 11494.3   44.28 11634.5   51.43 11684.6   53.47
 11874.9   57.85 12967.5   55.44   13157   53.13 13197.6      56 13310.1   55.55
#Mann= 7 ,-1 , 0
 -1207.9     .05       0    1738    .075       0  1821.6     .05       0
 2064.37     .03       0 11634.5     .05       0 12967.5     .12       0
 13197.6     .12       0
Bank Sta=1960.3,11684.6
XS Rating Curve= 0 ,0
Exp/Cntr=0.3,0.1

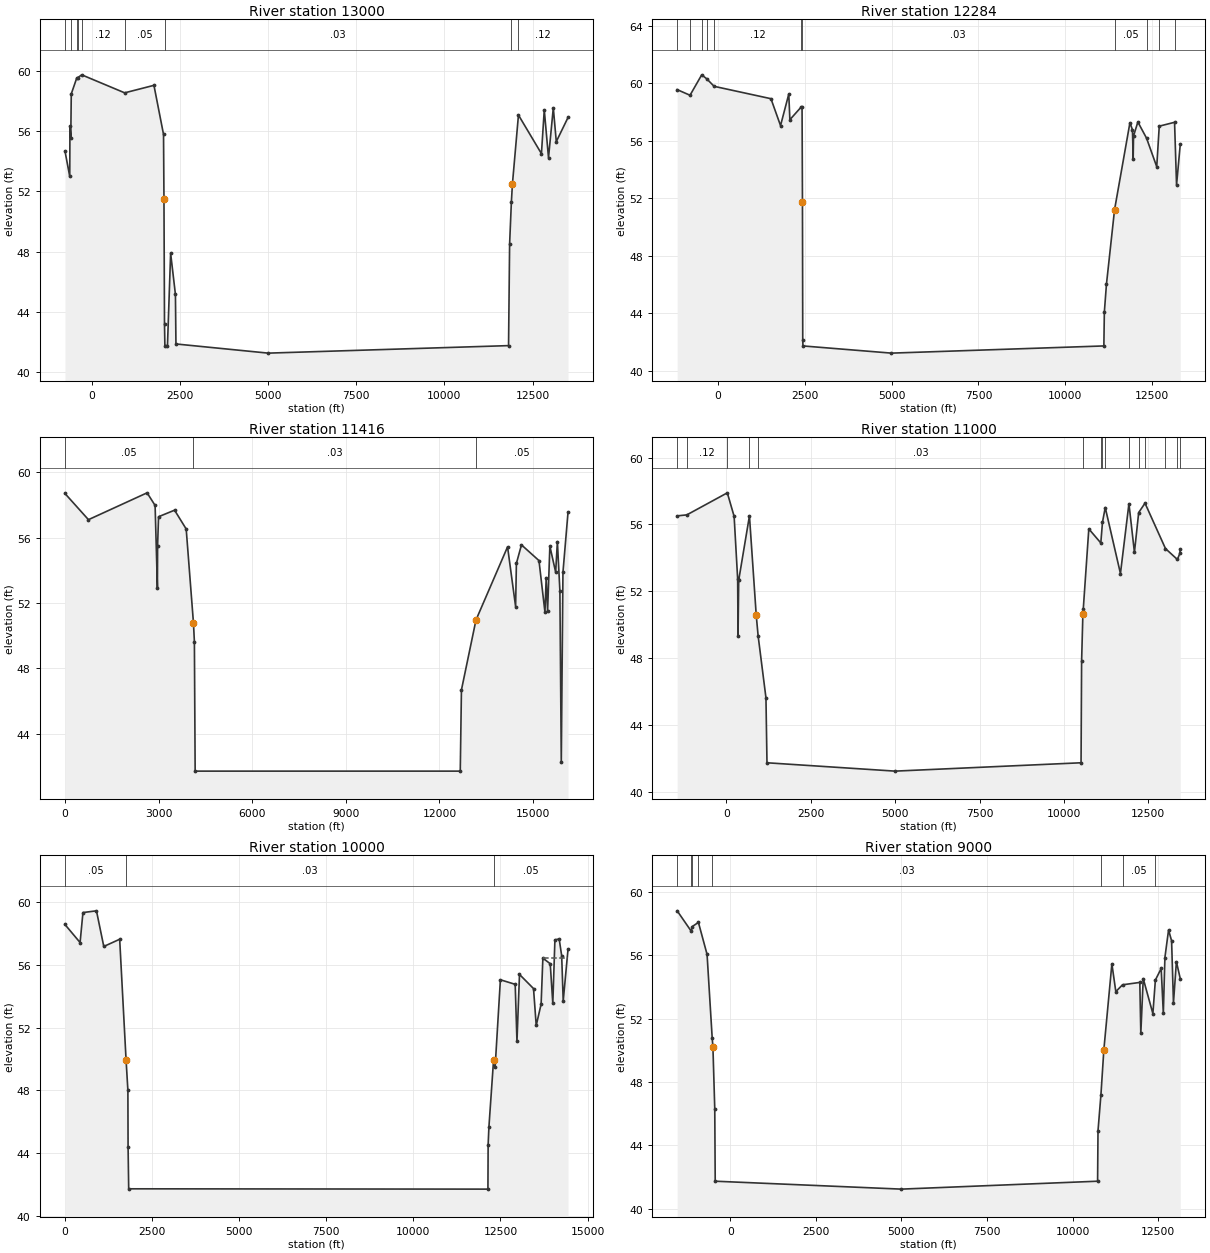
Type RM Length L Ch R = 1 ,13000   ,716,716,716
BEGIN DESCRIPTION:
WFSJ Main 13.0
END DESCRIPTION:
XS GIS Cut Line= 3
       3944058.8      9981697.54      3938543.95       9980002.4
      3930065.75      9979301.71
#Sta/Elev= 30
  -769.5    54.7  -633.1      53  -627.8   56.34  -603.9   55.59  -589.9    58.5
    -437   59.54    -400   59.59  -293.7   59.77   925.6   58.57  1756.1   59.07
  2028.2    55.8 2040.44   51.51  2055.7   43.15  2066.6   41.73  2139.9   41.73
  2229.7   47.88  2365.8   45.14  2380.5   41.84  4997.4   41.23 11819.3   41.73
 11849.4    48.5 11899.5   51.31 11929.6   52.51 12100.2   57.09 12752.4   54.52
 12832.7   57.43 12953.1   54.25 13089.2   57.57 13173.9   55.32 13507.1   56.93
#Mann= 9 ,-1 , 0
  -769.5     .12       0  -603.9      .1       0    -437     .12       0
    -400      .1       0  -293.7     .12       0   925.6     .05       0
  2066.6     .03       0 11899.5     .05       0 12100.2     .12       0
Bank Sta=2040.44,11929.6
XS Rating Curve= 0 ,0
Exp/Cntr=0.3,0.1

Type RM Length L Ch R = 1 ,12284   ,868,868,868
BEGIN DESCRIPTION:
Mapping XS cd349adf
END DESCRIPTION:
XS GIS Cut Line= 3
      3944783.62      9981393.71      3939384.34      9979536.08
      3930931.21      9977227.53
#Sta/Elev= 30
 -1166.8   59.55  -797.2   59.16  -460.8   60.58  -315.6    60.3  -104.1   59.78
  1530.8   58.92  1806.6   57.05  2043.6   59.24  2075.3   57.46  2389.4   58.31
  2425.9   58.31 2437.16   51.75  2445.5   42.16  2451.9   41.73  4997.4   41.23
 11108.1   41.73   11122   44.08 11182.4   46.02 11415.5    51.2   11858   57.25
 11930.6   56.76 11951.3   54.76 11961.7   56.33 12086.1    57.3 12335.3   56.18
 12629.2   54.19 12701.3   57.01 13141.8   57.28 13198.9   52.92 13305.8   55.75
#Mann= 11 ,-1 , 0
 -1166.8     .12       0  -797.2      .1       0  -460.8     .12       0
  -315.6      .1       0  -104.1     .12       0  2389.4     .05       0
  2425.9     .03       0 11415.5     .05       0 12335.3    .075       0
 12701.3     .05       0 13141.8    .075       0
Bank Sta=2437.16,11415.5
XS Rating Curve= 0 ,0
Exp/Cntr=0.3,0.1

Type RM Length L Ch R = 1 ,11416   ,416,416,416
XS GIS Cut Line= 4
      3945443.37      9980924.97      3939679.48      9978772.19
       3931586.5      9975788.76      3930380.17      9975199.24
#Sta/Elev= 30
       0   58.69   753.1   57.09  2631.9   58.73  2888.5   57.96  2962.8   52.94
  2968.7   55.51    2999   57.27  3512.4   57.67    3885   56.52  4117.5  50.783
  4147.7   49.64    4172   41.73 12666.5   41.73 12704.1   46.69 13169.8   50.96
   14182   55.43   14440   51.78 14465.1   54.42 14627.5   55.55 15188.5   54.59
 15379.9   51.44 15419.3   53.55 15464.4   51.51 15537.5   55.47 15723.2   53.88
 15778.4   55.75 15858.3   52.75 15903.3   42.27 15956.5   53.87 16119.4   57.55
#Mann= 3 , 0 , 0
       0     .05       0  4117.5     .03       0 13169.8     .05       0
#XS Ineff= 1 ,-1
   14182   16105   55.43
Permanent Ineff=
       F
Bank Sta=4117.5,13169.8
XS Rating Curve= 0 ,0
Exp/Cntr=0.3,0.1

Type RM Length L Ch R = 1 ,11000   ,1000,1000,1000
BEGIN DESCRIPTION:
WFSJ Main 11.0
END DESCRIPTION:
XS GIS Cut Line= 3
      3945617.01      9980543.04      3939565.45      9978292.18
      3932127.39      9974293.02
#Sta/Elev= 30
 -1456.6   56.51 -1170.5   56.57    28.6   57.89   230.4   56.48   334.9   52.73
   346.4   49.34   366.1   52.66   683.9   56.51   885.6   50.55     941   49.33
  1173.1   45.62  1203.5   41.73  4997.4   41.23 10506.4   41.73 10522.7    47.8
 10560.6   50.63 10572.2   50.93 10736.1   55.73 11091.6   54.89 11141.1   56.13
   11223   57.01 11673.3   53.06 11924.7   57.24 12087.4   54.33 12213.8   56.71
 12400.8   57.27 13007.6   54.55   13360    53.9 13431.5   54.26   13445    54.5
#Mann= 15 ,-1 , 0
 -1456.6      .1       0 -1170.5     .12       0    28.6      .1       0
   683.9     .05       0     941     .03       0 10572.2     .05       0
 11091.6     .12       0 11141.1     .05       0   11223     .05       0
 11924.7     .05       0 12213.8     .05       0 12400.8     .05       0
 13007.6     .05       0   13360    .075       0 13431.5     .05       0
Bank Sta=885.6,10560.6
XS Rating Curve= 0 ,0
Exp/Cntr=0.3,0.1

Type RM Length L Ch R = 1 ,10000   ,1000,1000,1000
XS GIS Cut Line= 4
      3946085.73      9980074.28       3940049.7      9977417.25
      3933340.53      9974065.85      3933052.48      9973873.72
#Sta/Elev= 30
       0   58.56   434.7   57.41   516.7   59.32   904.5   59.43    1115   57.16
    1571   57.62  1754.6   49.93  1806.7   48.01  1812.2    44.4    1830   41.73
 12141.4   41.71 12147.1   44.51 12169.5   45.66 12303.7   49.94 12348.4   49.49
 12499.1   55.04 12923.9   54.75 12974.7   51.11 13047.4   55.38   13450   54.48
 13527.5   52.13 13668.1   53.49 13718.4   56.42 13929.9   56.06 14003.6   53.53
 14064.1   57.58 14186.2   57.64 14258.3   56.57 14302.2   53.69 14440.6   56.99
#Mann= 3 , 0 , 0
       0     .05       0  1754.6     .03       0 12303.7     .05       0
#XS Ineff= 2 ,-1
 12499.1   13700   55.04 13728.7   14450   56.44
Permanent Ineff=
       F       F
Bank Sta=1754.6,12303.7
XS Rating Curve= 0 ,0
Exp/Cntr=0.3,0.1

Type RM Length L Ch R = 1 ,9000    ,1431,1431,1431
BEGIN DESCRIPTION:
WFSJ Main 9.0
END DESCRIPTION:
XS GIS Cut Line= 3
      3946415.57      9979431.91      3940533.95      9976542.32
      3933034.81      9973353.67
#Sta/Elev= 30
 -1553.1    58.8 -1144.1   57.52 -1110.2   57.81  -932.4   58.07  -679.6   56.05
  -530.6    50.8  -508.3   50.19  -454.7   46.31  -441.5   41.73  4997.4   41.23
 10733.2   41.73   10745   44.91   10831    47.2   10916   50.03 11150.5   55.45
 11265.7    53.7 11461.4   54.13 11966.9   54.28   11996   51.06 12066.9   54.52
 12348.7   52.31 12421.7   54.43 12591.4   55.16 12654.2   52.32 12700.1   55.85
 12806.9   57.59 12895.7   56.91   12950   52.98   13036   55.59 13148.9   54.52
#Mann= 8 ,-1 , 0
 -1553.1      .1       0 -1144.1     .05       0 -1110.2     .12       0
  -932.4     .05       0  -530.6     .03       0   10831     .05       0
 11461.4     .05       0 12421.7     .05       0
Bank Sta=-508.3,10916
XS Rating Curve= 0 ,0
Exp/Cntr=0.3,0.1

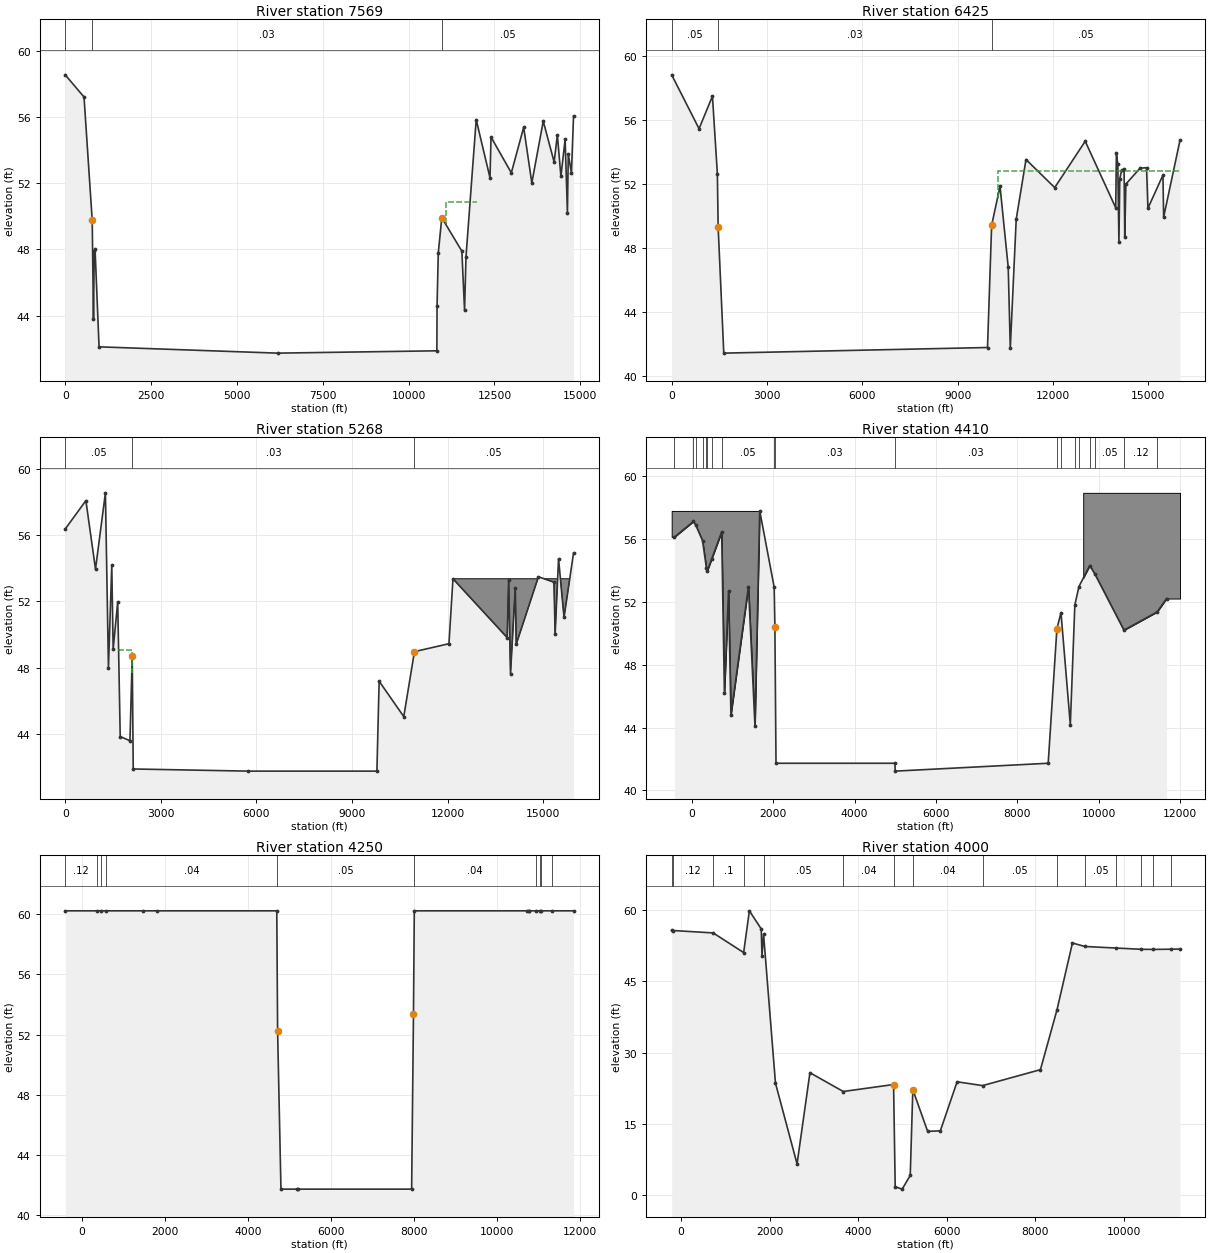
Type RM Length L Ch R = 1 ,7569    ,1144,1144,1144
XS GIS Cut Line= 4
      3947301.01      9977852.06      3941571.84      9975525.67
      3934759.15      9970943.83      3934358.25       9970859.4
#Sta/Elev= 30
       0   58.54     548    57.2   786.3   49.76   823.7   43.81   845.3   47.89
   869.3   48.01   985.6   42.11  6182.4   41.73 10822.9   41.87 10828.9   44.59
 10864.9   47.79 10966.8   49.91 11551.1   47.89 11629.7   44.31 11671.8   47.56
 11968.7   55.83 12370.7   52.32 12400.6   54.78 12991.6   52.62 13351.5   55.37
 13588.5   52.01 13921.4   55.74 14238.5   53.27 14332.3    54.9 14436.1    52.4
 14558.4   54.64 14625.1   50.21 14650.4   53.75 14742.4   52.61 14803.3   56.04
#Mann= 3 , 0 , 0
       0     .05       0   786.3     .03       0 10966.8     .05       0
#XS Ineff= 1 ,-1
   11081   12000   50.84
Permanent Ineff=
       F
Bank Sta=786.3,10966.8
XS Rating Curve= 0 ,0
Exp/Cntr=0.3,0.1

Type RM Length L Ch R = 1 ,6425    ,1157,1157,1157
XS GIS Cut Line= 4
      3947630.87      9976775.67      3942665.59      9974935.39
      3935501.24      9969781.18       3934162.5       9968467.9
#Sta/Elev= 30
       0    58.8   861.9   55.44    1283   57.47  1437.6   52.64  1462.6   49.31
  1639.6   41.45  9938.8    41.8 10068.9   49.42 10332.8   51.85 10590.6    46.8
 10655.6   41.76 10842.2    49.8 11150.3   53.52 12053.7   51.77 13013.6   54.66
 13973.5   50.51 13994.4   53.92 14038.5   53.22 14074.1   48.35 14101.2   52.32
 14158.9   52.84 14236.8   52.92 14257.9   48.72 14293.3   51.99 14738.8   52.98
 14943.8   53.01 14986.3   50.48   15460   52.55 15481.3   49.93 15996.2   54.72
#Mann= 3 , 0 , 0
       0     .05       0  1462.6     .03       0 10068.9     .05       0
#XS Ineff= 1 ,-1
 10255.4 15996.2   52.82
Permanent Ineff=
       F
Bank Sta=1462.6,10068.9
XS Rating Curve= 0 ,0
Exp/Cntr=0.3,0.1

Type RM Length L Ch R = 1 ,5268    ,858,858,858
XS GIS Cut Line= 4
      3947960.73      9976393.72      3940113.51      9972209.69
      3935741.35       9969546.2       3934157.7      9968434.91
#Sta/Elev= 30
       0   56.38   648.7    58.1   950.5   53.95  1261.2   58.57  1356.4   47.99
  1460.5   54.19  1504.5   49.11  1646.5   51.96  1725.8   43.82  2030.8   43.57
  2102.3   48.68  2133.8   41.86  5738.5   41.73  9777.8   41.73  9848.1   47.17
 10620.9   45.03 10955.6   48.96 12038.3   49.44 12164.1   53.37 13864.6   49.81
   13911    53.3 13969.1   47.63 14118.9   52.82 14148.6   49.41 14844.9   53.49
   15333   53.16 15368.7   50.01 15475.9   54.58 15648.5   51.04 15946.2   54.92
#Mann= 3 , 0 , 0
       0     .05       0  2102.3     .03       0 10955.6     .05       0
#XS Ineff= 1 ,-1
    1660  2088.5   49.05
Permanent Ineff=
       F
#Block Obstruct= 1 ,-1
 12164.1 15946.2   53.37
Bank Sta=2102.3,10955.6
XS Rating Curve= 0 ,0
Exp/Cntr=0.3,0.1

Type RM Length L Ch R = 1 ,4410    ,160,160,160
BEGIN DESCRIPTION:
WFSJ Main 5.0
END DESCRIPTION:
XS GIS Cut Line= 5
      3948176.76      9975841.98      3943319.99       9972977.4
      3940133.12       9971074.8      3939324.13      9971242.58
      3937518.61      9970578.53
#Sta/Elev= 30
  -430.7   56.11    34.8    57.1    93.2   56.86   258.8   55.88   354.1   54.15
   370.8   53.92   482.7   54.71     729   56.43   797.1   46.19   898.6   52.65
   957.1    44.8  1388.4   52.96  1548.4    44.1  1665.5   57.77  2020.552.92557
  2038.3   50.38  2065.5   41.73    4990   41.73  4997.4   41.23  8758.9   41.73
    8973   50.28  9073.3    51.3  9302.8   44.18  9414.1   51.79  9514.4   52.96
    9781    54.3  9912.5   53.73 10621.5   50.19 11438.3   51.35 11669.5    52.2
#Mann= 19 ,-1 , 0
  -430.7     .12       0    34.8     .05       0    93.2     .05       0
   258.8     .05       0   354.1      .1       0   370.8     .05       0
   482.7      .1       0     729     .05       0  2020.5     .05       0
  2038.3     .03       0    4990     .03       0    8973     .05       0
  9073.3     .05       0  9414.1     .05       0  9514.4     .12       0
    9781    .075       0  9912.5     .05       0 10621.5     .12       0
 11438.3     .05       0
#XS Ineff= 1 ,-1
  9073.3    9510    51.3
Permanent Ineff=
       F
#Block Obstruct= 2 ,-1
    9620   12000   58.92    -500  1665.5   57.77
Bank Sta=2038.3,8973
XS Rating Curve= 0 ,0
Exp/Cntr=0.5,0.3

Type RM Length L Ch R = 1 ,4250    ,250,250,250
BEGIN DESCRIPTION:
Mapping XS 4ca105be
Elevations from the TWDB website
END DESCRIPTION:
XS GIS Cut Line= 6
      3948244.09      9975745.96      3945995.86      9974417.86
      3940226.75      9970927.54      3939345.83      9971186.16
      3939055.03      9970344.14       3938122.4      9969793.24
#Sta/Elev= 22
    -401   60.23   361.1   60.23   473.2   60.23   585.2   60.23  1481.3   60.23
    1809   60.23    4696   60.23    4716  52.225  4796.6   41.73    5177   41.73
    5200   41.73    7945   41.73    7989  53.342    8009   60.23   10731   60.23
 10760.9   60.23 10770.3   60.23 10934.1   60.23 11046.1   60.23 11053.2   60.23
 11324.7   60.23 11845.1   60.23
#Mann= 10 ,-1 , 0
    -401     .12       0   361.1      .1       0   473.2     .12       0
   585.2     .04       0    4696     .05       0    8009     .04       0
 10934.1     .12       0 11046.1     .05       0 11053.2     .12       0
 11324.7     .05       0
Bank Sta=4716,7989
XS Rating Curve= 0 ,0
Exp/Cntr=0.5,0.3

Type RM Length L Ch R = 1 ,4000    ,287,287,287
BEGIN DESCRIPTION:
WFSJ Main 4.0
END DESCRIPTION:
XS GIS Cut Line= 3
       3948202.8      9975503.44      3943761.23      9972775.33
      3938359.02      9969578.95
#Sta/Elev= 30
  -212.5   55.67  -179.4   55.65   725.3   55.15  1414.4   51.02    1544   59.79
  1812.7   55.98  1828.2   50.36  1864.9   54.82  2133.6   23.59  2621.6    6.61
  2912.5   25.78  3665.6   21.83  4803.1    23.3  4839.7    1.82  4997.4    1.32
  5179.7    4.19  5238.2   22.21  5573.6   13.45  5860.3   13.57  6238.6   23.87
  6815.4   23.07  8122.3   26.42  8496.3   38.97  8845.8   53.03  9126.9    52.3
    9834   51.97 10401.3   51.71 10672.1   51.68 11081.3   51.73   11277   51.75
#Mann= 15 ,-1 , 0
  -212.5      .1       0  -179.4     .12       0   725.3      .1       0
  1414.4     .12       0  1864.9     .05       0  3665.6     .04       0
  4803.1     .04       0  5238.2     .04       0  6815.4     .05       0
  8496.3     .05       0  9126.9     .05       0    9834     .05       0
 10401.3     .05       0 10672.1     .12       0 11081.3     .05       0
Bank Sta=4803.1,5238.2
XS Rating Curve= 0 ,0
Exp/Cntr=0.5,0.3

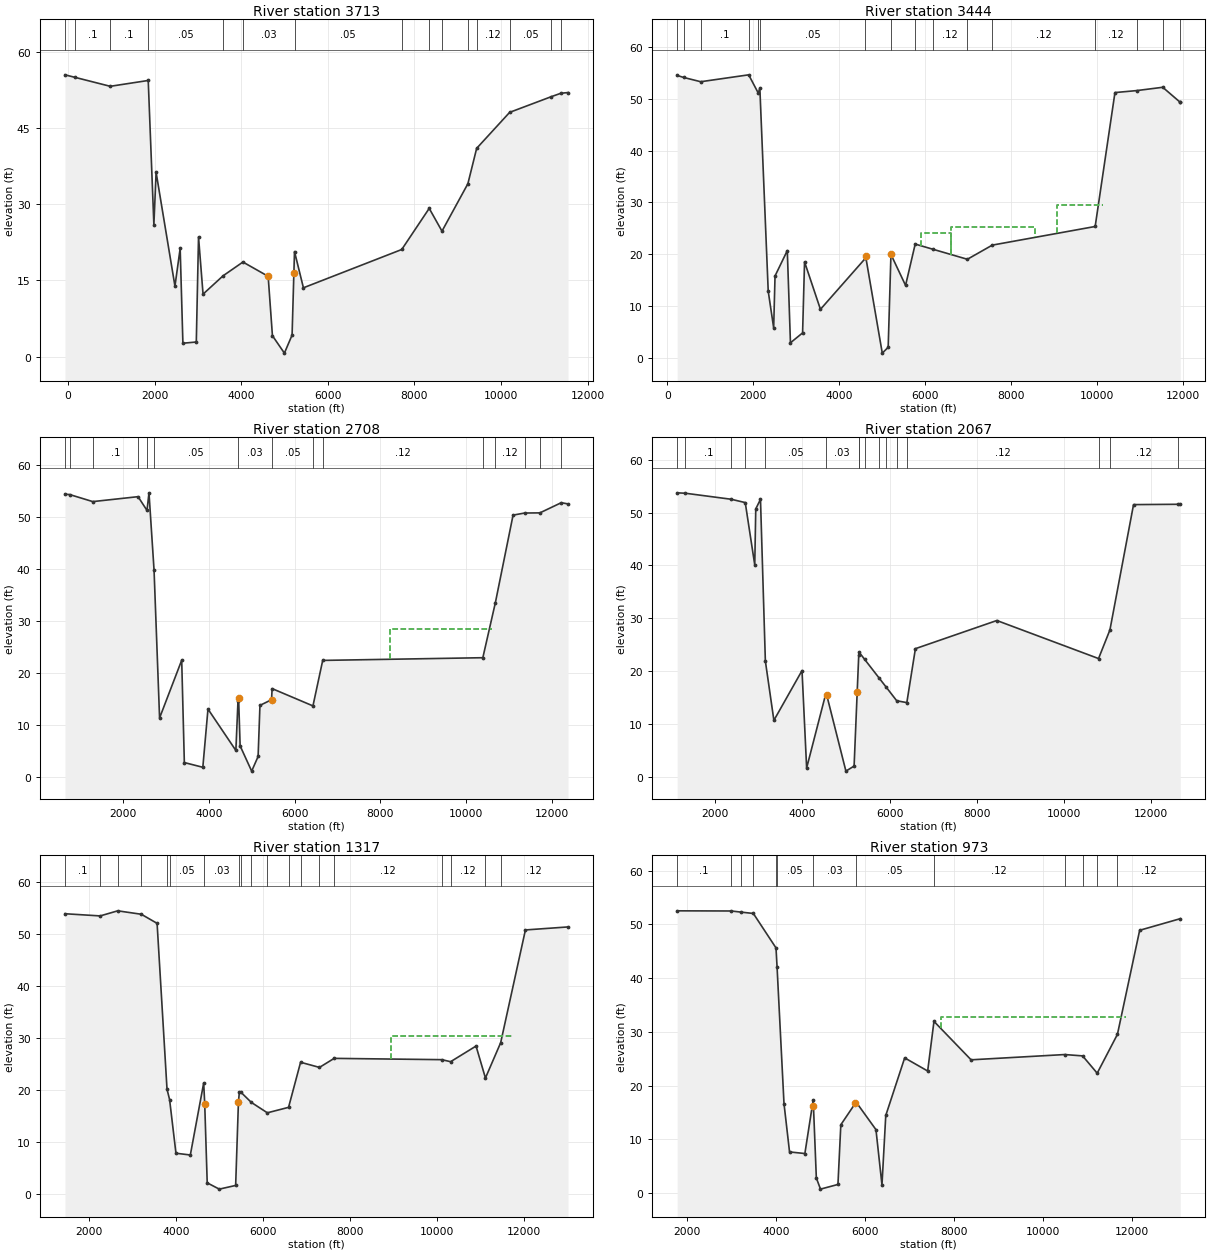
Type RM Length L Ch R = 1 ,3713    ,269,269,269
BEGIN DESCRIPTION:
Mapping XS 49cbcb47
END DESCRIPTION:
XS GIS Cut Line= 5
      3948464.77      9974987.38      3944697.39      9973251.26
      3942978.64       9971714.8      3941537.67      9970386.68
      3938482.51      9969414.58
#Sta/Elev= 30
     -71   55.48     172   54.96   975.5   53.22  1852.5   54.37    1983   25.99
  2034.4   36.29  2469.7   13.89  2590.2   21.31  2653.4    2.65  2962.8    2.89
  3014.2   23.57  3118.7   12.31  3581.2   15.92  4039.9   18.63  4622.4   15.82
  4721.1    4.13  4997.4      .7    5175    4.25  5216.8   16.55    5231   20.69
  5436.7   13.56 7707.6321.09797  8342.2   29.19  8637.1   24.71  9235.2   34.04
  9438.1   41.01 10199.6   48.09 11161.7   51.18 11382.1   51.85 11548.3   51.99
#Mann= 15 ,-1 , 0
     -71     .12       0     172      .1       0   975.5      .1       0
  1852.5     .05       0  3581.2     .05       0  4039.9     .03       0
    5231     .05       0 7707.63      .1       0  8342.2     .12       0
  8637.1      .1       0  9235.2     .05       0  9438.1     .12       0
 10199.6     .05       0 11161.7     .12       0 11382.1     .05       0
#XS Ineff= 1 ,-1
  8342.2    9195   29.19
Permanent Ineff=
       F
Bank Sta=4622.4,5216.8
XS Rating Curve= 0 ,0
Exp/Cntr=0.3,0.1

Type RM Length L Ch R = 1 ,3444    ,736,736,736
BEGIN DESCRIPTION:
Mapping XS c612900c
END DESCRIPTION:
XS GIS Cut Line= 4
      3948542.84      9974414.44       3944784.2      9973138.41
      3941954.34      9969883.21      3938655.69       9968989.1
#Sta/Elev= 30
   227.4   54.47   379.4   54.08   774.9   53.26  1890.7   54.59  2111.4    51.1
  2150.2   51.99  2344.8   12.89  2471.5    5.82  2503.2   15.82  2788.3   20.71
  2861.7    2.94  3144.2    4.85  3189.6   18.54  3559.2    9.39  4603.8   19.22
  4610.5   19.61  4997.4     .95  5134.6    2.07  5199.2   19.97  5539.1      14
    5763   21.97  6171.4   20.98  6976.3   19.04  7556.5   21.77  9948.7   25.36
 10408.9   51.17 10913.4   51.55 11520.1   52.19 11924.5   49.31 11927.7   49.32
#Mann= 16 ,-1 , 0
   227.4     .12       0   379.4      .1       0   774.9      .1       0
  1890.7     .05       0  2111.4      .1       0  2150.2     .05       0
  4603.8     .03       0  5199.2     .05       0    5763      .1       0
  6171.4     .12       0  6976.3      .1       0  7556.5     .12       0
  9948.7     .12       0 10913.4     .05       0 11520.1     .05       0
 11924.5     .12       0
#XS Ineff= 3 ,-1
  5907.5    6600   24.05  6602.6    8550   25.33  9071.7   10125   29.47
Permanent Ineff=
       F       F       F
Bank Sta=4610.5,5199.2
XS Rating Curve= 0 ,0
Exp/Cntr=0.3,0.1

Type RM Length L Ch R = 1 ,2708    ,641,641,641
BEGIN DESCRIPTION:
WFSJ Main 3.0
END DESCRIPTION:
XS GIS Cut Line= 4
      3948751.23        9974128.      3945348.43      9972773.83
       3942865.8      9969718.28      3938803.28      9968876.26
#Sta/Elev= 30
   637.1   54.45   746.8    54.4  1286.8   53.04  2344.4   53.99  2553.5   51.34
  2599.6   54.73    2718   39.84  2847.1   11.38  3363.7    22.5  3425.4    2.79
    3857    1.88  3977.2   13.09  4628.5    5.12  4678.1   14.66  4692.4   15.14
  4728.2       6  4997.4    1.14  5147.9    3.96    5191    13.8  5461.1   14.89
  5475.4   17.03  6428.7    13.7  6656.4   22.46 10395.9   22.98 10689.5   33.61
   11102   50.44 11372.9   50.84 11728.2   50.87 12227.7   52.83 12385.3   52.59
#Mann= 15 ,-1 , 0
   637.1     .12       0   746.8      .1       0  1286.8      .1       0
  2344.4     .05       0  2553.5     .12       0    2718     .05       0
  4678.1     .03       0  5475.4     .05       0  6428.7     .05       0
  6656.4     .12       0 10395.9      .1       0 10689.5     .12       0
 11372.9      .1       0 11728.2     .12       0 12227.7     .05       0
#XS Ineff= 1 ,-1
  8236.4   10620    28.5
Permanent Ineff=
       F
Bank Sta=4692.4,5461.1
XS Rating Curve= 0 ,0
Exp/Cntr=0.3,0.1

Type RM Length L Ch R = 1 ,2067    ,750,750,750
BEGIN DESCRIPTION:
WFSJ Main 2.0
END DESCRIPTION:
XS GIS Cut Line= 4
      3948953.06      9973741.72      3945828.04      9972341.97
      3943115.36      9969618.45      3938961.22      9968588.05
#Sta/Elev= 30
  1124.2   53.75  1314.7   53.67  2366.6   52.53  2686.7    51.9    2905   40.11
  2928.1   50.71  3036.5   52.52  3148.5    21.9  3344.2   10.68  3989.8    20.1
  4095.9    1.66  4535.3   15.71  4556.2   15.49  4997.4    1.07  5185.5    2.03
 5256.44   16.06  5291.6   22.96  5299.9   23.58  5427.8   22.22  5759.8   18.69
  5925.5   16.93  6163.7   14.39  6395.8   14.04  6592.7   24.25  8461.9   29.58
 10796.7   22.38 11057.9    27.8 11599.9   51.52   12616   51.58 12672.4   51.58
#Mann= 16 ,-1 , 0
  1124.2     .12       0  1314.7      .1       0  2366.6     .05       0
  2686.7     .12       0  3148.5     .05       0  4535.3     .03       0
  5291.6     .05       0  5299.9     .05       0  5427.8      .1       0
  5759.8      .1       0  5925.5     .05       0  6163.7     .05       0
  6395.8     .12       0 10796.7      .1       0 11057.9     .12       0
   12616      .1       0
#XS Ineff= 1 ,-1
  8461.9   11210   29.58
Permanent Ineff=
       F
Bank Sta=4556.2,5256.44
XS Rating Curve= 0 ,0
Exp/Cntr=0.3,0.1

Type RM Length L Ch R = 1 ,1317    ,344,344,344
BEGIN DESCRIPTION:
Mapping XS 278d6e0c
END DESCRIPTION:
XS GIS Cut Line= 4
      3949397.94      9973079.83      3946413.97      9971907.95
       3943636.2      9969661.85      3939003.65      9968435.91
#Sta/Elev= 30
    1448   53.87  2258.2   53.45  2661.9   54.43  3204.1   53.77  3567.3   52.02
  3795.5   20.09  3854.6    18.1    4001    7.77  4331.7    7.43  4638.9   21.29
  4662.5   17.31    4720    2.07  4997.4     .86    5374    1.57  5437.9   17.59
    5459   19.53  5487.7   19.57  5733.7   17.56  6102.9   15.55  6590.7    16.6
  6867.4   25.28  7301.5   24.29  7639.8   26.03 10114.4   25.78 10317.8   25.39
 10902.5    28.4 11118.7   22.25 11468.8   29.04 12038.2   50.75 13018.1   51.33
#Mann= 19 ,-1 , 0
    1448      .1       0  2258.2     .05       0  2661.9      .1       0
  3204.1     .12       0  3795.5      .1       0  3854.6     .05       0
  4638.9     .03       0    5459     .05       0  5487.7     .05       0
  5733.7     .05       0  6102.9     .05       0  6590.7      .1       0
  6867.4     .12       0  7301.5      .1       0  7639.8     .12       0
 10114.4      .1       0 10317.8     .12       0 11118.7      .1       0
 11468.8     .12       0
#XS Ineff= 1 ,-1
    8953   11720   30.31
Permanent Ineff=
       F
Bank Sta=4662.5,5437.9
XS Rating Curve= 0 ,0
Exp/Cntr=0.3,0.1

Type RM Length L Ch R = 1 ,973     ,836,836,836
BEGIN DESCRIPTION:
Mapping XS 129b9c40
END DESCRIPTION:
XS GIS Cut Line= 5
      3949450.02      9972437.47      3946542.01      9971560.72
      3945613.19      9970874.96      3944241.66      9969720.45
      3939085.46      9968331.57
#Sta/Elev= 30
  1771.3   52.51  2989.6   52.48  3209.9   52.27  3485.5   52.02    3996   45.61
  4019.2   42.14  4175.8   16.66  4300.5    7.67  4645.8    7.37  4832.8   17.32
  4839.1   16.17  4903.8    2.83  4997.4     .75  5390.3    1.62  5455.1   12.72
  5783.3   16.74  5797.5   16.96    6246   11.81  6381.3    1.53  6466.8   14.45
  6892.4   25.16    7410   22.72  7551.8   31.95  8387.2    24.8 10495.1   25.78
 10897.6   25.53   11226   22.31 11681.3   29.53 12182.1   48.89 13095.9   51.05
#Mann= 13 ,-1 , 0
  1771.3      .1       0  2989.6     .05       0  3209.9      .1       0
  3485.5     .12       0    3996      .1       0  4019.2     .05       0
  4832.8     .03       0  5797.5     .05       0  7551.8     .12       0
 10495.1      .1       0 10897.6     .12       0   11226      .1       0
 11681.3     .12       0
#XS Ineff= 1 ,-1
  7701.3   11880    32.8
Permanent Ineff=
       F
Bank Sta=4839.1,5783.3
XS Rating Curve= 0 ,0
Exp/Cntr=0.3,0.1

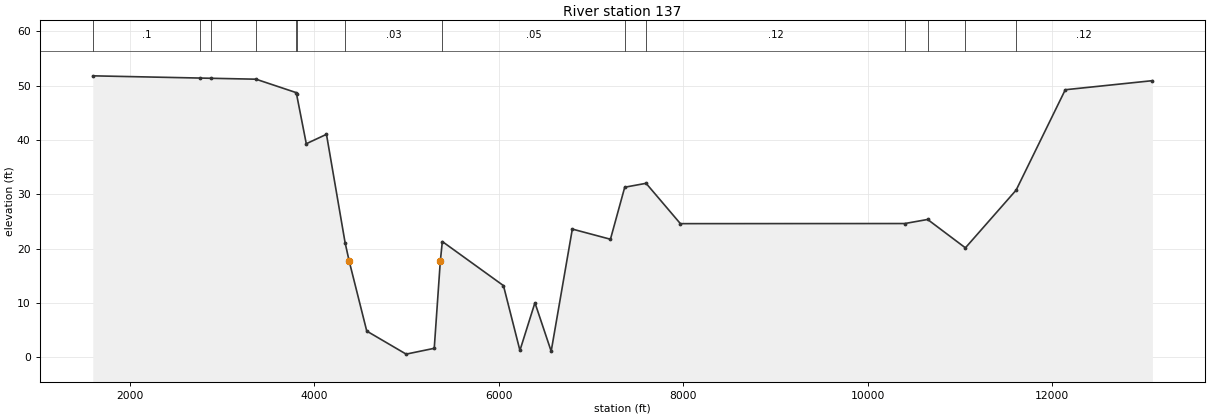
Type RM Length L Ch R = 1 ,137     ,0,0,0
BEGIN DESCRIPTION:
WFSJ Main 1.0
END DESCRIPTION:
XS GIS Cut Line= 4
      3949766.85       9971962.2      3947629.25      9971397.96
      3944298.09      9969596.75      3938982.09      9968229.78
#Sta/Elev= 30
  1600.5   51.79  2761.7   51.38  2879.2   51.34  3369.8   51.17  3802.1   48.72
  3809.4   48.44    3915    39.3  4133.8   41.03  4335.5   21.12  4379.3   17.75
  4570.5    4.84  4997.4      .6  5302.1    1.67  5367.9   17.71  5389.8   21.31
  6052.4    13.2  6230.9    1.28  6393.5   10.05  6569.6    1.13  6798.9    23.6
    7212   21.73  7366.9    31.3  7598.3   32.02  7970.2    24.6 10402.4   24.62
 10650.4   25.37 11059.8   20.15 11609.8   30.77 12142.6   49.23 13087.2    50.9
#Mann= 14 ,-1 , 0
  1600.5      .1       0  2761.7     .05       0  2879.2      .1       0
  3369.8     .12       0  3802.1      .1       0  3809.4     .05       0
  4335.5     .03       0  5389.8     .05       0  7366.9      .1       0
  7598.3     .12       0 10402.4      .1       0 10650.4     .12       0
 11059.8      .1       0 11609.8     .12       0
#XS Ineff= 1 ,-1
  7598.3   11800   32.02
Permanent Ineff=
       F
Bank Sta=4379.3,5367.9
XS Rating Curve= 0 ,0
Exp/Cntr=0.3,0.1