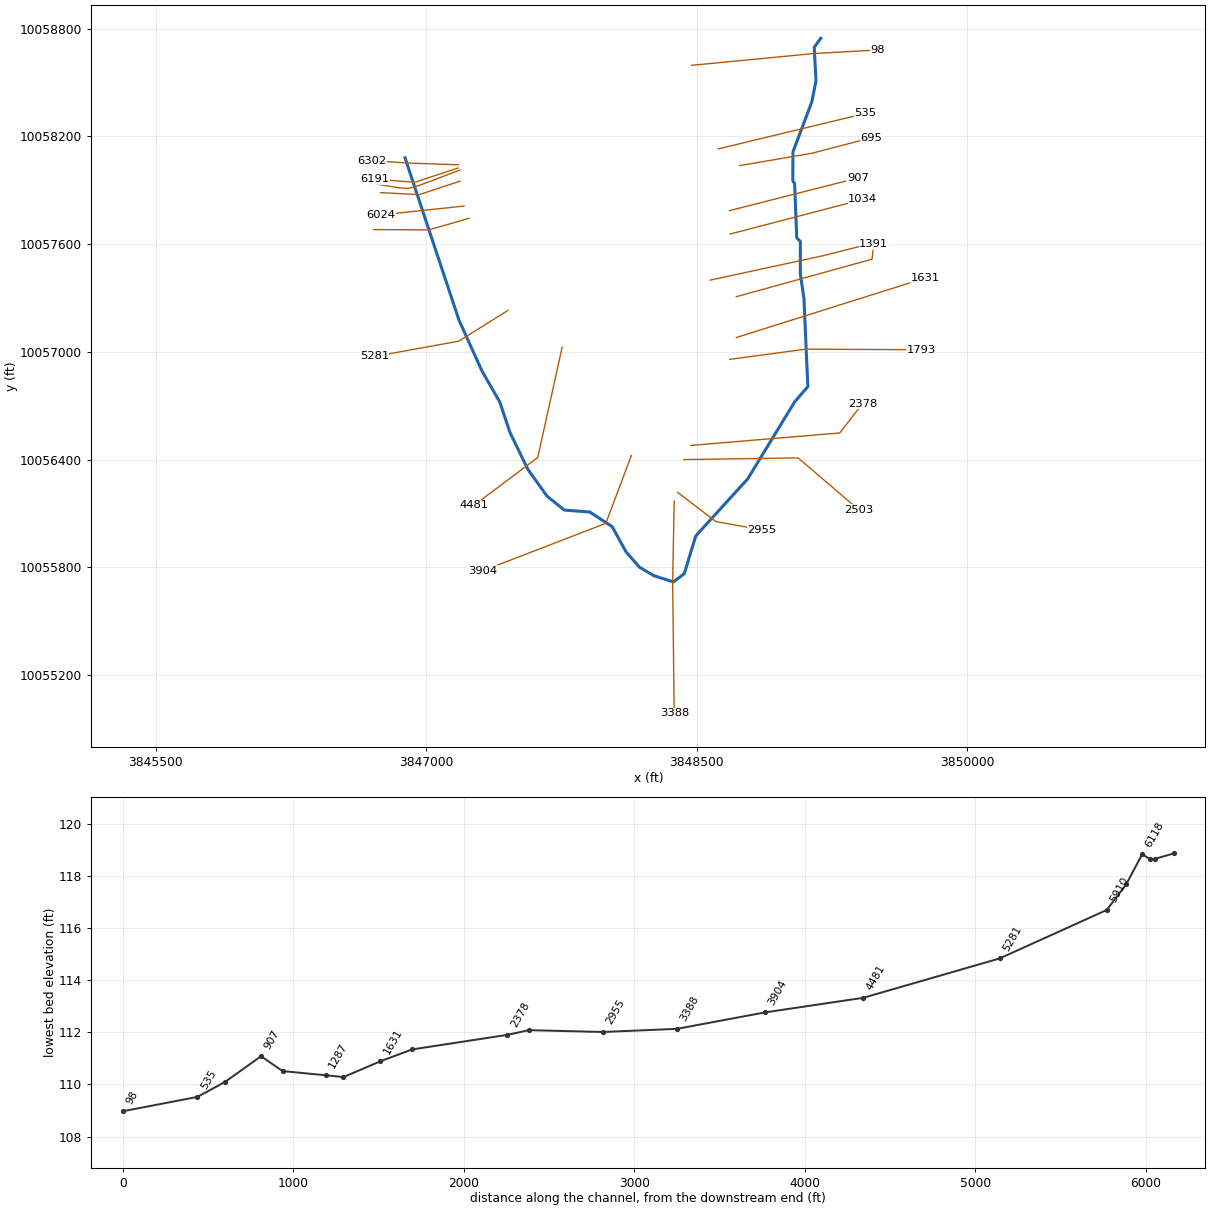
--- WHITE OAK CREEK WEST TRIB NO 1.prj (project) ---

Proj Title=WHITE OAK CREEK WEST TRIB NO 1 Base Level Engineering
Current Plan=p01
Default Exp/Contr=0.3,0.1
English Units
Geom File=g01
Flow File=f01
Plan File=p01
Y Axis Title=Elevation
X Axis Title(PF)=Main Channel Distance
X Axis Title(XS)=Station
BEGIN DESCRIPTION:
WHITE OAK CREEK WEST TRIB NO 1
END DESCRIPTION:
DSS File=dss
DSS Export Rating Curves= 0
DSS Export Rating Curve Sorted= 0
DSS Export Volume Flow Curves= 0
DXF OffsetX= 0
DXF OffsetY= 0
DXF ScaleX= 1
DXF ScaleY= 10

--- WHITE OAK CREEK WEST TRIB NO 1.p01 (plan) ---

Plan Title=Multiple Run
Program Version=4.10
Short Identifier=Multiple Run
Geom File=g01
Flow File=f01
Subcritical Flow
K Sum by GR= 0
Std Step Tol= 0.01
Critical Tol= 0.01
Num of Std Step Trials= 20
Max Error Tol= 0.3
Flow Tol Ratio= 0.001
Split Flow NTrial= 30
Split Flow Tol= 0.02
Split Flow Ratio= 0.02
Log Output Level= 0
Friction Slope Method= 1
Unsteady Friction Slope Method= 2
Unsteady Bridges Friction Slope Method= 1
Parabolic Critical Depth
Global Vel Dist= 1 , 1 , 1
Global Log Level= 0
CheckData=True
Encroach Param=-1 ,0,0, 0
BEGIN DESCRIPTION:
Multiple Run
END DESCRIPTION:
Computation Interval=1HOUR
Output Interval=1HOUR
Run HTab= 0
Run UNet= 0
Run PostProcess= 0
Run WQNet= 0
UNET Theta= 1
UNET Theta Warmup= 1
UNET ZTol= 0.02
UNET ZSATol= 0.05
UNET MxIter= 20
UNET MaxInSteps= 0
UNET DtIC= 0
UNET DtMin= 0
UNET MaxCRTS= 20
UNET WFStab= 2
UNET SFStab= 1
UNET WFX= 1
UNET SFX= 1
UNET DSS MLevel= 4
UNET DZMax Abort= 100
UNET Convert EG Bridges= 0
UNET Use Existing IB Tables=-1
UNET Froude Reduction=False
UNET Froude Limit= 1
UNET Froude Power= 10
UNET Time Slicing=0,0, 5
UNET Junction Losses=0
Instantaneous Interval=1HOUR
DSS File=dss
Write IC File= 0
Write IC File at Sim End=0
Echo Input=False
Echo Parameters=False
Echo Output=False
Write Detailed= 0
WQ AD Non Conservative
WQ ULTIMATE=-1
WQ Max Comp Step=1HOUR
WQ Output Interval=15MIN
WQ Output Selected Increments= 0
WQ Output face flow=0
WQ Output face velocity=0
WQ Output face area=0
WQ Output face dispersion=0
WQ Output cell volume=0
WQ Output cell surface area=0
WQ Output cell continuity=0
WQ Output cumulative cell continuity=0
WQ Output face conc=0
WQ Output face dconc_dx=0
WQ Output face courant=0
WQ Output face peclet=0
WQ Output face adv mass=0
WQ Output face disp mass=0
WQ Output cell mass=0
WQ Output cell source sink temp=0
WQ Output cell source sink nsm=0
WQ Output MaxMinRange=-1
WQ Daily Max Min Mean=-1
WQ Daily Range=0
WQ Daily Time=0
WQ Create Restart=0
WQ Fixed Restart=0
WQ System Summary=0
WQ Use Fixed Temperature=0
Sorting and Armoring Iterations= 10
XS Update Threshold= 0.02
Hydraulics Update Threshold= 0.02
Energy Slope Method= 1
Volume Change Method= 0
XS Weighting Method= 0
Number of US Weighted Cross Sections= 1
Number of DS Weighted Cross Sections= 1
Upstream XS Weight=0.25
Main XS Weight=0.5
Downstream XS Weight=0.25
Number of DS XS's Weighted with US Boundary= 1
Upstream Boundary Weight= 1
Weight of XSs Associated with US Boundary= 0
Number of US XS's Weighted with DS Boundary= 1
Downstream Boundary Weight= 0.5
Weight of XSs Associated with DS Boundary= 0.5
Sediment Output Level= 4
Mass or Volume Output= 0
Output Increment Type= 1
Profile and TS Output Increment= 10
XS Output Flag= 0
XS Output Increment= 10
Disregard all LS=0
Disregard all Conn=0
Disregard all Breaches=0
Disregard all Pumps=0

--- WHITE OAK CREEK WEST TRIB NO 1.f01 (steady flow) ---

Flow Title=Multiple
Program Version=4.10
Number of Profiles= 7
Profile Names=10-year,25-year,50-year,1pct_min,100-year,1pct_plu,500-year
River Rch & RM=WHITE OAK CREEK,Reach-1         ,6302
     428     551     720     309     933    2818    1620
Boundary for River Rch & Prof#=WHITE OAK CREEK,Reach-1         , 1
Up Type= 0
Dn Type= 3
Dn Slope=0.0065
Boundary for River Rch & Prof#=WHITE OAK CREEK,Reach-1         , 2
Up Type= 0
Dn Type= 3
Dn Slope=0.0065
Boundary for River Rch & Prof#=WHITE OAK CREEK,Reach-1         , 3
Up Type= 0
Dn Type= 3
Dn Slope=0.0065
Boundary for River Rch & Prof#=WHITE OAK CREEK,Reach-1         , 4
Up Type= 0
Dn Type= 3
Dn Slope=0.0065
Boundary for River Rch & Prof#=WHITE OAK CREEK,Reach-1         , 5
Up Type= 0
Dn Type= 3
Dn Slope=0.0065
Boundary for River Rch & Prof#=WHITE OAK CREEK,Reach-1         , 6
Up Type= 0
Dn Type= 3
Dn Slope=0.0065
Boundary for River Rch & Prof#=WHITE OAK CREEK,Reach-1         , 7
Up Type= 0
Dn Type= 3
Dn Slope=0.0065
DSS Import GetInterval= 0
DSS Import GetPeak= 0
DSS Import FillOption= 0

--- WHITE OAK CREEK WEST TRIB NO 1.g01 (geometry) ---

Geom Title=Existing Conditions
Program Version=4.10

River Reach=WHITE OAK CREEK ,Reach-1
Reach XY= 30
      3846882.07     10058080.63      3847181.12     10057177.37
       3847308.6     10056894.09      3847407.74     10056720.57
       3847464.4     10056550.61      3847563.57     10056345.23
      3847669.79      10056196.5       3847765.4     10056118.58
      3847907.04     10056107.93      3848030.97      10056026.5
      3848108.87     10055884.88      3848183.27     10055799.86
      3848261.14     10055753.86      3848370.94     10055718.43
      3848431.12     10055764.48        3848495.     10055975.05
      3848782.65     10056291.92      3849043.66     10056721.81
      3849116.55     10056806.26        3849095.       10057295.
      3849075.02     10057435.03      3849075.02       10057615.
        3849055.     10057634.99      3849043.18     10057937.17
      3849032.91     10057953.56      3849033.94     10058113.74
      3849138.06     10058390.11      3849161.67     10058508.24
      3849152.13      10058696.6      3849188.16     10058746.26

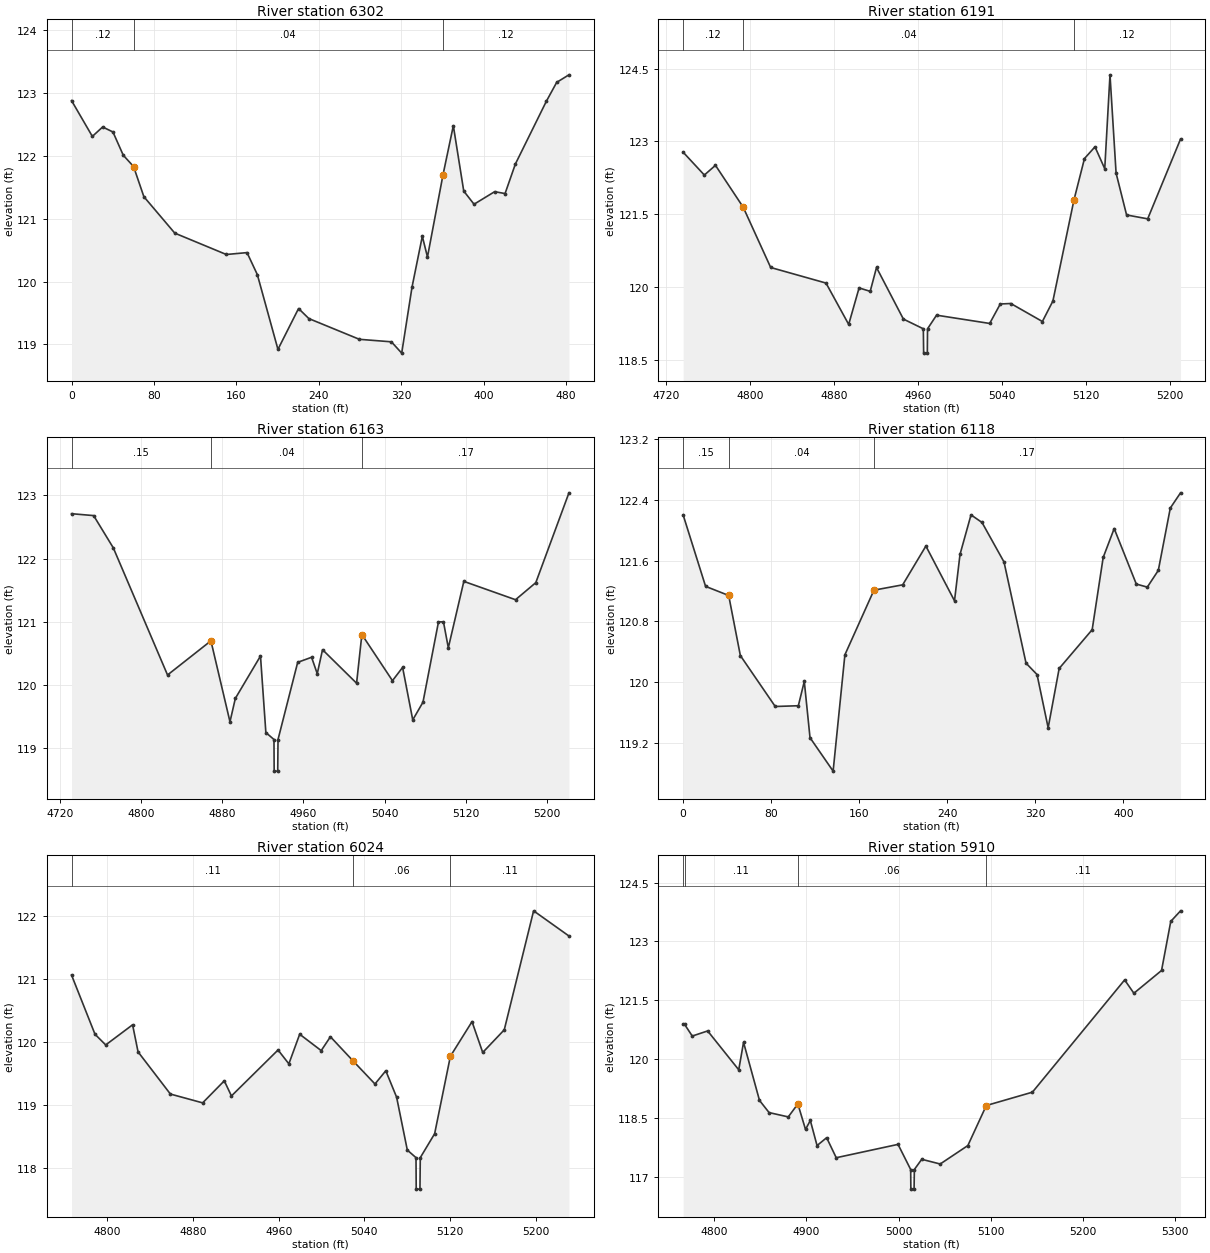
Type RM Length L Ch R = 1 ,6302    ,112,112,112
XS GIS Cut Line= 3
      3847178.01     10058041.83      3846894.87     10058051.81
      3846695.92     10058065.53
#Sta/Elev= 30
       0  122.88    20.2  122.31    30.2  122.46    40.2  122.38    50.2  122.01
    60.2  121.83    70.2  121.35   100.2  120.77   150.2  120.43   170.3  120.46
   180.3  120.11   200.3  118.92   220.3  119.57   230.3  119.41   279.3  119.08
   310.4  119.04   320.4  118.86   330.4  119.91   340.4  120.72   345.4  120.39
   360.5   121.7   370.5  122.48   380.6  121.44   390.6  121.23   410.6  121.43
   420.7   121.4   430.7  121.87   460.8  122.87   470.8  123.17   482.7  123.29
#Mann= 3 , 0 , 0
       0     .12       0    60.2     .04       0   360.5     .12       0
Bank Sta=60.2,360.5
XS Rating Curve= 0 ,0
Exp/Cntr=0.3,0.1

Type RM Length L Ch R = 1 ,6191    ,28,28,28
BEGIN DESCRIPTION:
Mapping XS 726f963b
END DESCRIPTION:
XS GIS Cut Line= 3
      3847177.03      10058024.1      3846937.15     10057944.81
      3846716.59     10057961.07
#Sta/Elev= 30
  4735.9  122.78  4756.1  122.31  4766.7  122.51  4793.1  121.65  4819.3  120.41
    4872  120.09  4893.6  119.24  4903.5  119.99  4914.1  119.92  4920.1  120.41
  4945.7  119.35  4964.7  119.15    4965  118.65  4968.5  118.65  4968.7  119.15
  4977.3  119.43  5027.9  119.26    5038  119.66    5048  119.67  5078.1   119.3
  5088.1  119.72  5108.2   121.8  5118.2  122.65  5128.2  122.89  5137.5  122.44
  5142.5  124.37  5148.3  122.35  5158.3  121.49  5178.4  121.41  5209.7  123.05
#Mann= 3 , 0 , 0
  4735.9     .12       0  4793.1     .04       0  5108.2     .12       0
Bank Sta=4793.1,5108.2
XS Rating Curve= 0 ,0
Exp/Cntr=0.3,0.1

Type RM Length L Ch R = 1 ,6163    ,46,46,46
BEGIN DESCRIPTION:
WHITE OAK CREEK WEST TRIB NO 1 13.0
END DESCRIPTION:
XS GIS Cut Line= 5
      3847186.34     10058012.61      3846966.98     10057929.16
      3846901.01     10057910.06      3846842.33     10057914.58
      3846715.55     10057935.37
#Sta/Elev= 30
  4731.2  122.71    4753  122.68  4772.4  122.17  4825.9  120.16  4868.7   120.7
  4887.5  119.42  4892.8  119.79  4917.6  120.46  4922.9  119.25  4930.9  119.14
  4931.1  118.64  4934.6  118.64  4934.9  119.14  4954.3  120.36    4968  120.44
  4973.6  120.18  4978.8  120.56  5012.4  120.03  5017.6   120.8  5047.8  120.07
  5057.8  120.28  5067.8  119.45  5077.9  119.73  5093.2     121  5098.1     121
  5102.9  120.59  5118.2  121.64  5169.2  121.35  5189.2  121.62  5221.9  123.04
#Mann= 3 , 0 , 0
  4731.2     .15       0  4868.7     .04       0  5017.6     .17       0
Bank Sta=4868.7,5017.6
XS Rating Curve= 0 ,0
Exp/Cntr=0.3,0.1

Type RM Length L Ch R = 1 ,6118    ,94,94,94
XS GIS Cut Line= 3
      3847187.24     10057950.76      3846960.86     10057875.65
       3846747.7     10057886.77
#Sta/Elev= 30
       0   122.2    20.4  121.26    41.4  121.14      52  120.35    83.7  119.68
   104.7  119.69   110.1  120.01   115.3  119.27   136.3  118.83     147  120.36
   173.4  121.21   199.5  121.28   220.6  121.79   246.6  121.07   251.6  121.68
   261.6   122.2   271.6   122.1   291.6  121.58   311.6  120.25   321.6   120.1
   331.7   119.4   341.7  120.18   371.7  120.69   381.7  121.64   391.7  122.02
   411.8  121.29   421.8  121.25   431.8  121.47   442.7  122.29     452  122.49
#Mann= 3 , 0 , 0
       0     .15       0    41.4     .04       0   173.4     .17       0
Bank Sta=41.4,173.4
XS Rating Curve= 0 ,0
Exp/Cntr=0.3,0.1

Type RM Length L Ch R = 1 ,6024    ,114,114,114
BEGIN DESCRIPTION:
Mapping XS 6394c6b0
END DESCRIPTION:
XS GIS Cut Line= 2
       3847209.6     10057812.11      3846747.82      10057762.8
#Sta/Elev= 30
  4766.6  121.07  4788.5  120.13  4798.5  119.96  4823.6  120.28  4828.7  119.85
  4858.9  119.18    4889  119.04  4909.2  119.39  4915.9  119.15  4959.4  119.88
  4969.5  119.66  4979.6  120.13  4999.7  119.87  5008.3  120.09  5029.8   119.7
  5049.9  119.34    5060  119.55  5070.1  119.13  5080.1  118.29  5088.2  118.17
  5088.4  117.67  5091.9  117.67  5092.2  118.17  5105.6  118.55  5120.3  119.78
  5140.5  120.33  5150.5  119.84  5170.6   120.2    5198  122.09    5231  121.69
#Mann= 3 , 0 , 0
  4766.6     .11       0  5029.8     .06       0  5120.3     .11       0
Bank Sta=5029.8,5120.3
XS Rating Curve= 0 ,0
Exp/Cntr=0.3,0.1

Type RM Length L Ch R = 1 ,5910    ,629,629,629
BEGIN DESCRIPTION:
WHITE OAK CREEK WEST TRIB NO 1 12.0
END DESCRIPTION:
XS GIS Cut Line= 3
      3847237.37     10057743.76      3847013.51     10057679.11
      3846707.23      10057681.2
#Sta/Elev= 30
  4766.4  120.89  4767.9  120.89  4776.3  120.59    4793  120.72  4826.7  119.73
  4831.9  120.43  4849.2  118.95  4859.6  118.64  4880.4  118.53  4890.8  118.86
  4899.1  118.21  4904.3  118.44  4911.6   117.8    4922     118  4932.4  117.49
  4999.4  117.83  5013.1  117.19  5013.3  116.69  5016.8  116.69  5017.1  117.19
  5025.1  117.45  5045.1  117.33  5075.1   117.8  5095.1  118.82  5145.1  119.16
  5245.1  122.02  5255.1  121.68  5285.1  122.26  5295.1  123.51  5305.7  123.78
#Mann= 4 ,-1 , 0
  4766.4     .17       0  4767.9     .11       0  4890.8     .06       0
  5095.1     .11       0
Bank Sta=4890.8,5095.1
XS Rating Curve= 0 ,0
Exp/Cntr=0.3,0.1

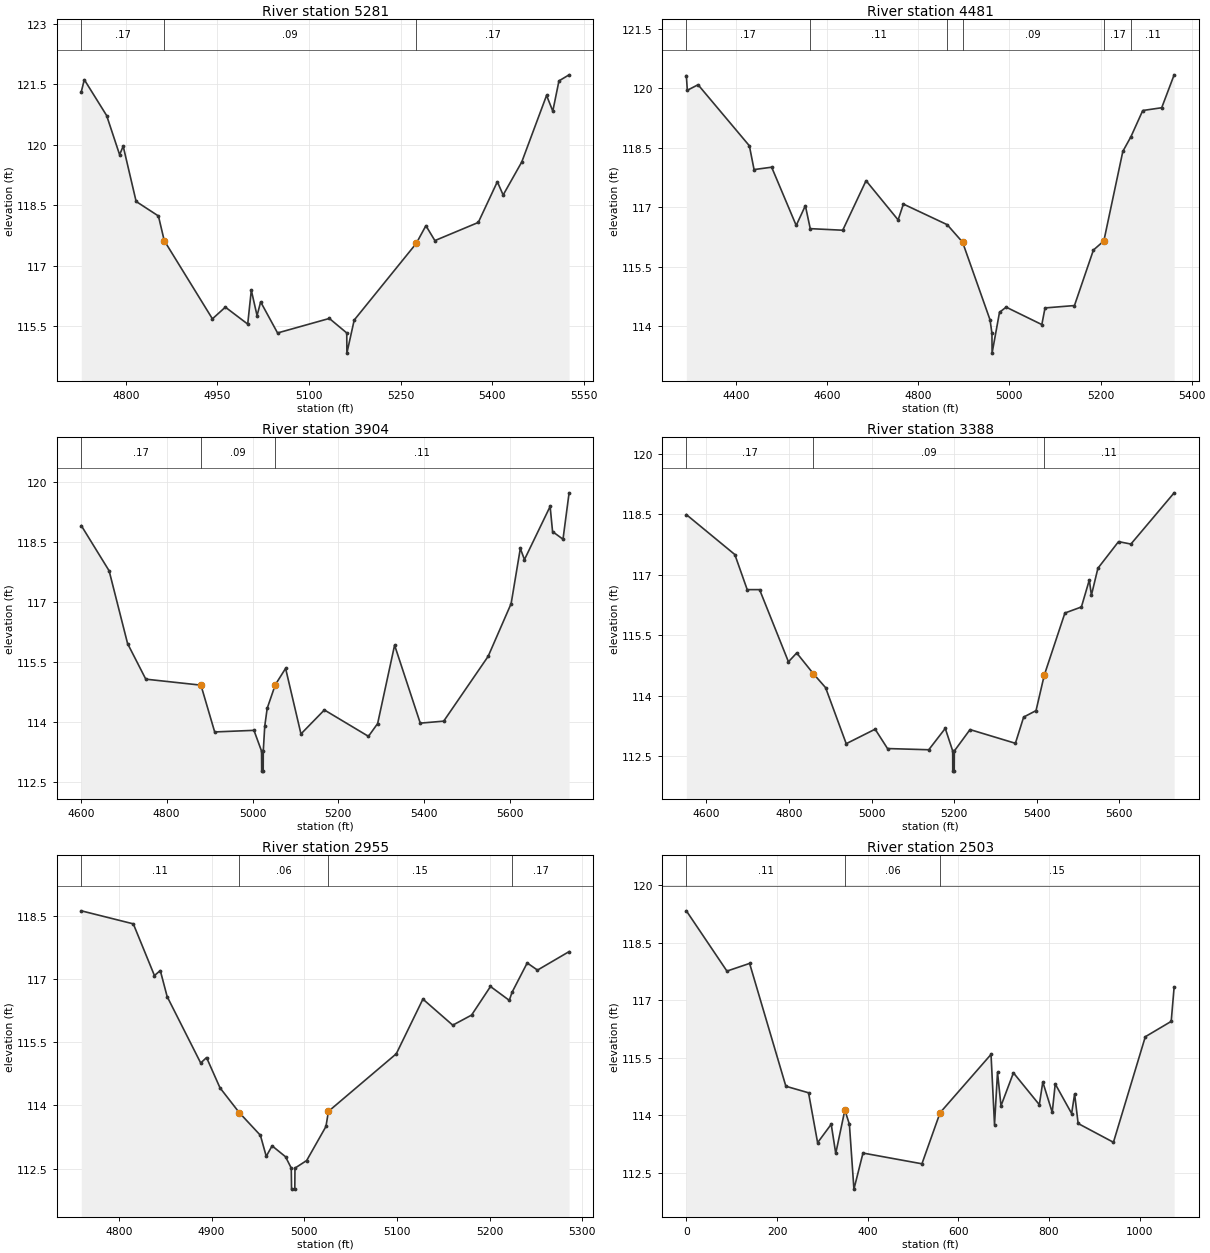
Type RM Length L Ch R = 1 ,5281    ,800,800,800
BEGIN DESCRIPTION:
WHITE OAK CREEK WEST TRIB NO 1 11.0
END DESCRIPTION:
XS GIS Cut Line= 3
      3847453.33     10057231.01      3847179.06     10057059.16
      3846711.56     10056974.32
#Sta/Elev= 30
  4727.2  121.31  4732.1  121.61  4768.7  120.72  4789.9  119.75  4795.8  119.96
    4817  118.59  4853.5  118.23    4863  117.62  4941.9  115.68  4963.1  115.97
  4999.7  115.55  5005.6  116.39    5015  115.76  5020.9   116.1  5048.6  115.33
  5133.4  115.69  5161.9  115.33  5162.1  114.83  5174.1  115.65  5275.7  117.55
  5291.5  117.99  5306.2  117.62  5377.3  118.07  5408.5  119.08    5418  118.75
  5448.5  119.57  5489.1  121.22  5499.3  120.83  5509.4  121.58    5526  121.73
#Mann= 3 , 0 , 0
  4727.2     .17       0    4863     .09       0  5275.7     .17       0
Bank Sta=4863,5275.7
XS Rating Curve= 0 ,0
Exp/Cntr=0.3,0.1

Type RM Length L Ch R = 1 ,4481    ,577,577,577
BEGIN DESCRIPTION:
WHITE OAK CREEK WEST TRIB NO 1 10.0
END DESCRIPTION:
XS GIS Cut Line= 3
      3847753.72     10057026.19       3847618.3     10056411.59
      3847265.92       10056146.
#Sta/Elev= 30
    4291  120.32  4293.1  119.95  4316.7  120.09  4429.3  118.55  4439.6  117.95
  4478.2  118.01  4532.1  116.54  4552.2  117.04  4562.9  116.46  4634.2  116.42
  4685.4  117.67  4755.8  116.68  4767.3  117.08  4863.5  116.56  4897.2  116.12
  4957.5  114.16  4961.7  113.82    4962  113.32  4978.3  114.35  4992.9  114.48
  5071.2  114.04  5078.2  114.46  5142.8  114.52  5184.4  115.92  5207.3  116.15
    5249  118.41  5266.8  118.78  5292.7  119.44  5334.3  119.51  5361.6  120.34
#Mann= 6 ,-1 , 0
    4291     .17       0  4562.9     .11       0  4863.5     .17       0
  4897.2     .09       0  5207.3     .17       0  5266.8     .11       0
Bank Sta=4897.2,5207.3
XS Rating Curve= 0 ,0
Exp/Cntr=0.3,0.1

Type RM Length L Ch R = 1 ,3904    ,516,516,516
BEGIN DESCRIPTION:
WHITE OAK CREEK WEST TRIB NO 1 9.0
END DESCRIPTION:
XS GIS Cut Line= 3
      3848137.39       10056422.      3847995.88     10056044.75
      3847311.95     10055780.01
#Sta/Elev= 30
  4601.2   118.9    4666  117.77    4709  115.95  4751.4  115.06  4879.9  114.91
  4911.9  113.74  5003.4  113.78  5021.1  113.26  5021.4  112.76  5024.9  112.76
  5025.1  113.26  5028.5  113.88  5034.2  114.33  5053.1  114.92  5077.1  115.33
  5112.9  113.69  5167.4  114.29  5270.1  113.63  5291.5  113.95    5331  115.91
  5390.8  113.96  5445.4  114.01  5548.9  115.63  5602.5  116.95  5623.9  118.33
  5633.5  118.05  5693.3  119.38    5699  118.75  5723.3  118.56  5737.5  119.72
#Mann= 3 , 0 , 0
  4601.2     .17       0  4879.9     .09       0  5053.1     .11       0
Bank Sta=4879.9,5053.1
XS Rating Curve= 0 ,0
Exp/Cntr=0.3,0.1

Type RM Length L Ch R = 1 ,3388    ,433,433,433
BEGIN DESCRIPTION:
WHITE OAK CREEK WEST TRIB NO 1 8.0
END DESCRIPTION:
XS GIS Cut Line= 3
      3848375.24     10056168.55      3848366.56     10055717.15
      3848375.24     10054986.28
#Sta/Elev= 30
  4551.2  118.49  4668.7   117.5  4698.7  116.63  4728.7  116.63  4798.7  114.84
  4818.7  115.06  4858.7  114.55  4888.7   114.2  4938.7  112.81  5008.8  113.17
  5038.8  112.69  5138.8  112.66  5178.8  113.19  5196.8  112.63    5197  112.13
  5200.5  112.13  5200.8  112.63  5238.8  113.16  5348.8  112.82  5368.8  113.47
  5398.8  113.63  5418.8  114.51  5468.8  116.05  5508.8   116.2    5528  116.87
    5533  116.49  5548.8  117.16  5598.8  117.82  5628.8  117.76  5733.6  119.03
#Mann= 3 , 0 , 0
  4551.2     .17       0  4858.7     .09       0  5418.8     .11       0
Bank Sta=4858.7,5418.8
XS Rating Curve= 0 ,0
Exp/Cntr=0.3,0.1

Type RM Length L Ch R = 1 ,2955    ,435,435,435
BEGIN DESCRIPTION:
WHITE OAK CREEK WEST TRIB NO 1 7.0
END DESCRIPTION:
XS GIS Cut Line= 3
      3848394.31     10056217.17      3848607.26     10056054.38
      3848861.37     10056008.81
#Sta/Elev= 30
  4759.5  118.63  4815.6  118.32  4838.4  117.09  4844.7  117.21  4852.1  116.59
  4888.3  115.01  4894.6  115.14  4909.1  114.42  4929.9  113.83  4952.7  113.29
    4959  112.79  4965.3  113.04  4979.8  112.78    4986  112.51  4986.3  112.01
  4989.8  112.01    4990  112.51  5002.6  112.69  5023.4   113.5  5026.1  113.86
  5099.3  115.23    5128  116.53  5160.2  115.91  5180.5  116.15  5200.9  116.83
  5221.2   116.5  5224.1  116.69  5240.5  117.39  5251.6  117.22  5285.7  117.66
#Mann= 4 ,-1 , 0
  4759.5     .11       0  4929.9     .06       0  5026.1     .15       0
  5224.1     .17       0
Bank Sta=4929.9,5026.1
XS Rating Curve= 0 ,0
Exp/Cntr=0.3,0.1

Type RM Length L Ch R = 1 ,2503    ,126,126,126
XS GIS Cut Line= 3
      3848428.34     10056400.02       3849062.3     10056409.36
      3849397.79     10056121.77
#Sta/Elev= 30
       0  119.33    89.5  117.76   139.5  117.96   219.5  114.76   269.5  114.59
   289.5  113.29   319.5  113.77   329.5  113.01   349.6  114.14   359.6  113.77
   369.6  112.08   389.6  113.02   519.6  112.74   559.6  114.07     672  115.59
   679.7  113.76   686.3  115.12     694  114.25   721.4  115.11   778.5  114.28
   786.2  114.87     807  114.08   813.6  114.82   849.8  114.05   856.4  114.56
   864.1  113.79     942   113.3  1012.3  116.05  1069.4  116.45  1075.9  117.35
#Mann= 3 , 0 , 0
       0     .11       0   349.6     .06       0   559.6     .15       0
Bank Sta=349.6,559.6
XS Rating Curve= 0 ,0
Exp/Cntr=0.3,0.1

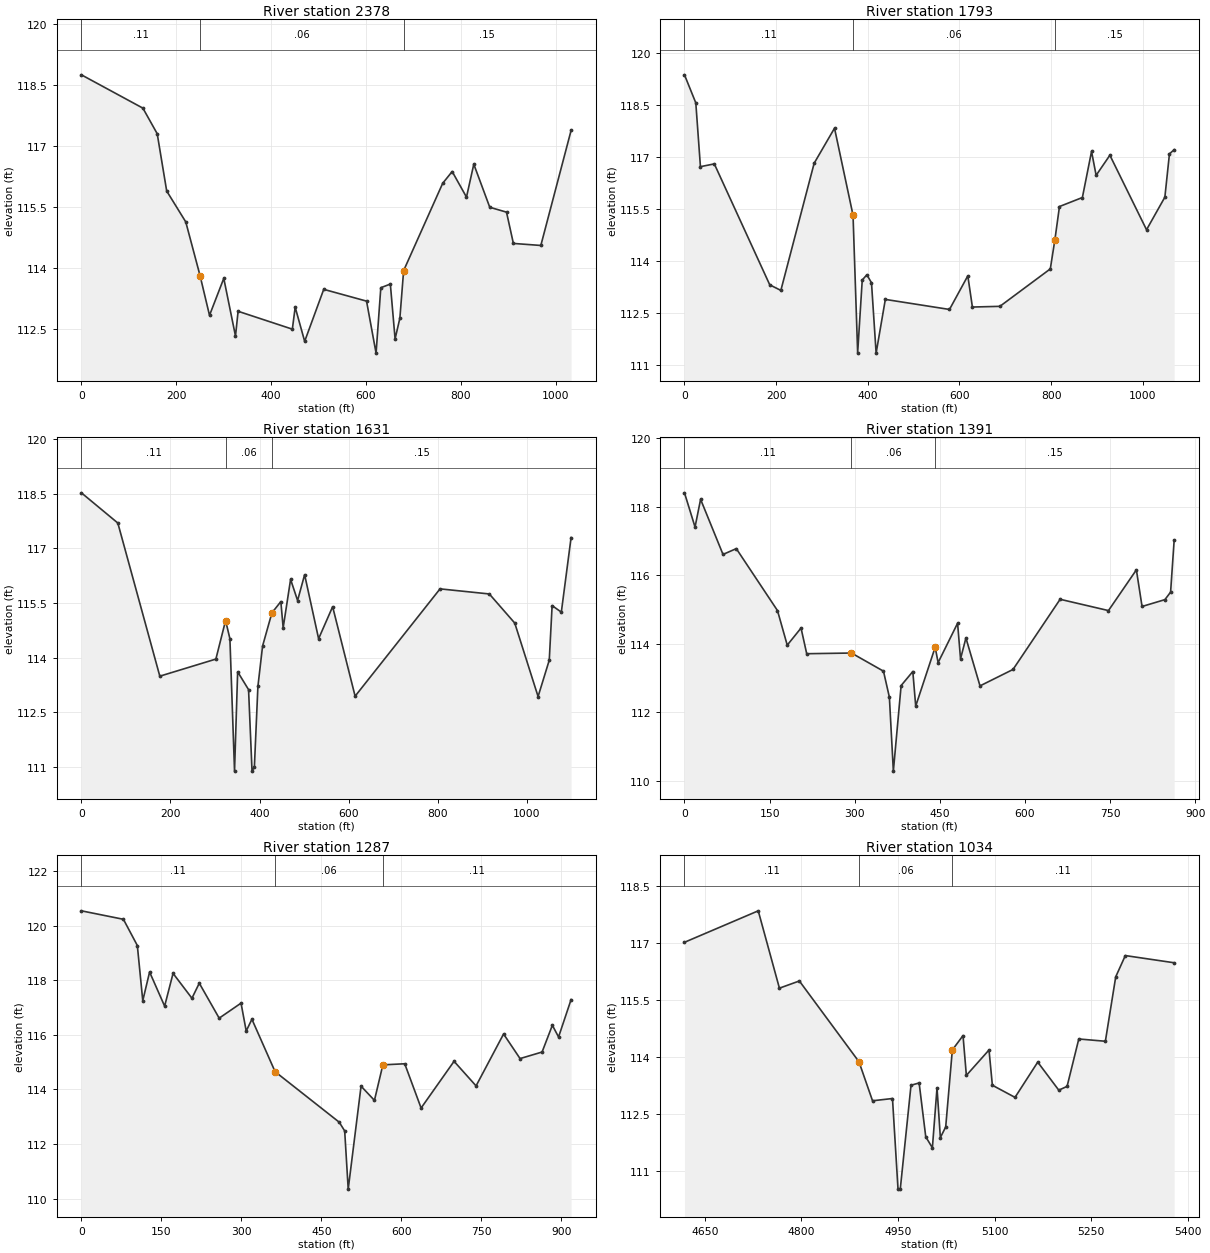
Type RM Length L Ch R = 1 ,2378    ,560,560,560
XS GIS Cut Line= 3
      3848468.56     10056478.86      3849293.65     10056548.26
      3849418.96     10056710.25
#Sta/Elev= 30
       0  118.75   129.7  117.93   159.9   117.3   179.9  115.89   220.1  115.13
   250.2  113.81   270.2  112.83   300.3  113.74     325  112.32   330.5  112.93
   444.9  112.49   450.9  113.03   470.9  112.19   511.1  113.47   601.4  113.18
   621.5   111.9   631.5  113.51   651.6   113.6   661.6  112.25   671.7  112.76
   679.6  113.93     762  116.08     782  116.37   812.2  115.74   827.6  116.55
   861.3  115.49   896.6  115.37   911.1   114.6     969  114.55  1032.8  117.38
#Mann= 3 , 0 , 0
       0     .11       0   250.2     .06       0   679.6     .15       0
Bank Sta=250.2,679.6
XS Rating Curve= 0 ,0
Exp/Cntr=0.3,0.1

Type RM Length L Ch R = 1 ,1793    ,188,188,188
XS GIS Cut Line= 3
       3848683.4     10056958.03      3849104.99     10057015.02
      3849748.11     10057011.72
#Sta/Elev= 30
       0  119.37    24.7  118.56    34.8  116.72    65.1   116.8   186.1  113.31
   210.3  113.15     283  116.82   327.4  117.83   367.8  115.32   377.9  111.35
   387.9  113.45     398   113.6   408.1  113.37   418.2  111.34   438.3  112.89
   578.3   112.6   618.3  113.57   628.3  112.67   688.3  112.69   798.3  113.77
   808.3  114.61   818.3  115.57   868.3  115.83   888.3  117.16   898.3  116.47
   928.3  117.05  1008.3   114.9  1048.3  115.84  1058.3  117.09  1068.6  117.21
#Mann= 3 , 0 , 0
       0     .11       0   367.8     .06       0   808.3     .15       0
Bank Sta=367.8,808.3
XS Rating Curve= 0 ,0
Exp/Cntr=0.3,0.1

Type RM Length L Ch R = 1 ,1631    ,214,214,214
XS GIS Cut Line= 2
      3848719.89      10057079.8      3849768.47     10057411.19
#Sta/Elev= 30
       0  118.53    81.8   117.7   176.1  113.49     302  113.96   323.8  115.02
   333.5  114.52   343.9  110.88   350.9  113.61   375.4  113.12   383.2  110.88
   388.5     111   396.4  113.21   406.9  114.32   427.8  115.23   447.9  115.54
   453.1  114.82   469.8  116.15   485.5  115.57   501.3  116.28   532.7  114.52
   564.2   115.4   614.7  112.94   805.4  115.89   916.1  115.75   973.2  114.95
  1025.6  112.93  1050.7  113.93  1057.1  115.43  1077.8  115.25  1099.7   117.3
#Mann= 3 , 0 , 0
       0     .11       0   323.8     .06       0   427.8     .15       0
Bank Sta=323.8,427.8
XS Rating Curve= 0 ,0
Exp/Cntr=0.3,0.1

Type RM Length L Ch R = 1 ,1391    ,104,104,104
XS GIS Cut Line= 3
      3848719.89     10057307.23      3849472.68     10057515.98
      3849481.69     10057598.49
#Sta/Elev= 30
       0  118.41    18.6  117.41    28.4  118.22    67.9  116.61    91.3  116.78
   163.9  114.97   181.1  113.96   205.4  114.46   215.4  113.71   294.3  113.73
   350.7   113.2   361.1  112.44   368.1  110.28   381.8  112.78   402.4  113.19
   407.5  112.18   441.8   113.9     447  113.45   481.3   114.6   486.5  113.56
     496  114.17   520.8  112.77     579  113.25     662   115.3   747.2  114.97
   796.4  116.16   806.4  115.09   846.7  115.29   856.7  115.51     863  117.03
#Mann= 3 , 0 , 0
       0     .11       0   294.3     .06       0   441.8     .15       0
Bank Sta=294.3,441.8
XS Rating Curve= 0 ,0
Exp/Cntr=0.3,0.1

Type RM Length L Ch R = 1 ,1287    ,253,253,253
XS GIS Cut Line= 3
      3848575.33     10057399.44      3849204.24     10057536.16
      3849470.62     10057603.75
#Sta/Elev= 30
       0  120.54    78.8  120.23   104.9  119.27   115.1  117.25   127.9   118.3
   156.1  117.05   171.9  118.25   207.3  117.34   221.1  117.89   258.4  116.61
   299.4  117.16   309.1  116.14   319.8  116.57   363.3  114.65   483.6   112.8
   493.8  112.48   500.4  110.35   524.5  114.12   549.6   113.6   565.4   114.9
   606.4  114.94   637.1  113.32   698.9  115.03   740.2  114.13   791.8  116.03
   822.7  115.13     864  115.37   883.3  116.35   894.9  115.92   918.4  117.29
#Mann= 3 , 0 , 0
       0     .11       0   363.3     .06       0   565.4     .11       0
Bank Sta=363.3,565.4
XS Rating Curve= 0 ,0
Exp/Cntr=0.3,0.1

Type RM Length L Ch R = 1 ,1034    ,127,127,127
BEGIN DESCRIPTION:
Mapping XS ffaafa4c
END DESCRIPTION:
XS GIS Cut Line= 2
      3848685.17     10057656.19      3849421.27      10057848.9
#Sta/Elev= 30
  4618.2  117.02  4732.8  117.85  4765.7  115.81  4796.7     116  4889.3  113.87
  4910.4  112.84  4941.4   112.9    4950  110.51  4953.5  110.51  4970.2  113.25
  4982.8  113.31  4993.1  111.89  5003.4   111.6  5010.6  113.18  5015.8  111.87
  5024.1  112.15  5034.4  114.18    5051  114.56  5056.2  113.51  5091.4  114.18
  5096.6  113.25  5131.8  112.93  5167.1  113.86  5199.8  113.12  5212.7  113.22
  5230.9  114.47  5272.2  114.41  5288.3  116.11  5303.2  116.67  5379.1  116.48
#Mann= 3 , 0 , 0
  4618.2     .11       0  4889.3     .06       0  5034.4     .11       0
Bank Sta=4889.3,5034.4
XS Rating Curve= 0 ,0
Exp/Cntr=0.3,0.1

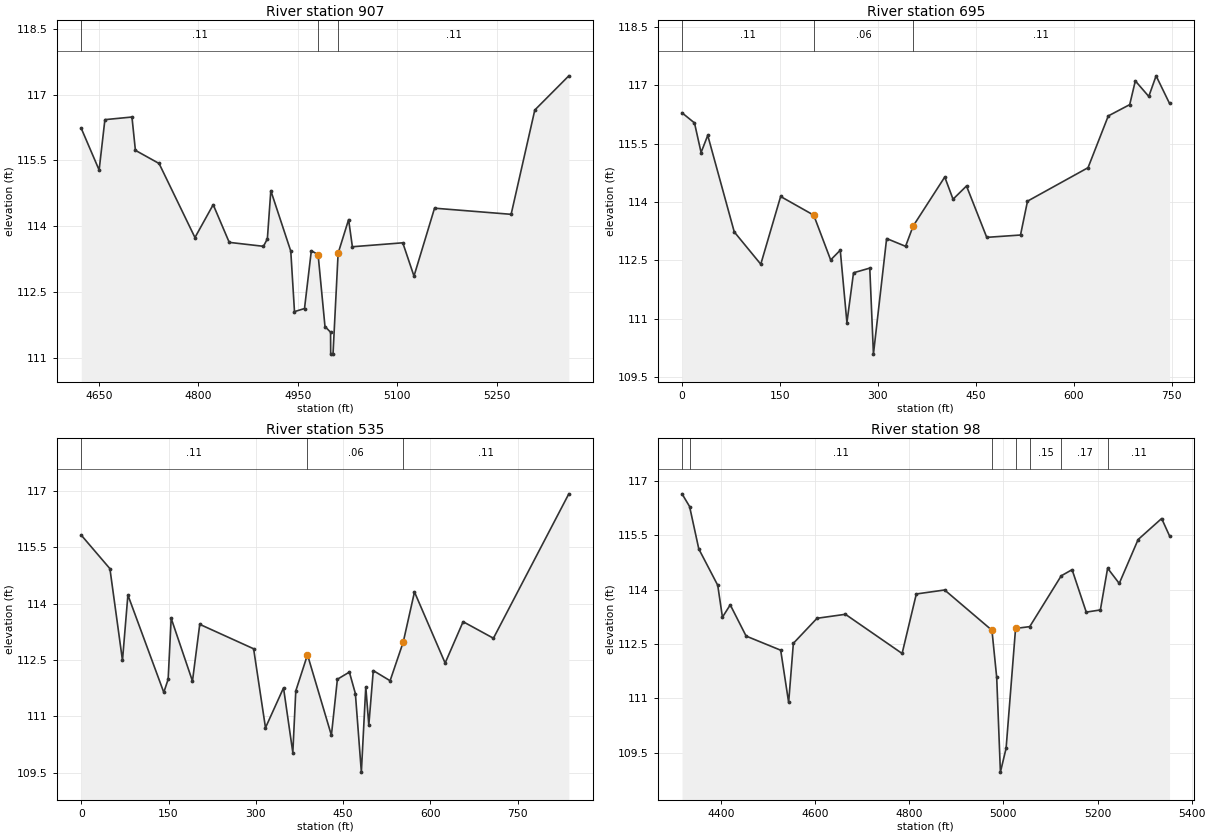
Type RM Length L Ch R = 1 ,907     ,212,212,212
BEGIN DESCRIPTION:
Mapping XS 1711f5b2
END DESCRIPTION:
XS GIS Cut Line= 2
      3848681.74     10057786.41      3849394.06     10057968.39
#Sta/Elev= 30
  4623.3  116.23  4650.2  115.28  4658.9  116.43  4699.7  116.49  4704.9  115.73
  4740.6  115.43  4794.7  113.74  4822.2  114.49  4846.4  113.63    4898  113.54
  4903.9  113.71  4909.1  114.81  4939.2  113.43  4944.8  112.05  4959.9  112.12
  4970.2  113.44  4980.4  113.35  4990.8  111.71  4999.2  111.58  4999.4  111.08
  5002.9  111.08  5010.6 113.381  5026.4  114.15  5032.1  113.53  5108.1  113.62
    5125  112.86    5156  114.41  5271.5  114.27  5307.2  116.65  5358.5  117.43
#Mann= 3 , 0 , 0
  4623.3     .11       0  4980.4     .06       0  5010.6     .11       0
Bank Sta=4980.4,5010.6
XS Rating Curve= 0 ,0
Exp/Cntr=0.3,0.1

Type RM Length L Ch R = 1 ,695     ,161,161,161
XS GIS Cut Line= 3
      3848739.04      10058037.4      3849140.43     10058106.47
      3849468.56     10058192.41
#Sta/Elev= 30
       0  116.29    19.1  116.03    29.2  115.27    39.4  115.71      80  113.23
   120.6   112.4     151  114.14   201.7  113.66   227.6  112.51   242.3  112.76
   252.5   110.9   262.6  112.18   287.5   112.3   293.1  110.09   313.3  113.06
   342.3  112.86   353.9  113.38   402.3  114.64     415  114.07   435.6  114.41
   466.6  113.09   518.3  113.15     529  114.02   621.7  114.88   652.7  116.21
   685.5   116.5   694.1  117.11   714.7  116.71   725.9  117.24   746.5  116.53
#Mann= 3 , 0 , 0
       0     .11       0   201.7     .06       0   353.9     .11       0
Bank Sta=201.7,353.9
XS Rating Curve= 0 ,0
Exp/Cntr=0.3,0.1

Type RM Length L Ch R = 1 ,535     ,437,437,437
XS GIS Cut Line= 2
      3848620.02     10058130.36      3849436.12     10058328.04
#Sta/Elev= 30
       0  115.82    49.2  114.93    70.8  112.49    80.1  114.23   141.8  111.64
   149.3  111.99   154.5  113.61   191.1  111.94   203.6  113.45   296.2   112.8
   316.6   110.7   347.6  111.76   363.6  110.04   368.7  111.68   388.8  112.64
   429.9   110.5   440.2  111.99   460.8  112.18   471.1  111.61   481.4  109.52
     489  111.79   494.2  110.77   501.9  112.22   530.8  111.95   553.4  112.98
   572.7  114.31   625.4  112.42   656.3  113.52   708.4  113.08     838  116.92
#Mann= 3 , 0 , 0
       0     .11       0   388.8     .06       0   553.4     .11       0
Bank Sta=388.8,553.4
XS Rating Curve= 0 ,0
Exp/Cntr=0.3,0.1

Type RM Length L Ch R = 1 ,98      ,0,0,0
BEGIN DESCRIPTION:
WHITE OAK CREEK WEST TRIB NO 1 1.0
END DESCRIPTION:
XS GIS Cut Line= 3
      3848472.31     10058596.04      3849152.13     10058661.88
      3849504.59     10058681.27
#Sta/Elev= 30
    4317  116.64  4333.1  116.29  4352.7  115.12  4392.9  114.12  4402.9  113.24
  4419.5  113.58  4453.2  112.72  4526.7  112.33  4543.6  110.89  4553.6  112.52
  4603.9  113.21  4664.2  113.32  4784.7  112.24  4814.9  113.88  4875.1  113.99
  4975.6  112.88  4985.7  111.58  4993.6  108.97  5005.7  109.63  5025.8  112.93
  5055.9  112.98  5122.8  114.38  5145.9  114.55    5176  113.38    5206  113.44
  5221.4  114.59  5246.1  114.17  5286.2  115.38  5336.2  115.96    5353  115.48
#Mann= 7 ,-1 , 0
    4317    .125       0  4333.1     .11       0  4975.6     .09       0
  5025.8     .11       0  5055.9     .15       0  5122.8     .17       0
  5221.4     .11       0
Bank Sta=4975.6,5025.8
XS Rating Curve= 0 ,0
Exp/Cntr=0.3,0.1

Chan Stop Cuts=-1
Use User Specified Reach Order=0
Composite Channel Slope=5

--- WHITE OAK CREEK WEST TRIB NO 1.g10 (geometry) ---

Geom Title=Existing Conditions
Program Version=4.10

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
River Reach=WHITE OAK CREEK ,Reach-1

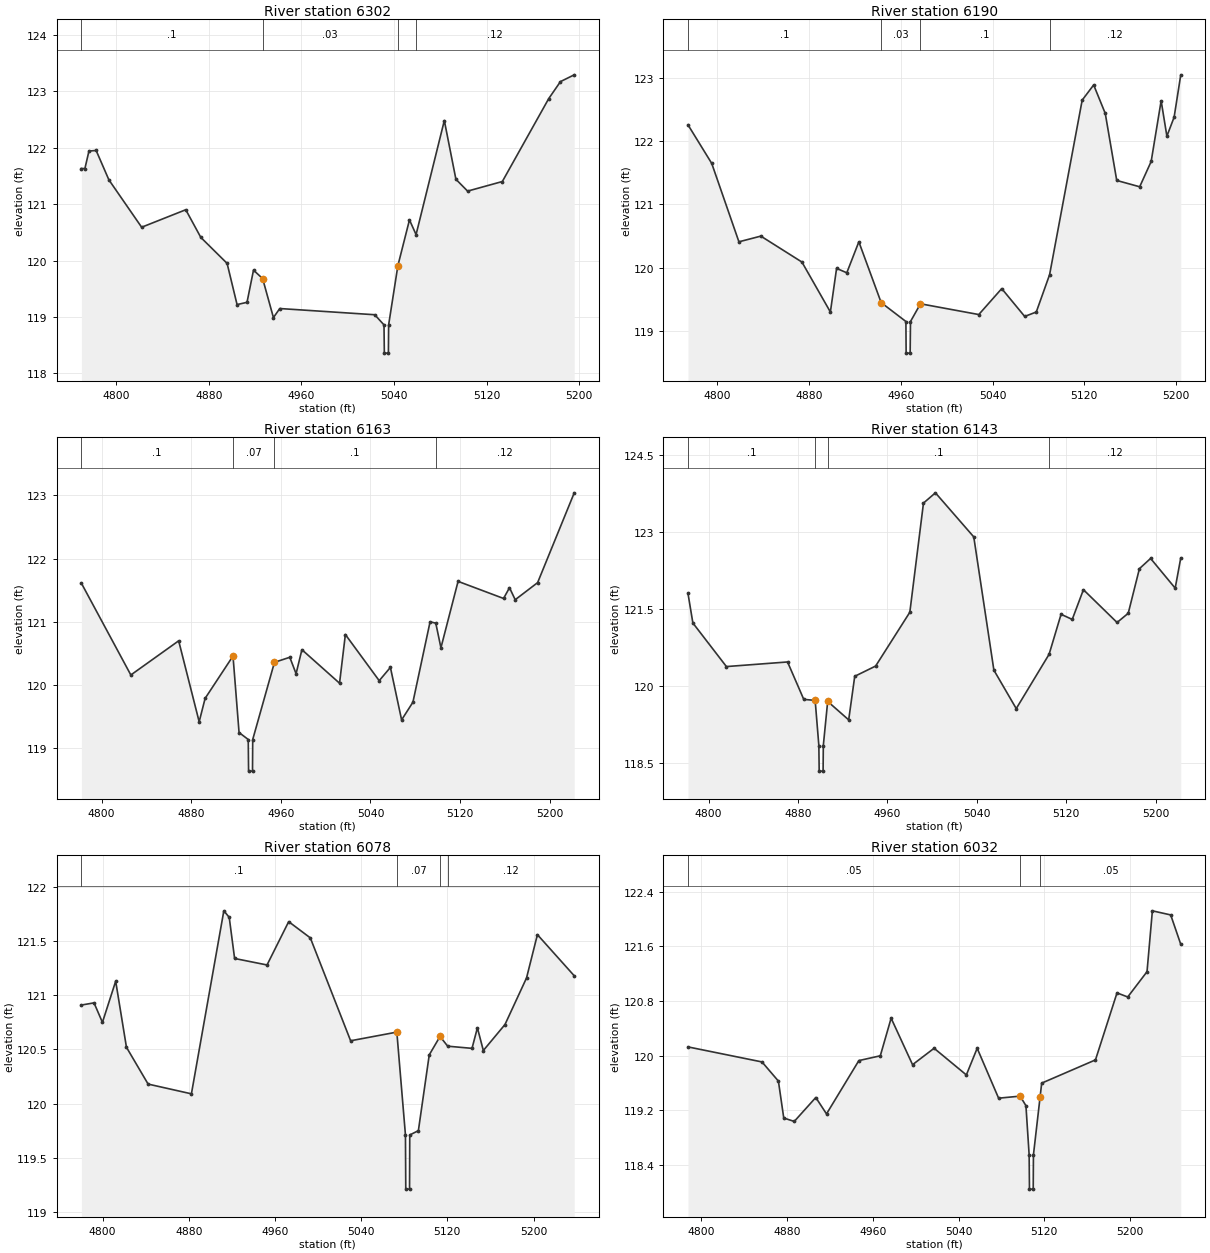
Type RM Length L Ch R = 1 ,6302    ,112,112,112
BEGIN DESCRIPTION:
WHITE OAK CREEK WEST TRIB NO 1 14.0
END DESCRIPTION:
XS GIS Cut Line= 3
      3847099.31      10058148.6      3846894.87     10058051.81
      3846695.94     10058065.52
#Sta/Elev= 30
  4770.1  121.63  4773.1  121.63  4776.6  121.94  4782.8  121.95  4793.8  121.43
  4822.1  120.59  4860.2   120.9  4873.2  120.41  4895.9  119.95  4904.5  119.22
  4913.1  119.26  4918.7  119.83  4926.6  119.68  4935.9  118.99  4941.4  119.15
  5023.4  119.04  5031.4  118.86  5031.7  118.36  5035.2  118.36  5035.4  118.86
  5043.4  119.91  5053.4  120.72  5059.1  120.46  5083.5  122.48  5093.5  121.44
  5103.6  121.23  5133.6   121.4  5173.7  122.87  5183.8  123.17  5195.7  123.29
#Mann= 4 ,-1 , 0
  4770.1      .1       0  4926.6     .03       0  5043.4      .1       0
  5059.1     .12       0
Bank Sta=4926.6,5043.4
XS Rating Curve= 0 ,0
Exp/Cntr=0.3,0.1

Type RM Length L Ch R = 1 ,6190    ,27,27,27
BEGIN DESCRIPTION:
Mapping XS 726f963b
END DESCRIPTION:
XS GIS Cut Line= 3
      3847137.25     10058020.75      3846937.15     10057944.81
      3846722.11     10057956.82
#Sta/Elev= 30
  4774.6  122.26  4795.3  121.65    4819  120.41  4838.1   120.5  4873.9  120.09
  4898.7   119.3  4904.1  119.99    4913  119.92  4923.5  120.41 4942.94 119.449
  4964.5  119.15  4964.7  118.65  4968.2  118.65  4968.5  119.15  4977.2  119.43
    5028  119.26    5048  119.67    5068  119.23  5078.1   119.3  5089.7  119.89
  5118.1  122.65  5128.1  122.89  5138.2  122.44  5148.2  121.38  5168.2  121.28
  5178.2  121.68  5186.9  122.64  5191.9  122.08  5198.2  122.38    5204  123.05
#Mann= 4 ,-1 , 0
  4774.6      .1       0 4942.94     .03       0  4977.2      .1       0
  5089.7     .12       0
Bank Sta=4942.94,4977.2
XS Rating Curve= 0 ,0
Exp/Cntr=0.3,0.1

Type RM Length L Ch R = 1 ,6163    ,20,20,20
BEGIN DESCRIPTION:
WHITE OAK CREEK WEST TRIB NO 1 13.0
END DESCRIPTION:
XS GIS Cut Line= 5
      3847139.17     10057993.73      3846966.98     10057929.16
      3846901.01     10057910.06      3846842.33     10057914.58
      3846715.55     10057935.37
#Sta/Elev= 30
    4782  121.61  4826.1  120.16  4868.8   120.7  4887.1  119.42  4892.4  119.79
  4917.3  120.46  4922.7  119.25  4930.9  119.14  4931.2  118.64  4934.7  118.64
  4934.9  119.14  4954.3  120.36    4968  120.44  4973.6  120.18  4978.8  120.56
  5012.4  120.03  5017.6   120.8  5047.8  120.07  5057.8  120.28  5067.8  119.45
  5077.9  119.73  5093.2     121  5098.3  120.98  5102.9  120.59  5118.2  121.64
  5158.8  121.37  5164.1  121.54  5169.2  121.35  5189.2  121.62  5221.9  123.04
#Mann= 4 ,-1 , 0
    4782      .1       0  4917.3     .07       0  4954.3      .1       0
  5098.3     .12       0
Bank Sta=4917.3,4954.3
XS Rating Curve= 0 ,0
Exp/Cntr=0.3,0.1

Type RM Length L Ch R = 1 ,6143    ,65,65,65
BEGIN DESCRIPTION:
Mapping XS 0180626a
END DESCRIPTION:
XS GIS Cut Line= 3
      3847144.56     10057978.58      3846905.81     10057886.94
      3846720.89     10057896.48
#Sta/Elev= 30
  4781.5  121.81  4785.9  121.23  4815.9  120.38  4870.6  120.47  4885.1  119.74
  4895.3  119.72  4898.6  118.84  4898.9  118.34  4902.4  118.34  4902.6  118.84
  4906.5   119.7  4925.3  119.34  4930.7  120.19  4949.4  120.39    4980  121.44
  4992.2  123.57  5002.9  123.77  5037.2  122.91  5055.2  120.31  5075.2  119.56
  5104.6  120.62  5115.3   121.4  5125.3   121.3  5135.3  121.88  5165.4  121.24
  5175.4  121.42  5185.4  122.29  5195.4  122.49  5217.4  121.91  5222.4   122.5
#Mann= 4 ,-1 , 0
  4781.5      .1       0  4895.3     .07       0  4906.5      .1       0
  5104.6     .12       0
Bank Sta=4895.3,4906.5
XS Rating Curve= 0 ,0
Exp/Cntr=0.3,0.1

Type RM Length L Ch R = 1 ,6078    ,46,46,46
BEGIN DESCRIPTION:
Mapping XS 807c3946
END DESCRIPTION:
XS GIS Cut Line= 2
      3847179.52     10057858.01      3846723.75     10057818.22
#Sta/Elev= 30
  4780.3  120.91    4792  120.93  4799.8  120.75  4812.1  121.13  4822.1  120.52
  4842.2  120.18  4882.4  120.09  4912.5  121.78  4917.5  121.72  4922.5  121.34
  4952.6  121.28  4972.7  121.68  4992.8  121.53  5030.2  120.58  5073.1  120.66
  5081.1  119.71  5081.4  119.21  5084.9  119.21  5085.1  119.71  5093.1  119.75
  5103.2  120.45  5113.2  120.62  5120.3  120.53  5142.9  120.51  5147.9   120.7
  5153.4  120.49  5173.5  120.73  5193.5  121.16  5203.6  121.56  5237.8  121.18
#Mann= 4 ,-1 , 0
  4780.3      .1       0  5073.1     .07       0  5113.2      .1       0
  5120.3     .12       0
Bank Sta=5073.1,5113.2
XS Rating Curve= 0 ,0
Exp/Cntr=0.3,0.1

Type RM Length L Ch R = 1 ,6032    ,122,122,122
BEGIN DESCRIPTION:
Mapping XS 6394c6b0
END DESCRIPTION:
XS GIS Cut Line= 2
      3847186.71     10057813.39      3846728.53      10057773.6
#Sta/Elev= 30
  4787.5  120.13  4856.6  119.91  4871.9  119.63  4876.9  119.09  4886.7  119.04
  4906.8  119.39  4916.8  119.15    4947  119.93    4967     120  4977.1  120.55
  4997.1  119.87  5017.2  120.11  5047.3  119.72  5057.4  120.11  5077.4  119.38
  5097.5  119.41  5102.9  119.27  5105.9  118.55  5106.2  118.05  5109.7  118.05
  5109.9  118.55 5116.14 119.401  5117.6   119.6  5167.8  119.94  5187.9  120.92
  5197.9  120.86  5215.9  121.23  5220.9  122.12    5238  122.06  5247.4  121.63
#Mann= 3 , 0 , 0
  4787.5     .05       0  5097.5     .07       0 5116.14     .05       0
Bank Sta=5097.5,5116.14
XS Rating Curve= 0 ,0
Exp/Cntr=0.3,0.1