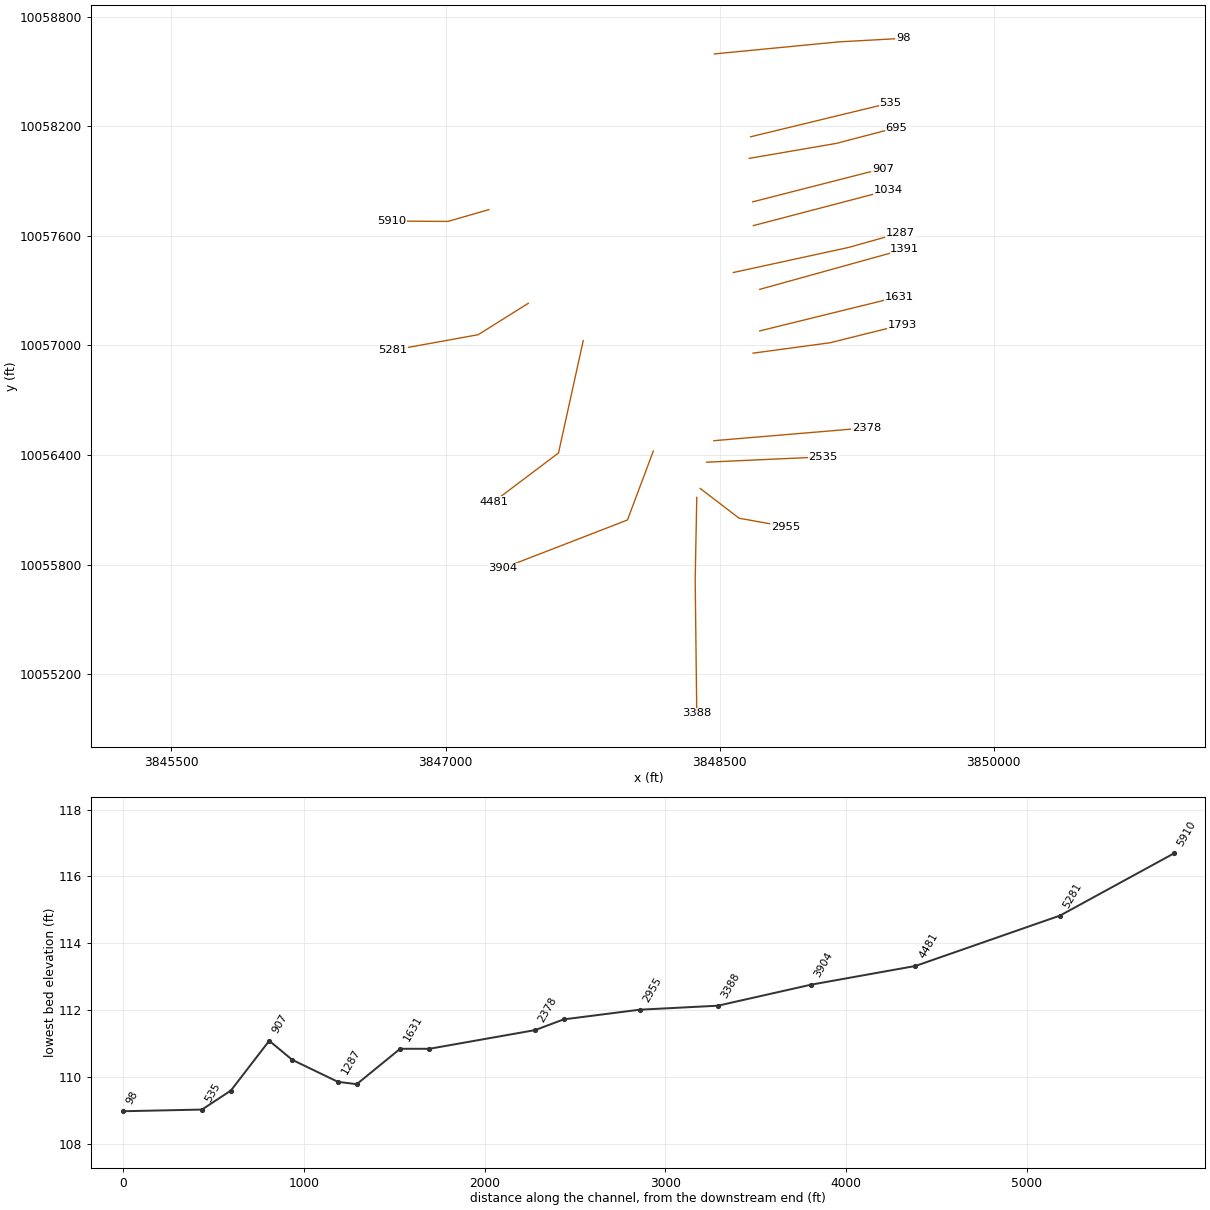
HEC-RAS study WHITE OAK CREEK WEST TRIB NO 1.prj: WHITE OAK CREEK WEST TRIB NO 1 Base Level Engineering

--- WHITE OAK CREEK WEST TRIB NO 1.g10 (geometry) --- (continued)

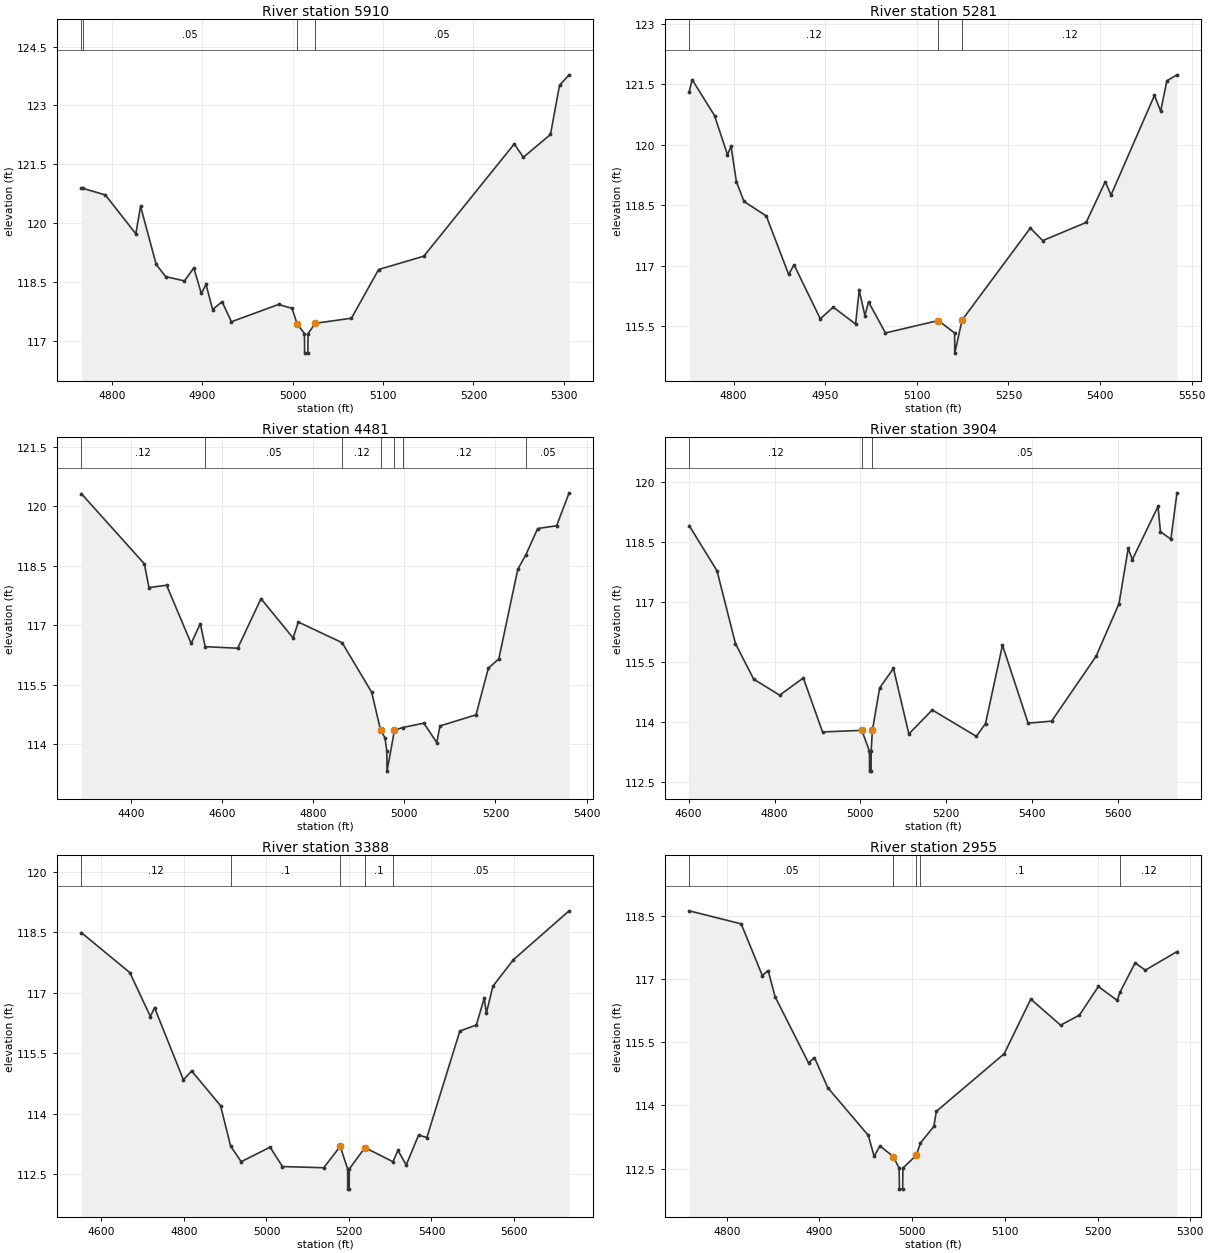
Type RM Length L Ch R = 1 ,5910    ,629,629,629
BEGIN DESCRIPTION:
WHITE OAK CREEK WEST TRIB NO 1 12.0
END DESCRIPTION:
XS GIS Cut Line= 3
      3847237.37     10057743.76      3847013.51     10057679.11
      3846707.23      10057681.2
#Sta/Elev= 30
  4766.4  120.89  4767.9  120.89    4793  120.72  4826.7  119.73  4831.9  120.43
  4849.2  118.95  4859.6  118.64  4880.4  118.53  4890.8  118.86  4899.1  118.21
  4904.3  118.44  4911.6   117.8    4922     118  4932.4  117.49  4984.5  117.93
  4999.4  117.83  5005.1  117.43  5013.1  117.19  5013.3  116.69  5016.8  116.69
  5017.1  117.19  5025.1  117.45  5065.1  117.58  5095.1  118.82  5145.1  119.16
  5245.1  122.02  5255.1  121.68  5285.1  122.26  5295.1  123.51  5305.7  123.78
#Mann= 4 ,-1 , 0
  4766.4     .12       0  4767.9     .05       0  5005.1     .03       0
  5025.1     .05       0
Bank Sta=5005.1,5025.1
XS Rating Curve= 0 ,0
Exp/Cntr=0.3,0.1

Type RM Length L Ch R = 1 ,5281    ,800,800,800
BEGIN DESCRIPTION:
WHITE OAK CREEK WEST TRIB NO 1 11.0
END DESCRIPTION:
XS GIS Cut Line= 3
      3847453.33     10057231.01      3847179.06     10057059.16
      3846711.56     10056974.32
#Sta/Elev= 30
  4727.2  121.31  4732.1  121.61  4768.7  120.72  4789.9  119.75  4795.8  119.96
  4804.5  119.08    4817  118.59  4853.5  118.23  4890.1  116.78  4898.9  117.02
  4941.9  115.68  4963.1  115.97  4999.7  115.55  5005.6  116.39    5015  115.76
  5020.9   116.1  5048.6  115.33 5135.18 115.638  5161.9  115.33  5162.1  114.83
  5174.1  115.65  5285.8  117.93  5306.2  117.62  5377.3  118.07  5408.5  119.08
    5418  118.75  5489.1  121.22  5499.3  120.83  5509.4  121.58    5526  121.73
#Mann= 3 , 0 , 0
  4727.2     .12       0 5135.18     .07       0  5174.1     .12       0
Bank Sta=5135.18,5174.1
XS Rating Curve= 0 ,0
Exp/Cntr=0.3,0.1

Type RM Length L Ch R = 1 ,4481    ,577,577,577
BEGIN DESCRIPTION:
WHITE OAK CREEK WEST TRIB NO 1 10.0
END DESCRIPTION:
XS GIS Cut Line= 3
      3847753.72     10057026.19       3847618.3     10056411.59
      3847265.92       10056146.
#Sta/Elev= 30
    4291  120.32  4429.3  118.55  4439.6  117.95  4478.2  118.01  4532.1  116.54
  4552.2  117.04  4562.9  116.46  4634.2  116.42  4685.4  117.67  4755.8  116.68
  4767.3  117.08  4863.5  116.56  4928.3  115.31 4947.98 114.349  4957.5  114.16
  4961.7  113.82    4962  113.32  4978.3  114.35  4996.2  114.42  5042.8  114.53
  5071.2  114.04  5078.2  114.46  5157.3  114.74  5184.4  115.92  5207.3  116.15
    5249  118.41  5266.8  118.78  5292.7  119.44  5334.3  119.51  5361.6  120.34
#Mann= 7 ,-1 , 0
    4291     .12       0  4562.9     .05       0  4863.5     .12       0
 4947.98     .07       0  4978.3      .1       0  4996.2     .12       0
  5266.8     .05       0
Bank Sta=4947.98,4978.3
XS Rating Curve= 0 ,0
Exp/Cntr=0.3,0.1

Type RM Length L Ch R = 1 ,3904    ,516,516,516
BEGIN DESCRIPTION:
WHITE OAK CREEK WEST TRIB NO 1 9.0
END DESCRIPTION:
XS GIS Cut Line= 3
      3848137.39       10056422.      3847995.88     10056044.75
      3847311.95     10055780.01
#Sta/Elev= 30
  4601.2   118.9    4666  117.77    4709  115.95  4751.4  115.06    4812  114.66
  4867.1  115.09  4911.9  113.74  5003.4  113.78  5021.1  113.26  5021.4  112.76
  5024.9  112.76  5025.1  113.26 5027.95  113.78  5044.9  114.84  5077.1  115.33
  5112.9  113.69  5167.4  114.29  5270.1  113.63  5291.5  113.95    5331  115.91
  5390.8  113.96  5445.4  114.01  5548.9  115.63  5602.5  116.95  5623.9  118.33
  5633.5  118.05  5693.3  119.38    5699  118.75  5723.3  118.56  5737.5  119.72
#Mann= 3 , 0 , 0
  4601.2     .12       0  5003.4     .07       0 5027.95     .05       0
Bank Sta=5003.4,5027.95
XS Rating Curve= 0 ,0
Exp/Cntr=0.3,0.1

Type RM Length L Ch R = 1 ,3388    ,433,433,433
BEGIN DESCRIPTION:
WHITE OAK CREEK WEST TRIB NO 1 8.0
END DESCRIPTION:
XS GIS Cut Line= 3
      3848375.24     10056168.55      3848366.56     10055717.15
      3848375.24     10054986.28
#Sta/Elev= 30
  4551.2  118.49  4668.7   117.5  4718.7  116.41  4728.7  116.63  4798.7  114.84
  4818.7  115.06  4888.7   114.2  4913.1   113.2  4938.7  112.81  5008.8  113.17
  5038.8  112.69  5138.8  112.66  5178.8  113.19  5196.8  112.63    5197  112.13
  5200.5  112.13  5200.8  112.63  5238.8  113.16  5306.5  112.81  5318.8  113.09
  5338.8  112.73  5368.8  113.47  5388.8  113.41  5468.8  116.05  5508.8   116.2
    5528  116.87    5533  116.49  5548.8  117.16  5598.8  117.82  5733.6  119.03
#Mann= 5 ,-1 , 0
  4551.2     .12       0  4913.1      .1       0  5178.8     .07       0
  5238.8      .1       0  5306.5     .05       0
Bank Sta=5178.8,5238.8
XS Rating Curve= 0 ,0
Exp/Cntr=0.3,0.1

Type RM Length L Ch R = 1 ,2955    ,420,420,420
BEGIN DESCRIPTION:
WHITE OAK CREEK WEST TRIB NO 1 7.0
END DESCRIPTION:
XS GIS Cut Line= 3
      3848394.31     10056217.17      3848607.26     10056054.38
      3848861.37     10056008.81
#Sta/Elev= 30
  4759.5  118.63  4815.6  118.32  4838.4  117.09  4844.7  117.21  4852.1  116.59
  4888.3  115.01  4894.6  115.14  4909.1  114.42  4952.7  113.29    4959  112.79
  4965.3  113.04  4979.8  112.78    4986  112.51  4986.3  112.01  4989.8  112.01
    4990  112.51  5004.5 112.816    5009  113.11  5023.4   113.5  5026.1  113.86
  5099.3  115.23    5128  116.53  5160.2  115.91  5180.5  116.15  5200.9  116.83
  5221.2   116.5  5224.1  116.69  5240.5  117.39  5251.6  117.22  5285.7  117.66
#Mann= 5 ,-1 , 0
  4759.5     .05       0  4979.8     .03       0  5004.5     .05       0
    5009      .1       0  5224.1     .12       0
Bank Sta=4979.8,5004.5
XS Rating Curve= 0 ,0
Exp/Cntr=0.3,0.1

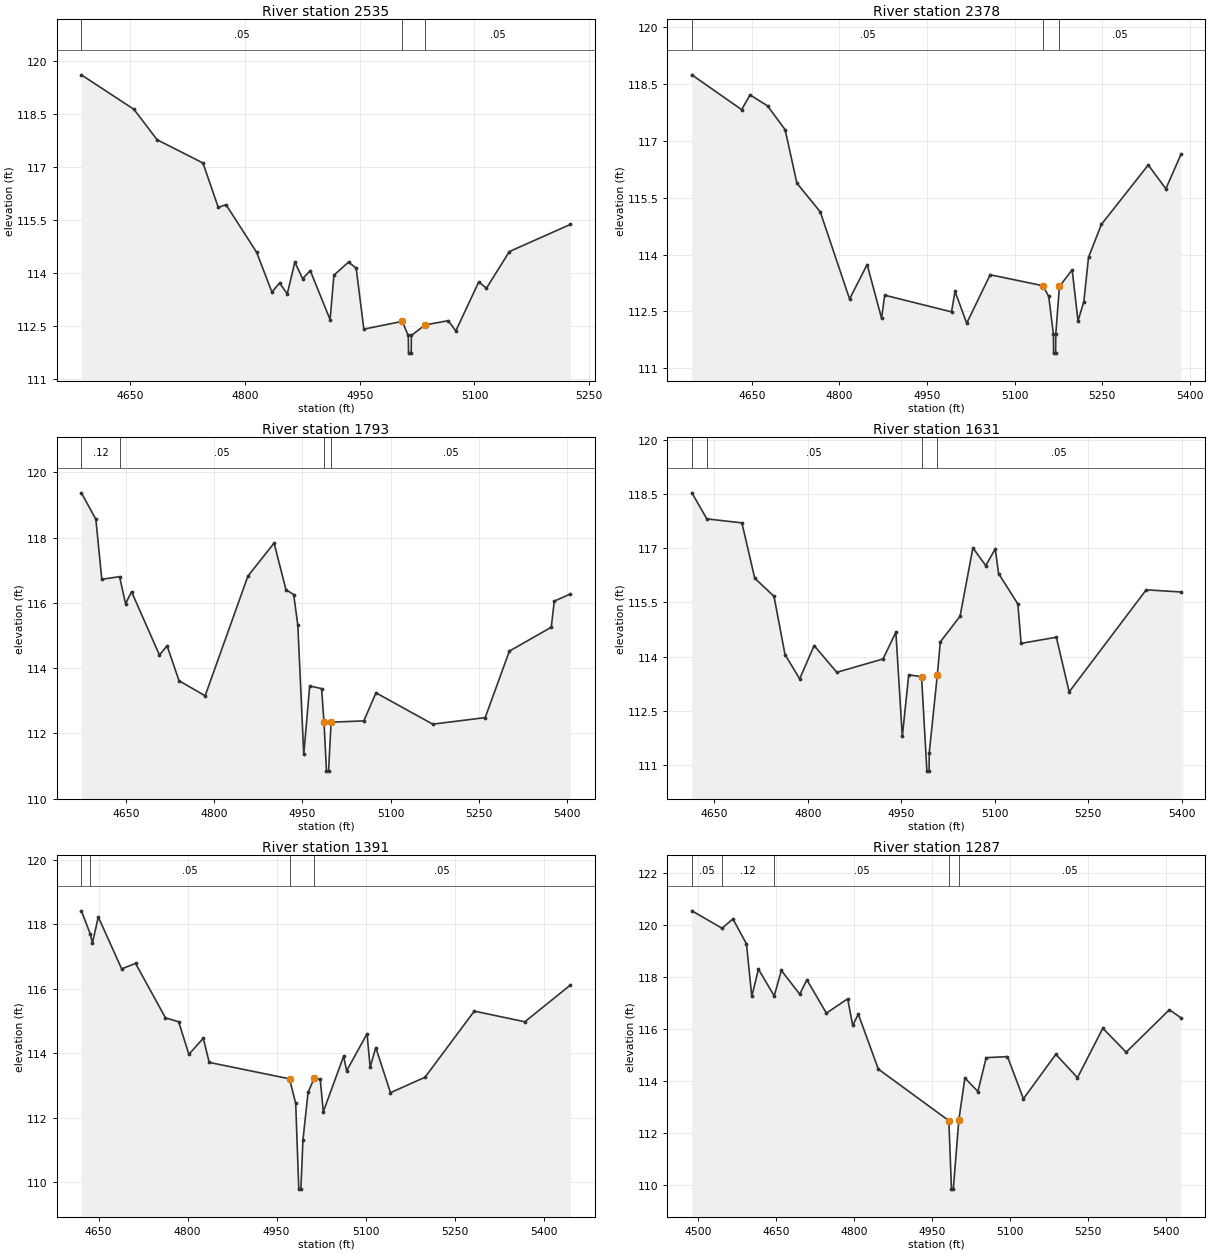
Type RM Length L Ch R = 1 ,2535    ,157,157,157
BEGIN DESCRIPTION:
WHITE OAK CREEK WEST TRIB NO 1 6.0
END DESCRIPTION:
XS GIS Cut Line= 2
      3848429.09     10056361.24      3849067.53     10056390.32
#Sta/Elev= 30
  4586.3  119.61  4655.1  118.63  4685.2  117.77  4745.2  117.11  4765.2  115.85
  4775.3  115.93  4815.3  114.58  4835.3  113.45  4845.3  113.71  4855.3   113.4
  4865.3   114.3  4875.4  113.83  4885.4  114.06  4911.3  112.67  4916.3  113.93
  4935.4   114.3  4945.4  114.13  4955.4   112.4  5005.5  112.62  5013.5  112.22
  5013.8  111.72  5017.3  111.72  5017.5  112.22  5035.5  112.52  5065.6  112.64
  5075.6  112.35  5105.6  113.74  5115.6  113.56  5145.6   114.6  5225.4  115.37
#Mann= 3 , 0 , 0
  4586.3     .05       0  5005.5     .03       0  5035.5     .05       0
Bank Sta=5005.5,5035.5
XS Rating Curve= 0 ,0
Exp/Cntr=0.3,0.1

Type RM Length L Ch R = 1 ,2378    ,585,585,585
BEGIN DESCRIPTION:
WHITE OAK CREEK WEST TRIB NO 1 5.0
END DESCRIPTION:
XS GIS Cut Line= 2
      3848468.58     10056478.87      3849303.64      10056549.1
#Sta/Elev= 30
  4547.2  118.75  4632.5  117.83  4646.8  118.22  4676.9  117.93    4707   117.3
  4727.1  115.89  4767.2  115.13  4817.4  112.83  4847.5  113.74  4872.2  112.32
  4877.6  112.93  4992.1  112.49  4998.1  113.03  5018.1  112.19  5058.3  113.47
  5148.6  113.18  5158.6   112.9  5166.7   111.9  5166.9   111.4  5170.4   111.4
  5170.7   111.9 5176.96  113.16  5198.8   113.6  5208.8  112.25  5218.8  112.76
  5226.8  113.93  5248.9   114.8  5329.2  116.37  5359.3  115.74  5385.2  116.65
#Mann= 3 , 0 , 0
  4547.2     .05       0  5148.6     .03       0 5176.96     .05       0
Bank Sta=5148.6,5176.96
XS Rating Curve= 0 ,0
Exp/Cntr=0.3,0.1

Type RM Length L Ch R = 1 ,1793    ,162,162,162
BEGIN DESCRIPTION:
WHITE OAK CREEK WEST TRIB NO 1 4.0
END DESCRIPTION:
XS GIS Cut Line= 3
      3848683.43     10056958.03      3849104.99     10057015.02
      3849498.48     10057112.97
#Sta/Elev= 30
  4574.6  119.37  4599.2  118.56  4609.3  116.72  4639.5   116.8  4649.7  115.97
  4659.8  116.34  4707.2   114.4  4720.3  114.68  4740.5  113.61  4784.9  113.15
  4857.6  116.82    4902  117.83  4922.2   116.4  4935.3  116.25  4942.3  115.32
  4952.4  111.35  4962.5  113.45  4982.7  113.37 4986.84 112.333    4991  110.84
  4994.5  110.84  4998.9  112.34  5054.5  112.38  5075.1  113.24  5171.5  112.28
  5260.6  112.48  5301.8  114.52  5372.9  115.25    5378  116.05  5405.5  116.27
#Mann= 4 ,-1 , 0
  4574.6     .12       0  4639.5     .05       0 4986.84     .07       0
  4998.9     .05       0
Bank Sta=4986.84,4998.9
XS Rating Curve= 0 ,0
Exp/Cntr=0.3,0.1

Type RM Length L Ch R = 1 ,1631    ,240,240,240
BEGIN DESCRIPTION:
Mapping XS 47592e90
END DESCRIPTION:
XS GIS Cut Line= 2
      3848719.89      10057079.8      3849482.07     10057267.31
#Sta/Elev= 30
  4613.7  118.53  4637.7  117.81    4694   117.7  4714.6  116.17  4745.5  115.67
  4763.2  114.06  4786.7  113.39  4809.9  114.31  4846.3  113.57  4920.5  113.94
  4941.1  114.68  4951.4   111.8  4961.7   113.5  4982.3  113.45  4990.9  110.84
  4994.4  110.84  4994.6  111.34 5007.54 113.489  5012.4  114.41  5044.1  115.12
  5064.7  117.01  5085.3  116.52  5100.6  116.98  5105.9   116.3  5136.8  115.46
  5142.1  114.37  5198.6  114.54  5219.2  113.03  5342.8  115.85  5398.6  115.79
#Mann= 4 ,-1 , 0
  4613.7     .12       0  4637.7     .05       0  4982.3     .07       0
 5007.54     .05       0
Bank Sta=4982.3,5007.54
XS Rating Curve= 0 ,0
Exp/Cntr=0.3,0.1

Type RM Length L Ch R = 1 ,1391    ,104,104,104
BEGIN DESCRIPTION:
Mapping XS a7b88400
END DESCRIPTION:
XS GIS Cut Line= 2
      3848719.89     10057307.23      3849513.92     10057527.41
#Sta/Elev= 30
  4621.1  118.41  4636.4  117.68  4639.7  117.41  4649.6  118.22    4689  116.61
  4712.4  116.78  4762.8  115.09    4785  114.97  4802.2  113.96  4826.5  114.46
  4836.5  113.71  4971.8   113.2  4982.2  112.44  4987.4  109.78  4990.9  109.78
  4994.4   111.3    5003  112.78  5013.3  113.22  5023.5  113.19  5028.7  112.18
  5062.9   113.9  5068.1  113.45  5102.4   114.6  5107.6  113.56  5117.1  114.17
  5141.9  112.77  5200.1  113.25  5283.1   115.3  5368.3  114.97  5445.1  116.11
#Mann= 4 ,-1 , 0
  4621.1     .12       0  4636.4     .05       0  4971.8     .07       0
  5013.3     .05       0
Bank Sta=4971.8,5013.3
XS Rating Curve= 0 ,0
Exp/Cntr=0.3,0.1

Type RM Length L Ch R = 1 ,1287    ,253,253,253
BEGIN DESCRIPTION:
WHITE OAK CREEK WEST TRIB NO 1 3.0
END DESCRIPTION:
XS GIS Cut Line= 3
      3848575.37     10057399.45      3849204.24     10057536.16
      3849489.29     10057616.09
#Sta/Elev= 30
  4488.7  120.54  4546.8  119.87  4567.5  120.23  4593.6  119.27  4603.8  117.25
  4616.6   118.3  4646.9  117.27  4660.6  118.25  4695.9  117.34  4709.7  117.89
  4747.1  116.61    4788  117.16  4797.7  116.14  4808.5  116.57  4846.9  114.46
  4982.4  112.48  4987.4  109.85  4990.9  109.85  5001.6 112.511  5013.2  114.12
  5038.2   113.6  5054.1   114.9    5095  114.94  5125.7  113.32  5187.9  115.03
  5229.5  114.13  5278.2  116.03    5323  115.11    5406  116.74  5428.3  116.43
#Mann= 5 ,-1 , 0
  4488.7     .05       0  4546.8     .12       0  4646.9     .05       0
  4982.4     .07       0  5001.6     .05       0
Bank Sta=4982.4,5001.6
XS Rating Curve= 0 ,0
Exp/Cntr=0.3,0.1

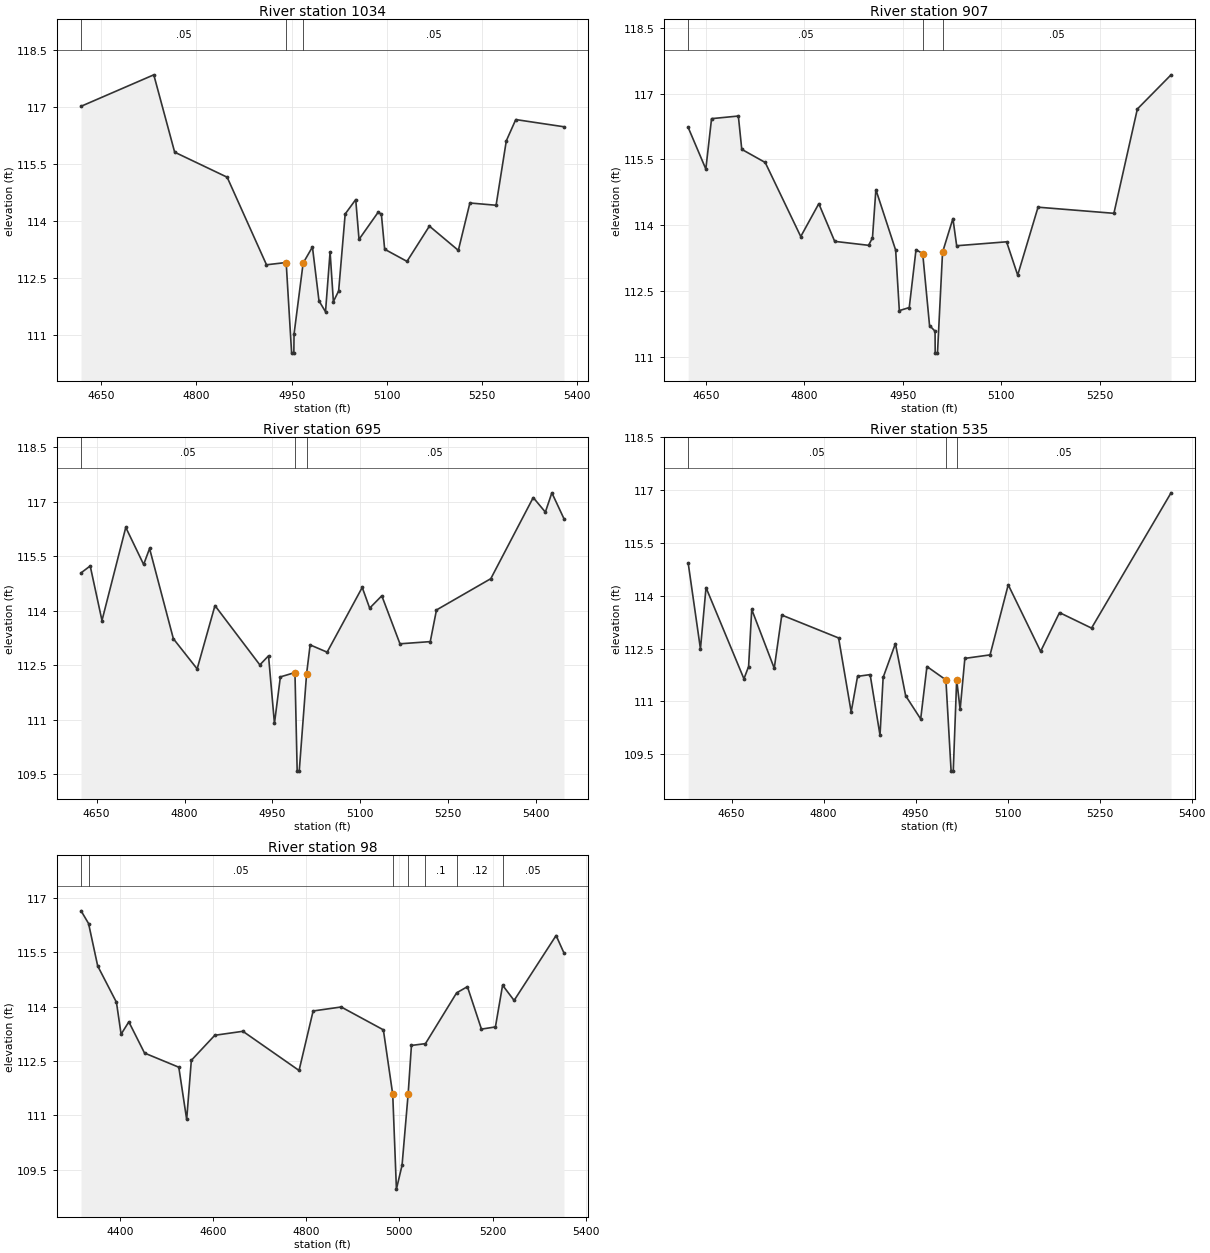
Type RM Length L Ch R = 1 ,1034    ,127,127,127
BEGIN DESCRIPTION:
Mapping XS ffaafa4c
END DESCRIPTION:
XS GIS Cut Line= 2
      3848685.17     10057656.19      3849421.27      10057848.9
#Sta/Elev= 30
  4618.2  117.02  4732.8  117.85  4765.7  115.81  4848.4  115.15  4910.4  112.84
  4941.4   112.9    4950  110.51  4953.5  110.51  4953.8  111.01 4968.18 112.886
  4982.8  113.31  4993.1  111.89  5003.4   111.6  5010.6  113.18  5015.8  111.87
  5024.1  112.15  5034.4  114.18    5051  114.56  5056.2  113.51  5086.1  114.22
  5091.4  114.18  5096.6  113.25  5131.8  112.93  5167.1  113.86  5212.7  113.22
  5230.9  114.47  5272.2  114.41  5288.3  116.11  5303.2  116.67  5379.1  116.48
#Mann= 3 , 0 , 0
  4618.2     .05       0  4941.4     .07       0 4968.18     .05       0
Bank Sta=4941.4,4968.18
XS Rating Curve= 0 ,0
Exp/Cntr=0.3,0.1

Type RM Length L Ch R = 1 ,907     ,212,212,212
BEGIN DESCRIPTION:
Mapping XS 1711f5b2
END DESCRIPTION:
XS GIS Cut Line= 2
      3848681.74     10057786.41      3849394.06     10057968.39
#Sta/Elev= 30
  4623.3  116.23  4650.2  115.28  4658.9  116.43  4699.7  116.49  4704.9  115.73
  4740.6  115.43  4794.7  113.74  4822.2  114.49  4846.4  113.63    4898  113.54
  4903.9  113.71  4909.1  114.81  4939.2  113.43  4944.8  112.05  4959.9  112.12
  4970.2  113.44  4980.4  113.35  4990.8  111.71  4999.2  111.58  4999.4  111.08
  5002.9  111.08  5010.6 113.381  5026.4  114.15  5032.1  113.53  5108.1  113.62
    5125  112.86    5156  114.41  5271.5  114.27  5307.2  116.65  5358.5  117.43
#Mann= 3 , 0 , 0
  4623.3     .05       0  4980.4     .07       0  5010.6     .05       0
Bank Sta=4980.4,5010.6
XS Rating Curve= 0 ,0
Exp/Cntr=0.3,0.1

Type RM Length L Ch R = 1 ,695     ,160,160,160
BEGIN DESCRIPTION:
WHITE OAK CREEK WEST TRIB NO 1 2.0
END DESCRIPTION:
XS GIS Cut Line= 3
      3848662.63     10058024.25      3849140.43     10058106.47
      3849468.54      10058192.4
#Sta/Elev= 30
  4623.4  115.04    4639  115.23  4659.1  113.73  4699.7  116.29  4730.2  115.27
  4740.3  115.71  4780.9  113.23  4821.5   112.4  4851.9  114.14  4928.5  112.51
  4943.3  112.76  4953.4   110.9  4963.5  112.18  4988.4   112.3  4992.2  109.59
  4995.7  109.59 5008.31 112.273  5014.3  113.06  5043.3  112.86  5103.2  114.64
  5115.9  114.07  5136.6  114.41  5167.6  113.09  5219.3  113.15  5229.9  114.02
  5322.6  114.88    5395  117.11  5415.7  116.71  5426.8  117.24  5447.4  116.53
#Mann= 3 , 0 , 0
  4623.4     .05       0  4988.4     .07       0 5008.31     .05       0
Bank Sta=4988.4,5008.31
XS Rating Curve= 0 ,0
Exp/Cntr=0.3,0.1

Type RM Length L Ch R = 1 ,535     ,437,437,437
BEGIN DESCRIPTION:
Mapping XS 937f19dd
END DESCRIPTION:
XS GIS Cut Line= 2
      3848669.55     10058142.31      3849434.52     10058327.65
#Sta/Elev= 30
  4579.3  114.93  4599.3  112.49  4608.4  114.23  4670.2  111.64  4677.8  111.99
  4682.9  113.61  4719.6  111.94  4731.9  113.45  4824.5   112.8    4845   110.7
  4855.4  111.71  4875.9  111.76    4892  110.04  4897.1  111.68  4917.1  112.64
  4933.8  111.16  4958.3   110.5  4968.5  111.99  4999.4  111.61  5007.9  109.02
  5011.4  109.02 5016.96 111.615  5022.6  110.77  5030.3  112.22  5071.4  112.32
    5101  114.31  5153.8  112.42  5184.6  113.52  5236.8  113.08  5366.4  116.92
#Mann= 3 , 0 , 0
  4579.3     .05       0  4999.4     .07       0 5016.96     .05       0
Bank Sta=4999.4,5016.96
XS Rating Curve= 0 ,0
Exp/Cntr=0.3,0.1

Type RM Length L Ch R = 1 ,98      ,0,0,0
BEGIN DESCRIPTION:
WHITE OAK CREEK WEST TRIB NO 1 1.0
END DESCRIPTION:
XS GIS Cut Line= 3
      3848472.31     10058596.04      3849152.13     10058661.88
      3849504.59     10058681.27
#Sta/Elev= 30
    4317  116.64  4333.1  116.29  4352.7  115.12  4392.9  114.12  4402.9  113.24
  4419.5  113.58  4453.2  112.72  4526.7  112.33  4543.6  110.89  4553.6  112.52
  4603.9  113.21  4664.2  113.32  4784.7  112.24  4814.9  113.88  4875.1  113.99
  4965.6  113.36  4985.7  111.58  4993.6  108.97  5005.7  109.63  5018.8 111.599
  5025.8  112.93  5055.9  112.98  5122.8  114.38  5145.9  114.55    5176  113.38
    5206  113.44  5221.4  114.59  5246.1  114.17  5336.2  115.96    5353  115.48
#Mann= 7 ,-1 , 0
    4317    .075       0  4333.1     .05       0  4985.7     .07       0
  5018.8     .05       0  5055.9      .1       0  5122.8     .12       0
  5221.4     .05       0
Bank Sta=4985.7,5018.8
XS Rating Curve= 0 ,0
Exp/Cntr=0.3,0.1