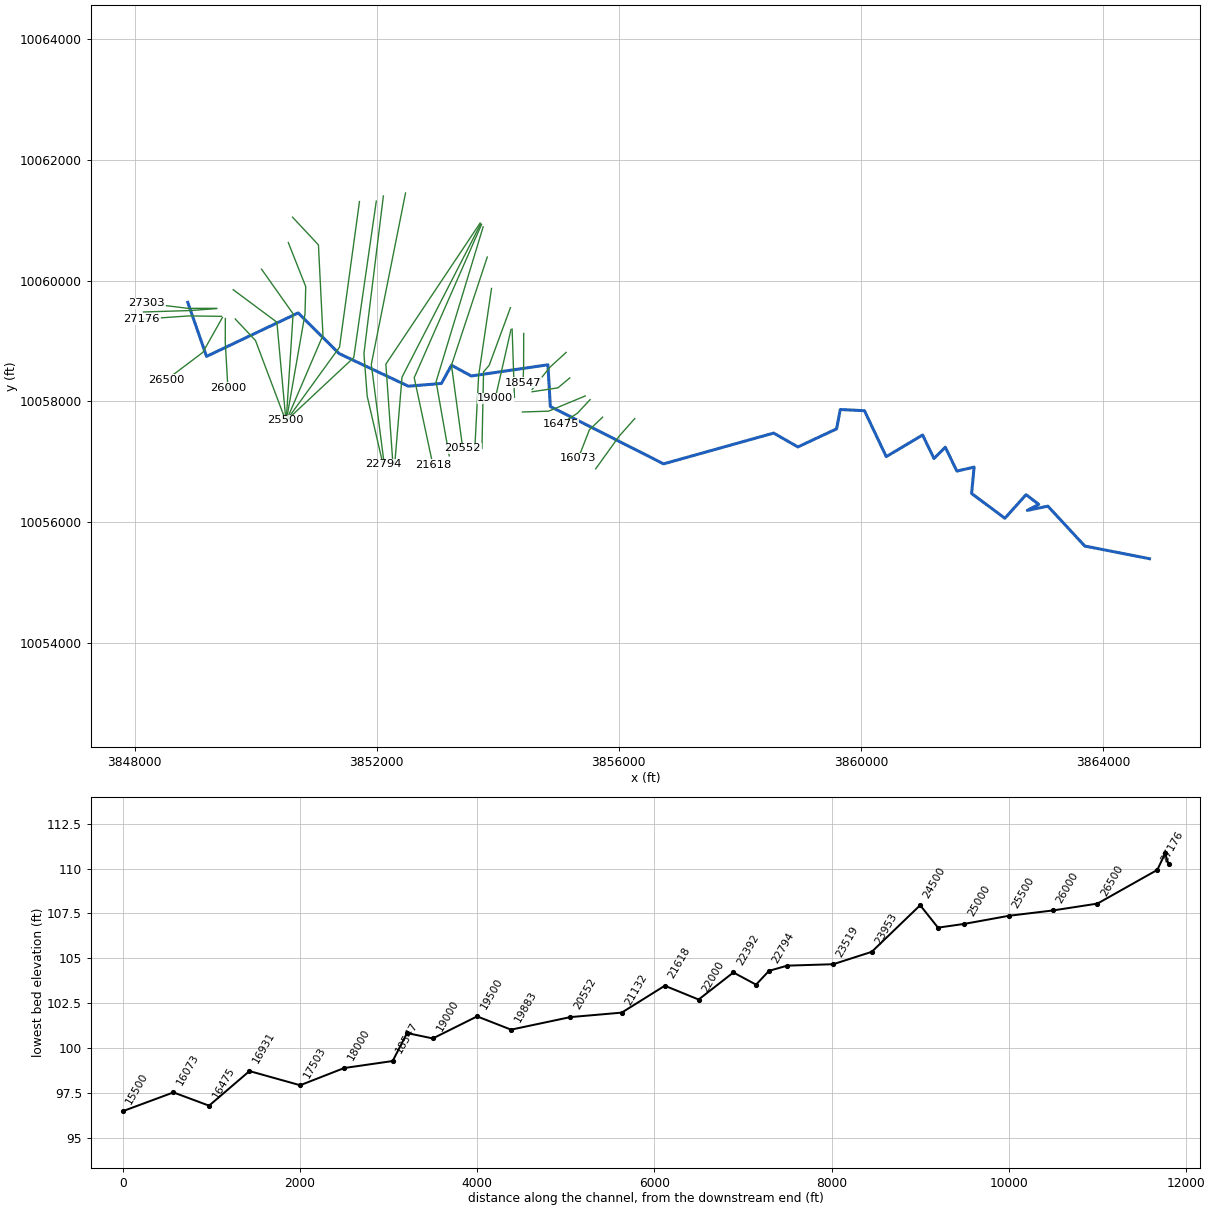
--- WHITE OAK CREEK WEST.prj (project) ---

Proj Title=WHITE OAK CREEK WEST Base Level Engineering
Current Plan=p01
Default Exp/Contr=0.3,0.1
English Units
Geom File=g01
Flow File=f01
Plan File=p01
Y Axis Title=Elevation
X Axis Title(PF)=Main Channel Distance
X Axis Title(XS)=Station
BEGIN DESCRIPTION:
WHITE OAK CREEK WEST
END DESCRIPTION:
DSS Export Rating Curves= 0
DSS Export Rating Curve Sorted= 0
DSS Export Volume Flow Curves= 0
DXF OffsetX= 0
DXF OffsetY= 0
DXF ScaleX= 1
DXF ScaleY= 10

--- WHITE OAK CREEK WEST.p01 (plan) ---

Plan Title=Multiple Run
Short Identifier=Multiple
Geom File=g01
Flow File=f01
Subcritical Flow
K Sum by GR= 0
Std Step Tol= 0.01
Critical Tol= 0.01
Num of Std Step Trials= 20
Max Error Tol= 0.3
Flow Tol Ratio= 0.001
Split Flow NTrial= 30
Split Flow Tol= 0.02
Split Flow Ratio= 0.02
Log Output Level= 0
Friction Slope Method= 1
Unsteady Friction Slope Method= 2
Unsteady Bridges Friction Slope Method= 1
Parabolic Critical Depth
Global Vel Dist=  1 , 1 , 1
Global Log Level= 0
CheckData=True
Encroach Param= -1, 0, 0, 0
BEGIN DESCRIPTION:
Multiple Run
END DESCRIPTION:

--- WHITE OAK CREEK WEST.f01 (steady flow) ---

Flow Title=Multiple
Program Version=4.10
Number of Profiles= 7
Profile Names=10-year,25-year,50-year,1pct_min,100-year,1pct_plu,500-year
River Rch & RM=WHITE OAK CREEK,Reach-1         ,27303
     445     558     714     299     904    2730    1500
River Rch & RM=WHITE OAK CREEK,Reach-1         ,26500
     625     810    1060     455    1374    4149    2386
River Rch & RM=WHITE OAK CREEK,Reach-1         ,23519
    1101    1469    1962     858    2590    7822    4666
River Rch & RM=WHITE OAK CREEK,Reach-1         ,22392
    1316    1772    2383    1048    3164    9555    5774
River Rch & RM=WHITE OAK CREEK,Reach-1         ,19000
    1043    1364    1796     773    2335    7052    4082
River Rch & RM=WHITE OAK CREEK,Reach-1         ,13429
    1669    2261    3052    1346    4065   12276    7463
Boundary for River Rch & Prof#=WHITE OAK CREEK,Reach-1         , 1
Up Type= 0
Dn Type= 3
Dn Slope=0.005
Boundary for River Rch & Prof#=WHITE OAK CREEK,Reach-1         , 2
Up Type= 0
Dn Type= 3
Dn Slope=0.005
Boundary for River Rch & Prof#=WHITE OAK CREEK,Reach-1         , 3
Up Type= 0
Dn Type= 3
Dn Slope=0.005
Boundary for River Rch & Prof#=WHITE OAK CREEK,Reach-1         , 4
Up Type= 0
Dn Type= 3
Dn Slope=0.005
Boundary for River Rch & Prof#=WHITE OAK CREEK,Reach-1         , 5
Up Type= 0
Dn Type= 3
Dn Slope=0.005
Boundary for River Rch & Prof#=WHITE OAK CREEK,Reach-1         , 6
Up Type= 0
Dn Type= 3
Dn Slope=0.005
Boundary for River Rch & Prof#=WHITE OAK CREEK,Reach-1         , 7
Up Type= 0
Dn Type= 3
Dn Slope=0.005
DSS Import GetInterval= 0
DSS Import GetPeak= 0
DSS Import FillOption= 0

--- WHITE OAK CREEK WEST.g01 (geometry) ---

Geom Title=Existing Conditions
Program Version=4.10

River Reach=WHITE OAK CREEK ,Reach-1
Reach XY= 30
      3848877.39     10059640.37      3849188.16     10058746.26
      3850701.62      10059465.8      3851379.25     10058792.17
      3852522.15     10058253.09       3853068.8     10058298.13
      3853234.74      10058599.9      3853561.68     10058421.76
      3854828.24     10058606.86      3854868.24     10057916.86
      3856739.52     10056967.13      3858558.24     10057476.86
      3858958.24     10057246.86      3859598.24     10057546.86
      3859658.24     10057866.86      3860058.24     10057846.86
      3860418.24     10057086.86      3861019.04     10057444.56
      3861206.54     10057055.67      3861394.04     10057243.17
      3861585.01     10056847.34      3861869.73     10056913.31
      3861828.24     10056476.86      3862378.24     10056066.86
      3862728.24     10056456.86      3862938.24     10056296.86
      3862748.24     10056196.86      3863088.24     10056266.86
      3863698.24     10055606.86      3864768.24     10055396.86

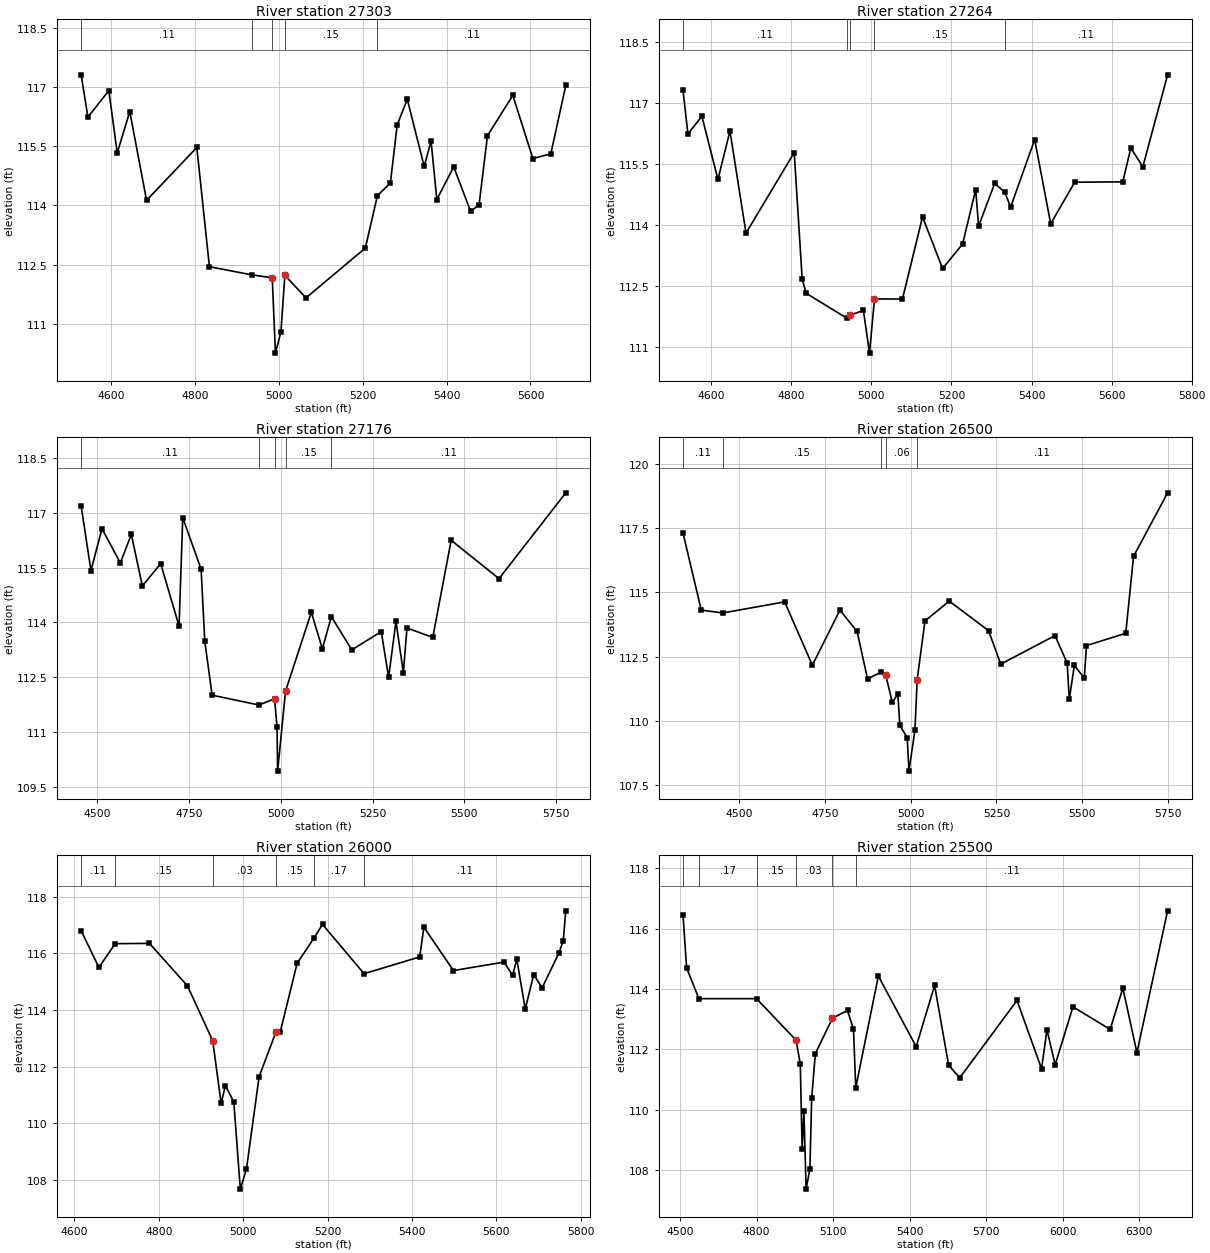
Type RM Length L Ch R = 1 ,27303   ,39,39,39
BEGIN DESCRIPTION:
WHITE OAK CREEK WEST 51.0
END DESCRIPTION:
XS GIS Cut Line= 3
      3849353.92     10059542.03      3848881.52      10059541.3
      3848202.51     10059625.43
#Sta/Elev= 30
  4527.6  117.31  4543.7  116.24  4593.7  116.91  4613.7  115.33  4643.7  116.38
  4683.7  114.13  4803.7  115.47  4833.7  112.45  4935.9  112.24  4983.7  112.17
  4991.3  110.26  5004.4   110.8  5013.8  112.23  5064.2  111.66  5205.8  112.92
  5234.7  114.25  5265.7  114.57  5281.8  116.04    5306  116.69  5346.3  114.99
  5362.7  115.63  5376.5  114.15  5416.8  114.98  5457.1  113.85  5477.3  114.02
  5497.4  115.77  5557.9  116.79  5605.7  115.19  5648.6  115.31  5684.2  117.04
#Mann= 5 ,-1 , 0
  4527.6     .11       0  4935.9     .15       0  4983.7     .06       0
  5013.8     .15       0  5234.7     .11       0
Bank Sta=4983.7,5013.8
XS Rating Curve= 0 ,0
Exp/Cntr=0.3,0.1

Type RM Length L Ch R = 1 ,27264   ,88,88,88
BEGIN DESCRIPTION:
Mapping XS 5e1510de
END DESCRIPTION:
XS GIS Cut Line= 3
      3849354.89     10059536.98      3848905.42     10059504.67
      3848146.01      10059481.2
#Sta/Elev= 30
  4529.5  117.31  4541.8  116.24  4576.7  116.67  4616.8  115.12  4646.8  116.31
  4686.9   113.8  4807.3  115.78  4827.3  112.66  4837.3  112.32  4938.6  111.71
  4947.8111.7856  4980.1   111.9  4995.4  110.85  5007.8 112.182  5077.7  112.18
  5127.8   114.2  5177.8  112.93  5227.8  113.53  5260.6  114.87  5267.8  113.97
  5307.9  115.02  5332.8  114.81  5347.9  114.44  5407.9   116.1  5447.9  114.03
  5507.9  115.05    5628  115.06    5648  115.89    5678  115.43  5739.9  117.69
#Mann= 5 ,-1 , 0
  4529.5     .11       0  4938.6     .15       0  4947.8     .09       0
  5007.8     .15       0  5332.8     .11       0
Bank Sta=4947.8,5007.8
XS Rating Curve= 0 ,0
Exp/Cntr=0.3,0.1

Type RM Length L Ch R = 1 ,27176   ,676,676,676
BEGIN DESCRIPTION:
Mapping XS 13a5a0ce
END DESCRIPTION:
XS GIS Cut Line= 3
       3849434.5     10059409.25      3848895.01     10059416.13
      3848116.52     10059362.12
#Sta/Elev= 30
  4456.3  117.19    4483  115.42    4513  116.57    4563  115.63    4593  116.41
    4623     115    4673  115.61    4723   113.9    4733  116.87    4783  115.46
    4793  113.49    4813  112.01  4940.4  111.74    4983  111.91  4989.8  111.15
  4991.4  109.93    5013  112.12  5083.2  114.28  5113.3  113.28  5137.7  114.16
  5193.5  113.25  5273.7  113.75  5293.7   112.5  5313.8  114.03  5333.8  112.63
  5343.8  113.85    5414  113.59  5464.1  116.25  5594.4   115.2  5776.2  117.55
#Mann= 5 ,-1 , 0
  4456.3     .11       0  4940.4     .15       0    4983     .06       0
    5013     .15       0  5137.7     .11       0
Bank Sta=4983,5013
XS Rating Curve= 0 ,0
Exp/Cntr=0.3,0.1

Type RM Length L Ch R = 1 ,26500   ,500,500,500
BEGIN DESCRIPTION:
WHITE OAK CREEK WEST 50.0
END DESCRIPTION:
XS GIS Cut Line= 3
      3849450.54     10059389.57      3849125.81     10058811.77
      3848528.76     10058360.18
#Sta/Elev= 30
  4337.2  117.31  4390.4  114.31  4453.4   114.2  4633.3  114.63    4714  112.17
  4794.3  114.31  4844.3  113.48  4874.6  111.64  4914.7   111.9  4927.3111.8009
    4947  110.72  4962.9  111.06  4968.7  109.83  4990.3  109.35  4995.2  108.05
  5012.8  109.65 5019.26111.6113    5042  113.89  5112.7  114.66  5227.2  113.51
  5262.6  112.21  5420.7  113.32  5456.1  112.25  5462.3  110.84  5476.9  112.16
    5506  111.67  5512.3  112.93  5626.7  113.41  5649.4   116.4  5748.6  118.87
#Mann= 5 ,-1 , 0
  4337.2     .11       0  4453.4     .15       0  4914.7     .11       0
  4927.3     .06       0 5019.26     .11       0
Bank Sta=4927.3,5019.26
XS Rating Curve= 0 ,0
Exp/Cntr=0.3,0.1

Type RM Length L Ch R = 1 ,26000   ,500,500,500
BEGIN DESCRIPTION:
WHITE OAK CREEK WEST 49.0
END DESCRIPTION:
XS GIS Cut Line= 3
      3849498.94     10059373.04      3849497.13     10058988.85
      3849540.78     10058225.19
#Sta/Elev= 30
  4615.8   116.8  4657.8   115.5  4696.6  116.34  4777.8  116.35  4867.8  114.85
  4927.8  112.91  4947.8   110.7  4957.8  111.33  4977.8  110.75  4993.2  107.67
  5007.8  108.38  5037.8  111.64  5077.9  113.23  5087.9  113.22    5128  115.65
  5167.5  116.53  5188.1  117.02  5286.7  115.28  5418.5  115.87  5428.5  116.92
  5498.6  115.39  5618.8  115.69  5638.8  115.22  5648.8  115.79  5668.9  114.03
  5688.9  115.25  5708.9  114.78    5749  116.02    5759  116.45  5764.9   117.5
#Mann= 6 ,-1 , 0
  4615.8     .11       0  4696.6     .15       0  4927.8     .03       0
  5077.9     .15       0  5167.5     .17       0  5286.7     .11       0
Bank Sta=4927.8,5077.9
XS Rating Curve= 0 ,0
Exp/Cntr=0.3,0.1

Type RM Length L Ch R = 1 ,25500   ,500,500,500
BEGIN DESCRIPTION:
WHITE OAK CREEK WEST 48.0
END DESCRIPTION:
XS GIS Cut Line= 3
      3849661.97     10059365.38      3849996.71     10059009.19
      3850493.33     10057688.48
#Sta/Elev= 30
  4511.2  116.46  4525.5   114.7  4573.6  113.68  4799.6  113.68  4954.6112.3003
    4971  111.51  4978.3  108.69  4985.2  109.96  4993.9  107.37  5008.7  108.04
  5015.7  110.39    5030  111.86  5097.2 113.035  5156.2  113.29  5179.6  112.66
  5188.5  110.73  5277.1  114.43  5425.3  112.09  5497.6  114.12  5552.7  111.47
  5596.3  111.06  5820.6  113.62  5916.8  111.36  5938.1  112.65  5970.2  111.49
    6040  113.41  6185.8  112.66  6235.6  114.03  6290.7  111.89    6411  116.59
#Mann= 6 ,-1 , 0
  4511.2     .11       0  4573.6     .17       0  4799.6     .15       0
  4954.6     .03       0  5097.2     .15       0  5188.5     .11       0
Bank Sta=4954.6,5097.2
XS Rating Curve= 0 ,0
Exp/Cntr=0.3,0.1

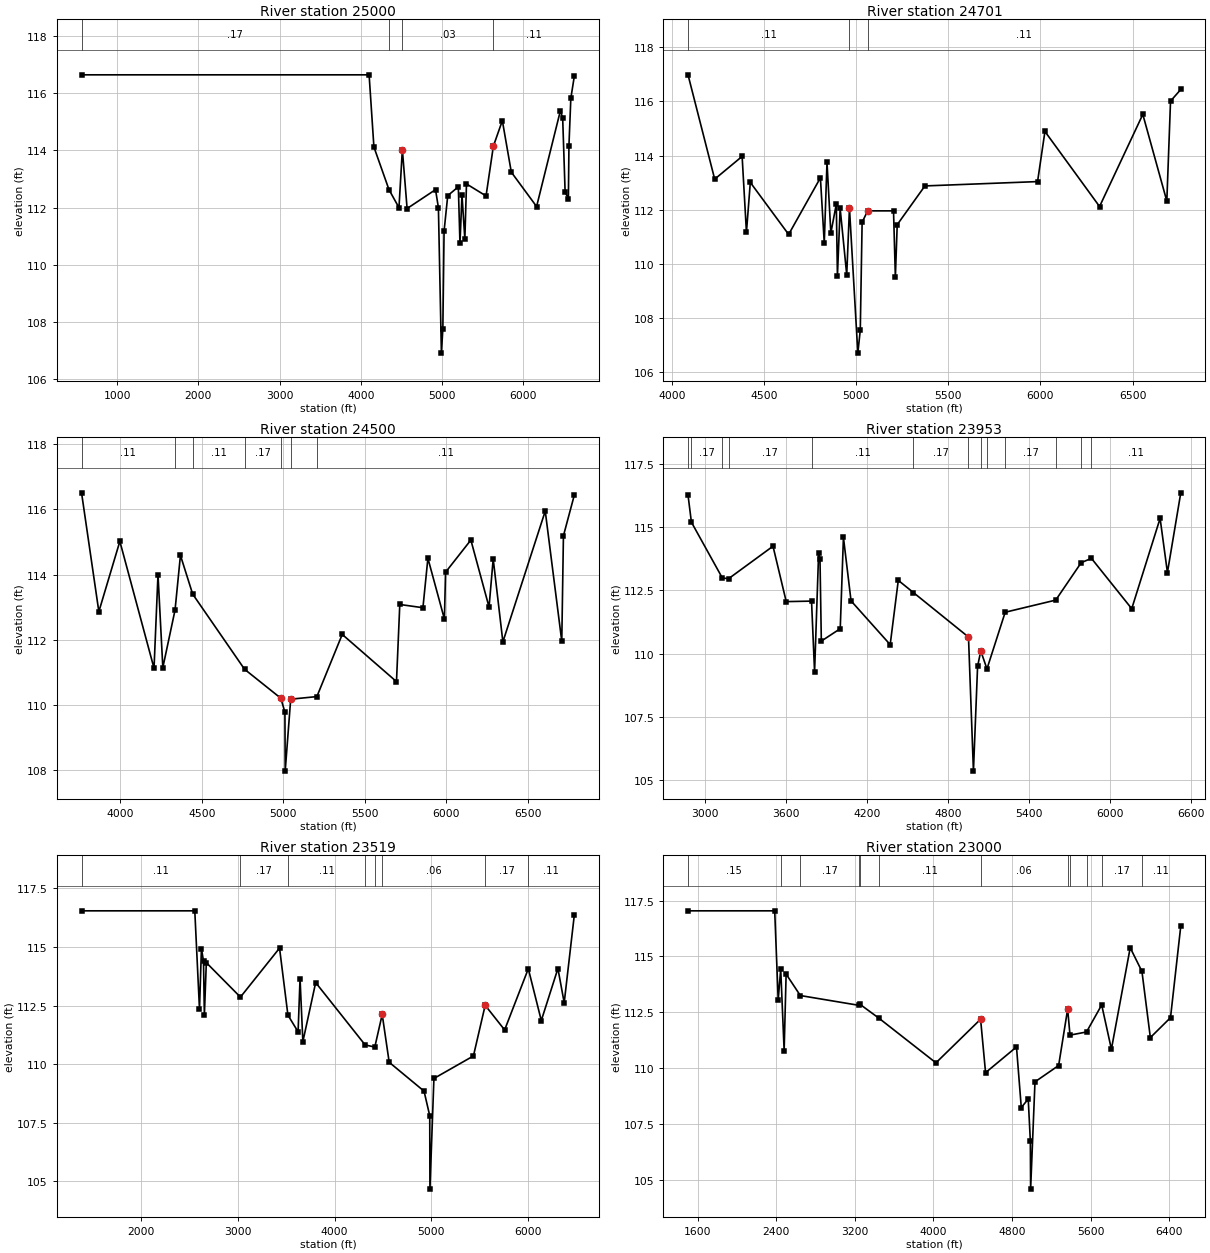
Type RM Length L Ch R = 1 ,25000   ,299,299,299
BEGIN DESCRIPTION:
WHITE OAK CREEK WEST 47.0
END DESCRIPTION:
XS GIS Cut Line= 3
      3849629.03     10059849.52      3850350.46     10059311.93
      3850498.69     10057688.39
#Sta/Elev= 30
   560.7  116.64  4102.7  116.64  4161.8  114.12  4347.5  112.63  4470.5     112
  4512.2  114.03  4570.6  111.97  4920.9  112.63  4956.3     112  4993.2  106.92
  5010.9  107.77  5026.1  111.18  5071.2  112.42  5201.7  112.73  5221.8  110.75
  5246.6  112.44    5282   110.9  5302.1  112.83  5543.1  112.41  5633.5  114.15
  5743.9  115.04  5854.4  113.24  6165.7  112.04    6459  115.39    6487  115.13
  6517.1  112.54  6557.3  112.32  6564.2  114.17  6587.4  115.82  6630.3  116.59
#Mann= 4 ,-1 , 0
   560.7     .17       0  4347.5     .11       0  4512.2     .03       0
  5633.5     .11       0
Bank Sta=4512.2,5633.5
XS Rating Curve= 0 ,0
Exp/Cntr=0.3,0.1

Type RM Length L Ch R = 1 ,24701   ,201,201,201
BEGIN DESCRIPTION:
Mapping XS 71a0bb95
END DESCRIPTION:
XS GIS Cut Line= 3
      3850096.34     10060189.98      3850618.18     10059451.18
       3850504.6     10057685.54
#Sta/Elev= 30
  4088.1  116.98  4232.8  113.13  4381.7  113.97  4405.1  111.17  4426.1  113.01
  4634.1  111.09  4806.5  113.18  4827.4  110.77  4842.2  113.75  4863.1  111.14
  4892.7  112.21  4898.8  109.56  4913.6  112.05  4949.3   109.6  4964.1  112.06
  5009.5  106.71  5022.8  107.56  5032.8  111.54  5062.9  111.96  5203.2  111.96
  5213.2  109.51  5223.2  111.45  5373.5  112.88  5984.8  113.04  6024.8  114.89
  6321.2  112.12  6555.9  115.52  6686.2  112.32  6706.3  116.01  6761.9  116.44
#Mann= 3 , 0 , 0
  4088.1     .11       0  4964.1     .03       0  5062.9     .11       0
Bank Sta=4964.1,5062.9
XS Rating Curve= 0 ,0
Exp/Cntr=0.3,0.1

Type RM Length L Ch R = 1 ,24500   ,547,547,547
BEGIN DESCRIPTION:
WHITE OAK CREEK WEST 46.0
END DESCRIPTION:
XS GIS Cut Line= 5
      3850539.14     10060629.79      3850552.23     10060596.68
      3850827.02     10059901.77      3850814.53     10059445.71
      3850507.16     10057685.24
#Sta/Elev= 30
  3760.9  116.51  3867.1  112.86  3996.1  115.02    4206  111.12  4230.3     114
    4260  111.14  4335.1  112.91  4368.2  114.59  4443.2   113.4  4761.9  111.09
  4984.6   110.2  5009.8  109.77  5011.5  107.96  5045.3  110.17  5206.1  110.25
  5361.8  112.16    5695  110.71  5715.3  113.08  5857.4  112.98  5887.9   114.5
  5989.4  112.63  5996.3  114.07  6151.8  115.06  6263.5     113  6288.9  114.48
  6348.4  111.93  6608.6  115.95  6710.1  111.95  6720.3  115.19  6787.1  116.44
#Mann= 7 ,-1 , 0
  3760.9     .11       0  4335.1    .125       0  4443.2     .11       0
  4761.9     .17       0  4984.6     .06       0  5045.3     .17       0
  5206.1     .11       0
Bank Sta=4984.6,5045.3
XS Rating Curve= 0 ,0
Exp/Cntr=0.3,0.1

Type RM Length L Ch R = 1 ,23953   ,434,434,434
BEGIN DESCRIPTION:
WHITE OAK CREEK WEST 45.0
END DESCRIPTION:
XS GIS Cut Line= 4
       3850608.9     10061050.67      3851036.75     10060591.84
      3851111.45     10059094.66      3850510.48     10057690.02
#Sta/Elev= 30
  2873.6  116.27  2898.7   115.2  3128.5  112.99  3175.3  112.97  3503.8  114.25
  3601.9  112.06  3789.6  112.08  3812.1  109.28  3842.2  113.99  3852.2  113.75
  3862.2   110.5  4002.4  110.99  4026.1   114.6  4082.5  112.09  4372.8  110.36
  4432.9   112.9  4544.6  112.42  4953.5  110.66  4990.2  105.36    5021   109.5
  5044.6  110.11  5090.5   109.4  5225.6  111.64  5600.4  112.12  5789.4   113.6
  5865.1  113.77  6164.1  111.78  6374.5  115.35  6428.8  113.21  6527.8  116.36
#Mann= 13 ,-1 , 0
  2873.6     .11       0  2898.7     .17       0  3128.5     .11       0
  3175.3     .17       0  3789.6     .11       0  4544.6     .17       0
  4953.5     .06       0  5044.6     .17       0  5090.5     .15       0
  5225.6     .17       0  5600.4     .11       0  5789.4     .17       0
  5865.1     .11       0
Bank Sta=4953.5,5044.6
XS Rating Curve= 0 ,0
Exp/Cntr=0.3,0.1

Type RM Length L Ch R = 1 ,23519   ,519,519,519
BEGIN DESCRIPTION:
WHITE OAK CREEK WEST 44.0
END DESCRIPTION:
XS GIS Cut Line= 3
      3851714.55     10061309.18      3851385.37     10058899.14
      3850512.13     10057690.65
#Sta/Elev= 30
  1384.1  116.54  2554.7  116.54  2603.3  112.34  2623.4  114.93  2644.9  114.39
  2653.7  112.09  2673.9  114.33  3026.5  112.86  3430.9  114.95  3517.5  112.09
  3622.6  111.38  3642.8  113.65  3671.9  110.96  3804.3  113.48  4315.8  110.82
  4415.6  110.73  4492.1  112.12  4564.4  110.08  4924.6  108.85  4983.6   107.8
  4985.5  104.67  5026.7  109.39  5435.2  110.35  5556.6  112.51  5757.8  111.46
  6002.6  114.07  6136.8  111.86  6308.6  114.08  6373.6  112.62  6478.1  116.36
#Mann= 8 ,-1 , 0
  1384.1     .11       0  3026.5     .17       0  3517.5     .11       0
  4315.8     .17       0  4415.6     .11       0  4492.1     .06       0
  5556.6     .17       0  6002.6     .11       0
Bank Sta=4492.1,5556.6
XS Rating Curve= 0 ,0
Exp/Cntr=0.3,0.1

Type RM Length L Ch R = 1 ,23000   ,206,206,206
BEGIN DESCRIPTION:
WHITE OAK CREEK WEST 43.0
END DESCRIPTION:
XS GIS Cut Line= 3
      3851992.71     10061316.19      3851620.37     10058726.31
      3850512.18      10057688.6
#Sta/Elev= 30
  1500.9  117.04  2383.5  117.04    2419  113.06  2444.7  114.43  2479.6  110.79
  2499.8  114.21  2644.5  113.25    3244  112.81    3248  112.87  3443.8  112.24
  4025.3  110.24  4479.9  112.19  4530.5   109.8  4845.4  110.95  4894.2  108.24
  4964.9  108.62  4986.3  106.76  4989.3  104.59  5033.7  109.39  5274.5  110.12
  5366.3  112.64  5390.2  111.48  5558.4  111.62  5712.9  112.83  5811.8  110.85
  6003.3  115.39  6122.7  114.33  6208.4  111.37  6413.6  112.26  6518.2  116.36
#Mann= 12 ,-1 , 0
  1500.9     .15       0  2444.7     .11       0  2644.5     .17       0
    3244     .11       0    3248     .17       0  3443.8     .11       0
  4479.9     .06       0  5366.3     .15       0  5390.2     .17       0
  5558.4     .11       0  5712.9     .17       0  6122.7     .11       0
Bank Sta=4479.9,5366.3
XS Rating Curve= 0 ,0
Exp/Cntr=0.3,0.1

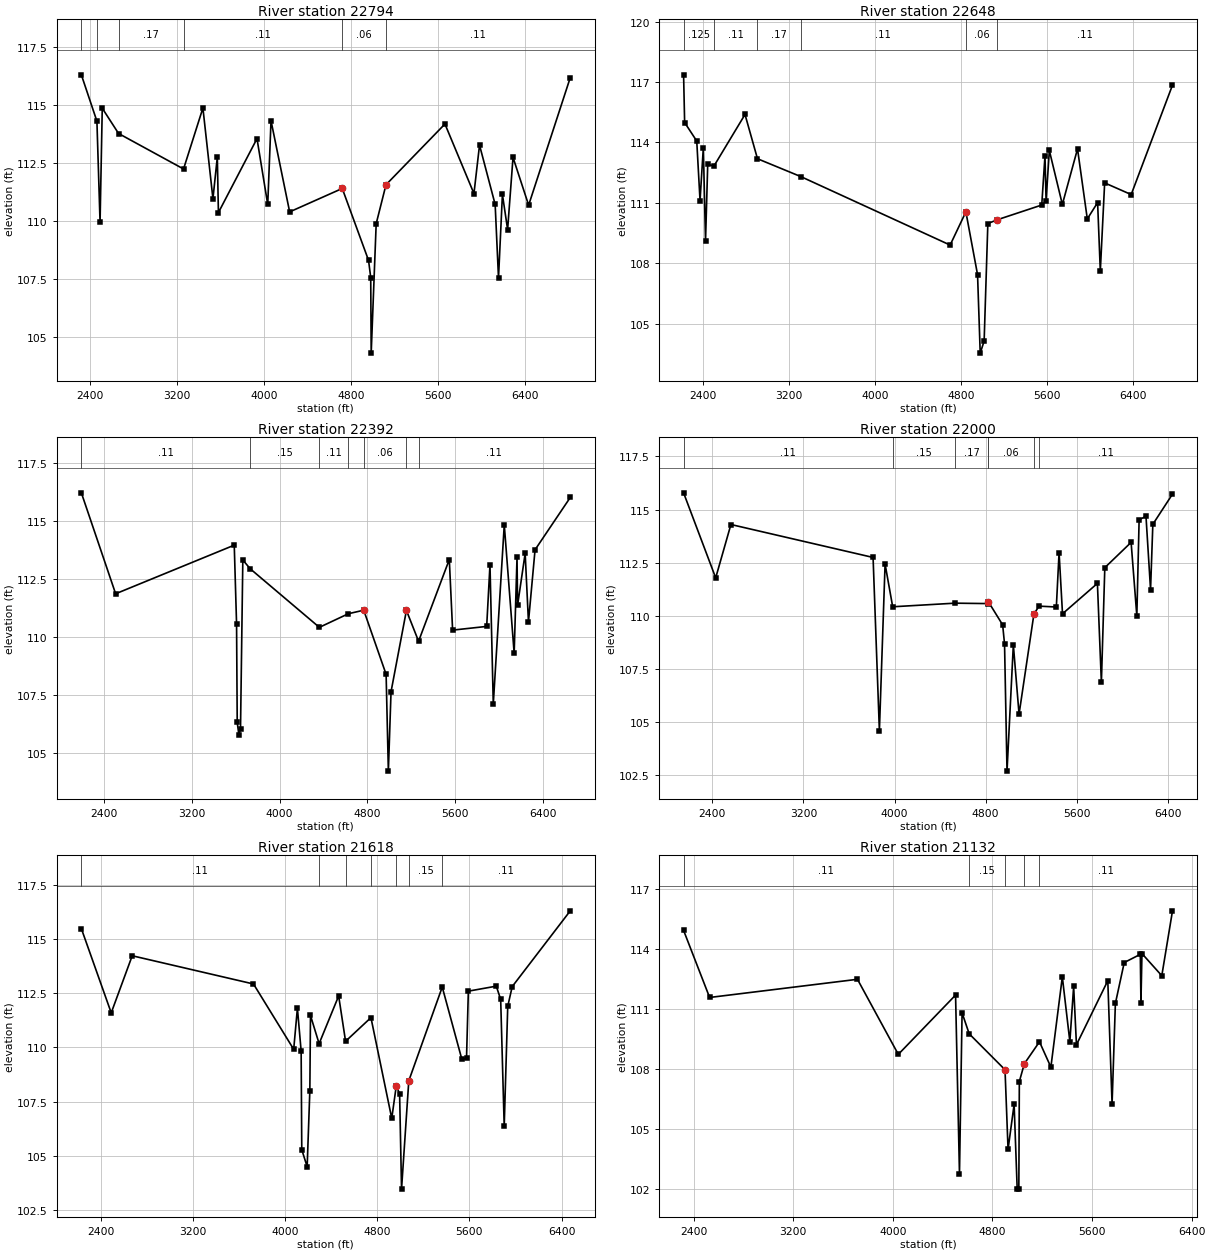
Type RM Length L Ch R = 1 ,22794   ,146,146,146
BEGIN DESCRIPTION:
Mapping XS 471f5f68
END DESCRIPTION:
XS GIS Cut Line= 4
      3852109.92     10061401.68      3851788.58     10058793.24
      3851842.46     10058087.28      3852103.21     10056958.17
#Sta/Elev= 30
  2321.1   116.3  2464.1   114.3    2493  109.94  2513.2  114.86  2663.2  113.77
  3260.6  112.24  3438.6  114.87  3530.8  110.96  3571.1  112.75  3581.2  110.36
  3935.9  113.55  4034.6  110.71  4064.8  114.32  4236.1  110.39  4719.7   111.4
  4961.5   108.3  4981.5  107.56  4985.8   104.3  5031.7  109.88  5121.9  111.56
  5663.9  114.18  5930.6  111.18  5981.8  113.27  6125.5  110.71  6156.3  107.54
  6192.3  111.14  6240.1  109.63  6289.7  112.74  6433.4  110.68  6816.1  116.18
#Mann= 6 ,-1 , 0
  2321.1     .15       0  2464.1     .11       0  2663.2     .17       0
  3260.6     .11       0  4719.7     .06       0  5121.9     .11       0
Bank Sta=4719.7,5121.9
XS Rating Curve= 0 ,0
Exp/Cntr=0.3,0.1

Type RM Length L Ch R = 1 ,22648   ,256,256,256
BEGIN DESCRIPTION:
Mapping XS 798abb9b
END DESCRIPTION:
XS GIS Cut Line= 3
      3852475.64     10061451.03      3851910.11     10058614.42
      3852122.19     10056975.62
#Sta/Elev= 30
  2221.2  117.36  2230.9  114.99  2343.5  114.07  2374.1  111.11  2404.7  113.74
  2425.1  109.09  2445.5  112.91  2503.8  112.83  2792.2  115.39    2908  113.19
  3312.2   112.3    4699   108.9  4845.4  110.55  4953.9  107.43  4978.7  103.53
  5015.1  104.13  5049.6  109.97  5138.6  110.16  5550.6  110.89  5580.8  113.34
  5590.9   111.1  5621.2   113.6  5742.2  110.92  5883.3  113.68  5974.1   110.2
    6070  111.01  6095.1  107.61  6135.4  111.99  6382.1  111.41  6766.1  116.85
#Mann= 6 ,-1 , 0
  2221.2    .125       0  2503.8     .11       0    2908     .17       0
  3312.2     .11       0  4845.4     .06       0  5138.6     .11       0
Bank Sta=4845.4,5138.6
XS Rating Curve= 0 ,0
Exp/Cntr=0.3,0.1

Type RM Length L Ch R = 1 ,22392   ,392,392,392
BEGIN DESCRIPTION:
WHITE OAK CREEK WEST 42.0
END DESCRIPTION:
XS GIS Cut Line= 3
       3853708.2     10060953.13      3852150.67     10058617.28
        3852267.     10056970.79
#Sta/Elev= 30
  2192.5  116.23    2505  111.87  3586.6  113.97  3607.7  110.58  3613.7  106.32
  3628.7  105.78  3643.7  106.03  3664.8  113.33    3732  112.95  4362.7  110.42
  4628.1  111.01  4767.4  111.16  4971.4  108.39  4991.9  104.21  5016.3  107.64
  5156.6  111.15  5267.4  109.82  5547.6  113.35  5577.7   110.3  5888.4  110.46
  5918.5  113.12  5948.6  107.11  6048.8  114.85    6139   109.3  6165.1  113.44
  6170.1  111.37  6239.3  113.62  6269.4  110.65  6329.5  113.77  6650.6  116.03
#Mann= 7 ,-1 , 0
  2192.5     .11       0    3732     .15       0  4362.7     .11       0
  4628.1     .17       0  4767.4     .06       0  5156.6     .15       0
  5267.4     .11       0
Bank Sta=4767.4,5156.6
XS Rating Curve= 0 ,0
Exp/Cntr=0.3,0.1

Type RM Length L Ch R = 1 ,22000   ,382,382,382
BEGIN DESCRIPTION:
WHITE OAK CREEK WEST 41.0
END DESCRIPTION:
XS GIS Cut Line= 3
      3853719.42     10060940.62        3852418.     10058403.65
      3852297.87     10056969.17
#Sta/Elev= 30
  2148.7  115.79  2430.4  111.79    2564   114.3  3811.7  112.75  3867.1   104.6
  3917.1  112.44  3983.8  110.43  4530.4   110.6  4820.8  110.58  4823.1  110.67
  4948.9  109.58  4965.5  108.68  4987.2   102.7  5042.7  108.64  5092.9  105.38
  5223.4  110.09  5268.3  110.46  5420.1  110.42  5444.1  112.98  5474.2   110.1
  5780.5  111.53  5815.4  106.87  5845.5  112.27  6076.3  113.46  6126.5     110
  6146.6  114.52  6206.8  114.69  6246.9  111.24    6267  114.31  6439.5  115.73
#Mann= 7 ,-1 , 0
  2148.7     .11       0  3983.8     .15       0  4530.4     .17       0
  4820.8     .15       0  4823.1     .06       0  5223.4     .15       0
  5268.3     .11       0
Bank Sta=4823.1,5223.4
XS Rating Curve= 0 ,0
Exp/Cntr=0.3,0.1

Type RM Length L Ch R = 1 ,21618   ,486,486,486
BEGIN DESCRIPTION:
WHITE OAK CREEK WEST 40.0
END DESCRIPTION:
XS GIS Cut Line= 3
      3853730.92     10060928.47      3852619.39     10058393.23
       3852927.4     10056950.33
#Sta/Elev= 30
  2231.8  115.47    2491  111.59  2673.2  114.22  3725.8  112.92  4074.8  109.91
    4107   111.8  4139.5  109.83  4144.9  105.29  4191.7   104.5    4215  108.01
  4220.5  111.47  4295.4  110.17  4465.1  112.37    4525  110.28  4745.3  111.37
  4925.9  106.73  4965.3  108.23  4994.1  107.86  5010.9  103.47  5073.8  108.46
  5364.2  112.78  5533.9  109.46  5574.8  109.49  5590.8  112.59  5833.2  112.82
  5871.4  112.21    5902  106.37  5932.7  111.89  5971.5   112.8  6475.4  116.29
#Mann= 7 ,-1 , 0
  2231.8     .11       0  4295.4     .15       0    4525     .17       0
  4745.3     .15       0  4965.3     .06       0  5073.8     .15       0
  5364.2     .11       0
Bank Sta=4965.3,5073.8
XS Rating Curve= 0 ,0
Exp/Cntr=0.3,0.1

Type RM Length L Ch R = 1 ,21132   ,580,580,580
BEGIN DESCRIPTION:
WHITE OAK CREEK WEST 39.0
END DESCRIPTION:
XS GIS Cut Line= 3
      3853758.16     10060891.07      3852980.81      10058326.6
      3853197.42     10057099.47
#Sta/Elev= 30
  2320.3  114.93  2529.3  111.57  3716.4  112.48  4044.4  108.72  4504.2  111.69
  4535.6  102.73  4556.5   110.8  4613.6  109.75  4901.3  107.95  4925.7  103.96
  4974.4  106.22  4999.1  101.97  5012.2  101.97  5016.3  107.36  5056.4  108.25
    5178  109.35  5269.6  108.08  5361.5   112.6  5421.9  109.36  5452.4  112.12
  5474.9   109.2  5726.6  112.41  5760.9  106.23  5787.5  111.27  5858.6  113.32
  5987.6  113.73  5992.7   111.3  6000.8  113.77  6160.2  112.66  6246.1  115.91
#Mann= 5 ,-1 , 0
  2320.3     .11       0  4613.6     .15       0  4901.3     .09       0
  5056.4     .15       0    5178     .11       0
Bank Sta=4901.3,5056.4
XS Rating Curve= 0 ,0
Exp/Cntr=0.3,0.1

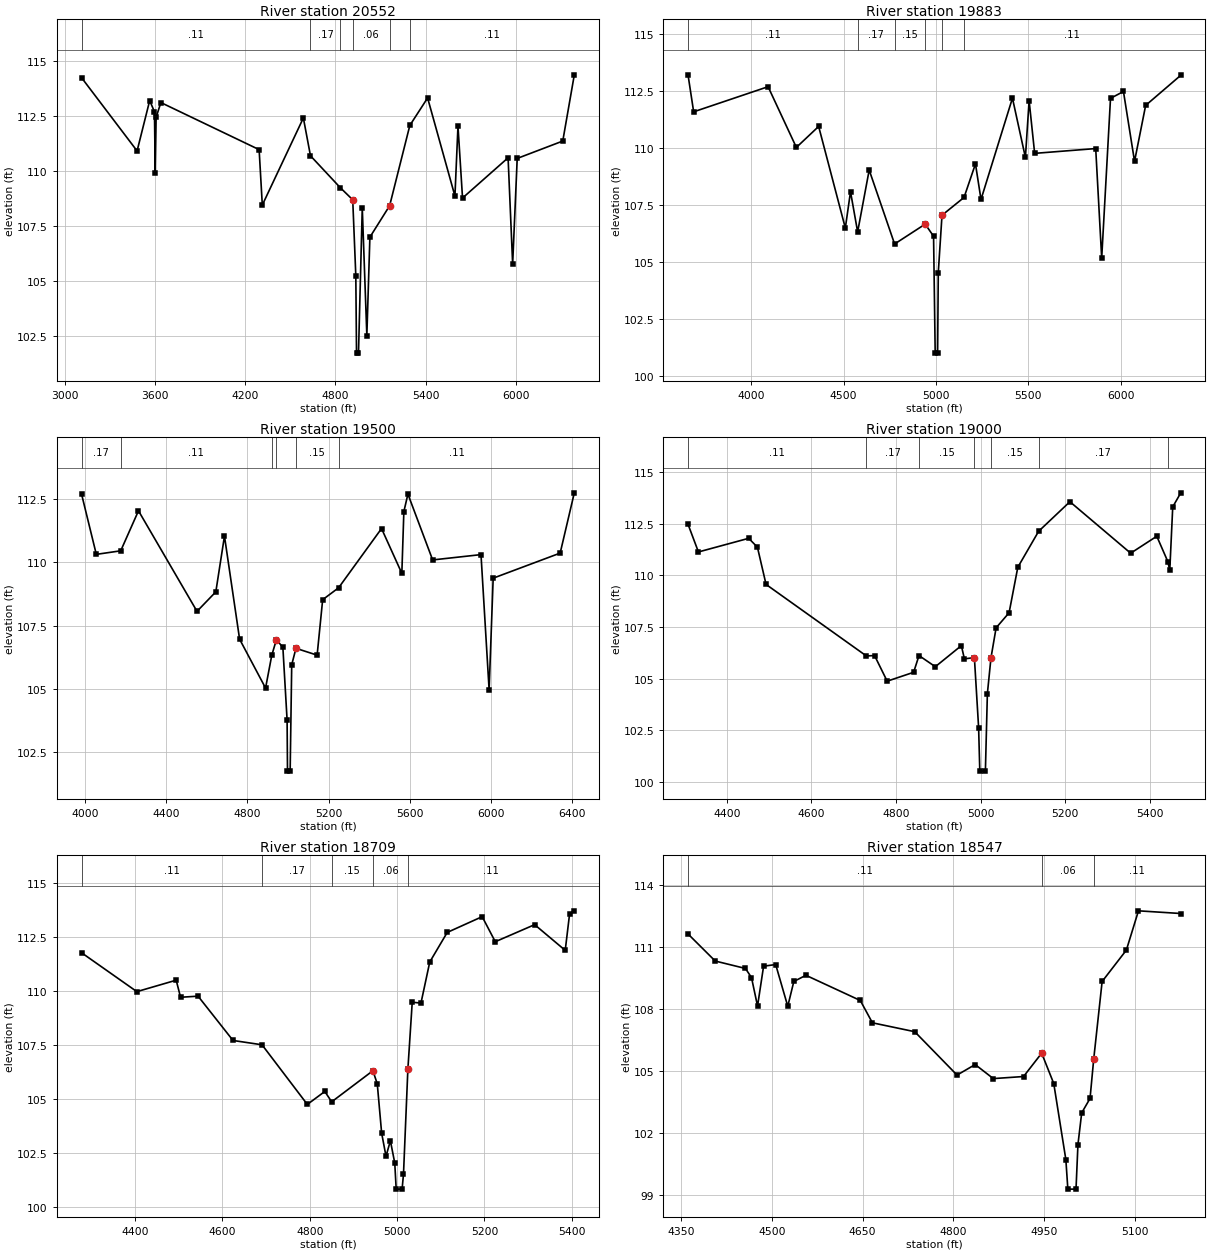
Type RM Length L Ch R = 1 ,20552   ,669,669,669
BEGIN DESCRIPTION:
WHITE OAK CREEK WEST 38.0
END DESCRIPTION:
XS GIS Cut Line= 3
      3853826.21     10060391.49      3853234.74      10058599.9
      3853421.11     10057225.08
#Sta/Elev= 30
  3113.3  114.24  3482.3  110.91    3566   113.2  3597.7  112.69    3603  109.91
  3608.7  112.44  3640.3  113.11  4293.2  110.97  4314.3  108.45  4587.1  112.41
  4634.4  110.69  4832.5  109.24  4915.1  108.69  4935.6  105.24  4940.3  101.72
  4953.4  101.72  4978.5  108.32  5008.9  102.52  5029.1  106.99  5160.3  108.42
  5294.5  112.07  5412.6  113.32  5594.2  108.86  5614.4  112.04  5644.7  108.77
  5947.4   110.6  5977.7  105.77    6008  110.57  6310.7  111.36  6387.4  114.37
#Mann= 6 ,-1 , 0
  3113.3     .11       0  4634.4     .17       0  4832.5     .11       0
  4915.1     .06       0  5160.3     .15       0  5294.5     .11       0
Bank Sta=4915.1,5160.3
XS Rating Curve= 0 ,0
Exp/Cntr=0.3,0.1

Type RM Length L Ch R = 1 ,19883   ,383,383,383
BEGIN DESCRIPTION:
WHITE OAK CREEK WEST 37.0
END DESCRIPTION:
XS GIS Cut Line= 3
      3853896.52     10059871.28      3853682.96     10058421.35
      3853620.45     10057221.15
#Sta/Elev= 30
    3658  113.21  3688.5  111.59  4091.4  112.69  4244.5  110.03  4365.1  110.95
  4509.5   106.5  4537.6  108.09  4576.2  106.33  4638.7  109.04  4776.2   105.8
  4941.9  106.67  4987.2  106.14    4996  101.02  5009.1  101.02  5012.7  104.55
  5032.9  107.06  5152.2  107.84    5214  109.31    5244  107.75  5414.2  112.19
  5484.3  109.59  5504.4  112.08  5534.4  109.77  5864.9  109.98  5897.3  105.18
    5945  112.18  6015.1  112.48  6075.1  109.42  6135.2  111.87  6325.4  113.19
#Mann= 6 ,-1 , 0
    3658     .11       0  4576.2     .17       0  4776.2     .15       0
  4941.9     .09       0  5032.9     .15       0  5152.2     .11       0
Bank Sta=4941.9,5032.9
XS Rating Curve= 0 ,0
Exp/Cntr=0.3,0.1

Type RM Length L Ch R = 1 ,19500   ,500,500,500
BEGIN DESCRIPTION:
WHITE OAK CREEK WEST 36.0
END DESCRIPTION:
XS GIS Cut Line= 4
      3854208.92     10059551.81      3853856.95     10058596.91
      3853764.55     10058490.79      3853738.41     10057221.37
#Sta/Elev= 30
  3982.3   112.7    4055  110.32  4175.3  110.46  4262.8  112.04  4551.2  108.07
  4643.9  108.84  4686.5  111.04  4761.1  106.97    4889  105.04  4919.5  106.33
  4942.3  106.95  4974.3  106.65  4995.1  103.78  4997.1  101.76  5010.2  101.76
  5017.9  105.96  5038.8  106.61  5143.1  106.34  5170.4  108.53  5248.9     109
  5460.5  111.34  5560.5  109.57  5570.5  112.01  5590.5   112.7  5712.3   110.1
  5950.6  110.31  5990.6  104.97  6010.6  109.38  6340.7  110.37  6410.4  112.75
#Mann= 6 ,-1 , 0
  3982.3     .17       0  4175.3     .11       0  4919.5     .15       0
  4942.3     .06       0  5038.8     .15       0  5248.9     .11       0
Bank Sta=4942.3,5038.8
XS Rating Curve= 0 ,0
Exp/Cntr=0.3,0.1

Type RM Length L Ch R = 1 ,19000   ,291,291,291
BEGIN DESCRIPTION:
WHITE OAK CREEK WEST 35.0
END DESCRIPTION:
XS GIS Cut Line= 3
      3854218.12      10059190.9      3854064.76     10058516.52
      3853959.05     10058055.69
#Sta/Elev= 30
  4308.4  112.47    4333  111.13  4451.8  111.79  4472.4  111.36  4492.8  109.56
  4729.9   106.1  4749.2  106.12    4779  104.88  4841.5  105.31  4854.2  106.12
  4892.8  105.58  4954.3   106.6  4961.5  105.96  4985.1  106.02  4995.1  102.63
  4997.9  100.53  5011.1  100.53  5015.8  104.28 5024.26106.0048  5036.4  107.46
  5067.1  108.19  5087.7  110.39  5136.9  112.13  5210.8  113.56  5354.4  111.07
  5416.1  111.89  5442.3  110.66  5446.8  110.24  5453.8  113.31  5472.8  113.99
#Mann= 7 ,-1 , 0
  4308.4     .11       0  4729.9     .17       0  4854.2     .15       0
  4985.1     .06       0 5024.26     .15       0  5136.9     .17       0
  5442.3     .11       0
Bank Sta=4985.1,5024.26
XS Rating Curve= 0 ,0
Exp/Cntr=0.3,0.1

Type RM Length L Ch R = 1 ,18709   ,162,162,162
BEGIN DESCRIPTION:
Mapping XS f73c2124
END DESCRIPTION:
XS GIS Cut Line= 2
      3854236.89     10059197.57      3854275.17     10058070.32
#Sta/Elev= 30
  4277.8  111.77  4404.4  109.97  4494.4   110.5  4504.4  109.71  4544.5  109.76
  4624.5  107.71  4690.9  107.51  4794.6  104.75  4834.6  105.35  4850.3  104.87
  4944.7  106.31  4954.7   105.7  4964.7  103.42  4974.7  102.35  4984.7  103.07
  4994.7  102.04    4998  100.83  5011.5  100.83  5014.7  101.52  5024.7  106.37
  5034.7  109.48  5054.7  109.44  5074.8  111.34  5114.8  112.71  5194.8  113.44
  5224.8  112.28  5314.9  113.07  5384.9  111.88  5394.9  113.57  5405.7  113.71
#Mann= 5 ,-1 , 0
  4277.8     .11       0  4690.9     .17       0  4850.3     .15       0
  4944.7     .06       0  5024.7     .11       0
Bank Sta=4944.7,5024.7
XS Rating Curve= 0 ,0
Exp/Cntr=0.3,0.1

Type RM Length L Ch R = 1 ,18547   ,547,547,547
BEGIN DESCRIPTION:
WHITE OAK CREEK WEST 34.0
END DESCRIPTION:
XS GIS Cut Line= 3
      3854428.07     10059126.03      3854426.77     10058601.25
      3854417.85     10058311.07
#Sta/Elev= 30
  4361.3  111.62  4406.3  110.31  4456.3  109.95  4466.3  109.51  4476.3  108.13
  4486.3  110.06  4506.3  110.14  4526.3  108.12  4536.3  109.32  4556.3  109.62
  4646.3   108.4  4666.3  107.32  4736.3  106.89  4806.3  104.79  4836.3   105.3
  4866.3  104.62  4916.3  104.72  4946.3  105.85  4966.3  104.38  4986.3   100.7
  4989.6   99.27  5003.1   99.27  5006.3  101.43  5012.5  102.96  5026.3  103.66
 5032.38105.5631  5046.3  109.32  5086.4  110.84  5106.4  112.74  5176.4  112.61
#Mann= 3 , 0 , 0
  4361.3     .11       0  4946.3     .06       0 5032.38     .11       0
Bank Sta=4946.3,5032.38
XS Rating Curve= 0 ,0
Exp/Cntr=0.3,0.1

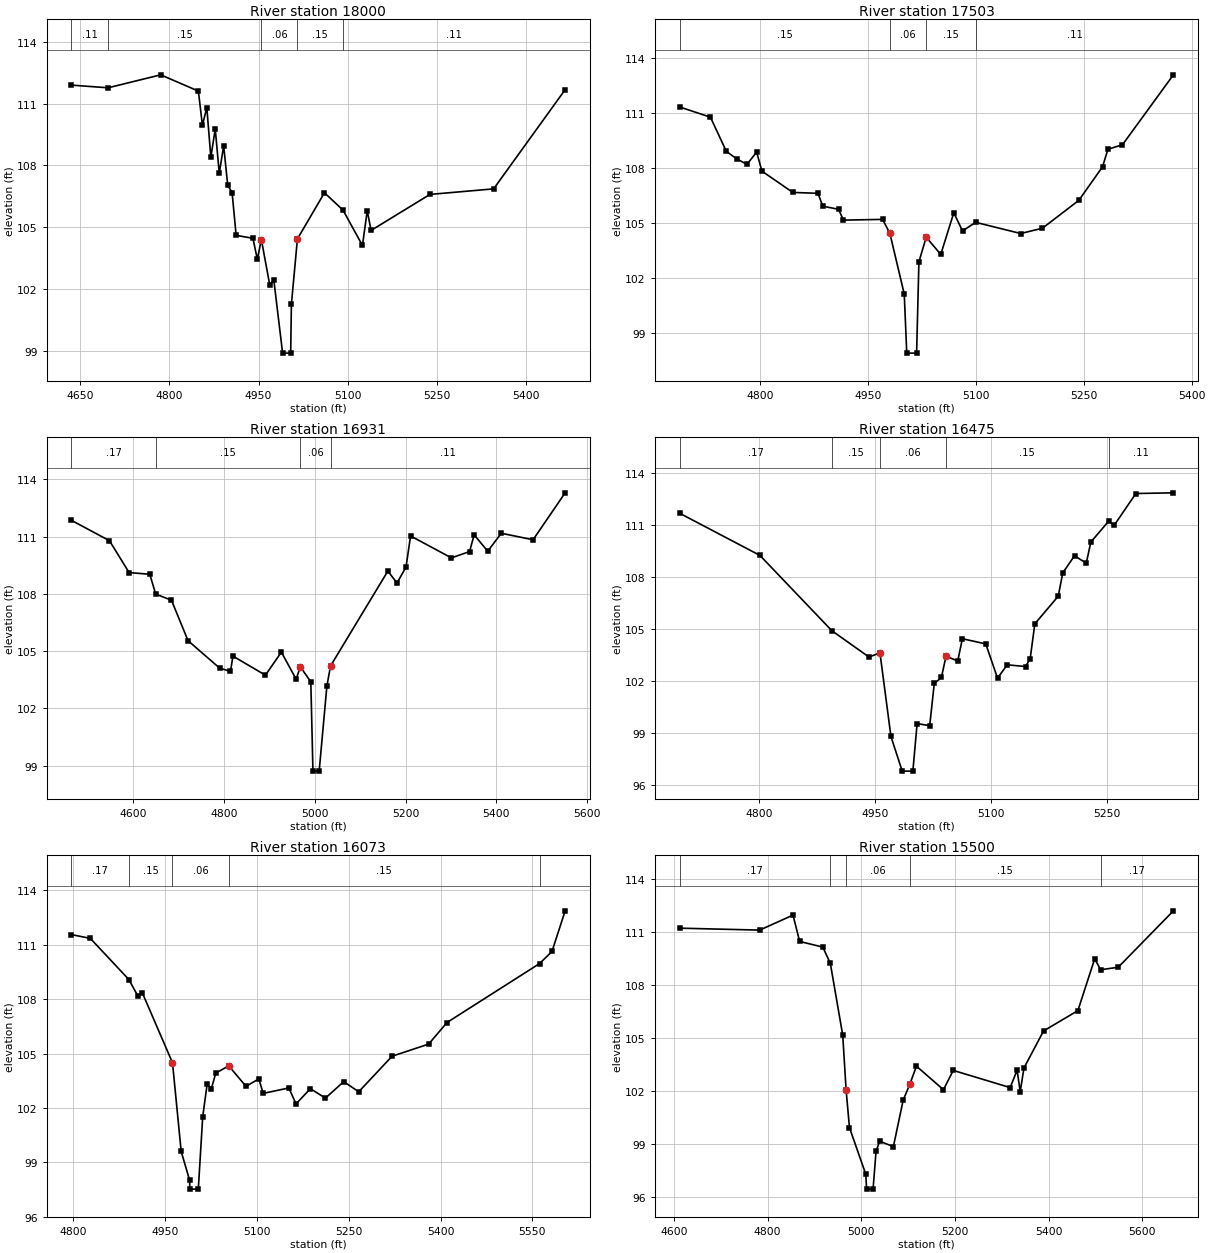
Type RM Length L Ch R = 1 ,18000   ,497,497,497
BEGIN DESCRIPTION:
WHITE OAK CREEK WEST 33.0
END DESCRIPTION:
XS GIS Cut Line= 3
      3855129.44     10058811.73      3854859.61     10058565.49
      3854568.72     10058200.67
#Sta/Elev= 30
  4634.7   111.9  4696.6  111.77  4785.2   112.4  4848.7  111.61  4855.5  109.95
  4862.9  110.81  4869.7   108.4  4877.1  109.77  4883.9  107.62  4891.3  108.95
  4898.1  107.04  4905.5  106.68  4912.3   104.6  4940.6  104.46    4948  103.44
  4954.8   104.4    4969  102.18  4975.8  102.43  4990.6   98.88  5004.2   98.88
  5005.4  101.25 5015.54104.4291  5061.1  106.67  5092.3  105.83  5125.1  104.11
  5133.2   105.8  5139.6  104.84  5238.8  106.59  5346.1  106.86  5466.6  111.68
#Mann= 5 ,-1 , 0
  4634.7     .11       0  4696.6     .15       0  4954.8     .06       0
 5015.54     .15       0  5092.3     .11       0
Bank Sta=4954.8,5015.54
XS Rating Curve= 0 ,0
Exp/Cntr=0.3,0.1

Type RM Length L Ch R = 1 ,17503   ,572,572,572
BEGIN DESCRIPTION:
WHITE OAK CREEK WEST 32.0
END DESCRIPTION:
XS GIS Cut Line= 3
      3855190.22     10058389.87      3854992.31     10058224.95
      3854567.81     10058161.06
#Sta/Elev= 30
  4687.7  111.34  4730.6  110.78  4752.7  108.92  4767.1  108.51  4781.4  108.21
  4794.9  108.88  4802.2  107.84  4845.2  106.68  4880.3  106.63  4886.8  105.93
  4908.9  105.76  4915.5  105.17  4970.1  105.21  4980.2  104.45  5000.2  101.14
  5003.7   97.92  5017.4   97.92  5020.6  102.89  5030.7  104.24    5051   103.3
  5069.1  105.57  5081.3  104.58  5099.5  105.05  5162.2  104.44  5192.5  104.73
  5243.1  106.25  5276.1  108.08  5283.5  109.03  5303.8  109.28  5374.6  113.09
#Mann= 4 ,-1 , 0
  4687.7     .15       0  4980.2     .06       0  5030.7     .15       0
  5099.5     .11       0
Bank Sta=4980.2,5030.7
XS Rating Curve= 0 ,0
Exp/Cntr=0.3,0.1

Type RM Length L Ch R = 1 ,16931   ,456,456,456
BEGIN DESCRIPTION:
WHITE OAK CREEK WEST 31.0
END DESCRIPTION:
XS GIS Cut Line= 3
      3855445.39     10058091.25      3854839.53     10057839.53
      3854407.22     10057825.65
#Sta/Elev= 30
  4463.3  111.86  4547.3  110.79  4590.6  109.12  4636.2  109.03  4649.3  107.99
    4684  107.67  4720.5  105.55  4790.2  104.11  4814.1  103.94  4819.5  104.74
  4891.1  103.74  4926.3  104.95  4958.8  103.53  4968.1  104.18  4991.2  103.39
  4995.9   98.71  5009.6   98.71  5026.6  103.16  5034.6  104.22  5161.1   109.2
  5181.1  108.57  5201.1  109.41  5211.1  111.04  5301.1  109.89  5341.2  110.22
  5351.2   111.1  5381.2  110.24  5411.2  111.18  5481.2  110.84  5551.9   113.3
#Mann= 4 ,-1 , 0
  4463.3     .17       0  4649.3     .15       0  4968.1     .06       0
  5034.6     .11       0
Bank Sta=4968.1,5034.6
XS Rating Curve= 0 ,0
Exp/Cntr=0.3,0.1

Type RM Length L Ch R = 1 ,16475   ,402,402,402
BEGIN DESCRIPTION:
WHITE OAK CREEK WEST 30.0
END DESCRIPTION:
XS GIS Cut Line= 3
      3855525.32     10058030.53      3855315.23     10057804.81
        3855037.     10057625.62
#Sta/Elev= 30
  4696.7   111.7  4800.7  109.26  4893.9   104.9  4941.9  103.38  4956.1  103.62
  4970.3   98.79  4984.9   96.78  4998.7   96.78  5004.2   99.53  5020.5   99.41
  5026.4  101.85  5035.7   102.2  5041.6  103.43  5056.8  103.15  5062.8  104.44
  5093.1  104.14  5108.3  102.16  5120.9  102.93  5144.6  102.83  5150.6  103.29
  5156.6   105.3  5186.9   106.9  5192.8  108.25    5208  109.24  5223.2  108.81
  5229.1  110.03    5252  111.23  5259.5  111.01  5287.4  112.84    5336  112.88
#Mann= 5 ,-1 , 0
  4696.7     .17       0  4893.9     .15       0  4956.1     .06       0
  5041.6     .15       0    5252     .11       0
Bank Sta=4956.1,5041.6
XS Rating Curve= 0 ,0
Exp/Cntr=0.3,0.1

Type RM Length L Ch R = 1 ,16073   ,573,573,573
BEGIN DESCRIPTION:
WHITE OAK CREEK WEST 29.0
END DESCRIPTION:
XS GIS Cut Line= 3
      3855732.38     10057740.29      3855513.66     10057531.55
      3855330.93     10057061.03
#Sta/Elev= 30
  4796.6  111.56  4827.6  111.35  4890.6  109.08  4905.3  108.17  4912.6  108.35
  4961.9  104.49  4976.1    99.6  4989.8   98.02  4990.3   97.52  5004.1   97.52
  5011.3  101.51  5018.5   103.3  5025.5  103.07  5032.7  103.92  5053.8  104.32
  5082.1  103.19    5103   103.6  5110.2   102.8  5152.1   103.1  5163.8  102.22
  5187.3  103.06  5211.9  102.54  5241.8  103.45  5266.3  102.89  5320.8  104.85
  5380.6  105.52  5410.6  106.71  5561.8  109.96  5582.2  110.63  5603.7  112.87
#Mann= 5 ,-1 , 0
  4796.6     .17       0  4890.6     .15       0  4961.9     .06       0
  5053.8     .15       0  5561.8     .11       0
Bank Sta=4961.9,5053.8
XS Rating Curve= 0 ,0
Exp/Cntr=0.3,0.1

Type RM Length L Ch R = 1 ,15500   ,500,500,500
BEGIN DESCRIPTION:
WHITE OAK CREEK WEST 28.0
END DESCRIPTION:
XS GIS Cut Line= 3
      3856263.26     10057717.39      3856006.54     10057426.86
      3855617.93     10056885.38
#Sta/Elev= 30
  4612.3  111.22  4783.3  111.11  4854.4  111.96  4868.6  110.47    4918  110.15
  4934.1  109.23  4960.6  105.17  4967.7   102.1  4974.9   99.95  5009.8   97.31
  5011.5   96.47  5025.3   96.47  5031.7    98.6  5039.3   99.18  5068.7   98.87
  5089.6   101.5  5104.3  102.43  5117.9  103.42  5175.6  102.09  5196.5  103.18
    5318  102.21  5332.8  103.19  5339.5  101.98  5347.5  103.32  5389.3  105.41
  5462.6  106.56  5498.5  109.49  5511.1  108.87  5548.7  109.01  5666.5   112.2
#Mann= 5 ,-1 , 0
  4612.3     .17       0  4934.1     .11       0  4967.7     .06       0
  5104.3     .15       0  5511.1     .17       0
Bank Sta=4967.7,5104.3
XS Rating Curve= 0 ,0
Exp/Cntr=0.3,0.1