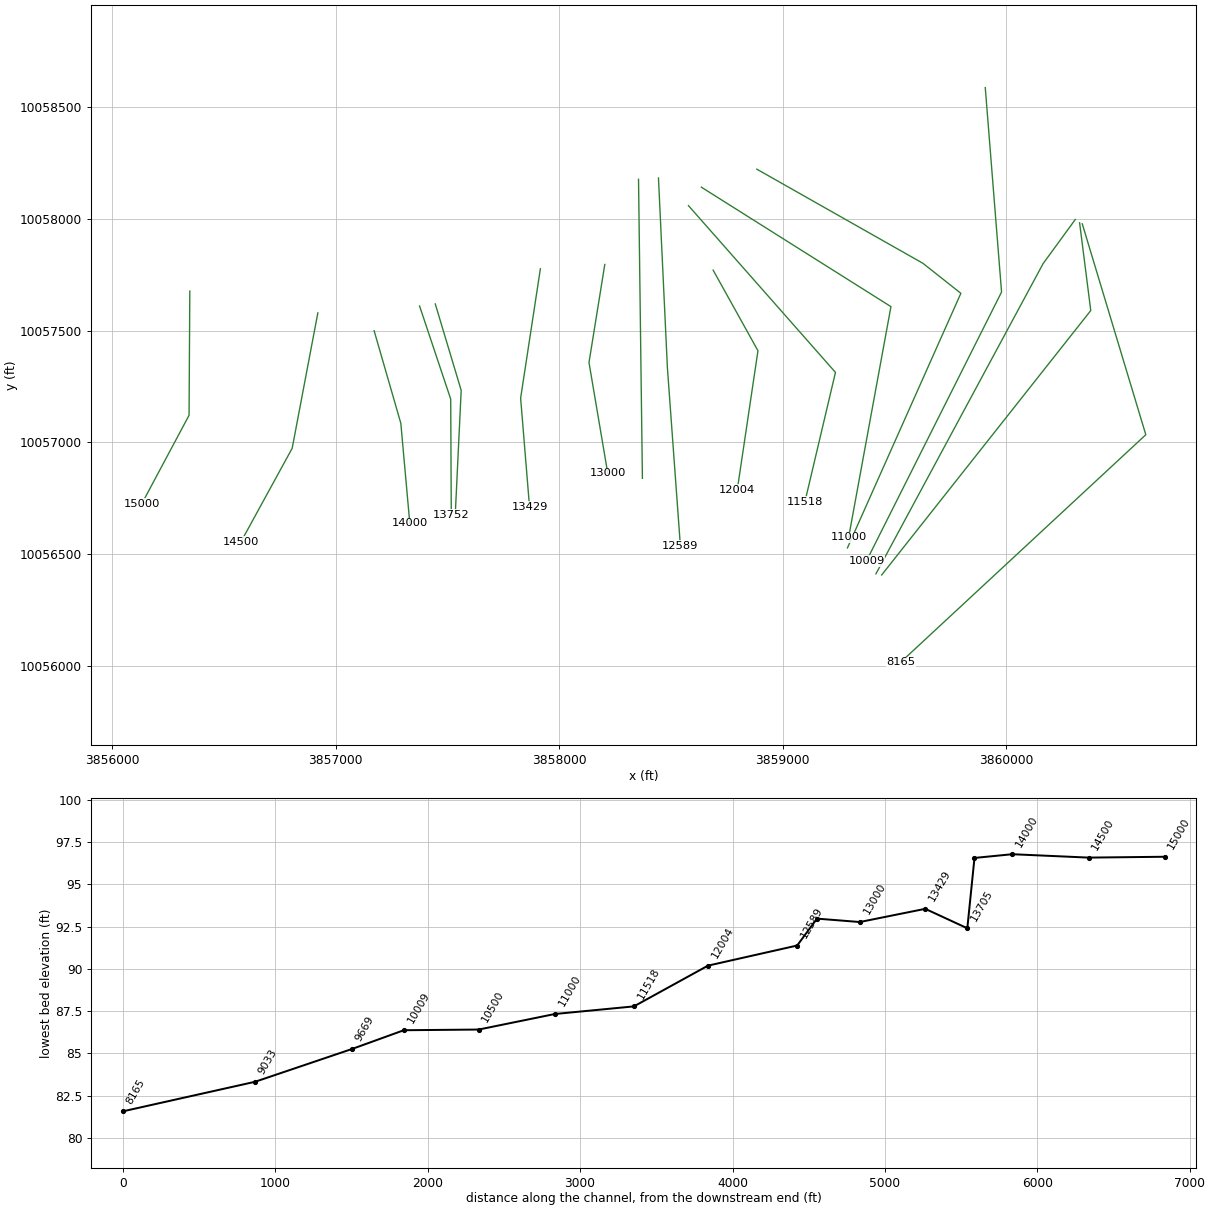
HEC-RAS study WHITE OAK CREEK WEST.prj: WHITE OAK CREEK WEST Base Level Engineering

--- WHITE OAK CREEK WEST.g01 (geometry) --- (continued)

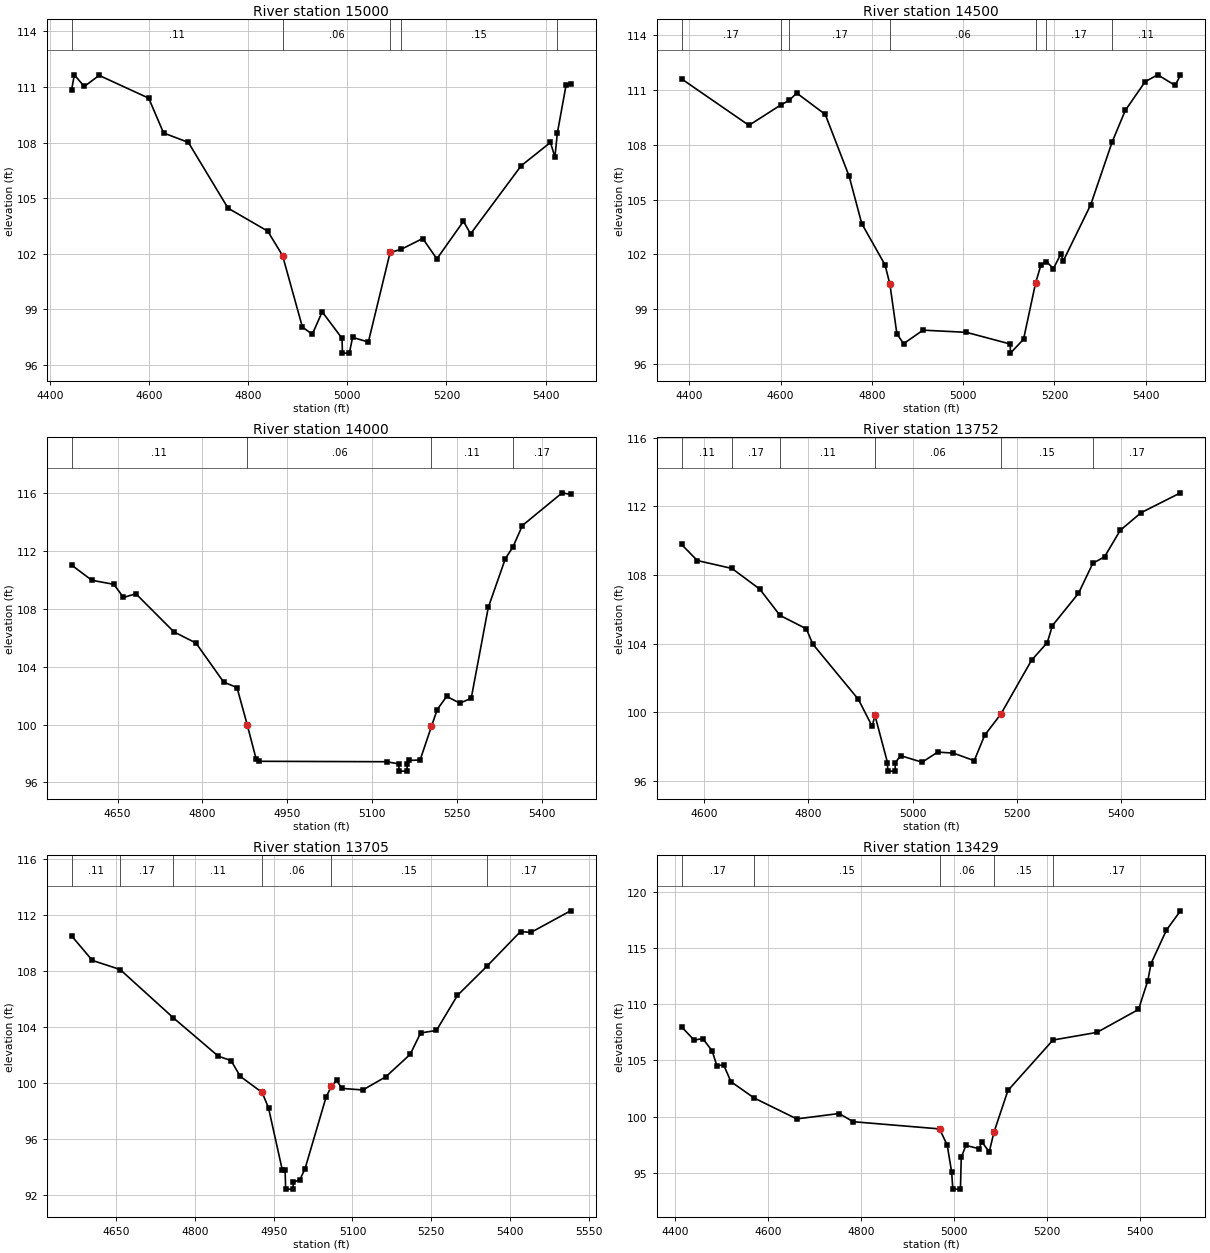
Type RM Length L Ch R = 1 ,15000   ,500,500,500
BEGIN DESCRIPTION:
WHITE OAK CREEK WEST 27.0
END DESCRIPTION:
XS GIS Cut Line= 3
      3856347.87     10057676.56      3856344.52     10057120.57
      3856132.29      10056723.2
#Sta/Elev= 30
    4444  110.85  4449.5  111.66  4469.5  111.03  4499.5  111.63  4599.5   110.4
  4629.5  108.52  4679.5  108.01  4759.5  104.46  4839.5  103.22  4869.5   101.9
  4909.5   98.04  4929.5   97.65  4949.5   98.86  4989.5   97.43  4990.3   96.63
  5004.2   96.63  5010.8   97.48  5042.6   97.23  5086.5  102.07  5108.4  102.23
  5152.3  102.82  5180.8  101.72  5234.4  103.75  5248.8  103.07  5350.9  106.75
    5410  108.01  5418.9  107.21  5423.8  108.51  5441.6  111.13  5450.5  111.18
#Mann= 5 ,-1 , 0
    4444     .11       0  4869.5     .06       0  5086.5     .11       0
  5108.4     .15       0  5423.8     .11       0
Bank Sta=4869.5,5086.5
XS Rating Curve= 0 ,0
Exp/Cntr=0.3,0.1

Type RM Length L Ch R = 1 ,14500   ,500,500,500
BEGIN DESCRIPTION:
WHITE OAK CREEK WEST 26.0
END DESCRIPTION:
XS GIS Cut Line= 3
      3856920.77     10057578.97      3856805.91     10056972.85
      3856577.41      10056555.4
#Sta/Elev= 30
  4383.1  111.62  4530.8  109.07  4600.6  110.19  4619.1  110.44  4635.4  110.84
  4697.9  109.67  4750.2  106.28  4777.9  103.68  4828.8  101.42  4839.5  100.36
  4854.8   97.64  4869.5    97.1  4912.2   97.84  5007.1   97.72    5103   97.08
  5103.5   96.58  5132.2   97.34 5158.64100.4291  5170.2   101.4    5182   101.6
  5197.7  101.22  5213.8  102.01  5219.5  101.65  5279.2  104.71  5326.6  108.18
  5355.1  109.89  5398.7  111.47  5426.2  111.84  5464.2  111.26  5475.9  111.82
#Mann= 7 ,-1 , 0
  4383.1     .17       0  4600.6     .11       0  4619.1     .17       0
  4839.5     .06       0 5158.64     .11       0    5182     .17       0
  5326.6     .11       0
Bank Sta=4839.5,5158.64
XS Rating Curve= 0 ,0
Exp/Cntr=0.3,0.1

Type RM Length L Ch R = 1 ,14000   ,248,248,248
BEGIN DESCRIPTION:
WHITE OAK CREEK WEST 25.0
END DESCRIPTION:
XS GIS Cut Line= 3
      3857172.53     10057499.11      3857292.02      10057084.8
      3857332.24      10056636.3
#Sta/Elev= 30
  4568.8  111.03  4604.6  109.98  4643.5   109.7  4660.4  108.79  4682.3  109.05
  4749.6  106.41  4788.5  105.64  4837.4  102.94    4861  102.56    4879   99.99
  4894.7   97.63  4899.9   97.46  5125.3   97.43  5146.8   97.28  5147.3   96.78
  5161.3   96.78  5161.8   97.28  5164.4   97.52  5184.5   97.55  5204.5   99.87
  5214.6  101.03  5231.4  101.95  5254.7  101.48  5274.8  101.82  5304.9   108.1
  5335.1  111.48  5348.3  112.27  5365.2  113.77  5435.5  116.03  5450.3  115.92
#Mann= 4 ,-1 , 0
  4568.8     .11       0    4879     .06       0  5204.5     .11       0
  5348.3     .17       0
Bank Sta=4879,5204.5
XS Rating Curve= 0 ,0
Exp/Cntr=0.3,0.1

Type RM Length L Ch R = 1 ,13752   ,47,47,47
BEGIN DESCRIPTION:
Mapping XS 20092637
END DESCRIPTION:
XS GIS Cut Line= 3
      3857375.84     10057609.87      3857515.18     10057193.16
      3857517.79     10056675.46
#Sta/Elev= 30
  4556.8  109.78  4587.2  108.84  4653.5  108.38  4706.7  107.18  4745.8  105.64
  4796.2  104.86  4808.6  103.97  4896.2  100.74  4922.5   99.17  4927.8   99.81
  4951.9   97.06  4952.4   96.56  4966.4   96.56  4966.9   97.06  4977.3   97.46
  5018.3   97.08  5048.3   97.67  5078.3   97.61  5118.3   97.17  5138.3   98.65
 5169.55  99.895  5228.3  103.03  5258.3  104.05  5268.3  105.05  5318.3  106.93
  5345.8  108.68  5368.3  109.06  5398.3   110.6  5438.3  111.63  5513.9  112.79
#Mann= 6 ,-1 , 0
  4556.8     .11       0  4653.5     .17       0  4745.8     .11       0
  4927.8     .06       0 5169.55     .15       0  5345.8     .17       0
Bank Sta=4927.8,5169.55
XS Rating Curve= 0 ,0
Exp/Cntr=0.3,0.1

Type RM Length L Ch R = 1 ,13705   ,276,276,276
BEGIN DESCRIPTION:
Mapping XS 2ab35044
END DESCRIPTION:
XS GIS Cut Line= 3
      3857446.18     10057618.93      3857562.06     10057232.22
      3857536.04     10056685.73
#Sta/Elev= 30
  4564.8  110.48  4604.3  108.73  4657.2  108.08  4758.7  104.63  4844.4  101.89
  4868.6  101.58  4886.2  100.45  4927.9    99.3    4940    98.2  4966.5   93.73
  4971.6   93.73  4972.7    92.4  4986.7    92.4  4987.2    92.9  4999.7   93.06
  5009.7   93.87  5049.7   98.97  5059.7   99.73  5069.8  100.17  5079.8   99.59
  5119.8   99.48  5163.5  100.42  5209.9  102.02  5229.9  103.55    5260  103.73
    5300  106.23  5356.6  108.33  5420.2  110.79  5440.2  110.73  5515.6  112.27
#Mann= 6 ,-1 , 0
  4564.8     .11       0  4657.2     .17       0  4758.7     .11       0
  4927.9     .06       0  5059.7     .15       0  5356.6     .17       0
Bank Sta=4927.9,5059.7
XS Rating Curve= 0 ,0
Exp/Cntr=0.3,0.1

Type RM Length L Ch R = 1 ,13429   ,429,429,429
BEGIN DESCRIPTION:
WHITE OAK CREEK WEST 24.0
END DESCRIPTION:
XS GIS Cut Line= 3
      3857916.44     10057776.25      3857828.06     10057197.36
      3857867.85     10056711.09
#Sta/Elev= 30
  4413.9     108  4441.1  106.81  4459.6  106.95  4479.8  105.86    4490  104.53
  4504.5  104.61  4520.3  103.11  4570.6  101.65  4661.9    99.8    4753  100.28
  4783.3   99.55  4969.1   98.91  4985.6   97.46  4995.1   95.06  4997.6   93.55
    5014   93.55  5015.8   96.39  5025.9   97.44  5054.6   97.14  5059.6   97.78
    5076   96.87  5086.1   98.61  5116.2  102.33  5213.1  106.82  5307.7   107.5
  5397.1  109.54  5417.2  112.11  5424.1  113.63  5457.3  116.61  5487.4  118.32
#Mann= 5 ,-1 , 0
  4413.9     .17       0  4570.6     .15       0  4969.1     .06       0
  5086.1     .15       0  5213.1     .17       0
Bank Sta=4969.1,5086.1
XS Rating Curve= 0 ,0
Exp/Cntr=0.3,0.1

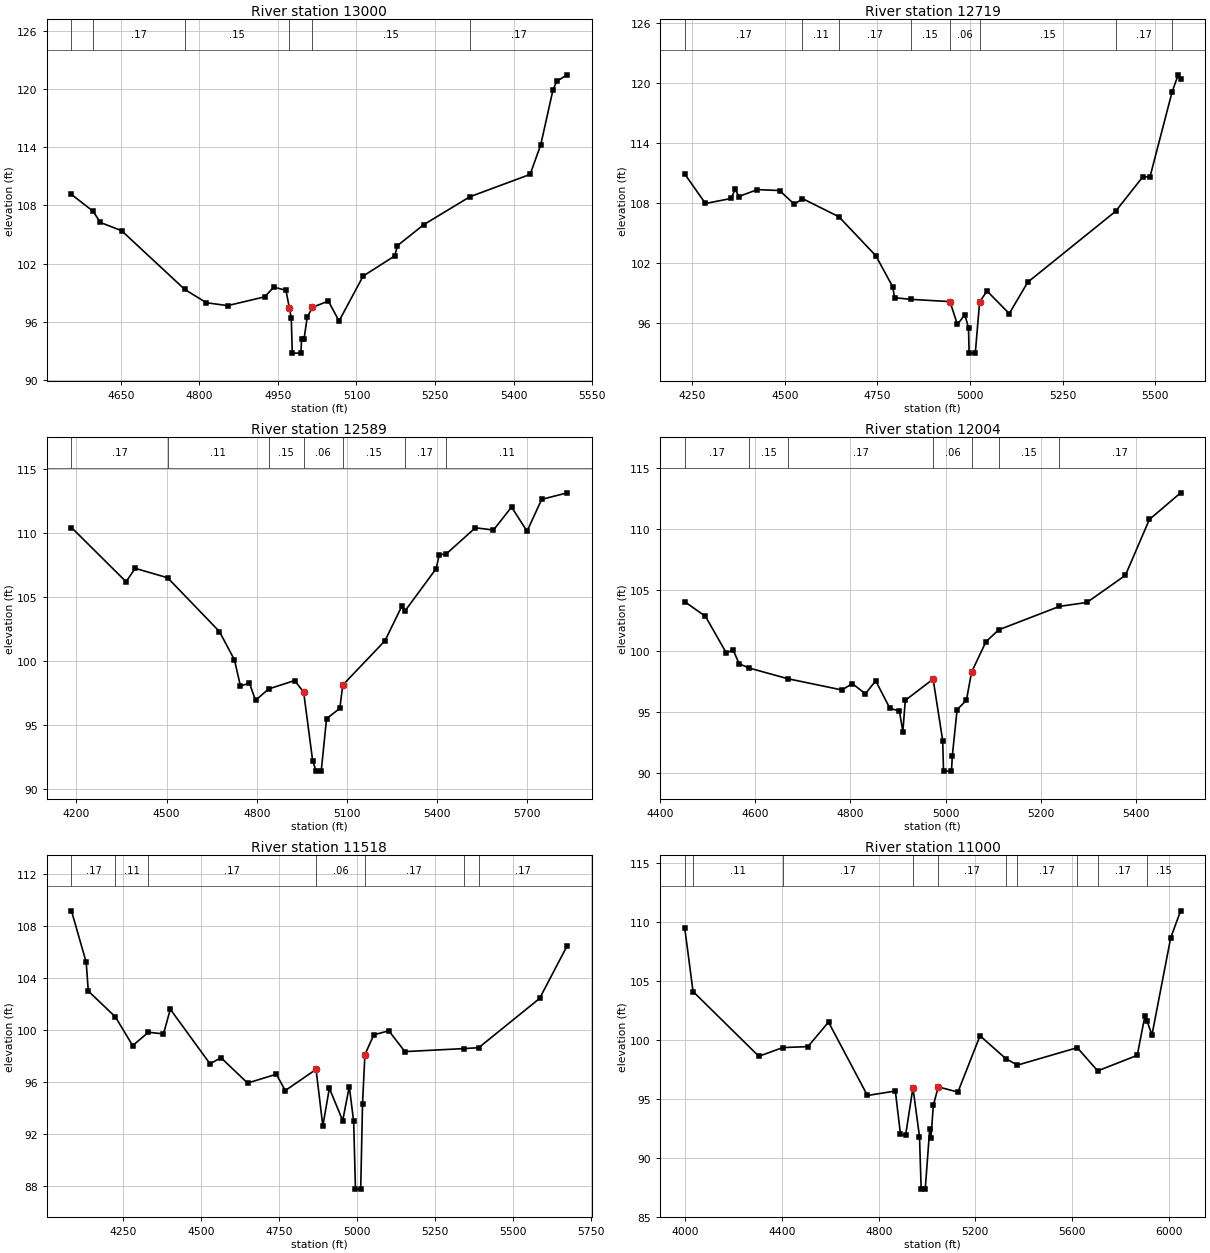
Type RM Length L Ch R = 1 ,13000   ,281,281,281
BEGIN DESCRIPTION:
WHITE OAK CREEK WEST 23.0
END DESCRIPTION:
XS GIS Cut Line= 3
      3858204.64      10057795.6      3858133.95     10057356.86
      3858217.84     10056861.11
#Sta/Elev= 30
  4555.6  109.14    4597   107.4  4610.8  106.25  4651.4   105.4    4772   99.34
  4813.3   97.97  4853.9   97.67  4924.8   98.58    4942   99.58  4965.4   99.25
  4971.7 97.4535  4975.5   96.37  4977.4   92.77  4993.8   92.77  4995.3   94.27
    5000   94.27  5005.9   96.47    5016    97.5  5046.4   98.14  5066.7   96.08
  5112.8  100.72  5173.2   102.8  5178.3  103.86  5228.5  106.02  5316.6   108.9
  5431.8  111.21  5452.1  114.28  5475.2  119.88  5482.6  120.82  5502.8  121.48
#Mann= 6 ,-1 , 0
  4555.6     .11       0    4597     .17       0    4772     .15       0
  4971.7     .06       0    5016     .15       0  5316.6     .17       0
Bank Sta=4971.7,5016
XS Rating Curve= 0 ,0
Exp/Cntr=0.3,0.1

Type RM Length L Ch R = 1 ,12719   ,130,130,130
BEGIN DESCRIPTION:
Mapping XS c284c707
END DESCRIPTION:
XS GIS Cut Line= 2
      3858355.56       10058177.      3858372.92     10056838.51
#Sta/Elev= 30
  4229.8  110.91  4285.7  107.96  4355.7  108.47  4365.7  109.42  4375.7  108.66
  4425.7  109.35  4485.7  109.26  4525.8  107.88  4547.6  108.45  4645.9  106.63
  4745.8  102.72  4791.3    99.6  4796.3   98.52  4839.4   98.36  4945.8   98.13
  4965.8   95.84  4985.8   96.82  4995.8   95.51  4997.4   92.97  5014.1   92.97
  5025.8    98.1  5045.8   99.19  5105.8   96.93  5155.8  100.08  5392.7  107.17
  5465.8  110.61  5485.8  110.64  5545.4  119.14  5561.8  120.85  5568.4  120.45
#Mann= 8 ,-1 , 0
  4229.8     .17       0  4547.6     .11       0  4645.9     .17       0
  4839.4     .15       0  4945.8     .06       0  5025.8     .15       0
  5392.7     .17       0  5545.4     .11       0
Bank Sta=4945.8,5025.8
XS Rating Curve= 0 ,0
Exp/Cntr=0.3,0.1

Type RM Length L Ch R = 1 ,12589   ,585,585,585
BEGIN DESCRIPTION:
WHITE OAK CREEK WEST 22.0
END DESCRIPTION:
XS GIS Cut Line= 3
       3858444.8     10058182.69      3858484.73     10057333.73
      3858542.85     10056536.05
#Sta/Elev= 30
  4183.7  110.42  4365.5  106.18  4395.6  107.23  4503.7  106.49  4675.9  102.29
  4725.9  100.08  4745.9   98.03  4775.9   98.26    4796   96.91  4839.7    97.8
  4926.1   98.46  4956.2   97.55  4986.2   92.18  4997.9   91.38  5014.6   91.38
  5032.4   95.48  5076.4   96.28  5086.4   98.11  5226.8  101.57  5282.4  104.25
  5292.2  103.86  5397.2  107.21  5407.2   108.3  5429.8  108.34  5527.6   110.4
  5587.7  110.22  5647.9  112.02  5699.4  110.13  5748.1  112.62  5833.4  113.13
#Mann= 7 ,-1 , 0
  4183.7     .17       0  4503.7     .11       0  4839.7     .15       0
  4956.2     .06       0  5086.4     .15       0  5292.2     .17       0
  5429.8     .11       0
Bank Sta=4956.2,5086.4
XS Rating Curve= 0 ,0
Exp/Cntr=0.3,0.1

Type RM Length L Ch R = 1 ,12004   ,486,486,486
BEGIN DESCRIPTION:
WHITE OAK CREEK WEST 21.0
END DESCRIPTION:
XS GIS Cut Line= 3
      3858689.42     10057770.17      3858889.94     10057409.51
      3858797.24     10056786.12
#Sta/Elev= 30
  4451.5  104.05  4495.1  102.85  4538.6   99.88  4553.4  100.08    4566   98.97
  4586.5   98.63  4668.3   97.75  4782.2   96.83  4803.9   97.35  4831.4   96.52
  4853.1   97.58  4882.8   95.34    4903    95.1  4910.2   93.42  4915.3   95.98
  4973.8   97.72    4994   92.69  4995.7   90.19  5012.5   90.19  5014.2   91.43
  5024.3   95.22  5043.9   95.99  5054.7   98.29    5085  100.78  5111.7  101.75
  5239.6  103.67  5297.3  103.99  5378.2  106.21  5428.7  110.78  5494.4  112.96
#Mann= 7 ,-1 , 0
  4451.5     .17       0  4586.5     .15       0  4668.3     .17       0
  4973.8     .06       0  5054.7     .17       0  5111.7     .15       0
  5239.6     .17       0
Bank Sta=4973.8,5054.7
XS Rating Curve= 0 ,0
Exp/Cntr=0.3,0.1

Type RM Length L Ch R = 1 ,11518   ,518,518,518
BEGIN DESCRIPTION:
WHITE OAK CREEK WEST 20.0
END DESCRIPTION:
XS GIS Cut Line= 3
       3858579.2      10058058.7      3859236.73     10057312.64
      3859100.35     10056734.67
#Sta/Elev= 30
  4085.4  109.19  4132.6  105.23  4139.3  103.02  4226.1  101.03  4281.5   98.82
  4331.9   99.85  4380.2   99.72    4402  101.62  4529.2   97.42  4564.3   97.89
  4649.6   95.94  4741.7   96.62  4770.1   95.36  4868.8   96.99  4890.6   92.64
  4911.5   95.54  4954.2   93.05  4975.3   95.67  4989.3   92.99  4995.1   87.78
  5011.9   87.78  5017.7   94.34  5025.3   98.12  5053.8   99.65    5102   99.96
  5153.4   98.36  5341.4   98.59  5389.8   98.66  5584.9  102.45  5673.7  106.52
#Mann= 7 ,-1 , 0
  4085.4     .17       0  4226.1     .11       0  4331.9     .17       0
  4868.8     .06       0  5025.3     .17       0  5341.4     .15       0
  5389.8     .17       0
Bank Sta=4868.8,5025.3
XS Rating Curve= 0 ,0
Exp/Cntr=0.3,0.1

Type RM Length L Ch R = 1 ,11000   ,500,500,500
BEGIN DESCRIPTION:
WHITE OAK CREEK WEST 19.0
END DESCRIPTION:
XS GIS Cut Line= 3
      3858636.71     10058141.58      3859484.94     10057606.86
      3859295.64     10056574.37
#Sta/Elev= 30
  3997.3  109.48  4031.6  104.11  4303.9   98.61  4403.2   99.35    4507   99.43
  4592.3  101.51  4753.5   95.28  4868.9   95.66  4890.1      92  4911.3    91.9
  4941.8   95.94  4968.9   91.78  4975.8   87.33  4992.6   87.33  5011.3   92.46
  5016.4    91.7  5026.2   94.45  5046.6   96.01  5127.9   95.57  5219.4  100.35
  5326.2   98.41  5374.3   97.86  5621.9   99.34  5706.4   97.37  5870.1   98.69
  5902.2  102.07    5911  101.59  5931.1  100.42  6008.5  108.66  6049.7  110.96
#Mann= 10 ,-1 , 0
  3997.3     .17       0  4031.6     .11       0  4403.2     .17       0
  4941.8     .06       0  5046.6     .17       0  5326.2     .15       0
  5374.3     .17       0  5621.9     .15       0  5706.4     .17       0
    5911     .15       0
Bank Sta=4941.8,5046.6
XS Rating Curve= 0 ,0
Exp/Cntr=0.3,0.1

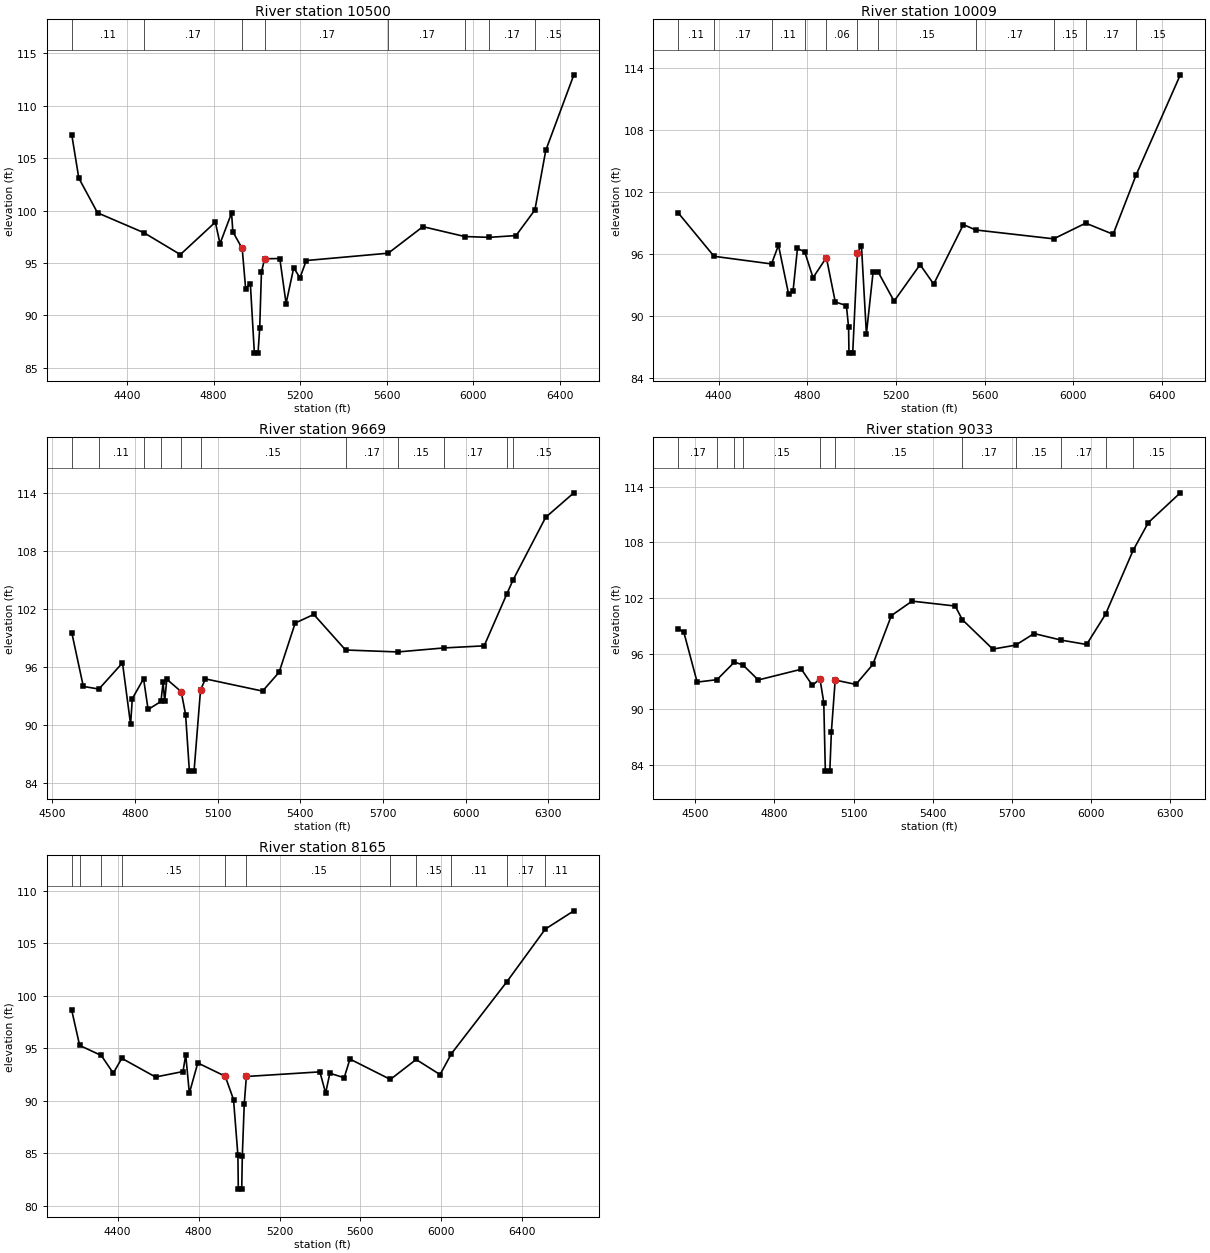
Type RM Length L Ch R = 1 ,10500   ,491,491,491
BEGIN DESCRIPTION:
WHITE OAK CREEK WEST 18.0
END DESCRIPTION:
XS GIS Cut Line= 4
       3858884.8     10058222.21      3859628.24     10057800.72
      3859797.81     10057666.51      3859290.36     10056527.06
#Sta/Elev= 30
  4145.4  107.23  4177.9   103.1  4264.4   99.79  4478.8   97.89  4646.7   95.81
  4808.3    98.9  4829.9   96.85  4883.3   99.77  4889.1   97.98  4932.3   96.39
  4948.2   92.56  4969.9   93.05  4988.5   86.41  5005.4   86.41  5013.1    88.8
  5021.1   94.11  5035.6   95.41    5106   95.43  5134.9   91.14  5170.2   94.55
    5199   93.59  5228.1   95.24  5606.7   95.94  5766.7   98.47  5959.7   97.53
  6072.2   97.45  6196.5   97.62  6283.7  100.06  6333.9  105.74  6463.6  112.95
#Mann= 8 ,-1 , 0
  4145.4     .11       0  4478.8     .17       0  4932.3     .06       0
  5035.6     .17       0  5606.7     .17       0  5959.7     .15       0
  6072.2     .17       0  6283.7     .15       0
Bank Sta=4932.3,5035.6
XS Rating Curve= 0 ,0
Exp/Cntr=0.3,0.1

Type RM Length L Ch R = 1 ,10009   ,340,340,340
BEGIN DESCRIPTION:
WHITE OAK CREEK WEST 17.0
END DESCRIPTION:
XS GIS Cut Line= 3
      3859906.96     10058587.24      3859979.88     10057672.28
      3859375.29     10056468.32
#Sta/Elev= 30
    4218   99.94  4379.5   95.74  4638.9      95  4670.2   96.81  4715.7    92.1
  4735.8   92.34  4755.9    96.5  4788.9   96.16  4826.1   93.67  4886.3   95.61
  4926.5   91.32  4976.6   90.97  4986.6   88.88  4988.2   86.37  5005.1   86.37
  5026.7   96.09  5044.6   96.75  5066.9   88.23  5096.9   94.18  5119.9   94.22
  5191.8    91.4  5309.1   94.93  5370.5   93.05  5504.5   98.81  5559.4   98.29
  5911.9   97.43  6056.3   98.95    6180   97.87  6284.5  103.65  6483.1   113.3
#Mann= 11 ,-1 , 0
    4218     .11       0  4379.5     .17       0  4638.9     .11       0
  4788.9     .17       0  4886.3     .06       0  5026.7     .11       0
  5119.9     .15       0  5559.4     .17       0  5911.9     .15       0
  6056.3     .17       0  6284.5     .15       0
Bank Sta=4886.3,5026.7
XS Rating Curve= 0 ,0
Exp/Cntr=0.3,0.1

Type RM Length L Ch R = 1 ,9669    ,636,636,636
BEGIN DESCRIPTION:
WHITE OAK CREEK WEST 16.0
END DESCRIPTION:
XS GIS Cut Line= 3
      3860309.72     10057996.91      3860165.64     10057799.24
      3859417.84     10056411.05
#Sta/Elev= 30
    4571   99.55  4612.9      94  4669.5   93.73    4755   96.43  4784.4   90.08
  4790.6   92.74  4831.5   94.79  4847.9   91.62  4894.5   92.45  4902.3   94.41
    4908   92.49  4915.8   94.74    4968   93.46  4983.9    91.1  4997.7   85.26
  5014.6   85.26  5038.193.62053  5055.6   94.78  5263.2   93.52  5323.3   95.47
  5381.5  100.54    5449  101.43  5564.2   97.76    5754   97.56  5919.6   97.97
  6067.1   98.19  6149.1  103.53  6171.9  104.99  6290.2  111.45  6392.4  113.98
#Mann= 11 ,-1 , 0
    4571     .17       0  4669.5     .11       0  4831.5     .17       0
  4894.5     .15       0    4968     .06       0  5038.1     .15       0
  5564.2     .17       0    5754     .15       0  5919.6     .17       0
  6149.1     .11       0  6171.9     .15       0
Bank Sta=4968,5038.1
XS Rating Curve= 0 ,0
Exp/Cntr=0.3,0.1

Type RM Length L Ch R = 1 ,9033    ,868,868,868
BEGIN DESCRIPTION:
WHITE OAK CREEK WEST 15.0
END DESCRIPTION:
XS GIS Cut Line= 3
      3860329.05     10057982.21      3860378.97     10057589.38
      3859443.53     10056405.92
#Sta/Elev= 30
  4435.1   98.68  4456.4   98.31  4506.8   92.93    4582   93.19  4648.3   95.09
  4680.6   94.78  4738.7   93.16  4902.2   94.32  4943.9   92.58  4972.7   93.28
  4987.2   90.72  4993.1   83.32  5010.1   83.32    5016   87.56  5030.5   93.15
    5109   92.68  5173.1   94.83  5243.6  100.11  5322.2  101.67  5485.7  101.14
  5512.7   99.67  5628.4   96.49    5715   96.92  5784.9   98.17    5888   97.46
  5984.2   96.99  6055.9  100.25  6160.4  107.14  6218.3  110.15  6339.6  113.36
#Mann= 11 ,-1 , 0
  4435.1     .17       0    4582     .15       0  4648.3     .17       0
  4680.6     .15       0  4972.7     .06       0  5030.5     .15       0
  5512.7     .17       0    5715     .15       0    5888     .17       0
  6055.9     .11       0  6160.4     .15       0
Bank Sta=4972.7,5030.5
XS Rating Curve= 0 ,0
Exp/Cntr=0.3,0.1

Type RM Length L Ch R = 1 ,8165    ,558,558,558
BEGIN DESCRIPTION:
WHITE OAK CREEK WEST 14.0
END DESCRIPTION:
XS GIS Cut Line= 3
      3860340.98     10057977.58      3860625.28     10057033.54
      3859528.72     10056015.49
#Sta/Elev= 30
    4173   98.59  4211.9   95.26  4318.9    94.3  4378.2   92.62  4420.5   94.03
  4587.1   92.25  4722.9   92.77  4736.4   94.37  4754.2    90.7    4796   93.59
  4931.7   92.32  4972.7    90.1  4994.4   84.79  4996.3   81.57  5013.3   81.57
  5016.1   84.72  5025.7   89.68  5036.2    92.3  5399.6   92.74    5428   90.72
    5449   92.61  5519.8   92.18  5548.2   93.96  5748.2   92.02  5875.4   93.92
  5993.8   92.48  6050.2   94.48  6323.9  101.32    6514  106.34  6655.2  108.08
#Mann= 11 ,-1 , 0
    4173     .17       0  4211.9     .15       0  4318.9     .17       0
  4420.5     .15       0  4931.7     .06       0  5036.2     .15       0
  5748.2     .17       0  5875.4     .15       0  6050.2     .11       0
  6323.9     .17       0    6514     .11       0
Bank Sta=4931.7,5036.2
XS Rating Curve= 0 ,0
Exp/Cntr=0.3,0.1