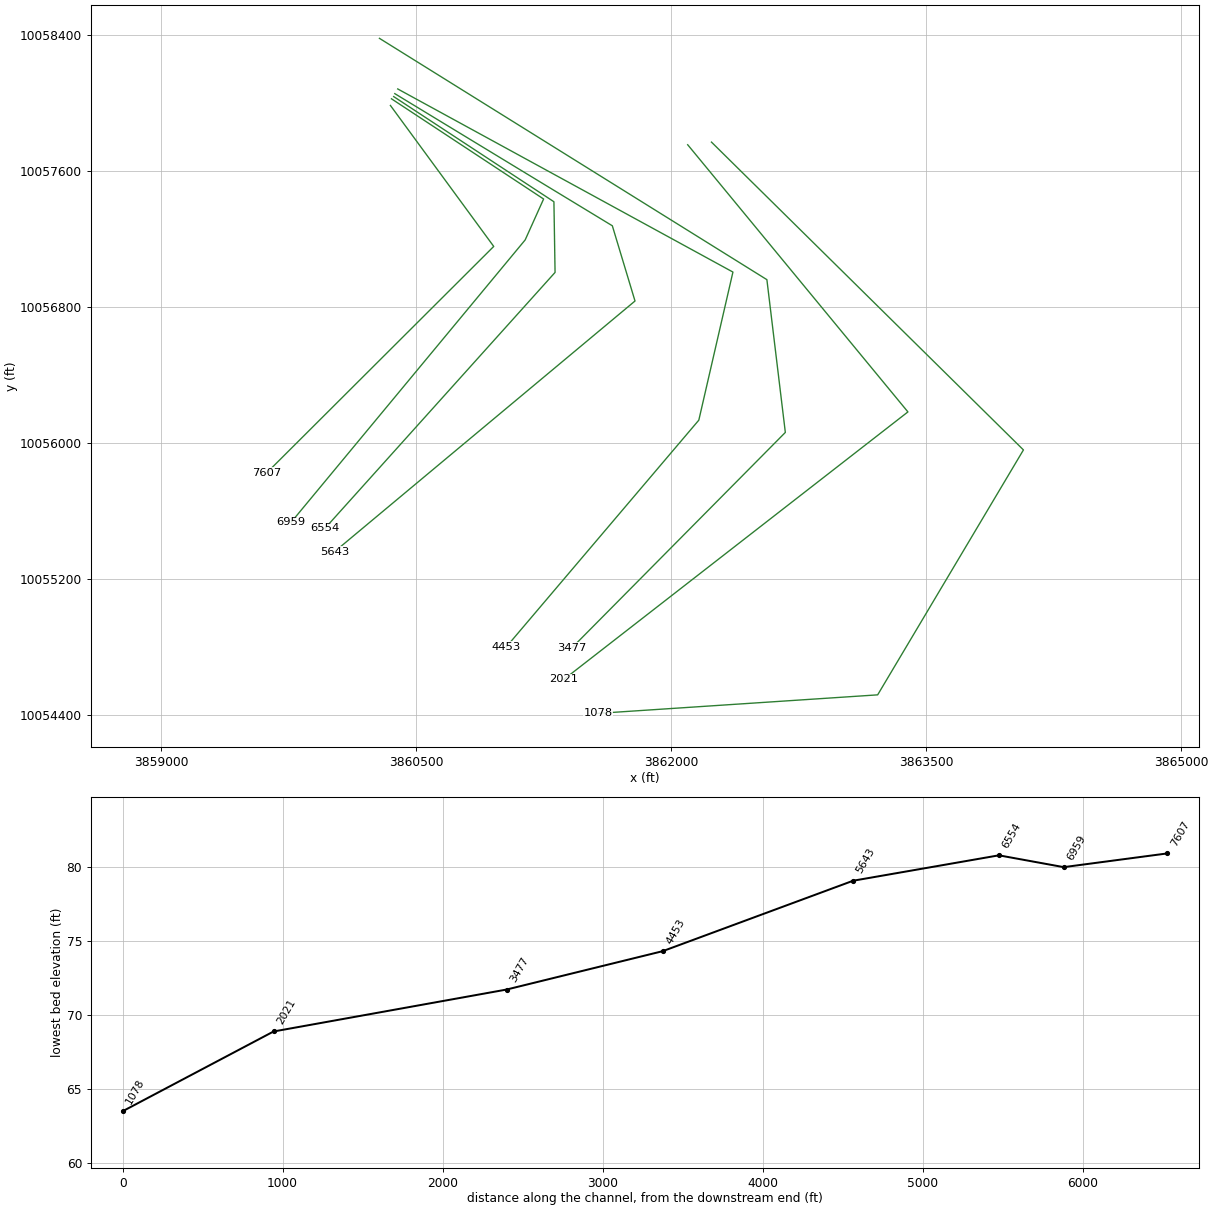
HEC-RAS study WHITE OAK CREEK WEST.prj: WHITE OAK CREEK WEST Base Level Engineering

--- WHITE OAK CREEK WEST.g01 (geometry) --- (continued)

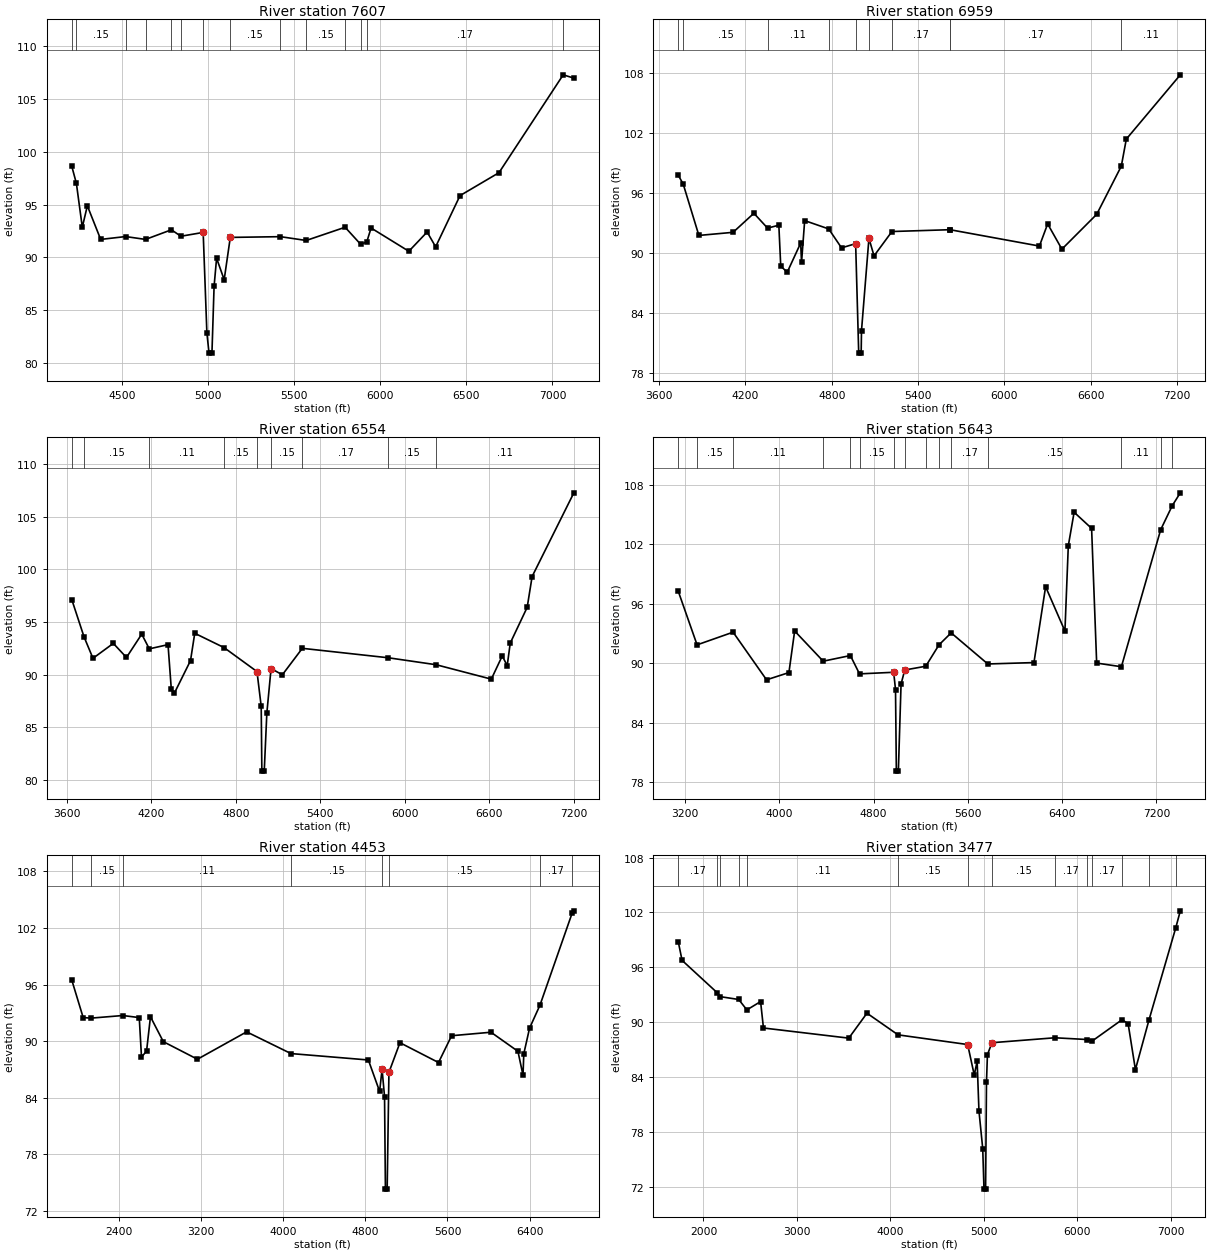
Type RM Length L Ch R = 1 ,7607    ,648,648,648
BEGIN DESCRIPTION:
WHITE OAK CREEK WEST 13.0
END DESCRIPTION:
XS GIS Cut Line= 3
      3860347.51     10057986.38      3860955.14     10057157.24
      3859619.42     10055824.98
#Sta/Elev= 30
  4209.9   98.62  4236.8   96.99    4271   92.85  4300.3   94.88  4377.7    91.7
  4522.7   91.97    4638    91.7  4788.2   92.61  4843.2      92  4972.7   92.36
  4994.2   82.87  5006.6   80.95  5023.6   80.95    5036   87.26  5050.6   89.92
  5094.6   87.89  5130.1   91.89    5421   91.96  5570.7    91.6  5796.6   92.85
  5887.3   91.23  5922.5   91.47  5947.4   92.78  6166.6   90.58  6272.7    92.4
  6322.2      91  6463.6   95.84  6689.9   98.01  7062.5  107.26  7124.4  106.95
#Mann= 14 ,-1 , 0
  4209.9     .17       0  4236.8     .15       0  4522.7     .17       0
    4638     .15       0  4788.2     .11       0  4843.2     .15       0
  4972.7     .06       0  5130.1     .15       0    5421     .17       0
  5570.7     .15       0  5796.6     .17       0  5887.3     .15       0
  5922.5     .17       0  7062.5     .11       0
Bank Sta=4972.7,5130.1
XS Rating Curve= 0 ,0
Exp/Cntr=0.3,0.1

Type RM Length L Ch R = 1 ,6959    ,405,405,405
BEGIN DESCRIPTION:
WHITE OAK CREEK WEST 12.0
END DESCRIPTION:
XS GIS Cut Line= 4
      3860353.71      10058025.5      3861248.43     10057436.13
      3861140.04      10057195.6       3859764.3     10055535.86
#Sta/Elev= 30
  3732.9   97.77  3767.5   96.88  3876.4   91.76  4114.3   92.07  4258.9   93.97
    4354   92.49  4432.4   92.78  4445.6    88.7  4490.8   88.09  4584.2      91
  4590.2   89.06    4612   93.24    4779   92.41  4868.4   90.52  4966.4   90.94
  4987.8   80.02  5004.8   80.02  5007.2   82.27  5058.9   91.47  5094.3   89.72
  5218.8   92.15  5619.1   92.33  5619.2   92.34  6244.2    90.7  6301.5   92.91
  6400.5   90.39  6642.8   93.87  6813.6   98.67  6848.5  101.37  7223.9  107.78
#Mann= 10 ,-1 , 0
  3732.9     .17       0  3767.5     .15       0    4354     .11       0
    4779     .15       0  4966.4     .06       0  5058.9     .15       0
  5218.8     .17       0  5619.1     .15       0  5619.2     .17       0
  6813.6     .11       0
Bank Sta=4966.4,5058.9
XS Rating Curve= 0 ,0
Exp/Cntr=0.3,0.1

Type RM Length L Ch R = 1 ,6554    ,911,911,911
BEGIN DESCRIPTION:
WHITE OAK CREEK WEST 11.0
END DESCRIPTION:
XS GIS Cut Line= 4
      3860366.71     10058038.54      3861309.12     10057420.03
      3861315.86     10057004.41      3859961.97     10055498.59
#Sta/Elev= 30
  3634.2   97.14  3721.1    93.6  3784.8   91.55  3929.5   92.97  4022.9   91.63
  4131.4   93.85  4185.1   92.45  4318.2   92.85  4341.3   88.65  4363.5   88.24
    4478   91.33  4508.1   93.93  4716.3   92.57  4950.4   90.29  4980.4   86.98
    4985   80.82    5002   80.82  5020.4   86.34  5050.5   90.58  5130.5   89.98
  5272.6    92.5  5884.5    91.6  6223.5   90.94  6615.6   89.57  6693.4   91.78
  6728.5   90.85  6750.2      93  6870.5    96.4  6905.6   99.33  7202.1  107.29
#Mann= 9 ,-1 , 0
  3634.2     .17       0  3721.1     .15       0  4185.1     .11       0
  4716.3     .15       0  4950.4     .06       0  5050.5     .15       0
  5272.6     .17       0  5884.5     .15       0  6223.5     .11       0
Bank Sta=4950.4,5050.5
XS Rating Curve= 0 ,0
Exp/Cntr=0.3,0.1

Type RM Length L Ch R = 1 ,5643    ,1190,1190,1190
BEGIN DESCRIPTION:
WHITE OAK CREEK WEST 9.0
END DESCRIPTION:
XS GIS Cut Line= 4
      3860373.26     10058055.87      3861652.68     10057278.68
      3861786.01     10056836.26      3860017.84     10055361.06
#Sta/Elev= 30
  3141.2   97.27  3301.1   91.85  3606.8   93.13  3890.8   88.32  4080.7   89.05
  4129.4   93.25  4371.6    90.2  4602.3   90.77  4679.9   88.92  4969.9   89.08
  4985.5   87.34  4992.7    79.1  5009.7    79.1  5032.6   87.89  5063.9   89.31
  5242.1   89.69  5354.7   91.85  5457.9   93.06  5768.9   89.92  6160.6   90.06
  6259.6   97.72  6423.6   93.24  6452.2  101.85  6501.6  105.24    6650  103.61
    6693   90.01  6902.9   89.64  7236.2  103.47  7334.3   105.9    7403   107.2
#Mann= 15 ,-1 , 0
  3141.2     .17       0  3301.1     .15       0  3606.8     .11       0
  4371.6     .15       0  4602.3     .11       0  4679.9     .15       0
  4969.9     .06       0  5063.9     .15       0  5242.1     .17       0
  5354.7     .11       0  5457.9     .17       0  5768.9     .15       0
  6902.9     .11       0  7236.2     .17       0  7334.3     .11       0
Bank Sta=4969.9,5063.9
XS Rating Curve= 0 ,0
Exp/Cntr=0.3,0.1

Type RM Length L Ch R = 1 ,4453    ,976,976,976
BEGIN DESCRIPTION:
WHITE OAK CREEK WEST 8.0
END DESCRIPTION:
XS GIS Cut Line= 4
       3860390.5     10058083.49      3862361.89      10057006.5
       3862161.3     10056135.59      3861029.38     10054802.28
#Sta/Elev= 30
  1941.8   96.48  2052.7   92.51  2125.3   92.44  2439.2   92.72  2598.9    92.5
  2620.8   88.32  2670.1   88.95  2708.1   92.59  2833.3   89.95  3165.4   88.09
  3644.6   90.99  4076.2   88.69    4830   88.01  4939.5   84.68  4963.4   87.02
  4987.5   84.13    4996   74.33    5013   74.33  5030.3    86.7  5137.5   89.84
  5513.2   87.74  5640.6   90.58  6023.9   90.95  6286.4   88.93  6335.8    86.4
  6343.6   88.67  6399.6   91.38  6501.1   93.82  6815.9  103.62  6830.9  103.81
#Mann= 8 ,-1 , 0
  1941.8     .17       0  2125.3     .15       0  2439.2     .11       0
  4076.2     .15       0  4963.4     .06       0  5030.3     .15       0
  6501.1     .17       0  6815.9     .11       0
Bank Sta=4963.4,5030.3
XS Rating Curve= 0 ,0
Exp/Cntr=0.3,0.1

Type RM Length L Ch R = 1 ,3477    ,1456,1456,1456
BEGIN DESCRIPTION:
WHITE OAK CREEK WEST 6.0
END DESCRIPTION:
XS GIS Cut Line= 4
      3860282.98     10058381.11      3862561.62     10056961.84
      3862670.13      10056063.4      3861413.86     10054795.28
#Sta/Elev= 30
  1729.9   98.81    1771   96.76    2147   93.22  2179.1   92.79  2377.2   92.48
  2464.6   91.34  2611.4   92.25  2642.1   89.36  3555.5   88.25  3750.2   90.98
    4083   88.61  4828.2   87.55  4898.7   84.21  4929.5   85.73    4949   80.28
  4989.3   76.17  5002.9   71.73    5020   71.73  5029.6   83.45  5039.7   86.44
  5088.4   87.75  5761.7   88.29  6104.8    88.1  6161.6   87.94    6481   90.27
    6546   89.82  6623.7   84.81  6769.6   90.26  7056.5  100.35  7104.4  102.18
#Mann= 14 ,-1 , 0
  1729.9     .17       0    2147     .15       0  2179.1     .11       0
  2377.2     .15       0  2464.6     .11       0    4083     .15       0
  4828.2     .06       0  5088.4     .15       0  5761.7     .17       0
  6104.8     .15       0  6161.6     .17       0    6481     .15       0
  6769.6     .17       0  7056.5     .11       0
Bank Sta=4828.2,5088.4
XS Rating Curve= 0 ,0
Exp/Cntr=0.3,0.1

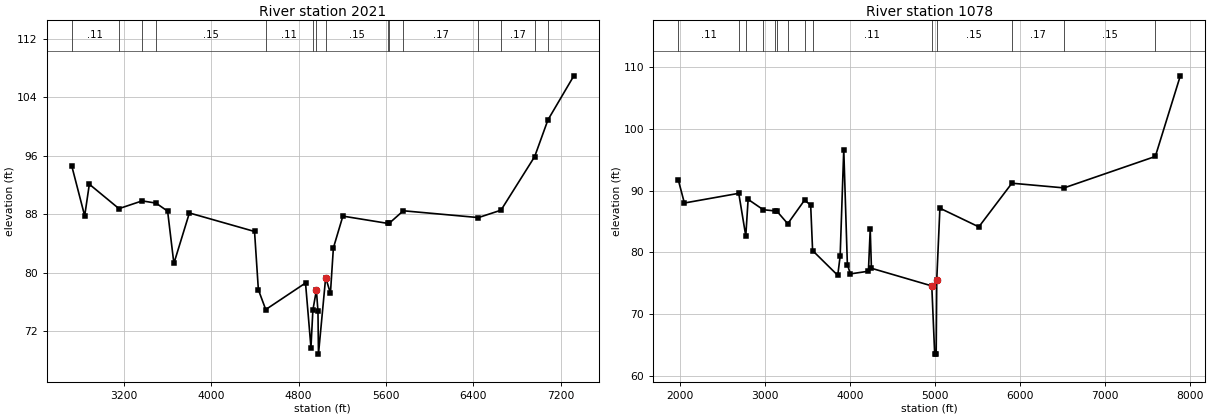
Type RM Length L Ch R = 1 ,2021    ,943,943,943
BEGIN DESCRIPTION:
WHITE OAK CREEK WEST 4.0
END DESCRIPTION:
XS GIS Cut Line= 3
      3862095.89     10057755.26      3863391.05     10056184.06
      3861367.88     10054611.09
#Sta/Elev= 30
  2721.5    94.6  2839.8   87.78  2882.4   92.11  3153.8   88.77  3365.8   89.83
  3492.7   89.53  3599.4   88.43  3656.8   81.28  3798.8   88.18  4395.6   85.65
  4430.7   77.69  4498.2   74.98  4862.6   78.61  4912.4   69.79    4930   74.91
  4962.2   77.63  4976.6   74.74  4981.2   68.89  5047.2   79.36  5090.7    77.2
  5117.8    83.4  5204.7   87.75  5613.9   86.76  5629.9   86.78  5758.4   88.48
  6446.4   87.55    6653   88.56  6961.5   95.88  7082.8  100.89  7320.4  106.92
#Mann= 15 ,-1 , 0
  2721.5     .11       0  3153.8     .15       0  3365.8     .11       0
  3492.7     .15       0  4498.2     .11       0    4930     .15       0
  4962.2     .06       0  5047.2     .15       0  5613.9     .17       0
  5629.9     .15       0  5758.4     .17       0  6446.4     .15       0
    6653     .17       0  6961.5     .15       0  7082.8     .11       0
Bank Sta=4962.2,5047.2
XS Rating Curve= 0 ,0
Exp/Cntr=0.3,0.1

Type RM Length L Ch R = 1 ,1078    ,0,0,0
BEGIN DESCRIPTION:
WHITE OAK CREEK WEST 2.0
END DESCRIPTION:
XS GIS Cut Line= 4
      3862235.67     10057770.86      3864070.42     10055960.43
       3863213.1       10054520.      3861567.85     10054411.07
#Sta/Elev= 30
  1980.5   91.77  2052.7   87.99    2692   89.56  2774.6   82.64  2802.1   88.58
  2979.9    86.9  3123.9    86.7  3140.4   86.66  3267.9   84.63  3465.9   88.46
  3537.6   87.64  3560.1   80.28  3855.8   76.26    3884   79.38  3926.5   96.66
  3968.9   78.02  4004.3    76.5  4216.4   76.93  4237.6   83.76  4251.8   77.41
  4961.4   74.55  4995.5   63.49    5013   63.49  5019.8   75.58  5056.8   87.15
  5514.4   84.12  5903.2    91.2  6516.3   90.44  7589.5   95.54  7883.2  108.61
#Mann= 14 ,-1 , 0
  1980.5     .11       0    2692     .17       0  2774.6     .15       0
  2979.9     .17       0  3123.9     .11       0  3140.4     .17       0
  3267.9     .11       0  3465.9     .17       0  3560.1     .11       0
  4961.4     .09       0  5019.8     .15       0  5903.2     .17       0
  6516.3     .15       0  7589.5     .17       0
Bank Sta=4961.4,5019.8
XS Rating Curve= 0 ,0
Exp/Cntr=0.3,0.1

Chan Stop Cuts=-1
Use User Specified Reach Order=0
Composite Channel Slope=5

--- WHITE OAK CREEK WEST.g10 (geometry) ---

Geom Title=Existing Conditions
Program Version=4.10

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
River Reach=WHITE OAK CREEK ,Reach-1

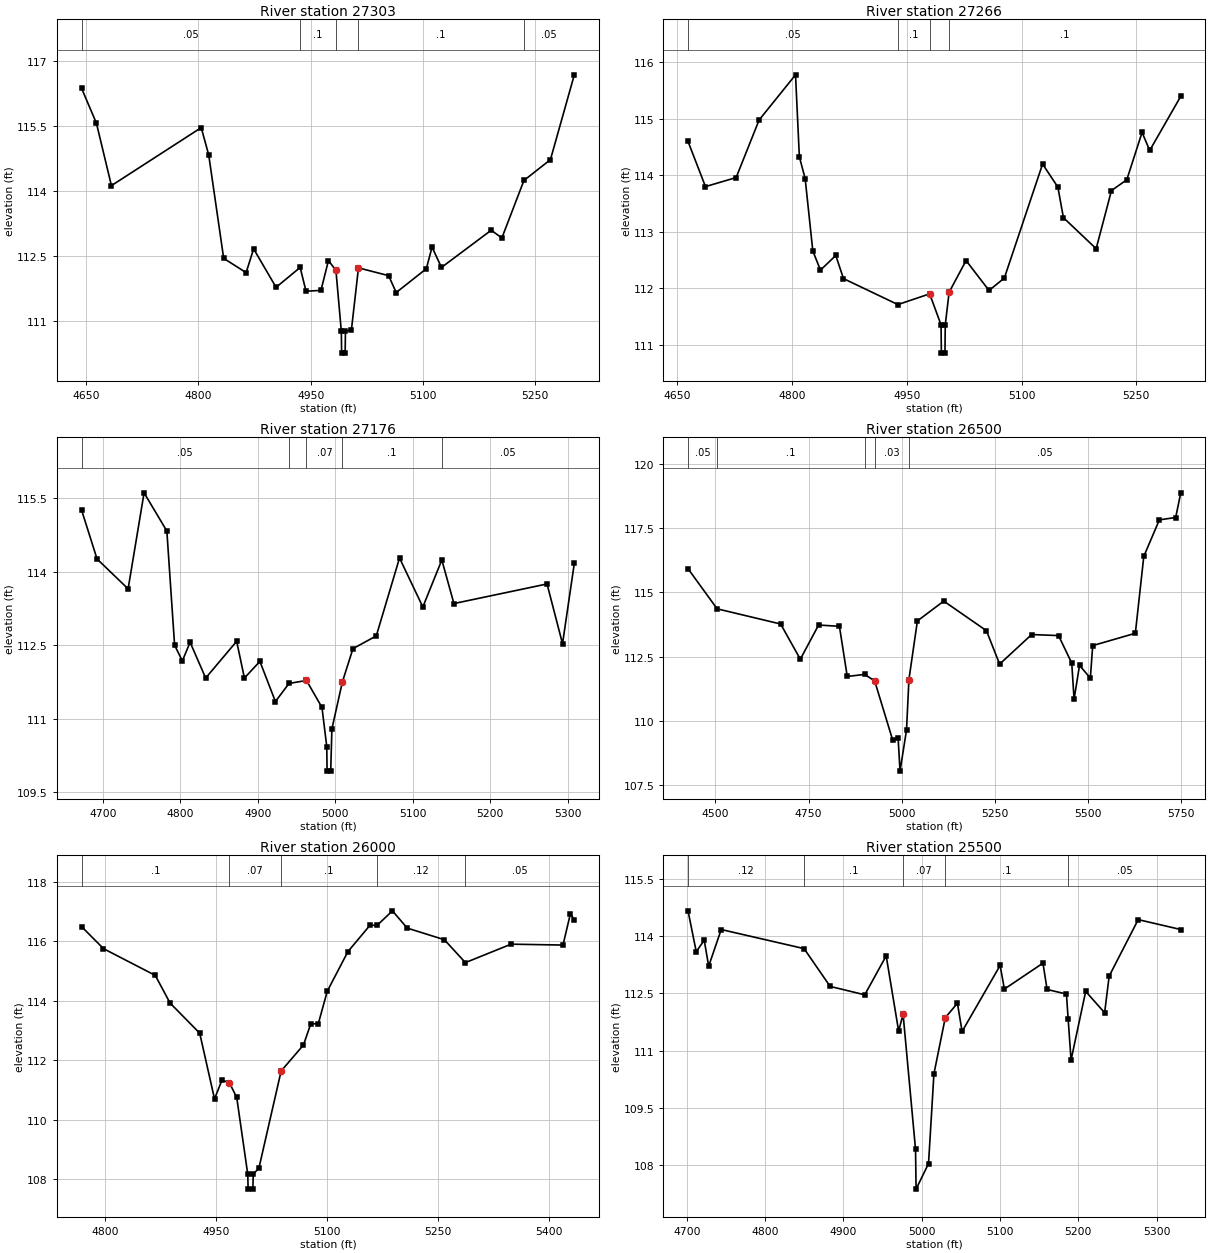
Type RM Length L Ch R = 1 ,27303   ,37,37,37
BEGIN DESCRIPTION:
WHITE OAK CREEK WEST 51.0
END DESCRIPTION:
XS GIS Cut Line= 3
      3849237.72     10059541.98      3848881.52      10059541.3
      3848581.84     10059580.27
#Sta/Elev= 30
  4643.8  116.38  4663.7  115.57  4683.7  114.13  4803.7  115.47  4813.7  114.84
  4833.7  112.45  4863.7  112.12  4873.7  112.67  4903.7  111.78  4935.9  112.24
  4943.7  111.69  4963.7  111.71  4973.7   112.4  4983.7  112.17  4990.9  110.76
  4991.3  110.26    4996  110.26  4996.4  110.76  5004.4   110.8  5013.8  112.23
  5054.1  112.05  5064.2  111.66  5104.5  112.21  5112.1  112.71  5124.7  112.24
  5191.2   113.1  5205.4  112.92  5234.9  114.25  5270.3  114.73  5302.2  116.69
#Mann= 5 ,-1 , 0
  4643.8     .05       0  4935.9      .1       0  4983.7     .07       0
  5013.8      .1       0  5234.9     .05       0
Bank Sta=4983.7,5013.8
XS Rating Curve= 0 ,0
Exp/Cntr=0.3,0.1

Type RM Length L Ch R = 1 ,27266   ,90,90,90
BEGIN DESCRIPTION:
Mapping XS 5e1510de
END DESCRIPTION:
XS GIS Cut Line= 3
      3849220.57      10059525.5      3848905.42     10059504.67
      3848577.27     10059507.27
#Sta/Elev= 30
  4664.1   114.6  4686.9   113.8    4727  113.96    4757  114.98  4804.6  115.78
  4809.6  114.33  4817.2  113.94  4827.2  112.66  4837.2  112.32  4857.2  112.58
  4867.3  112.17  4938.4  111.71  4979.9   111.9  4994.8  111.35  4995.2  110.85
  4999.9  110.85  5000.3  111.35 5005.31 111.928  5027.5  112.49  5057.5  111.96
  5077.5  112.18  5127.5   114.2  5147.5  113.79  5154.7  113.25  5197.5   112.7
  5217.5  113.73  5237.5  113.92  5257.5  114.76  5267.5  114.44  5308.1   115.4
#Mann= 4 ,-1 , 0
  4664.1     .05       0  4938.4      .1       0  4979.9     .07       0
 5005.31      .1       0
Bank Sta=4979.9,5005.31
XS Rating Curve= 0 ,0
Exp/Cntr=0.3,0.1

Type RM Length L Ch R = 1 ,27176   ,676,676,676
BEGIN DESCRIPTION:
Mapping XS 13a5a0ce
END DESCRIPTION:
XS GIS Cut Line= 3
      3849217.88     10059429.15      3848895.01     10059416.13
      3848582.68     10059397.91
#Sta/Elev= 30
  4672.7  115.26  4692.7  114.26  4732.8  113.65  4753.4  115.61  4782.8  114.83
  4792.8   112.5  4802.8  112.18  4812.8  112.56  4832.9  111.83  4872.9  112.58
  4882.9  111.83  4902.9  112.17  4922.9  111.35  4940.5  111.72    4963  111.78
    4983  111.23  4989.2  110.43  4989.6  109.93  4994.3  109.93  4995.8  110.79
 5009.35 111.751    5023  112.43  5053.1  112.69  5083.1  114.28  5113.2  113.28
  5137.7  114.24  5153.3  113.35  5273.5  113.75  5293.5  112.53  5308.7  114.17
#Mann= 5 ,-1 , 0
  4672.7     .05       0  4940.5      .1       0    4963     .07       0
 5009.35      .1       0  5137.7     .05       0
Bank Sta=4963,5009.35
XS Rating Curve= 0 ,0
Exp/Cntr=0.3,0.1

Type RM Length L Ch R = 1 ,26500   ,500,500,500
BEGIN DESCRIPTION:
WHITE OAK CREEK WEST 50.0
END DESCRIPTION:
XS GIS Cut Line= 3
      3849299.56     10059358.21      3849125.81     10058811.77
      3848528.76     10058360.18
#Sta/Elev= 30
  4426.6  115.92  4504.7  114.36    4675  113.77  4727.9   112.4  4776.9  113.73
  4832.8  113.68  4853.8  111.73  4900.1  111.81  4927.3  111.56  4975.6  109.26
  4990.2  109.35  4995.4  108.05  5012.8  109.65 5019.26 111.611    5042  113.89
  5112.7  114.66  5227.2  113.51  5262.6  112.21  5348.5  113.36  5420.7  113.32
  5456.1  112.25  5462.3  110.84  5476.9  112.16    5506  111.67  5512.3  112.93
  5626.7  113.41  5649.4   116.4  5691.2  117.82  5734.9  117.91  5748.6  118.87
#Mann= 5 ,-1 , 0
  4426.6     .05       0  4504.7      .1       0  4900.1     .05       0
  4927.3     .03       0 5019.26     .05       0
Bank Sta=4927.3,5019.26
XS Rating Curve= 0 ,0
Exp/Cntr=0.3,0.1

Type RM Length L Ch R = 1 ,26000   ,500,500,500
BEGIN DESCRIPTION:
WHITE OAK CREEK WEST 49.0
END DESCRIPTION:
XS GIS Cut Line= 3
       3849497.7     10059220.65      3849497.13     10058988.85
      3849522.64      10058555.8
#Sta/Elev= 30
  4768.2  116.49  4797.8  115.75  4867.8  114.85  4887.8  113.92  4927.8  112.91
  4947.8   110.7  4957.8  111.33  4967.8  111.25  4977.8  110.75  4992.7  108.17
  4993.2  107.67  4999.6  107.67  5000.1  108.17  5007.8  108.38  5037.8  111.64
  5067.9  112.51  5077.9  113.23  5087.9  113.22  5100.1  114.32    5128  115.65
    5158  116.54  5167.4  116.53  5188.1  117.02  5208.1  116.44  5258.2  116.05
  5286.7  115.28  5348.4   115.9  5418.5  115.87  5428.5  116.92  5433.8  116.72
#Mann= 5 ,-1 , 0
  4768.2      .1       0  4967.8     .07       0  5037.8      .1       0
  5167.4     .12       0  5286.7     .05       0
Bank Sta=4967.8,5037.8
XS Rating Curve= 0 ,0
Exp/Cntr=0.3,0.1

Type RM Length L Ch R = 1 ,25500   ,500,500,500
BEGIN DESCRIPTION:
WHITE OAK CREEK WEST 48.0
END DESCRIPTION:
XS GIS Cut Line= 3
      3849849.92     10059269.22      3849996.71     10059009.19
      3850115.53     10058700.25
#Sta/Elev= 30
  4701.4  114.66  4711.9  113.59  4722.1  113.89  4727.8  113.21  4743.8  114.17
  4849.7  113.67    4883  112.68  4927.2  112.46  4954.6  113.48  4970.5  111.51
  4976.2  111.95  4992.1  108.41  4992.8  107.37  5008.7  108.04  5015.6  110.39
  5030.1  111.86  5045.6  112.24  5051.6   111.5  5100.2  113.23  5105.6  112.61
  5154.9  113.29  5160.2   112.6  5184.9  112.48  5187.1  111.83  5190.8  110.75
  5209.5  112.55  5233.7  111.99  5239.5  112.95  5276.6  114.43    5331  114.17
#Mann= 5 ,-1 , 0
  4701.4     .12       0  4849.7      .1       0  4976.2     .07       0
  5030.1      .1       0  5187.1     .05       0
Bank Sta=4976.2,5030.1
XS Rating Curve= 0 ,0
Exp/Cntr=0.3,0.1

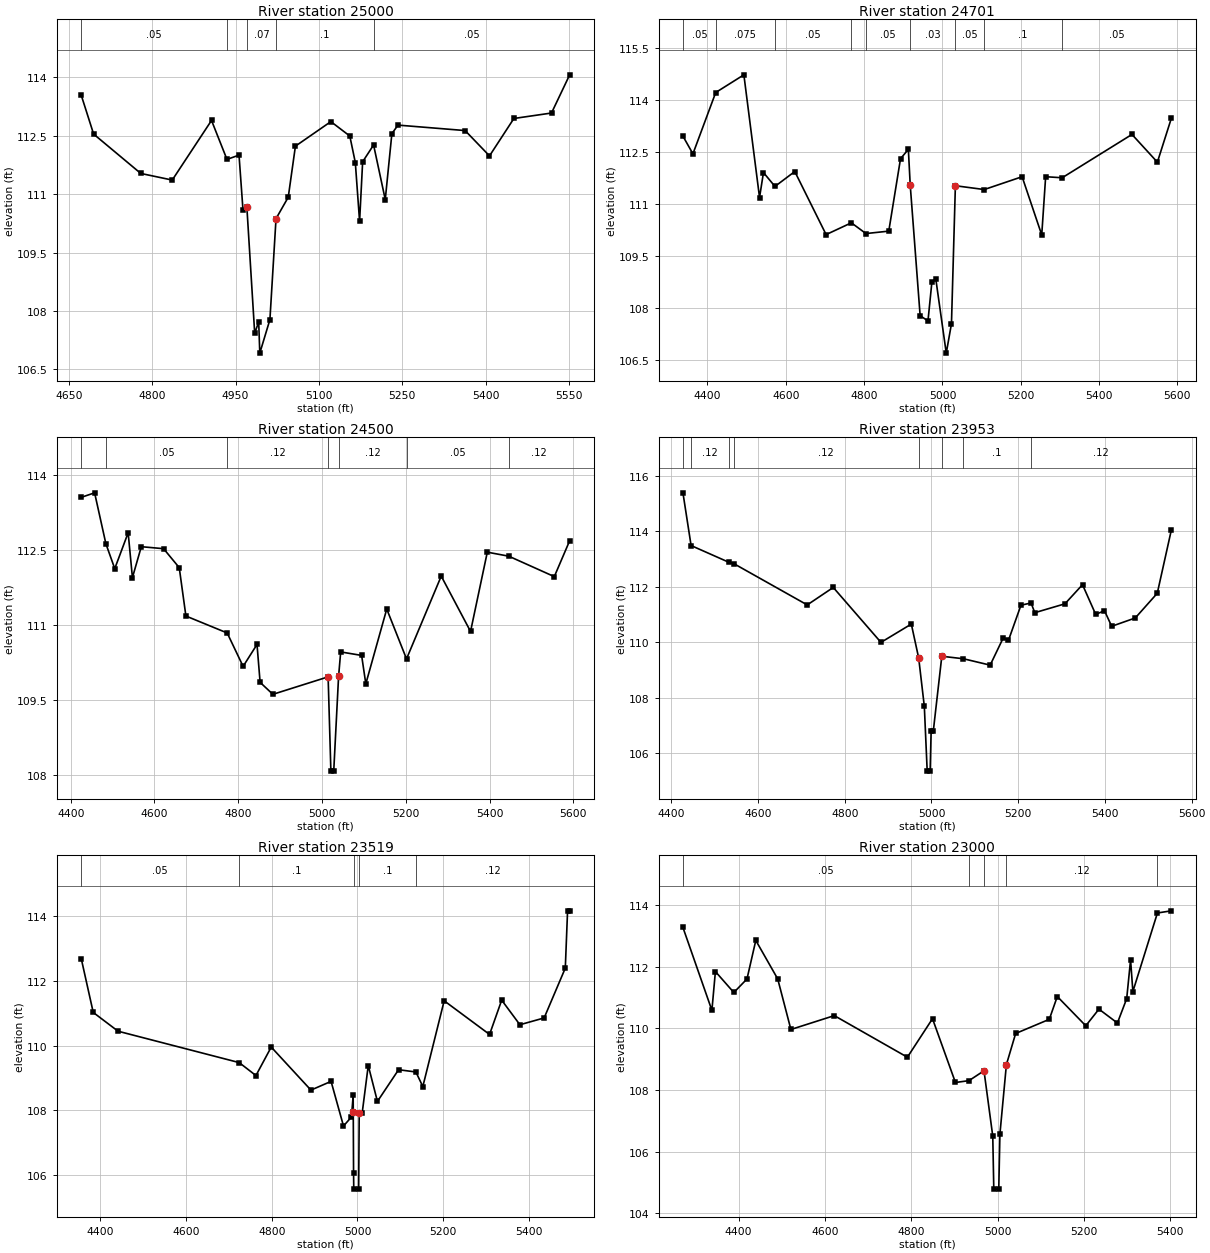
Type RM Length L Ch R = 1 ,25000   ,299,299,299
BEGIN DESCRIPTION:
WHITE OAK CREEK WEST 47.0
END DESCRIPTION:
XS GIS Cut Line= 3
      3850115.52     10059540.09      3850350.46     10059311.93
      3850577.79     10058809.57
#Sta/Elev= 30
  4672.5  113.53  4694.6  112.54  4779.5  111.53  4836.1  111.36  4906.8  112.89
  4934.6  111.89  4956.3     112  4963.4   110.6  4970.4  110.67  4984.5  107.43
  4991.7  107.72  4993.7  106.92  5011.9  107.78  5022.9  110.37  5044.9  110.92
  5057.8  112.23  5121.6  112.86  5155.7  112.49  5165.6  111.81  5173.3   110.3
  5178.8  111.83  5198.5  112.26  5219.5  110.86  5231.4  112.55  5242.4  112.77
  5363.2  112.63  5407.1  111.98    5451  112.94  5518.7  113.08  5551.4  114.06
#Mann= 5 ,-1 , 0
  4672.5     .05       0  4934.6      .1       0  4970.4     .07       0
  5022.9      .1       0  5198.5     .05       0
Bank Sta=4970.4,5022.9
XS Rating Curve= 0 ,0
Exp/Cntr=0.3,0.1

Type RM Length L Ch R = 1 ,24701   ,201,201,201
BEGIN DESCRIPTION:
Mapping XS 71a0bb95
END DESCRIPTION:
XS GIS Cut Line= 3
      3850605.16      10060106.6      3850618.18     10059451.18
      3850655.08     10058860.89
#Sta/Elev= 30
  4337.3  112.97  4362.8  112.46    4421  114.23  4492.9  114.74  4532.9   111.2
  4542.9  111.92  4572.3  111.52  4622.9  111.95  4702.9  110.13  4767.4  110.47
  4804.6  110.16  4862.9  110.23  4892.9  112.32  4912.9  112.59 4917.74 111.549
    4943  107.79    4963  107.64    4973  108.76    4983  108.85  5009.7  106.71
    5023  107.56    5033  111.54  5106.7  111.43  5203.4   111.8  5253.5  110.12
  5263.5   111.8  5305.7  111.77  5483.9  113.02  5548.8  112.22  5584.3  113.48
#Mann= 9 ,-1 , 0
  4337.3     .05       0    4421    .075       0  4572.3     .05       0
  4767.4     .12       0  4804.6     .05       0 4917.74     .03       0
    5033     .05       0  5106.7      .1       0  5305.7     .05       0
Bank Sta=4917.74,5033
XS Rating Curve= 0 ,0
Exp/Cntr=0.3,0.1

Type RM Length L Ch R = 1 ,24500   ,547,547,547
BEGIN DESCRIPTION:
WHITE OAK CREEK WEST 46.0
END DESCRIPTION:
XS GIS Cut Line= 3
      3850917.85     10060011.05      3850814.53     10059445.71
      3850809.56     10058854.33
#Sta/Elev= 30
  4425.3  113.56    4457  113.65  4483.9  112.63  4505.1  112.13  4537.1  112.85
  4547.3  111.95  4568.5  112.57  4621.7  112.53  4659.1  112.15    4675  111.18
  4773.6  110.84  4811.6  110.17  4844.8  110.61  4852.2  109.85  4882.7  109.61
  5014.6  109.96  5021.2  108.07    5028  108.07 5039.58 109.968  5044.6  110.46
  5094.6  110.39  5104.6  109.82  5154.6  111.32  5201.8  110.32  5284.7  111.98
  5354.7  110.87  5394.7  112.46  5445.9  112.38  5554.7  111.97  5591.4  112.69
#Mann= 7 ,-1 , 0
  4425.3    .075       0  4483.9     .05       0  4773.6     .12       0
  5014.6     .07       0 5039.58     .12       0  5201.8     .05       0
  5445.9     .12       0
Bank Sta=5014.6,5039.58
XS Rating Curve= 0 ,0
Exp/Cntr=0.3,0.1

Type RM Length L Ch R = 1 ,23953   ,434,434,434
BEGIN DESCRIPTION:
WHITE OAK CREEK WEST 45.0
END DESCRIPTION:
XS GIS Cut Line= 3
      3851115.54     10059667.65      3851111.45     10059094.66
      3851020.49     10058549.19
#Sta/Elev= 30
    4427  115.39  4445.8  113.49  4532.5  112.89  4544.1  112.84  4713.6  111.35
  4773.6  111.98  4883.6     110  4953.6  110.66 4970.61 109.433  4983.6  107.69
  4990.2  105.36    4997  105.36  4999.3  106.82  5004.4  106.82  5023.9   109.5
  5073.7  109.41  5135.4  109.18  5165.8  110.17  5177.5  110.07  5206.4  111.34
  5229.7  111.42  5238.3  111.07  5307.8  111.39  5348.3  112.08  5378.7  111.01
    5399  111.14  5415.6  110.58    5470  110.88  5520.7  111.77    5553  114.04
#Mann= 8 ,-1 , 0
    4427     .05       0  4445.8     .12       0  4532.5     .05       0
  4544.1     .12       0 4970.61     .07       0  5023.9     .12       0
  5073.7      .1       0  5229.7     .12       0
Bank Sta=4970.61,5023.9
XS Rating Curve= 0 ,0
Exp/Cntr=0.3,0.1

Type RM Length L Ch R = 1 ,23519   ,519,519,519
BEGIN DESCRIPTION:
WHITE OAK CREEK WEST 44.0
END DESCRIPTION:
XS GIS Cut Line= 3
      3851635.36      10059478.1      3851385.37     10058899.14
      3851036.11     10058528.35
#Sta/Elev= 30
  4355.4  112.68  4383.2  111.03  4441.1  110.45  4723.9  109.48    4763  109.08
  4798.7  109.96  4891.4  108.63  4938.4   108.9  4967.4  107.52    4986   107.8
    4990  108.47 4990.19 107.963  4990.9  106.07  4991.4  105.57  5002.8  105.57
  5004.1  107.93    5011  107.92  5025.2  109.39  5046.6  108.28    5096  109.26
  5136.4  109.19  5152.6  108.74  5202.4  111.39  5308.4  110.35  5336.7  111.41
  5379.2  110.65  5435.8  110.86  5485.2   112.4  5490.5  114.17  5495.4  114.17
#Mann= 5 ,-1 , 0
  4355.4     .05       0  4723.9      .1       0  4990.9     .07       0
  5004.1      .1       0  5136.4     .12       0
Bank Sta=4990.19,5004.1
XS Rating Curve= 0 ,0
Exp/Cntr=0.3,0.1

Type RM Length L Ch R = 1 ,23000   ,205,205,205
BEGIN DESCRIPTION:
WHITE OAK CREEK WEST 43.0
END DESCRIPTION:
XS GIS Cut Line= 3
      3851756.99     10059447.05      3851625.13     10058729.97
      3851480.18     10058354.69
#Sta/Elev= 30
  4270.9  113.27    4338  110.58  4346.1  111.84  4388.8  111.16  4419.3   111.6
  4439.7  112.85  4490.5   111.6    4521  109.96  4621.6  110.41  4790.9  109.06
  4849.1  110.31  4902.2  108.24  4933.6   108.3  4968.4  108.62  4988.7   106.5
  4991.1  104.78  5002.6  104.78  5005.3  106.57  5020.3  108.82  5041.7  109.83
  5119.7  110.29  5138.2  111.03  5204.2  110.08  5234.7  110.62  5277.5  110.17
    5299  110.96    5308  112.22  5313.3  111.19  5370.2  113.74  5402.3  113.81
#Mann= 5 ,-1 , 0
  4270.9     .05       0  4933.6     .12       0  4968.4     .07       0
  5020.3     .12       0  5370.2     .05       0
Bank Sta=4968.4,5020.3
XS Rating Curve= 0 ,0
Exp/Cntr=0.3,0.1

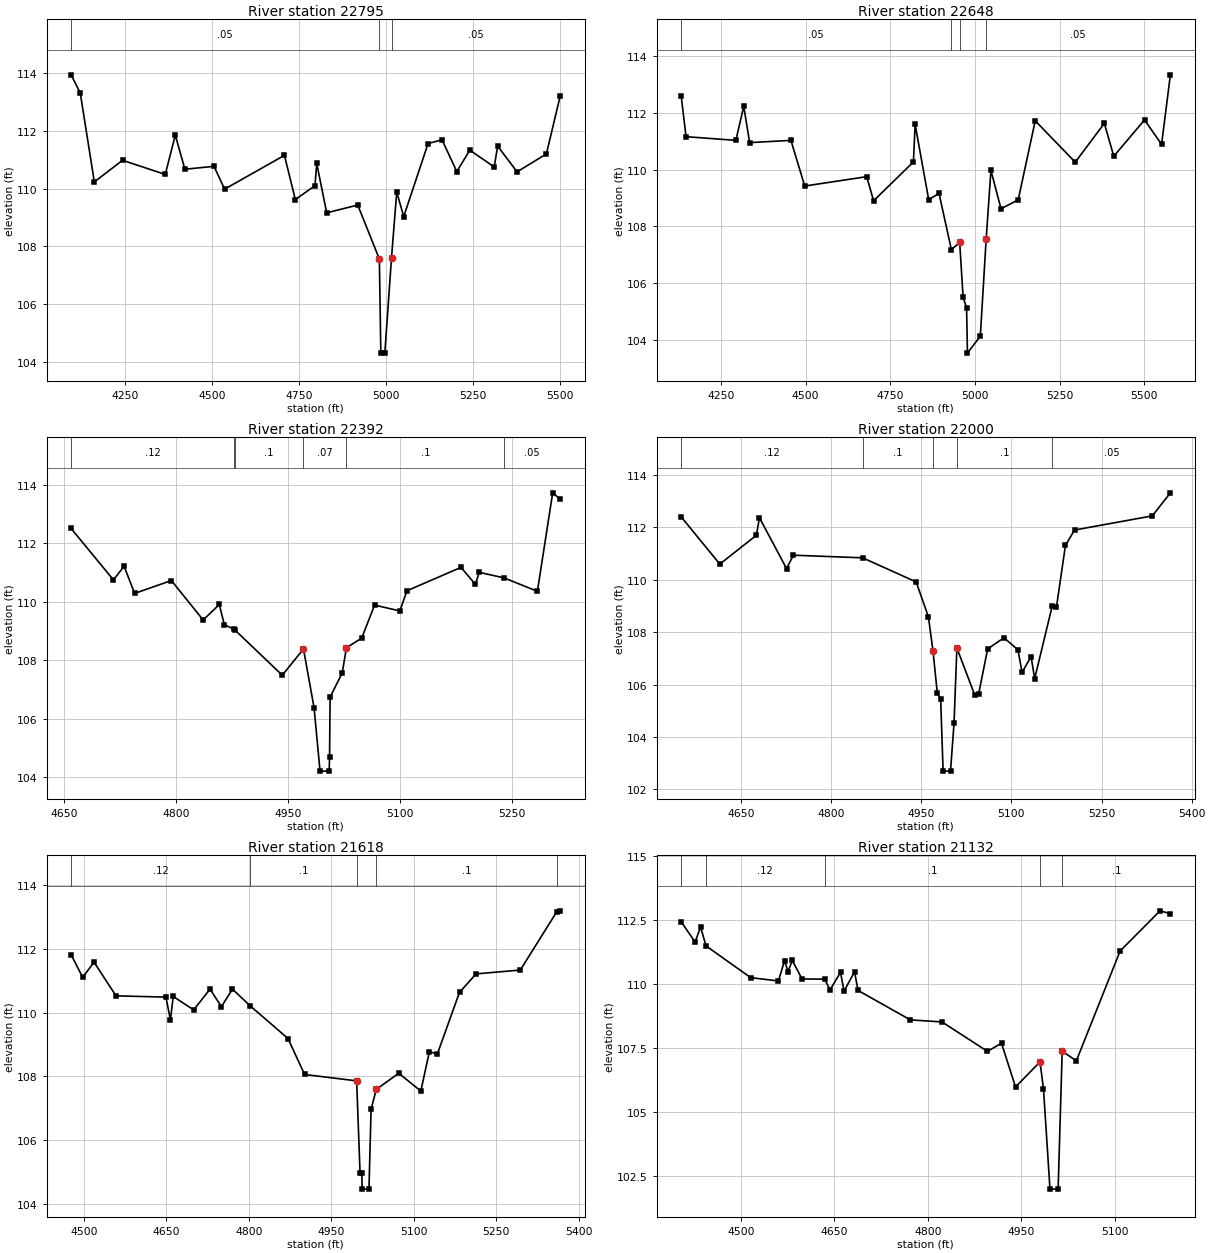
Type RM Length L Ch R = 1 ,22795   ,147,147,147
BEGIN DESCRIPTION:
Mapping XS 471f5f68
END DESCRIPTION:
XS GIS Cut Line= 3
      3851925.74     10059637.01      3851788.58     10058793.24
      3851819.83     10058241.17
#Sta/Elev= 30
  4093.8  113.94  4120.1  113.31  4160.6  110.23  4241.7  110.98  4364.7  110.49
  4393.6  111.85  4421.2  110.67  4505.1  110.77  4535.5  109.98  4707.7  111.15
  4739.1  109.62  4795.6   110.1  4800.7  110.87  4829.3  109.16  4918.7  109.43
  4980.9  107.56  4985.1   104.3  4996.6   104.3 5015.87 107.599  5030.9  109.88
    5051  109.03  5121.1  111.56  5161.2  111.69  5203.7  110.59  5241.3  111.33
  5311.4  110.75  5321.4  111.47  5377.3  110.58  5461.6   111.2  5501.6  113.22
#Mann= 3 , 0 , 0
  4093.8     .05       0  4980.9     .07       0 5015.87     .05       0
Bank Sta=4980.9,5015.87
XS Rating Curve= 0 ,0
Exp/Cntr=0.3,0.1

Type RM Length L Ch R = 1 ,22648   ,256,256,256
BEGIN DESCRIPTION:
Mapping XS 798abb9b
END DESCRIPTION:
XS GIS Cut Line= 3
      3852085.46      10059579.7      3851910.11     10058614.42
      3851967.29     10058155.25
#Sta/Elev= 30
  4133.2  112.58  4147.4  111.16  4294.4  111.03  4317.7  112.23  4335.1  110.95
    4457  111.03  4497.7  109.42  4680.6  109.75    4701   108.9  4818.5  110.27
  4823.6  111.59  4863.6  108.94  4894.1  109.16  4930.5  107.18  4955.1  107.43
  4965.2   105.5  4975.4  105.13    4978  103.53    5016  104.13  5033.3 107.561
  5047.3  109.97    5077  108.62  5127.7  108.93  5178.1  111.72  5296.1  110.26
    5382  111.63  5409.9  110.47  5500.6  111.75    5551  110.89    5577  113.34
#Mann= 4 ,-1 , 0
  4133.2     .05       0  4930.5      .1       0  4955.1     .03       0
  5033.3     .05       0
Bank Sta=4955.1,5033.3
XS Rating Curve= 0 ,0
Exp/Cntr=0.3,0.1

Type RM Length L Ch R = 1 ,22392   ,392,392,392
BEGIN DESCRIPTION:
WHITE OAK CREEK WEST 42.0
END DESCRIPTION:
XS GIS Cut Line= 3
      3852378.32     10058871.03      3852146.31     10058612.43
      3852078.82     10058311.12
#Sta/Elev= 30
  4659.1  112.51  4715.9  110.75  4730.1  111.22  4744.3  110.29  4793.6  110.73
  4836.2  109.38  4857.9  109.91  4864.6  109.22  4877.8  109.06  4878.3  109.05
  4942.4  107.49  4970.8  108.39    4985  106.38    4993  104.21  5005.3  104.21
  5005.8  104.71  5006.5  106.74  5022.8  107.57  5028.4  108.43  5048.9  108.76
  5066.2  109.89  5100.1  109.69  5109.6  110.38  5182.1  111.18  5201.4   110.6
  5206.6  111.01    5240  110.82  5284.6  110.36  5305.1  113.73  5315.3  113.51
#Mann= 6 ,-1 , 0
  4659.1     .12       0  4877.8     .05       0  4878.3      .1       0
  4970.8     .07       0  5028.4      .1       0    5240     .05       0
Bank Sta=4970.8,5028.4
XS Rating Curve= 0 ,0
Exp/Cntr=0.3,0.1

Type RM Length L Ch R = 1 ,22000   ,382,382,382
BEGIN DESCRIPTION:
WHITE OAK CREEK WEST 41.0
END DESCRIPTION:
XS GIS Cut Line= 3
      3852509.17     10058843.91        3852418.     10058403.65
      3852217.52     10058099.12
#Sta/Elev= 30
  4550.4   112.4  4614.6   110.6  4675.5   111.7  4680.6  112.37  4725.7  110.43
  4737.1  110.94  4852.3  110.84  4941.4  109.92  4961.8  108.59 4969.54 107.273
  4976.6  105.68  4982.2  105.45  4986.3   102.7  4998.6   102.7  5004.5  104.53
  5009.2   107.4    5039   105.6  5045.4  105.64  5060.4  107.36  5087.5  107.79
  5110.8  107.33  5117.7  106.47  5132.7  107.07  5138.7  106.23  5168.1  109.02
  5174.9  108.95  5189.9  111.31    5205   111.9  5334.5  112.44  5364.6  113.32
#Mann= 5 ,-1 , 0
  4550.4     .12       0  4852.3      .1       0 4969.54     .07       0
  5009.2      .1       0  5168.1     .05       0
Bank Sta=4969.54,5009.2
XS Rating Curve= 0 ,0
Exp/Cntr=0.3,0.1

Type RM Length L Ch R = 1 ,21618   ,486,486,486
BEGIN DESCRIPTION:
WHITE OAK CREEK WEST 40.0
END DESCRIPTION:
XS GIS Cut Line= 3
      3852547.83     10058911.98      3852618.53     10058397.26
      3852658.51     10058028.78
#Sta/Elev= 30
  4476.5  111.82  4497.6  111.11  4518.1  111.59  4558.2  110.53    4649  110.49
  4657.2  109.78  4662.3  110.51  4699.5  110.09  4729.3  110.74    4750  110.19
  4770.1  110.74  4802.1  110.22  4871.1  109.19  4901.4  108.06  4996.1  107.86
  5002.3  104.98  5005.6  104.96  5006.1  104.46  5018.5  104.46  5022.4  106.97
  5031.8  107.59  5072.7   108.1  5112.9  107.54  5128.4  108.77  5143.1  108.71
  5183.3  110.64  5213.5  111.22    5294  111.34  5359.9  113.16  5366.7   113.2
#Mann= 5 ,-1 , 0
  4476.5     .12       0  4802.1      .1       0  4996.1     .07       0
  5031.8      .1       0  5359.9     .05       0
Bank Sta=4996.1,5031.8
XS Rating Curve= 0 ,0
Exp/Cntr=0.3,0.1

Type RM Length L Ch R = 1 ,21132   ,580,580,580
BEGIN DESCRIPTION:
WHITE OAK CREEK WEST 39.0
END DESCRIPTION:
XS GIS Cut Line= 3
      3852717.84      10058861.1      3852989.45     10058308.72
      3853120.75     10058201.29
#Sta/Elev= 30
  4404.3  112.41  4426.6  111.62  4435.3  112.21  4444.1  111.47  4515.8  110.23
  4560.3   110.1  4570.1  110.89  4575.7  110.47  4582.6   110.9  4598.2  110.18
  4634.6  110.17  4643.1  109.75    4660  110.44  4665.6   109.7  4682.5  110.46
  4688.1  109.73  4772.1  108.58  4822.9   108.5  4895.9  107.35  4918.4  107.67
  4940.9  105.96  4980.2  106.94  4985.8  105.89  4996.2  101.97  5009.3  101.97
  5015.8  107.36  5038.5  106.98  5108.8  111.27  5172.8  112.84  5189.5  112.73
#Mann= 5 ,-1 , 0
  4404.3      .1       0  4444.1     .12       0  4634.6      .1       0
  4980.2     .07       0  5015.8      .1       0
Bank Sta=4980.2,5015.8
XS Rating Curve= 0 ,0
Exp/Cntr=0.3,0.1

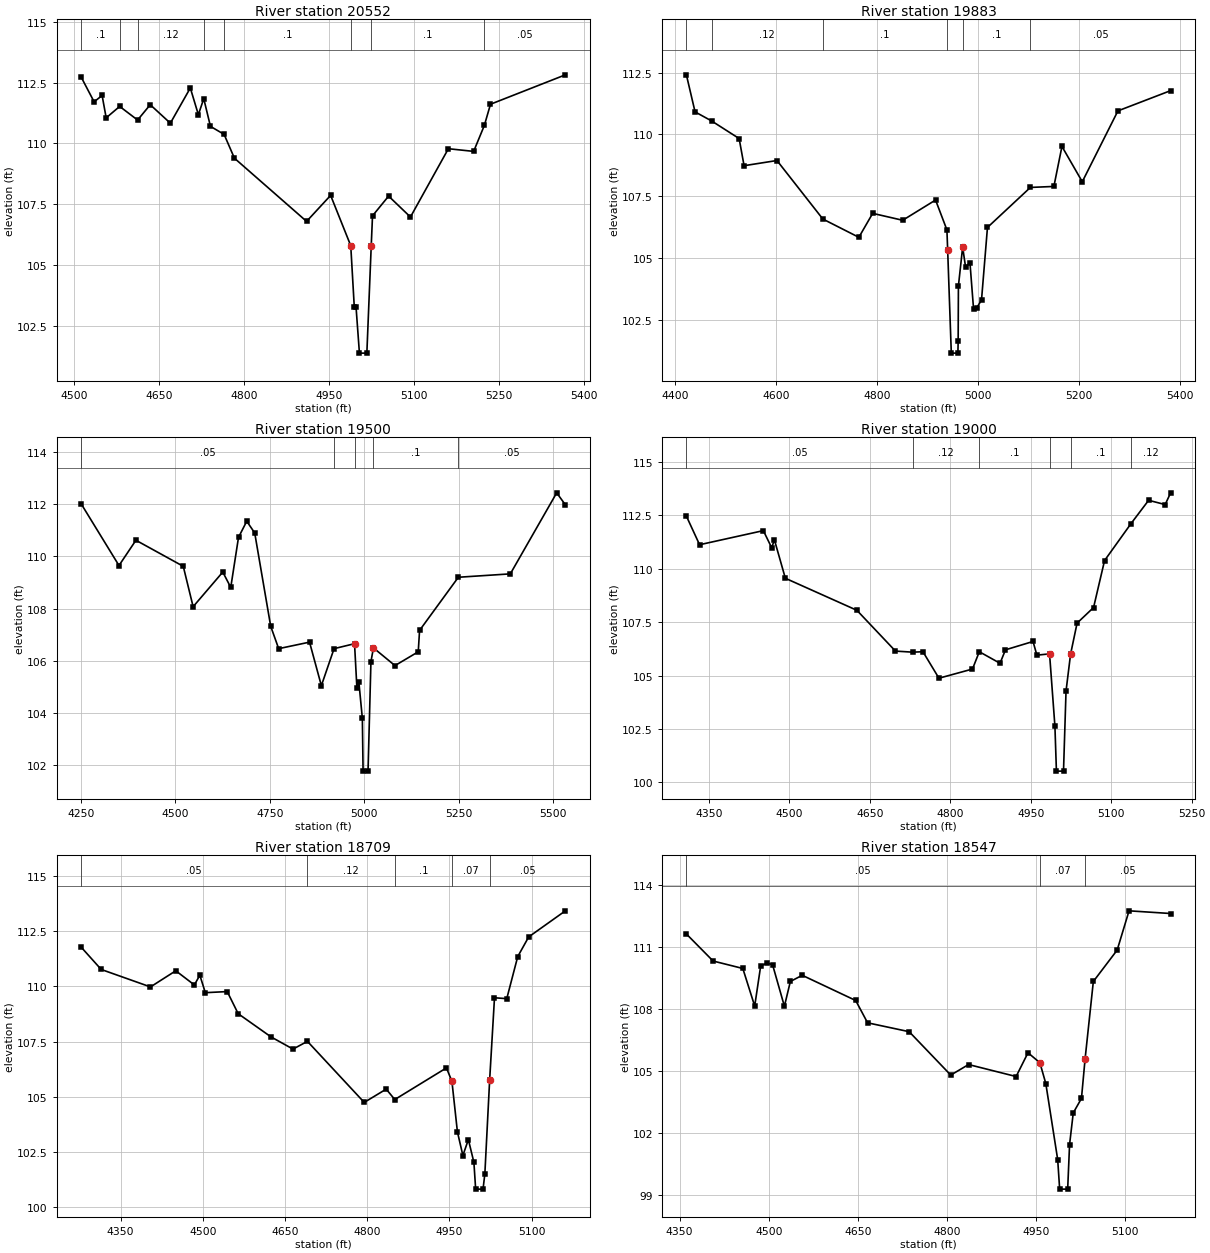
Type RM Length L Ch R = 1 ,20552   ,669,669,669
BEGIN DESCRIPTION:
WHITE OAK CREEK WEST 38.0
END DESCRIPTION:
XS GIS Cut Line= 3
      3852868.75      10058904.4      3853207.26      10058557.2
      3853370.33     10058225.86
#Sta/Elev= 30
    4513  112.73  4535.9  111.71    4550  111.97  4557.2  111.05    4581  111.52
  4612.6  110.96  4634.9  111.59  4670.4  110.83  4705.6  112.28  4719.8  111.18
  4729.3  111.84  4741.1   110.7  4765.2  110.37  4783.4  109.39  4910.7  106.79
  4953.1  107.86  4988.6  105.79  4994.8  103.28  4997.9  103.28  5003.9  101.37
    5017  101.37 5024.73 105.789    5027  107.02  5055.4  107.83  5093.9  106.97
  5160.8  109.78  5205.4  109.67  5224.3  110.74  5235.1  111.61  5367.2  112.82
#Mann= 8 ,-1 , 0
    4513      .1       0    4581     .05       0  4612.6     .12       0
  4729.3     .05       0  4765.2      .1       0  4988.6     .07       0
 5024.73      .1       0  5224.3     .05       0
Bank Sta=4988.6,5024.73
XS Rating Curve= 0 ,0
Exp/Cntr=0.3,0.1

Type RM Length L Ch R = 1 ,19883   ,383,383,383
BEGIN DESCRIPTION:
WHITE OAK CREEK WEST 37.0
END DESCRIPTION:
XS GIS Cut Line= 3
      3853365.27     10058992.49      3853682.96     10058421.35
      3853641.29     10058117.54
#Sta/Elev= 30
  4421.9  112.41  4439.1  110.91  4472.1  110.54  4526.5  109.83  4536.3  108.73
  4601.5  108.94  4692.5  106.57  4763.9  105.83  4791.3   106.8  4850.8  106.52
    4916  107.34  4938.5  106.13 4939.96 105.331  4947.2  101.14  4960.3  101.14
  4960.8  101.64  4961.3  103.86  4969.7  105.43  4975.4  104.64  4984.2   104.8
  4991.4  102.91  4997.2  102.96  5007.1  103.29  5018.9  106.23    5104  107.85
  5150.6  107.89  5166.6  109.51  5206.9  108.08  5277.6  110.95  5382.1  111.77
#Mann= 6 ,-1 , 0
  4421.9     .05       0  4472.1     .12       0  4692.5      .1       0
  4938.5     .07       0  4969.7      .1       0    5104     .05       0
Bank Sta=4939.96,4969.7
XS Rating Curve= 0 ,0
Exp/Cntr=0.3,0.1

Type RM Length L Ch R = 1 ,19500   ,500,500,500
BEGIN DESCRIPTION:
WHITE OAK CREEK WEST 36.0
END DESCRIPTION:
XS GIS Cut Line= 4
      3854098.76     10059305.91      3853856.95     10058596.91
      3853764.55     10058490.79      3853667.86     10058111.12
#Sta/Elev= 30
  4250.9  112.02  4351.1  109.65  4395.9  110.62  4521.2  109.62  4547.3  108.07
  4625.8   109.4  4646.9  108.81  4667.4  110.73  4689.2  111.35  4710.3   110.9
  4752.6  107.32  4773.7  106.46  4855.4  106.71  4886.7  105.04  4920.3  106.46
  4974.5  106.65  4980.7  104.96    4986  105.17  4995.2  103.78  4997.1  101.76
  5010.2  101.76  5017.9  105.96  5024.5  106.49  5081.5  105.81  5143.1  106.34
  5146.6  107.16  5249.2   109.2  5386.8  109.33  5509.5  112.44  5532.5  111.98
#Mann= 5 ,-1 , 0
  4250.9     .05       0  4920.3      .1       0  4974.5     .07       0
  5024.5      .1       0  5249.2     .05       0
Bank Sta=4974.5,5024.5
XS Rating Curve= 0 ,0
Exp/Cntr=0.3,0.1

Type RM Length L Ch R = 1 ,19000   ,291,291,291
BEGIN DESCRIPTION:
WHITE OAK CREEK WEST 35.0
END DESCRIPTION:
XS GIS Cut Line= 3
      3854218.12      10059190.9      3854064.76     10058516.52
      3854017.86     10058311.11
#Sta/Elev= 30
  4308.4  112.47    4333  111.13  4451.8  111.79  4467.3  110.99  4472.4  111.36
  4492.8  109.56  4626.1  108.06    4698  106.15  4729.9   106.1  4749.2  106.12
    4779  104.88  4841.5  105.31  4854.2  106.12  4892.8  105.58    4903  106.21
  4954.3   106.6  4961.5  105.96  4985.1  106.02  4995.1  102.63  4997.9  100.53
  5011.1  100.53  5015.8  104.28 5024.26 106.005  5036.4  107.46  5067.1  108.19
  5087.6  110.39  5136.9  112.12  5169.7  113.21  5200.5  113.01  5210.7  113.56
#Mann= 6 ,-1 , 0
  4308.4     .05       0  4729.9     .12       0  4854.2      .1       0
  4985.1     .07       0 5024.26      .1       0  5136.9     .12       0
Bank Sta=4985.1,5024.26
XS Rating Curve= 0 ,0
Exp/Cntr=0.3,0.1

Type RM Length L Ch R = 1 ,18709   ,162,162,162
BEGIN DESCRIPTION:
Mapping XS f73c2124
END DESCRIPTION:
XS GIS Cut Line= 2
      3854236.89      10059197.6       3854267.2     10058314.12
#Sta/Elev= 30
  4277.8  111.77  4314.4  110.76  4404.4  109.97  4450.6   110.7  4484.5  110.06
  4494.5   110.5  4504.5  109.71  4544.5  109.76  4564.5  108.76  4624.5  107.71
  4664.6  107.16  4690.9  107.51  4794.6  104.75  4834.7  105.35  4850.4  104.88
  4944.7  106.31  4954.7   105.7  4964.7  103.42  4974.7  102.35  4984.7  103.07
  4994.8  102.04    4998  100.83  5011.5  100.83  5014.8  101.52 5023.52 105.749
  5032.4  109.48  5054.8  109.44  5074.8  111.34  5094.8  112.23  5161.8  113.41
#Mann= 5 ,-1 , 0
  4277.8     .05       0  4690.9     .12       0  4850.4      .1       0
  4954.7     .07       0 5023.52     .05       0
Bank Sta=4954.7,5023.52
XS Rating Curve= 0 ,0
Exp/Cntr=0.3,0.1

Type RM Length L Ch R = 1 ,18547   ,547,547,547
BEGIN DESCRIPTION:
WHITE OAK CREEK WEST 34.0
END DESCRIPTION:
XS GIS Cut Line= 3
      3854428.07     10059126.03      3854426.77     10058601.25
      3854417.85     10058311.07
#Sta/Elev= 30
  4361.3  111.62  4406.3  110.31  4456.3  109.95  4476.3  108.13  4486.3  110.06
  4496.3  110.21  4506.3  110.14  4526.3  108.12  4536.3  109.32  4556.3  109.62
  4646.3   108.4  4666.3  107.32  4736.3  106.89  4806.3  104.79  4836.3   105.3
  4916.3  104.72  4936.3  105.87  4956.3  105.39  4966.3  104.38  4986.3   100.7
  4989.6   99.27  5003.1   99.27  5006.3  101.43  5012.5  102.96  5026.3  103.66
 5032.38 105.563  5046.3  109.32  5086.4  110.84  5106.4  112.74  5176.4  112.61
#Mann= 3 , 0 , 0
  4361.3     .05       0  4956.3     .07       0 5032.38     .05       0
Bank Sta=4956.3,5032.38
XS Rating Curve= 0 ,0
Exp/Cntr=0.3,0.1