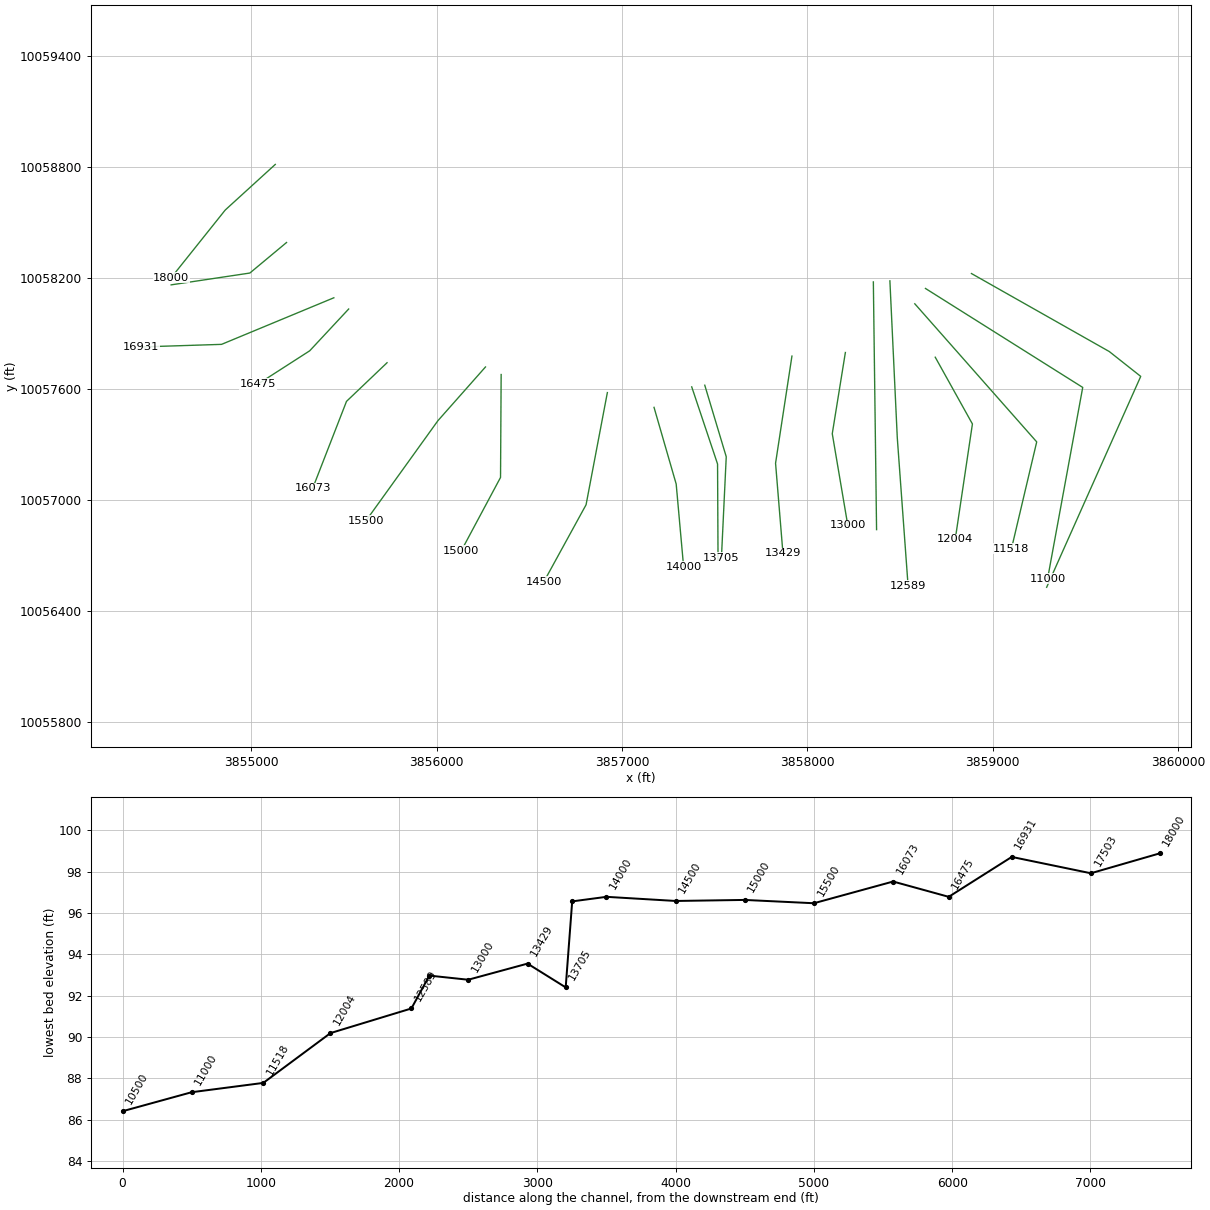
HEC-RAS study WHITE OAK CREEK WEST.prj: WHITE OAK CREEK WEST Base Level Engineering

--- WHITE OAK CREEK WEST.g10 (geometry) --- (continued)

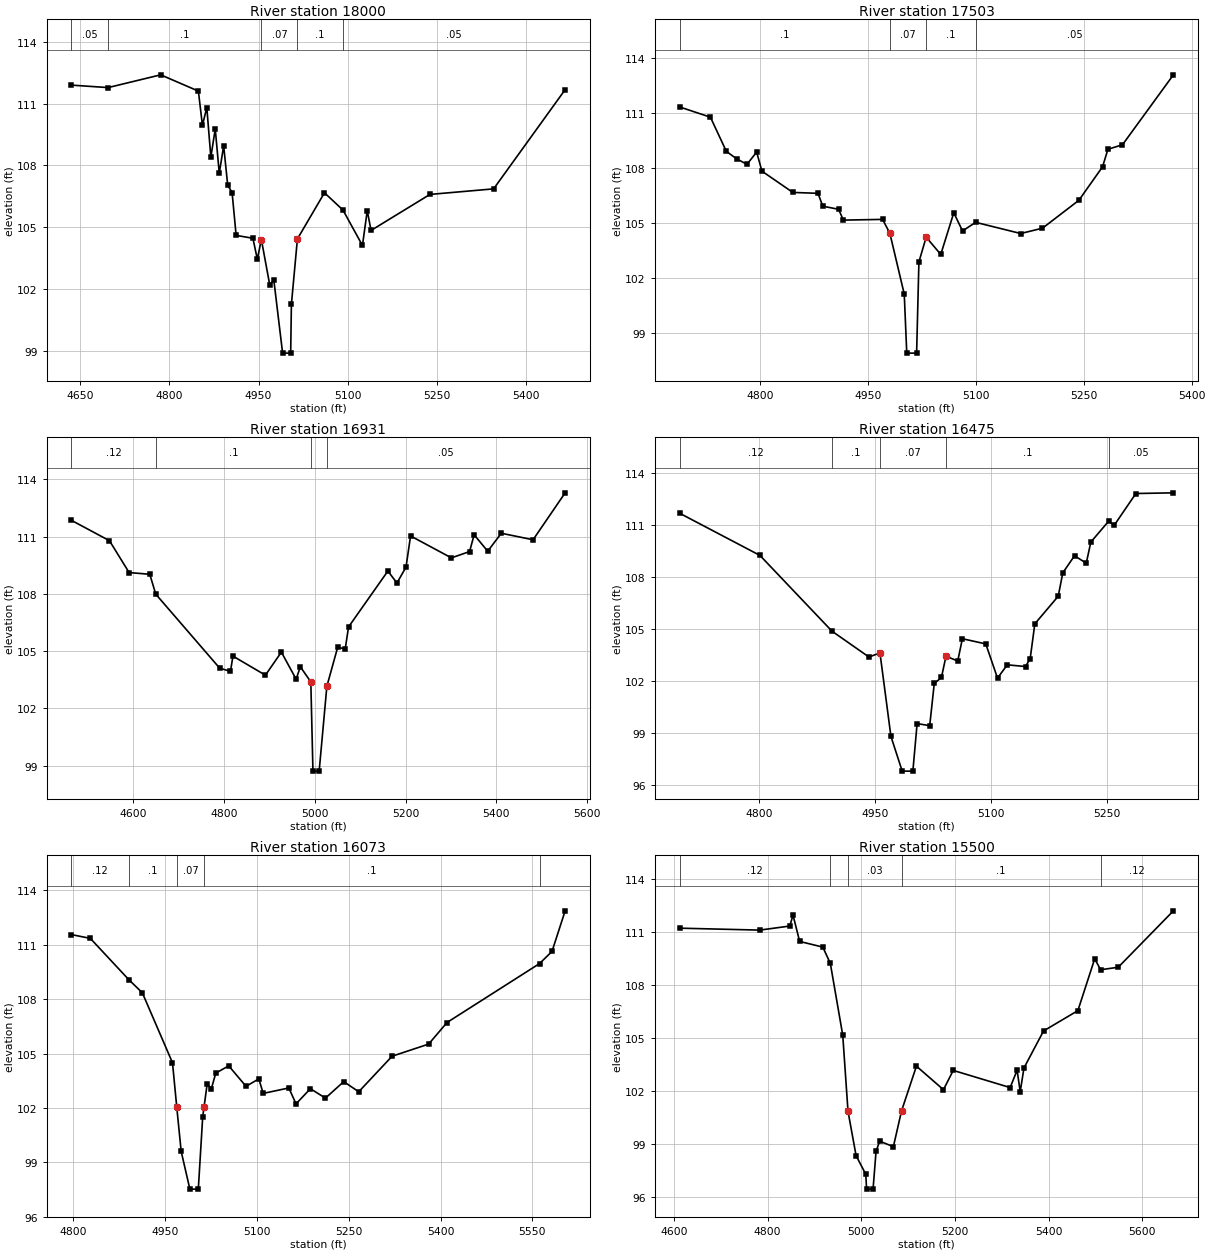
Type RM Length L Ch R = 1 ,18000   ,497,497,497
BEGIN DESCRIPTION:
WHITE OAK CREEK WEST 33.0
END DESCRIPTION:
XS GIS Cut Line= 3
      3855129.44     10058811.73      3854859.61     10058565.49
      3854568.72     10058200.67
#Sta/Elev= 30
  4634.7   111.9  4696.6  111.78  4785.2   112.4  4848.7  111.61  4855.5  109.95
  4862.9  110.81  4869.7   108.4  4877.1  109.77  4883.9  107.62  4891.3  108.95
  4898.1  107.04  4905.5  106.68  4912.3   104.6  4940.6  104.46    4948  103.44
  4954.8   104.4    4969  102.18  4975.8  102.43  4990.6   98.88  5004.2   98.88
  5005.4  101.25 5015.54 104.429  5061.1  106.67  5092.3  105.83  5125.1  104.11
  5133.2   105.8  5139.6  104.84  5238.8  106.59  5346.1  106.86  5466.6  111.68
#Mann= 5 ,-1 , 0
  4634.7     .05       0  4696.6      .1       0  4954.8     .07       0
 5015.54      .1       0  5092.3     .05       0
Bank Sta=4954.8,5015.54
XS Rating Curve= 0 ,0
Exp/Cntr=0.3,0.1

Type RM Length L Ch R = 1 ,17503   ,572,572,572
BEGIN DESCRIPTION:
WHITE OAK CREEK WEST 32.0
END DESCRIPTION:
XS GIS Cut Line= 3
      3855190.22     10058389.87      3854992.31     10058224.95
      3854567.81     10058161.06
#Sta/Elev= 30
  4687.7  111.34  4730.6  110.78  4752.7  108.92  4767.1  108.51  4781.4  108.21
  4794.9  108.88  4802.2  107.84  4845.2  106.68  4880.3  106.63  4886.8  105.93
  4908.9  105.76  4915.5  105.17  4970.1  105.21  4980.2  104.45  5000.2  101.14
  5003.7   97.92  5017.4   97.92  5020.6  102.89  5030.7  104.24    5051   103.3
  5069.1  105.57  5081.3  104.58  5099.5  105.05  5162.2  104.44  5192.5  104.73
  5243.1  106.25  5276.1  108.08  5283.5  109.03  5303.8  109.28  5374.6  113.09
#Mann= 4 ,-1 , 0
  4687.7      .1       0  4980.2     .07       0  5030.7      .1       0
  5099.5     .05       0
Bank Sta=4980.2,5030.7
XS Rating Curve= 0 ,0
Exp/Cntr=0.3,0.1

Type RM Length L Ch R = 1 ,16931   ,456,456,456
BEGIN DESCRIPTION:
WHITE OAK CREEK WEST 31.0
END DESCRIPTION:
XS GIS Cut Line= 3
      3855445.39     10058091.25      3854839.53     10057839.53
      3854407.22     10057825.65
#Sta/Elev= 30
  4463.3  111.86  4547.3  110.79  4590.6  109.12  4636.2  109.03  4649.3  107.99
  4790.2  104.11  4814.1  103.94  4819.5  104.74  4891.1  103.74  4926.3  104.95
  4958.8  103.53  4968.1  104.18  4991.2  103.39  4995.9   98.71  5009.6   98.71
  5026.6  103.16  5050.5  105.21    5067  105.11  5074.4  106.27  5161.1   109.2
  5181.1  108.57  5201.1  109.41  5211.1  111.04  5301.1  109.89  5341.2  110.22
  5351.2   111.1  5381.2  110.24  5411.2  111.18  5481.2  110.84  5551.9   113.3
#Mann= 4 ,-1 , 0
  4463.3     .12       0  4649.3      .1       0  4991.2     .07       0
  5026.6     .05       0
Bank Sta=4991.2,5026.6
XS Rating Curve= 0 ,0
Exp/Cntr=0.3,0.1

Type RM Length L Ch R = 1 ,16475   ,402,402,402
BEGIN DESCRIPTION:
WHITE OAK CREEK WEST 30.0
END DESCRIPTION:
XS GIS Cut Line= 3
      3855525.32     10058030.53      3855315.23     10057804.81
        3855037.     10057625.62
#Sta/Elev= 30
  4696.7   111.7  4800.7  109.26  4893.9  104.88  4941.9  103.38  4956.1  103.62
  4970.3   98.79  4984.9   96.78  4998.7   96.78  5004.2   99.53  5020.5   99.41
  5026.4  101.85  5035.7   102.2  5041.6  103.43  5056.8  103.15  5062.8  104.44
  5093.1  104.14  5108.3  102.16  5120.9  102.93  5144.6  102.83  5150.6  103.29
  5156.6   105.3  5186.9   106.9  5192.8  108.25    5208  109.24  5223.2  108.81
  5229.1  110.03    5252  111.23  5259.5  111.01  5287.4  112.84    5336  112.88
#Mann= 5 ,-1 , 0
  4696.7     .12       0  4893.9      .1       0  4956.1     .07       0
  5041.6      .1       0    5252     .05       0
Bank Sta=4956.1,5041.6
XS Rating Curve= 0 ,0
Exp/Cntr=0.3,0.1

Type RM Length L Ch R = 1 ,16073   ,573,573,573
BEGIN DESCRIPTION:
WHITE OAK CREEK WEST 29.0
END DESCRIPTION:
XS GIS Cut Line= 3
      3855732.38     10057740.29      3855513.66     10057531.55
      3855330.93     10057061.03
#Sta/Elev= 30
  4796.6  111.56  4827.6  111.35  4890.6  109.07  4912.6  108.35  4961.9  104.49
  4968.8  102.07  4976.1    99.6  4990.3   97.52  5004.1   97.52  5011.3  101.51
 5013.43  102.04  5018.5   103.3  5025.5  103.07  5032.7  103.92  5053.8  104.32
  5082.1  103.19    5103   103.6  5110.2   102.8  5152.1   103.1  5163.8  102.22
  5187.3  103.06  5211.9  102.54  5241.8  103.45  5266.3  102.89  5320.8  104.85
  5380.6  105.52  5410.6  106.71  5561.8  109.96  5582.2  110.63  5603.7  112.87
#Mann= 5 ,-1 , 0
  4796.6     .12       0  4890.6      .1       0  4968.8     .07       0
 5013.43      .1       0  5561.8     .05       0
Bank Sta=4968.8,5013.43
XS Rating Curve= 0 ,0
Exp/Cntr=0.3,0.1

Type RM Length L Ch R = 1 ,15500   ,500,500,500
BEGIN DESCRIPTION:
WHITE OAK CREEK WEST 28.0
END DESCRIPTION:
XS GIS Cut Line= 3
      3856263.26     10057717.39      3856006.54     10057426.86
      3855617.93     10056885.38
#Sta/Elev= 30
  4612.3  111.22  4783.3  111.11  4847.6  111.34  4854.4  111.96  4868.6  110.47
    4918  110.15  4934.1  109.23  4960.6  105.17 4971.82  100.87  4989.1   98.36
  5009.8   97.31  5011.5   96.47  5025.3   96.47  5031.7    98.6  5039.3   99.18
  5068.7   98.87 5086.14 100.893  5117.9  103.42  5175.6  102.09  5196.5  103.18
    5318  102.21  5332.8  103.19  5339.5  101.98  5347.5  103.32  5389.3  105.41
  5462.6  106.56  5498.5  109.49  5511.1  108.87  5548.7  109.01  5666.5   112.2
#Mann= 5 ,-1 , 0
  4612.3     .12       0  4934.1     .05       0 4971.82     .03       0
 5086.14      .1       0  5511.1     .12       0
Bank Sta=4971.82,5086.14
XS Rating Curve= 0 ,0
Exp/Cntr=0.3,0.1

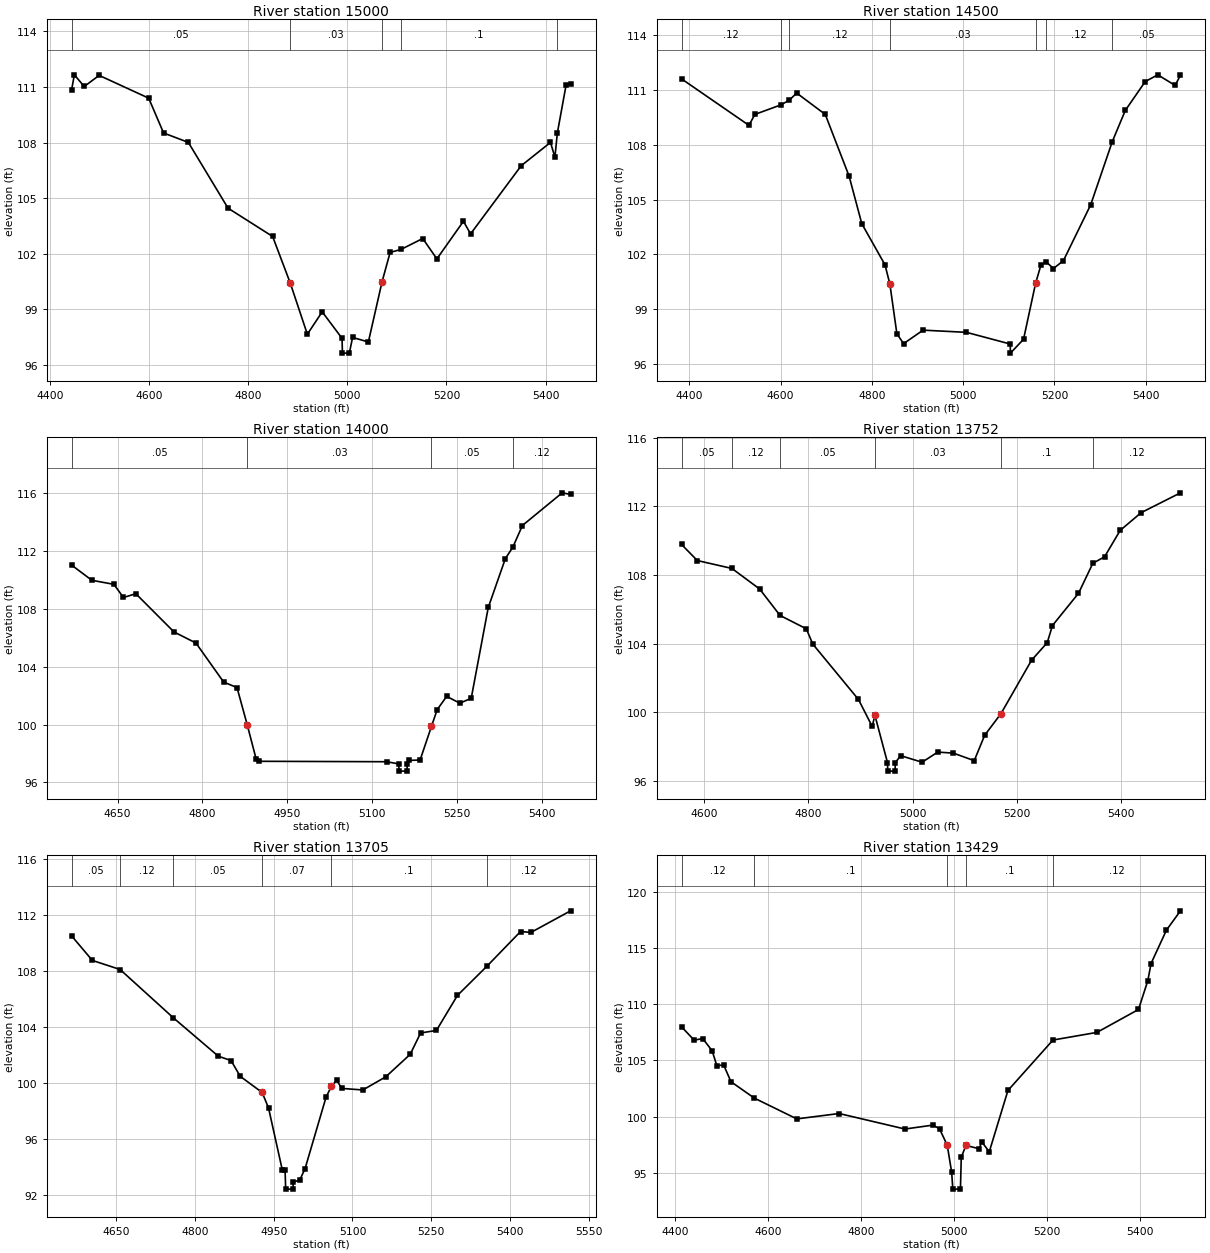
Type RM Length L Ch R = 1 ,15000   ,500,500,500
BEGIN DESCRIPTION:
WHITE OAK CREEK WEST 27.0
END DESCRIPTION:
XS GIS Cut Line= 3
      3856347.87     10057676.56      3856344.52     10057120.57
      3856132.29      10056723.2
#Sta/Elev= 30
    4444  110.85  4449.5  111.66  4469.5  111.03  4499.5  111.63  4599.5   110.4
  4629.5  108.52  4679.5  108.01  4759.5  104.46  4849.5  102.93  4885.2 100.403
  4919.5   97.65  4949.5   98.86  4989.5   97.43  4990.3   96.63  5004.2   96.63
  5010.8   97.48  5042.6   97.23  5070.2  100.48  5086.5  102.07  5108.4  102.23
  5152.3  102.82  5180.8  101.72  5234.4  103.75  5248.8  103.07  5350.9  106.75
    5410  108.01  5418.9  107.21  5423.8  108.51  5441.6  111.13  5450.5  111.18
#Mann= 5 ,-1 , 0
    4444     .05       0  4885.2     .03       0  5070.2     .05       0
  5108.4      .1       0  5423.8     .05       0
Bank Sta=4885.2,5070.2
XS Rating Curve= 0 ,0
Exp/Cntr=0.3,0.1

Type RM Length L Ch R = 1 ,14500   ,500,500,500
BEGIN DESCRIPTION:
WHITE OAK CREEK WEST 26.0
END DESCRIPTION:
XS GIS Cut Line= 3
      3856920.77     10057578.97      3856805.91     10056972.85
      3856577.41      10056555.4
#Sta/Elev= 30
  4383.1  111.62  4530.8  109.07  4543.8  109.67  4600.6  110.19  4619.1  110.45
  4635.4  110.84  4697.9  109.67  4750.2  106.28  4777.9  103.68  4828.8  101.42
  4839.5  100.36  4854.8   97.64  4869.5    97.1  4912.2   97.84  5007.1   97.72
    5103   97.08  5103.5   96.58  5132.2   97.34 5158.64 100.413  5170.2   101.4
    5182  101.58  5197.7  101.22  5219.5  101.65  5279.2  104.71  5326.6  108.18
  5355.1  109.89  5398.7  111.47  5426.2  111.84  5464.2  111.26  5475.9  111.82
#Mann= 7 ,-1 , 0
  4383.1     .12       0  4600.6     .05       0  4619.1     .12       0
  4839.5     .03       0 5158.64     .05       0    5182     .12       0
  5326.6     .05       0
Bank Sta=4839.5,5158.64
XS Rating Curve= 0 ,0
Exp/Cntr=0.3,0.1

Type RM Length L Ch R = 1 ,14000   ,248,248,248
BEGIN DESCRIPTION:
WHITE OAK CREEK WEST 25.0
END DESCRIPTION:
XS GIS Cut Line= 3
      3857172.53     10057499.11      3857292.02      10057084.8
      3857332.24      10056636.3
#Sta/Elev= 30
  4568.8  111.03  4604.6  109.98  4643.5   109.7  4660.4  108.79  4682.3  109.05
  4749.6  106.41  4788.5  105.64  4837.4  102.94    4861  102.56    4879   99.99
  4894.7   97.63  4899.9   97.46  5125.3   97.43  5146.8   97.28  5147.3   96.78
  5161.3   96.78  5161.8   97.28  5164.4   97.52  5184.5   97.55  5204.5   99.87
  5214.6  101.03  5231.4  101.95  5254.7  101.48  5274.8  101.82  5304.9   108.1
  5335.1  111.48  5348.3  112.27  5365.2  113.77  5435.5  116.03  5450.3  115.92
#Mann= 4 ,-1 , 0
  4568.8     .05       0    4879     .03       0  5204.5     .05       0
  5348.3     .12       0
Bank Sta=4879,5204.5
XS Rating Curve= 0 ,0
Exp/Cntr=0.3,0.1

Type RM Length L Ch R = 1 ,13752   ,47,47,47
BEGIN DESCRIPTION:
Mapping XS 20092637
END DESCRIPTION:
XS GIS Cut Line= 3
      3857375.84     10057609.87      3857515.18     10057193.16
      3857517.79     10056675.46
#Sta/Elev= 30
  4556.8  109.78  4587.2  108.84  4653.5  108.38  4706.7  107.18  4745.8  105.64
  4796.2  104.86  4808.6  103.97  4896.2  100.74  4922.5   99.17  4927.8   99.81
  4951.9   97.06  4952.4   96.56  4966.4   96.56  4966.9   97.06  4977.3   97.46
  5018.3   97.08  5048.3   97.67  5078.3   97.61  5118.3   97.17  5138.3   98.65
 5169.55  99.911  5228.3  103.03  5258.3  104.05  5268.3  105.05  5318.3  106.93
  5345.8  108.68  5368.3  109.06  5398.3   110.6  5438.3  111.63  5513.9  112.79
#Mann= 6 ,-1 , 0
  4556.8     .05       0  4653.5     .12       0  4745.8     .05       0
  4927.8     .03       0 5169.55      .1       0  5345.8     .12       0
Bank Sta=4927.8,5169.55
XS Rating Curve= 0 ,0
Exp/Cntr=0.3,0.1

Type RM Length L Ch R = 1 ,13705   ,276,276,276
BEGIN DESCRIPTION:
Mapping XS 2ab35044
END DESCRIPTION:
XS GIS Cut Line= 3
      3857446.18     10057618.93      3857562.06     10057232.22
      3857536.04     10056685.73
#Sta/Elev= 30
  4564.8  110.48  4604.3  108.73  4657.2  108.08  4758.7  104.63  4844.4  101.89
  4868.6  101.58  4886.2  100.45  4927.9    99.3    4940    98.2  4966.5   93.73
  4971.6   93.73  4972.7    92.4  4986.7    92.4  4987.2    92.9  4999.7   93.06
  5009.7   93.87  5049.7   98.97  5059.7   99.73  5069.8  100.17  5079.8   99.59
  5119.8   99.48  5163.5  100.42  5209.9  102.02  5229.9  103.55    5260  103.73
    5300  106.23  5356.6  108.33  5420.2  110.79  5440.2  110.73  5515.6  112.27
#Mann= 6 ,-1 , 0
  4564.8     .05       0  4657.2     .12       0  4758.7     .05       0
  4927.9     .07       0  5059.7      .1       0  5356.6     .12       0
Bank Sta=4927.9,5059.7
XS Rating Curve= 0 ,0
Exp/Cntr=0.3,0.1

Type RM Length L Ch R = 1 ,13429   ,429,429,429
BEGIN DESCRIPTION:
WHITE OAK CREEK WEST 24.0
END DESCRIPTION:
XS GIS Cut Line= 3
      3857916.44     10057776.25      3857828.06     10057197.36
      3857867.85     10056711.09
#Sta/Elev= 30
  4413.9     108  4441.1  106.81  4459.6  106.95  4479.8  105.86    4490  104.53
  4504.5  104.61  4520.3  103.11  4570.6  101.65  4661.9    99.8    4753  100.28
  4894.6    98.9  4955.3   99.25  4969.1   98.91  4985.6   97.46  4995.1   95.06
  4997.6   93.55    5014   93.55  5015.8   96.39  5025.9   97.44  5054.6   97.14
  5059.6   97.78    5076   96.87  5116.2  102.33  5213.1  106.82  5307.7   107.5
  5397.1  109.54  5417.2  112.11  5424.1  113.63  5457.3  116.61  5487.4  118.32
#Mann= 5 ,-1 , 0
  4413.9     .12       0  4570.6      .1       0  4985.6     .07       0
  5025.9      .1       0  5213.1     .12       0
Bank Sta=4985.6,5025.9
XS Rating Curve= 0 ,0
Exp/Cntr=0.3,0.1

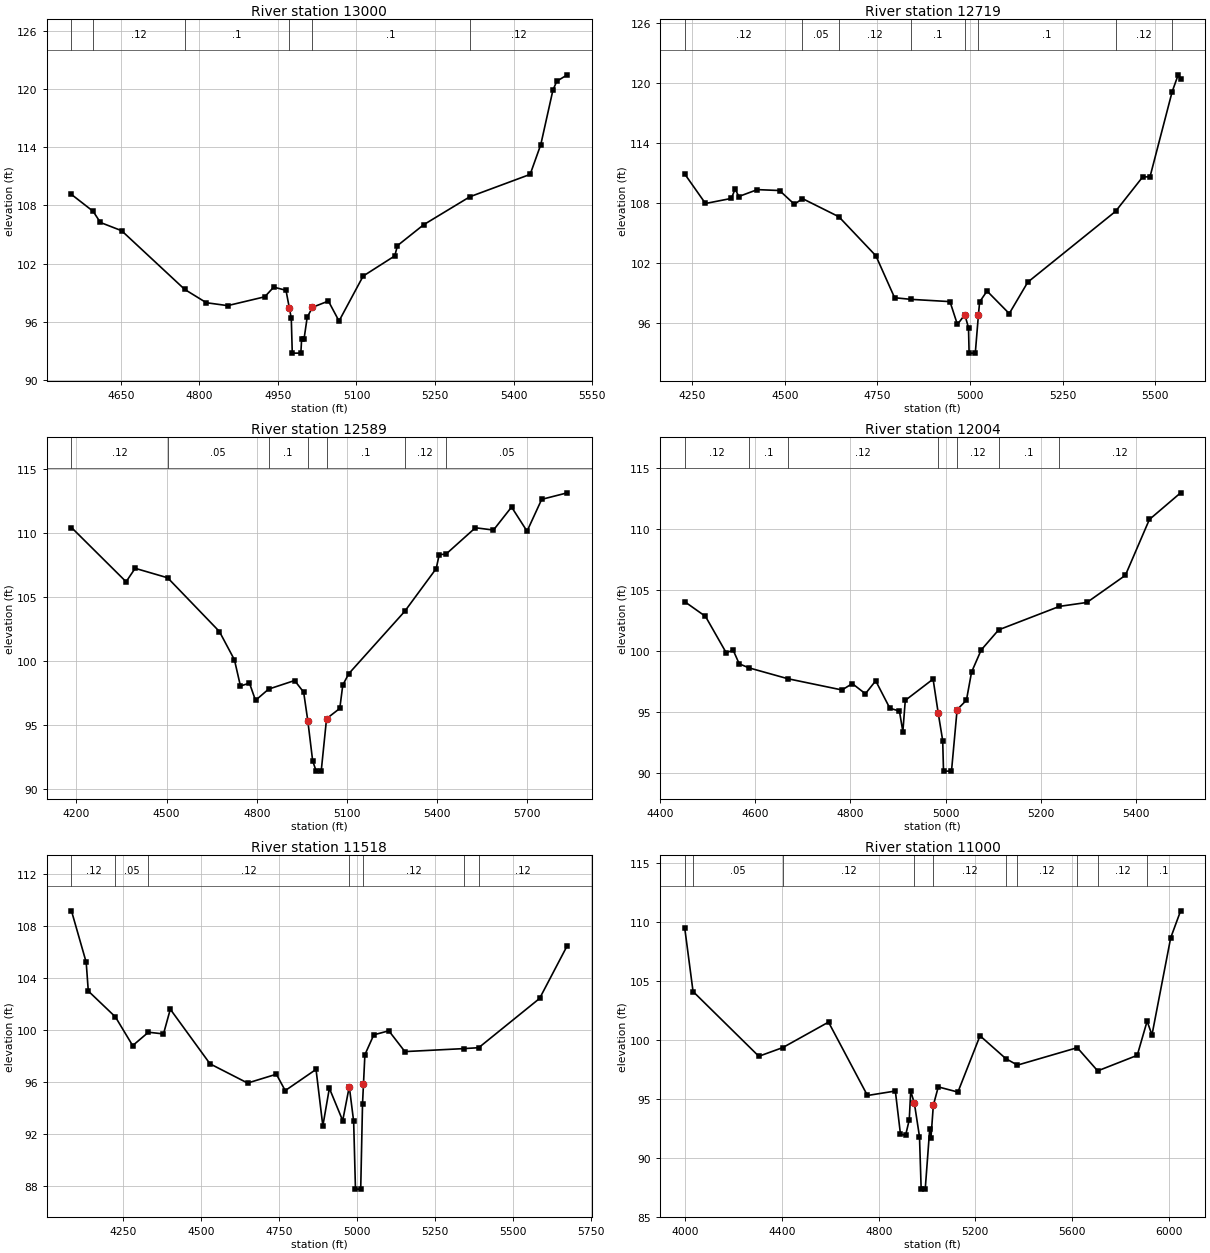
Type RM Length L Ch R = 1 ,13000   ,281,281,281
BEGIN DESCRIPTION:
WHITE OAK CREEK WEST 23.0
END DESCRIPTION:
XS GIS Cut Line= 3
      3858204.64      10057795.6      3858133.95     10057356.86
      3858217.84     10056861.11
#Sta/Elev= 30
  4555.6  109.14    4597   107.4  4610.8  106.25  4651.4   105.4    4772   99.34
  4813.3   97.97  4853.9   97.67  4924.8   98.58    4942   99.58  4965.4   99.25
  4971.7  97.454  4975.5   96.37  4977.4   92.77  4993.8   92.77  4995.3   94.27
    5000   94.27  5005.9   96.47    5016    97.5  5046.4   98.14  5066.7   96.08
  5112.8  100.72  5173.2   102.8  5178.3  103.86  5228.5  106.02  5316.6   108.9
  5431.8  111.21  5452.1  114.28  5475.2  119.88  5482.6  120.82  5502.8  121.48
#Mann= 6 ,-1 , 0
  4555.6     .05       0    4597     .12       0    4772      .1       0
  4971.7     .07       0    5016      .1       0  5316.6     .12       0
Bank Sta=4971.7,5016
XS Rating Curve= 0 ,0
Exp/Cntr=0.3,0.1

Type RM Length L Ch R = 1 ,12719   ,130,130,130
BEGIN DESCRIPTION:
Mapping XS c284c707
END DESCRIPTION:
XS GIS Cut Line= 2
      3858355.56       10058177.      3858372.92     10056838.51
#Sta/Elev= 30
  4229.8  110.91  4285.7  107.96  4355.7  108.47  4365.7  109.42  4375.7  108.66
  4425.7  109.35  4485.7  109.26  4525.8  107.88  4547.6  108.45  4645.9  106.63
  4745.8  102.72  4796.3   98.52  4839.4   98.36  4945.8   98.13  4965.8   95.84
  4985.8   96.82  4995.8   95.51  4997.4   92.97  5014.1   92.97  5022.5   96.77
  5025.8    98.1  5045.8   99.19  5105.8   96.93  5155.8  100.08  5392.7  107.17
  5465.8  110.61  5485.8  110.64  5545.4  119.14  5561.8  120.85  5568.4  120.45
#Mann= 8 ,-1 , 0
  4229.8     .12       0  4547.6     .05       0  4645.9     .12       0
  4839.4      .1       0  4985.8     .07       0  5022.5      .1       0
  5392.7     .12       0  5545.4     .05       0
Bank Sta=4985.8,5022.5
XS Rating Curve= 0 ,0
Exp/Cntr=0.3,0.1

Type RM Length L Ch R = 1 ,12589   ,585,585,585
BEGIN DESCRIPTION:
WHITE OAK CREEK WEST 22.0
END DESCRIPTION:
XS GIS Cut Line= 3
       3858444.8     10058182.69      3858484.73     10057333.73
      3858542.85     10056536.05
#Sta/Elev= 30
  4183.7  110.42  4365.5  106.18  4395.6  107.23  4503.7  106.49  4675.9  102.29
  4725.9  100.08  4745.9   98.03  4775.9   98.26    4796   96.91  4839.7   97.79
  4926.1   98.46  4956.2   97.55 4969.99  95.321  4986.2   92.18  4997.9   91.38
  5014.6   91.38  5032.4   95.48  5076.4   96.28  5086.4   98.11  5106.5      99
  5292.2  103.86  5397.2  107.21  5407.2   108.3  5429.8  108.34  5527.6   110.4
  5587.7  110.22  5647.9  112.02  5699.4  110.13  5748.1  112.62  5833.4  113.13
#Mann= 7 ,-1 , 0
  4183.7     .12       0  4503.7     .05       0  4839.7      .1       0
 4969.99     .07       0  5032.4      .1       0  5292.2     .12       0
  5429.8     .05       0
Bank Sta=4969.99,5032.4
XS Rating Curve= 0 ,0
Exp/Cntr=0.3,0.1

Type RM Length L Ch R = 1 ,12004   ,486,486,486
BEGIN DESCRIPTION:
WHITE OAK CREEK WEST 21.0
END DESCRIPTION:
XS GIS Cut Line= 3
      3858689.42     10057770.17      3858889.94     10057409.51
      3858797.24     10056786.12
#Sta/Elev= 30
  4451.5  104.05  4495.1  102.85  4538.6   99.88  4553.4  100.08    4566   98.97
  4586.5   98.64  4668.3   97.75  4782.2   96.83  4803.9   97.35  4831.4   96.52
  4853.1   97.58  4882.8   95.34    4903    95.1  4910.2   93.42  4915.3   95.98
  4973.8   97.72  4984.6   94.93    4994   92.69  4995.7   90.19  5012.5   90.19
  5024.3   95.22  5043.9   95.99  5054.7   98.29  5074.9   100.1  5111.7  101.75
  5239.6  103.67  5297.3  103.99  5378.2  106.21  5428.7  110.78  5494.4  112.96
#Mann= 7 ,-1 , 0
  4451.5     .12       0  4586.5      .1       0  4668.3     .12       0
  4984.6     .07       0  5024.3     .12       0  5111.7      .1       0
  5239.6     .12       0
Bank Sta=4984.6,5024.3
XS Rating Curve= 0 ,0
Exp/Cntr=0.3,0.1

Type RM Length L Ch R = 1 ,11518   ,518,518,518
BEGIN DESCRIPTION:
WHITE OAK CREEK WEST 20.0
END DESCRIPTION:
XS GIS Cut Line= 3
       3858579.2      10058058.7      3859236.73     10057312.64
      3859100.35     10056734.67
#Sta/Elev= 30
  4085.4  109.19  4132.6  105.23  4139.3  103.02  4226.1  101.03  4281.5   98.82
  4331.9   99.85  4380.2   99.72    4402  101.62  4529.2   97.42  4649.6   95.94
  4741.7   96.62  4770.1   95.36  4868.8   96.99  4890.6   92.64  4911.5   95.54
  4954.2   93.05  4975.3   95.67  4989.3   92.99  4995.1   87.78  5011.9   87.78
  5017.7   94.34  5020.8  95.882  5025.3   98.12  5053.8   99.65    5102   99.96
  5153.4   98.36  5341.4   98.59  5389.8   98.66  5584.9  102.45  5673.7  106.52
#Mann= 7 ,-1 , 0
  4085.4     .12       0  4226.1     .05       0  4331.9     .12       0
  4975.3     .07       0  5020.8     .12       0  5341.4      .1       0
  5389.8     .12       0
Bank Sta=4975.3,5020.8
XS Rating Curve= 0 ,0
Exp/Cntr=0.3,0.1

Type RM Length L Ch R = 1 ,11000   ,500,500,500
BEGIN DESCRIPTION:
WHITE OAK CREEK WEST 19.0
END DESCRIPTION:
XS GIS Cut Line= 3
      3858636.71     10058141.58      3859484.94     10057606.86
      3859295.64     10056574.37
#Sta/Elev= 30
  3997.3  109.48  4031.6  104.11  4303.9   98.61  4403.2   99.35  4592.3  101.51
  4753.5   95.28  4868.9   95.66  4890.1      92  4911.3    91.9  4926.5   93.21
  4932.5   95.65  4947.7   94.62  4968.9   91.78  4975.8   87.33  4992.6   87.33
  5011.3   92.46  5016.4    91.7  5026.2   94.45  5046.6   96.01  5127.9   95.57
  5219.4  100.35  5326.2   98.41  5374.3   97.86  5621.9   99.34  5706.4   97.37
  5870.1   98.69    5911  101.59  5931.1  100.42  6008.5  108.66  6049.7  110.96
#Mann= 10 ,-1 , 0
  3997.3     .12       0  4031.6     .05       0  4403.2     .12       0
  4947.7     .07       0  5026.2     .12       0  5326.2      .1       0
  5374.3     .12       0  5621.9      .1       0  5706.4     .12       0
    5911      .1       0
Bank Sta=4947.7,5026.2
XS Rating Curve= 0 ,0
Exp/Cntr=0.3,0.1

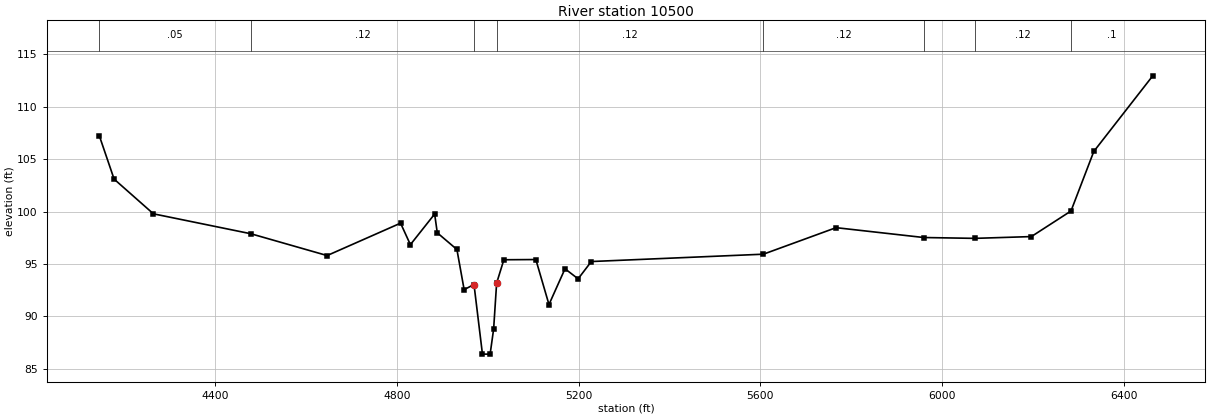
Type RM Length L Ch R = 1 ,10500   ,491,491,491
BEGIN DESCRIPTION:
WHITE OAK CREEK WEST 18.0
END DESCRIPTION:
XS GIS Cut Line= 4
       3858884.8     10058222.21      3859628.24     10057800.72
      3859797.81     10057666.51      3859290.36     10056527.06
#Sta/Elev= 30
  4145.4  107.23  4177.9   103.1  4264.4   99.79  4478.8   97.89  4646.7   95.81
  4808.3    98.9  4829.9   96.85  4883.3   99.77  4889.1   97.98  4932.3   96.39
  4948.2   92.56  4969.9   93.05  4988.5   86.41  5005.4   86.41  5013.1    88.8
  5019.7  93.181  5035.6   95.41    5106   95.43  5134.9   91.14  5170.2   94.55
    5199   93.59  5228.1   95.24  5606.7   95.94  5766.7   98.47  5959.7   97.53
  6072.2   97.45  6196.5   97.62  6283.7  100.06  6333.9  105.74  6463.6  112.95
#Mann= 8 ,-1 , 0
  4145.4     .05       0  4478.8     .12       0  4969.9     .07       0
  5019.7     .12       0  5606.7     .12       0  5959.7      .1       0
  6072.2     .12       0  6283.7      .1       0
Bank Sta=4969.9,5019.7
XS Rating Curve= 0 ,0
Exp/Cntr=0.3,0.1