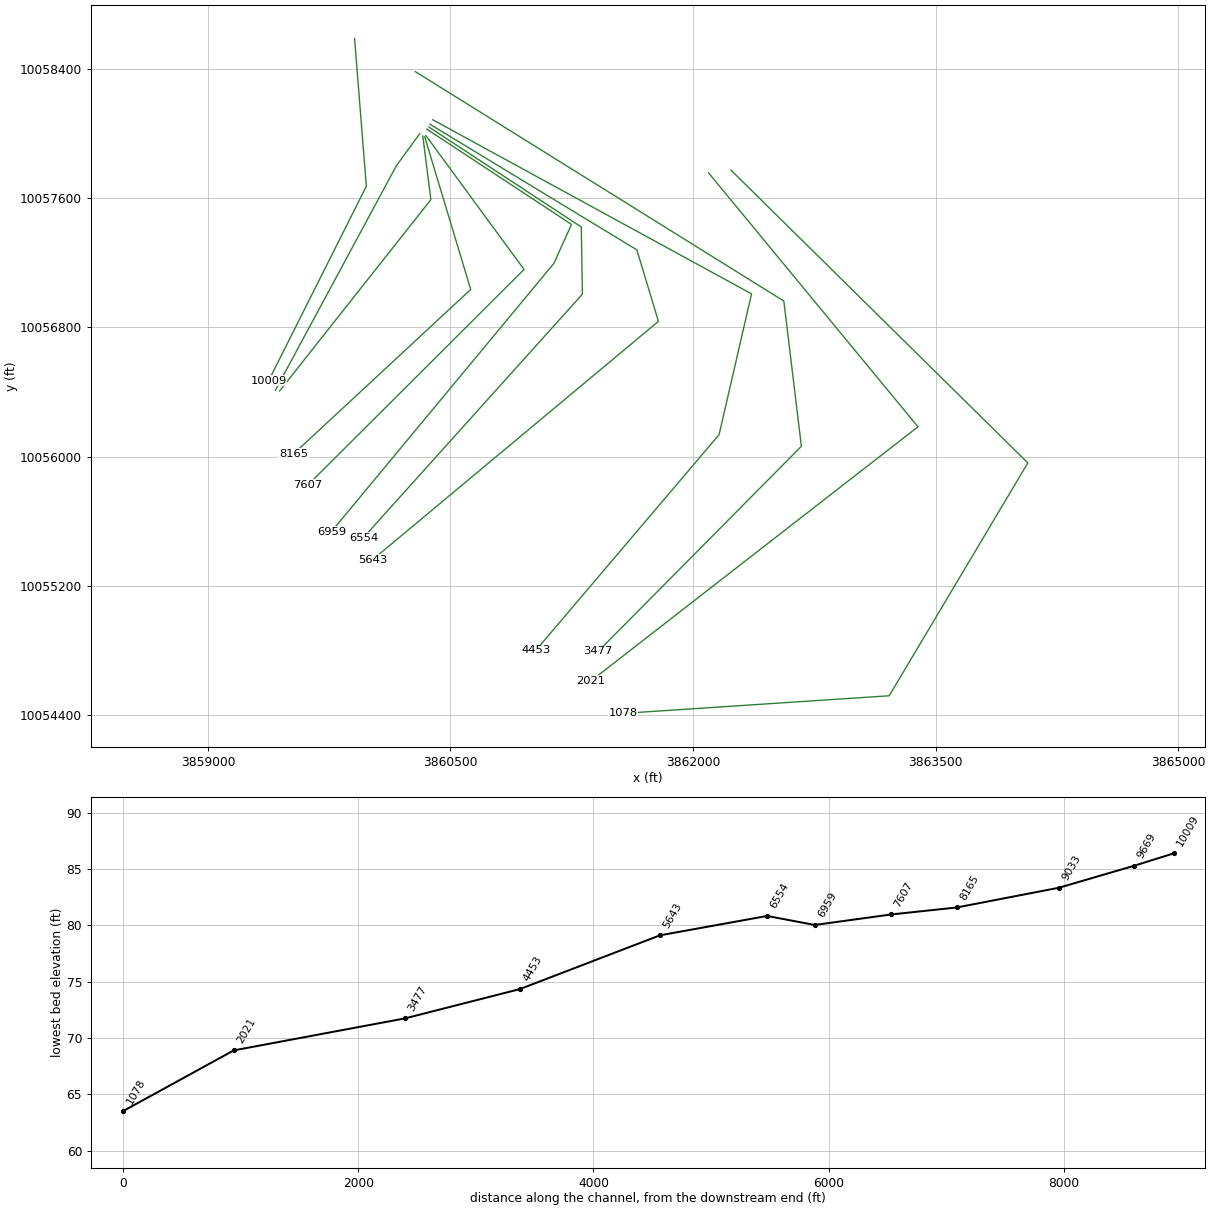
HEC-RAS study WHITE OAK CREEK WEST.prj: WHITE OAK CREEK WEST Base Level Engineering

--- WHITE OAK CREEK WEST.g10 (geometry) --- (continued)

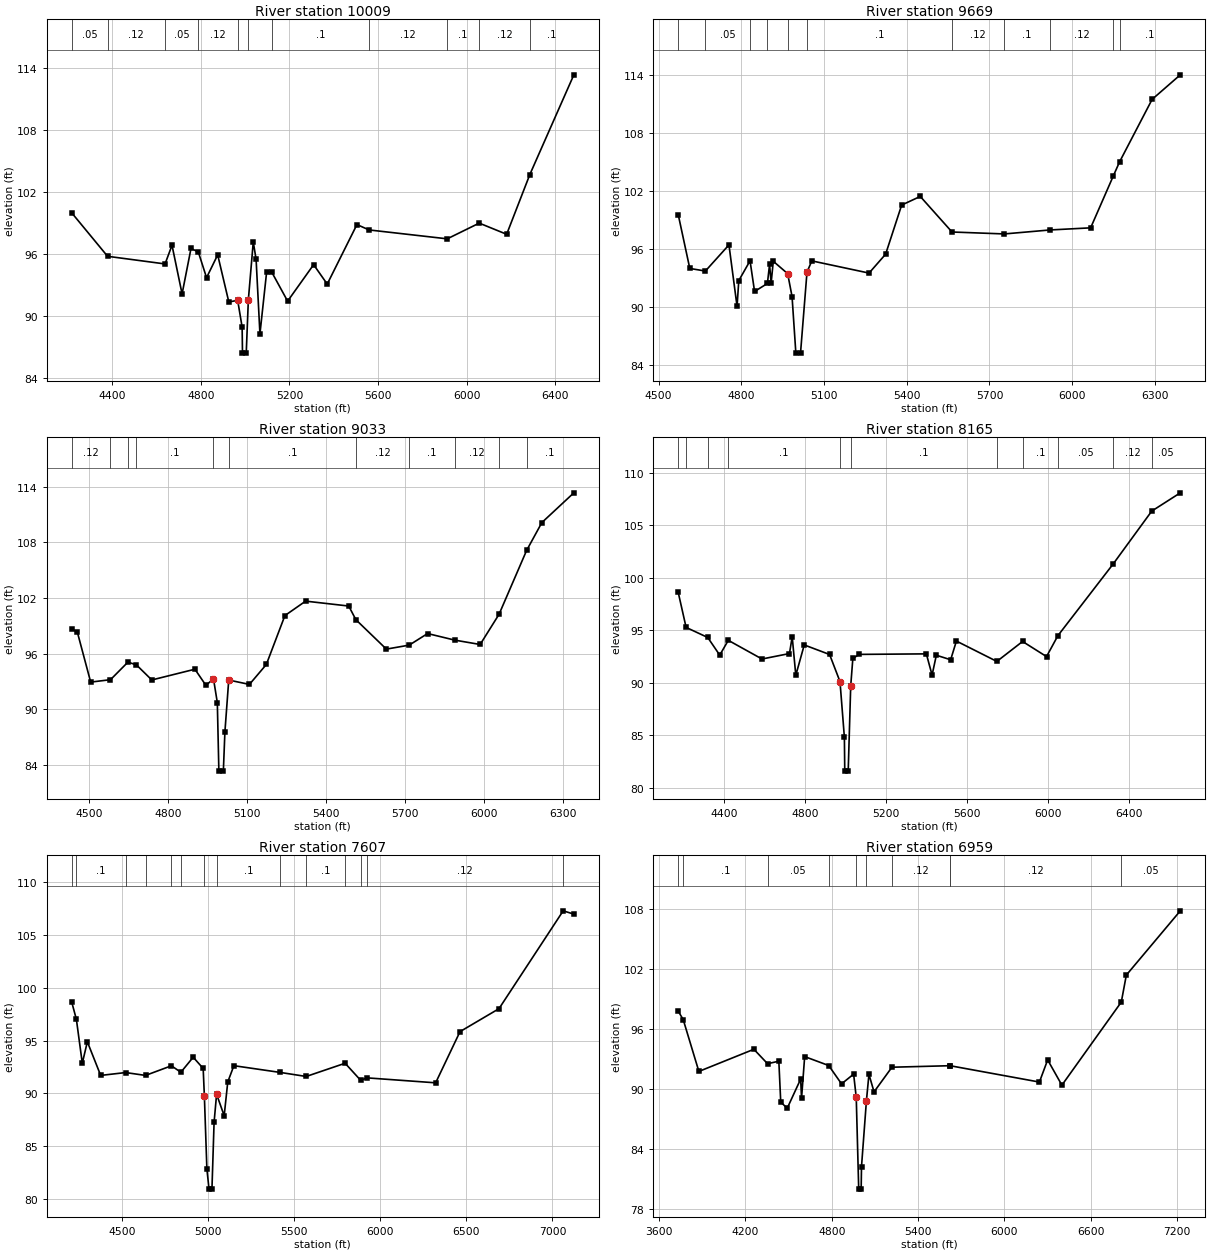
Type RM Length L Ch R = 1 ,10009   ,340,340,340
BEGIN DESCRIPTION:
WHITE OAK CREEK WEST 17.0
END DESCRIPTION:
XS GIS Cut Line= 3
      3859906.96     10058587.24      3859979.88     10057672.28
      3859375.29     10056468.32
#Sta/Elev= 30
    4218   99.94  4379.5   95.74  4638.9      95  4670.2   96.81  4715.7    92.1
  4755.9    96.5  4788.9   96.16  4826.1   93.67  4876.3   95.88  4926.5   91.32
  4966.5   91.48  4986.6   88.88  4988.2   86.37  5005.1   86.37 5014.62  91.523
  5036.8   97.13  5049.6   95.44  5066.9   88.23  5096.9   94.18  5119.9   94.22
  5191.8    91.4  5309.1   94.93  5370.5   93.05  5504.5   98.81  5559.4   98.29
  5911.9   97.43  6056.3   98.95    6180   97.87  6284.5  103.65  6483.1   113.3
#Mann= 11 ,-1 , 0
    4218     .05       0  4379.5     .12       0  4638.9     .05       0
  4788.9     .12       0  4966.5     .07       0 5014.62     .05       0
  5119.9      .1       0  5559.4     .12       0  5911.9      .1       0
  6056.3     .12       0  6284.5      .1       0
Bank Sta=4966.5,5014.62
XS Rating Curve= 0 ,0
Exp/Cntr=0.3,0.1

Type RM Length L Ch R = 1 ,9669    ,636,636,636
BEGIN DESCRIPTION:
WHITE OAK CREEK WEST 16.0
END DESCRIPTION:
XS GIS Cut Line= 3
      3860309.72     10057996.91      3860165.64     10057799.24
      3859417.84     10056411.05
#Sta/Elev= 30
    4571   99.55  4612.9      94  4669.5   93.73    4755   96.43  4784.4   90.08
  4790.6   92.74  4831.5   94.79  4847.9   91.62  4894.5   92.45  4902.3   94.41
    4908   92.49  4915.8   94.74    4968   93.46  4983.9    91.1  4997.7   85.26
  5014.6   85.26  5038.1  93.621  5055.6   94.78  5263.2   93.52  5323.3   95.47
  5381.5  100.54    5449  101.43  5564.2   97.76    5754   97.56  5919.6   97.97
  6067.1   98.19  6149.1  103.53  6171.9  104.99  6290.2  111.45  6392.4  113.98
#Mann= 11 ,-1 , 0
    4571     .12       0  4669.5     .05       0  4831.5     .12       0
  4894.5      .1       0    4968     .07       0  5038.1      .1       0
  5564.2     .12       0    5754      .1       0  5919.6     .12       0
  6149.1     .05       0  6171.9      .1       0
Bank Sta=4968,5038.1
XS Rating Curve= 0 ,0
Exp/Cntr=0.3,0.1

Type RM Length L Ch R = 1 ,9033    ,868,868,868
BEGIN DESCRIPTION:
WHITE OAK CREEK WEST 15.0
END DESCRIPTION:
XS GIS Cut Line= 3
      3860329.05     10057982.21      3860378.97     10057589.38
      3859443.53     10056405.92
#Sta/Elev= 30
  4435.1   98.68  4456.4   98.31  4506.8   92.93    4582   93.19  4648.3   95.09
  4680.6   94.78  4738.7   93.16  4902.2   94.32  4943.9   92.58  4972.7   93.28
  4987.2   90.72  4993.1   83.32  5010.1   83.32    5016   87.56  5030.5   93.15
    5109   92.68  5173.1   94.83  5243.6  100.11  5322.2  101.67  5485.7  101.14
  5512.7   99.67  5628.4   96.49    5715   96.92  5784.9   98.17    5888   97.46
  5984.2   96.99  6055.9  100.25  6160.4  107.14  6218.3  110.15  6339.6  113.36
#Mann= 11 ,-1 , 0
  4435.1     .12       0    4582      .1       0  4648.3     .12       0
  4680.6      .1       0  4972.7     .07       0  5030.5      .1       0
  5512.7     .12       0    5715      .1       0    5888     .12       0
  6055.9     .05       0  6160.4      .1       0
Bank Sta=4972.7,5030.5
XS Rating Curve= 0 ,0
Exp/Cntr=0.3,0.1

Type RM Length L Ch R = 1 ,8165    ,558,558,558
BEGIN DESCRIPTION:
WHITE OAK CREEK WEST 14.0
END DESCRIPTION:
XS GIS Cut Line= 3
      3860340.98     10057977.58      3860625.28     10057033.54
      3859528.72     10056015.49
#Sta/Elev= 30
    4173   98.59  4211.9   95.26  4318.9    94.3  4378.2   92.62  4420.5   94.03
  4587.1   92.25  4722.9   92.77  4736.4   94.37  4754.2    90.7    4796   93.59
  4921.3   92.68  4972.7    90.1  4994.4   84.79  4996.3   81.57  5013.3   81.57
  5025.7   89.68  5036.2    92.3  5067.5   92.69  5399.6   92.74    5428   90.72
    5449   92.61  5519.8   92.18  5548.2   93.96  5748.2   92.02  5875.4   93.92
  5993.8   92.48  6050.2   94.48  6323.9  101.32    6514  106.34  6655.2  108.08
#Mann= 11 ,-1 , 0
    4173     .12       0  4211.9      .1       0  4318.9     .12       0
  4420.5      .1       0  4972.7     .07       0  5025.7      .1       0
  5748.2     .12       0  5875.4      .1       0  6050.2     .05       0
  6323.9     .12       0    6514     .05       0
Bank Sta=4972.7,5025.7
XS Rating Curve= 0 ,0
Exp/Cntr=0.3,0.1

Type RM Length L Ch R = 1 ,7607    ,648,648,648
BEGIN DESCRIPTION:
WHITE OAK CREEK WEST 13.0
END DESCRIPTION:
XS GIS Cut Line= 3
      3860347.51     10057986.38      3860955.14     10057157.24
      3859619.42     10055824.98
#Sta/Elev= 30
  4209.9   98.62  4236.8   96.99    4271   92.85  4300.3   94.88  4377.7    91.7
  4522.7   91.97    4638    91.7  4788.2   92.61  4843.2      92  4914.8   93.42
  4972.7   92.36  4979.6   89.76  4994.2   82.87  5006.6   80.95  5023.6   80.95
    5036   87.26  5050.6   89.92  5094.6   87.89  5115.4   91.08    5151   92.62
    5421   91.98  5570.7    91.6  5796.6   92.85  5887.3   91.23  5922.5   91.47
  6322.2      91  6463.6   95.84  6689.9   98.01  7062.5  107.26  7124.4  106.95
#Mann= 14 ,-1 , 0
  4209.9     .12       0  4236.8      .1       0  4522.7     .12       0
    4638      .1       0  4788.2     .05       0  4843.2      .1       0
  4979.6     .07       0  5050.6      .1       0    5421     .12       0
  5570.7      .1       0  5796.6     .12       0  5887.3      .1       0
  5922.5     .12       0  7062.5     .05       0
Bank Sta=4979.6,5050.6
XS Rating Curve= 0 ,0
Exp/Cntr=0.3,0.1

Type RM Length L Ch R = 1 ,6959    ,405,405,405
BEGIN DESCRIPTION:
WHITE OAK CREEK WEST 12.0
END DESCRIPTION:
XS GIS Cut Line= 4
      3860353.71      10058025.5      3861248.43     10057436.13
      3861140.04      10057195.6       3859764.3     10055535.86
#Sta/Elev= 30
  3732.9   97.77  3767.5   96.93  3876.4   91.76  4258.9   93.97    4354   92.53
  4432.4   92.78  4445.6    88.7  4490.8   88.09  4584.2      91  4590.2   89.06
    4612   93.24    4779   92.35  4868.4   90.52  4952.4   91.49  4970.6  89.176
  4987.8   80.02  5004.8   80.02  5007.2   82.27  5041.3   88.82  5058.9   91.47
  5094.3   89.72  5218.8   92.18  5619.1   92.33  5619.2   92.34  6244.2    90.7
  6301.5   92.91  6400.5   90.39  6813.6   98.68  6848.5  101.37  7223.9  107.78
#Mann= 10 ,-1 , 0
  3732.9     .12       0  3767.5      .1       0    4354     .05       0
    4779      .1       0  4970.6     .07       0  5041.3      .1       0
  5218.8     .12       0  5619.1      .1       0  5619.2     .12       0
  6813.6     .05       0
Bank Sta=4970.6,5041.3
XS Rating Curve= 0 ,0
Exp/Cntr=0.3,0.1

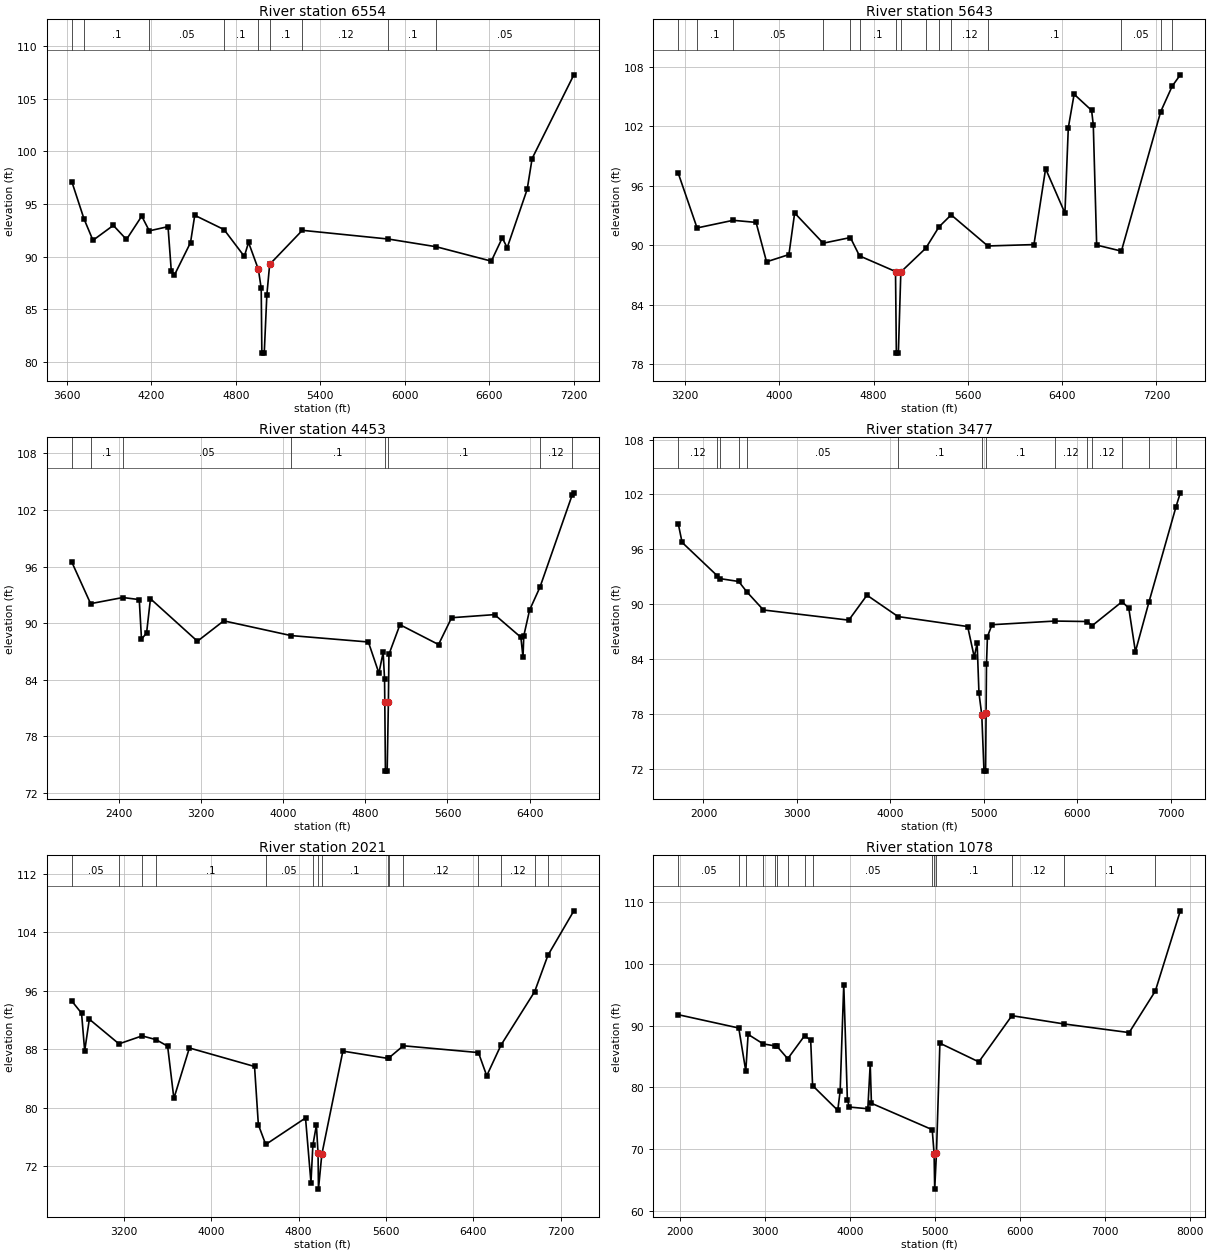
Type RM Length L Ch R = 1 ,6554    ,911,911,911
BEGIN DESCRIPTION:
WHITE OAK CREEK WEST 11.0
END DESCRIPTION:
XS GIS Cut Line= 4
      3860366.71     10058038.54      3861309.12     10057420.03
      3861315.86     10057004.41      3859961.97     10055498.59
#Sta/Elev= 30
  3634.2   97.14  3721.1   93.59  3784.8   91.55  3929.5   92.97  4022.9   91.63
  4131.4   93.85  4185.1   92.45  4318.2   92.85  4341.3   88.65  4363.5   88.24
    4478   91.33  4508.1   93.93  4716.3   92.57  4860.4   90.02  4890.4   91.35
  4960.4   88.78  4980.4   86.98    4985   80.82    5002   80.82  5020.4   86.34
  5040.5   89.26  5272.6    92.5  5884.5   91.67  6223.5   90.94  6615.6   89.57
  6693.4   91.78  6728.5   90.85  6870.5    96.4  6905.6   99.33  7202.1  107.29
#Mann= 9 ,-1 , 0
  3634.2     .12       0  3721.1      .1       0  4185.1     .05       0
  4716.3      .1       0  4960.4     .07       0  5040.5      .1       0
  5272.6     .12       0  5884.5      .1       0  6223.5     .05       0
Bank Sta=4960.4,5040.5
XS Rating Curve= 0 ,0
Exp/Cntr=0.3,0.1

Type RM Length L Ch R = 1 ,5643    ,1190,1190,1190
BEGIN DESCRIPTION:
WHITE OAK CREEK WEST 9.0
END DESCRIPTION:
XS GIS Cut Line= 4
      3860373.26     10058055.87      3861652.68     10057278.68
      3861786.01     10056836.26      3860017.84     10055361.06
#Sta/Elev= 30
  3141.2   97.27  3301.1   91.74  3606.8   92.51  3801.8    92.3  3890.8   88.32
  4080.7   89.05  4129.4   93.25  4371.6    90.2  4602.3   90.77  4679.9   88.92
  4985.5   87.34  4992.7    79.1  5009.7    79.1  5030.7  87.292  5242.1   89.69
  5354.7   91.85  5457.9   93.06  5768.9   89.92  6160.6   90.06  6259.6   97.72
  6423.6   93.24  6452.2  101.85  6501.6  105.24    6650  103.61  6664.3  102.15
    6693   90.01  6902.9    89.4  7236.2  103.47  7334.3  106.06    7403   107.2
#Mann= 15 ,-1 , 0
  3141.2     .12       0  3301.1      .1       0  3606.8     .05       0
  4371.6      .1       0  4602.3     .05       0  4679.9      .1       0
  4985.5     .07       0  5030.7      .1       0  5242.1     .12       0
  5354.7     .05       0  5457.9     .12       0  5768.9      .1       0
  6902.9     .05       0  7236.2     .12       0  7334.3     .05       0
Bank Sta=4985.5,5030.7
XS Rating Curve= 0 ,0
Exp/Cntr=0.3,0.1

Type RM Length L Ch R = 1 ,4453    ,976,976,976
BEGIN DESCRIPTION:
WHITE OAK CREEK WEST 8.0
END DESCRIPTION:
XS GIS Cut Line= 4
       3860390.5     10058083.49      3862361.89      10057006.5
       3862161.3     10056135.59      3861029.38     10054802.28
#Sta/Elev= 30
  1941.8   96.48  2125.3   92.07  2439.2   92.72  2598.9    92.5  2620.8   88.32
  2670.1   88.95  2708.1   92.59  3165.4   88.09  3421.6   90.25  4076.2   88.69
    4830   88.01  4932.6   84.71  4973.7    86.9  4987.5   84.13 4990.02  81.633
    4996   74.33    5013   74.33    5025   81.63  5030.3    86.7  5137.5   89.84
  5513.2   87.74  5640.6   90.58    6059   90.91    6315   88.51  6335.8    86.4
  6343.6   88.67  6399.6   91.38  6501.1   93.82  6815.9  103.62  6830.9  103.81
#Mann= 8 ,-1 , 0
  1941.8     .12       0  2125.3      .1       0  2439.2     .05       0
  4076.2      .1       0 4990.02     .07       0    5025      .1       0
  6501.1     .12       0  6815.9     .05       0
Bank Sta=4990.02,5025
XS Rating Curve= 0 ,0
Exp/Cntr=0.3,0.1

Type RM Length L Ch R = 1 ,3477    ,1456,1456,1456
BEGIN DESCRIPTION:
WHITE OAK CREEK WEST 6.0
END DESCRIPTION:
XS GIS Cut Line= 4
      3860282.98     10058381.11      3862561.62     10056961.84
      3862670.13      10056063.4      3861413.86     10054795.28
#Sta/Elev= 30
  1729.9   98.81    1771   96.76    2147   93.11  2179.1   92.79  2377.2   92.48
  2464.6   91.34  2642.1   89.36  3555.5   88.25  3750.2   90.98    4083   88.64
  4828.2   87.55  4898.7   84.21  4929.5   85.73    4949   80.28  4979.2   77.88
  5002.9   71.73    5020   71.73 5025.22   78.05  5029.6   83.45  5039.7   86.44
  5088.4   87.75  5761.7   88.15  6104.8    88.1  6161.6   87.65    6481   90.27
    6553   89.55  6623.7   84.81  6769.6   90.26  7056.5  100.59  7104.4  102.18
#Mann= 14 ,-1 , 0
  1729.9     .12       0    2147      .1       0  2179.1     .05       0
  2377.2      .1       0  2464.6     .05       0    4083      .1       0
  4979.2     .07       0 5025.22      .1       0  5761.7     .12       0
  6104.8      .1       0  6161.6     .12       0    6481      .1       0
  6769.6     .12       0  7056.5     .05       0
Bank Sta=4979.2,5025.22
XS Rating Curve= 0 ,0
Exp/Cntr=0.3,0.1

Type RM Length L Ch R = 1 ,2021    ,943,943,943
BEGIN DESCRIPTION:
WHITE OAK CREEK WEST 4.0
END DESCRIPTION:
XS GIS Cut Line= 3
      3862095.89     10057755.26      3863391.05     10056184.06
      3861367.88     10054611.09
#Sta/Elev= 30
  2721.5    94.6  2811.1   92.93  2839.8   87.78  2882.4   92.11  3153.8   88.74
  3365.8   89.83  3492.7   89.32  3599.4   88.43  3656.8   81.28  3798.8   88.18
  4395.6   85.65  4430.7   77.69  4498.2   74.99  4862.6   78.61  4912.4   69.79
    4930   74.91  4962.2   77.63 4977.33  73.787  4981.2   68.89  5011.9   73.64
  5204.7   87.75  5613.9   86.76  5629.9   86.87  5758.4   88.48  6446.4   87.55
  6522.4   84.38    6653   88.57  6961.5   95.88  7082.8  100.84  7320.4  106.92
#Mann= 15 ,-1 , 0
  2721.5     .05       0  3153.8      .1       0  3365.8     .05       0
  3492.7      .1       0  4498.2     .05       0    4930      .1       0
 4977.33     .07       0  5011.9      .1       0  5613.9     .12       0
  5629.9      .1       0  5758.4     .12       0  6446.4      .1       0
    6653     .12       0  6961.5      .1       0  7082.8     .05       0
Bank Sta=4977.33,5011.9
XS Rating Curve= 0 ,0
Exp/Cntr=0.3,0.1

Type RM Length L Ch R = 1 ,1078    ,0,0,0
BEGIN DESCRIPTION:
WHITE OAK CREEK WEST 2.0
END DESCRIPTION:
XS GIS Cut Line= 4
      3862235.67     10057770.86      3864070.42     10055960.43
       3863213.1       10054520.      3861567.85     10054411.07
#Sta/Elev= 30
  1980.5   91.77    2692   89.61  2774.6   82.64  2802.1   88.58  2979.9   87.03
  3123.9    86.7  3140.4   86.66  3267.9   84.63  3465.9   88.36  3537.6   87.64
  3560.1   80.28  3855.8   76.26    3884   79.38  3926.5   96.66  3968.9   78.02
  3990.2    76.8  4209.3   76.52  4237.6   83.76  4251.8   77.41  4966.4   73.13
  4988.6   69.26  4995.5   63.49 5016.42  69.362  5056.8   87.15  5514.4   84.12
  5903.2   91.61  6516.3   90.27  7281.9   88.87  7589.5   95.61  7883.2  108.61
#Mann= 15 ,-1 , 0
  1980.5     .05       0    2692     .12       0  2774.6      .1       0
  2979.9     .12       0  3123.9     .05       0  3140.4     .12       0
  3267.9     .05       0  3465.9     .12       0  3560.1     .05       0
  4966.4      .1       0  4988.6     .07       0 5016.42      .1       0
  5903.2     .12       0  6516.3      .1       0  7589.5     .12       0
Bank Sta=4988.6,5016.42
XS Rating Curve= 0 ,0
Exp/Cntr=0.3,0.1