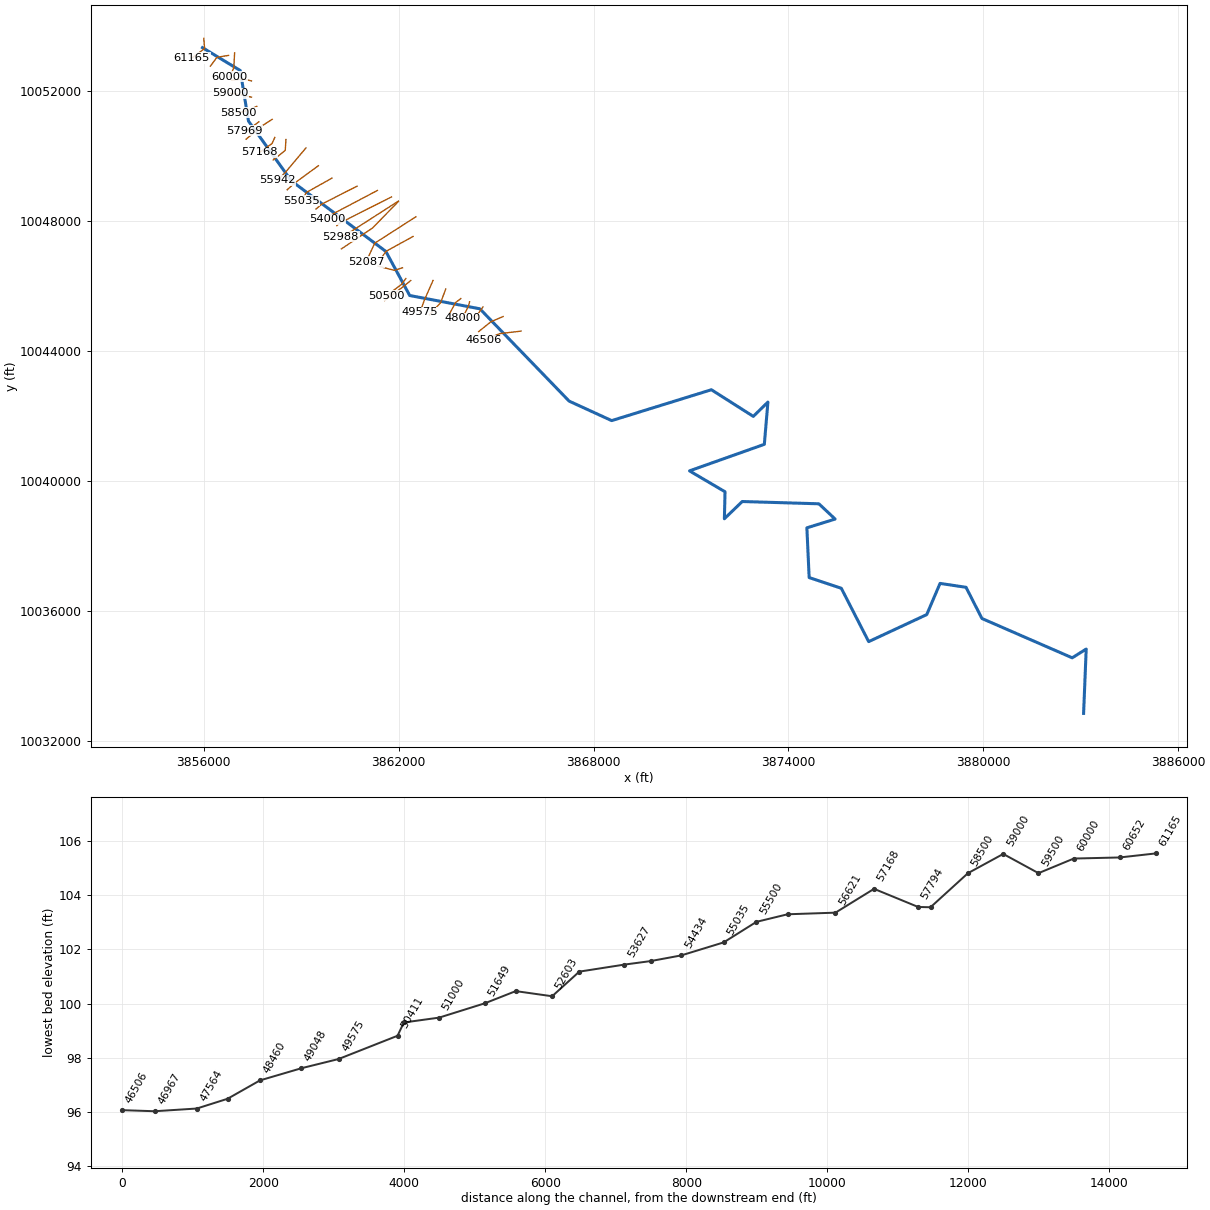
--- WOODSONS GULLY.prj (project) ---

Proj Title=WOODSONS GULLY Base Level Engineering
Current Plan=p01
Default Exp/Contr=0.3,0.1
English Units
Geom File=g01
Flow File=f01
Plan File=p01
Y Axis Title=Elevation
X Axis Title(PF)=Main Channel Distance
X Axis Title(XS)=Station
BEGIN DESCRIPTION:
WOODSONS GULLY
END DESCRIPTION:
DSS File=dss
DSS Export Rating Curves= 0
DSS Export Rating Curve Sorted= 0
DSS Export Volume Flow Curves= 0
DXF OffsetX= 0
DXF OffsetY= 0
DXF ScaleX= 1
DXF ScaleY= 10

--- WOODSONS GULLY.p01 (plan) ---

Plan Title=Multiple Run
Program Version=4.10
Geom File=g01
Subcritical Flow
K Sum by GR= 0
Std Step Tol= 0.01
Critical Tol= 0.01
Num of Std Step Trials= 20
Max Error Tol= 0.3
Flow Tol Ratio= 0.001
Split Flow NTrial= 30
Split Flow Tol= 0.02
Split Flow Ratio= 0.02
Log Output Level= 0
Friction Slope Method= 1
Unsteady Friction Slope Method= 2
Unsteady Bridges Friction Slope Method= 1
Parabolic Critical Depth
Global Vel Dist= 1 , 1 , 1
Global Log Level= 0
CheckData=True
Encroach Param=-1 ,0,0, 0
BEGIN DESCRIPTION:
Multiple Run
END DESCRIPTION:
Computation Interval=1HOUR
Output Interval=1HOUR
Run HTab= 0
Run UNet= 0
Run PostProcess= 0
Run WQNet= 0
UNET Theta= 1
UNET Theta Warmup= 1
UNET ZTol= 0.02
UNET ZSATol= 0.05
UNET MxIter= 20
UNET MaxInSteps= 0
UNET DtIC= 0
UNET DtMin= 0
UNET MaxCRTS= 20
UNET WFStab= 2
UNET SFStab= 1
UNET WFX= 1
UNET SFX= 1
UNET DSS MLevel= 4
UNET DZMax Abort= 100
UNET Convert EG Bridges= 0
UNET Use Existing IB Tables=-1
UNET Froude Reduction=False
UNET Froude Limit= 1
UNET Froude Power= 10
UNET Time Slicing=0,0, 5
UNET Junction Losses=0
Instantaneous Interval=1HOUR
DSS File=dss
Write IC File= 0
Write IC File at Sim End=0
Echo Input=False
Echo Parameters=False
Echo Output=False
Write Detailed= 0
WQ AD Non Conservative
WQ ULTIMATE=-1
WQ Max Comp Step=1HOUR
WQ Output Interval=15MIN
WQ Output Selected Increments= 0
WQ Output face flow=0
WQ Output face velocity=0
WQ Output face area=0
WQ Output face dispersion=0
WQ Output cell volume=0
WQ Output cell surface area=0
WQ Output cell continuity=0
WQ Output cumulative cell continuity=0
WQ Output face conc=0
WQ Output face dconc_dx=0
WQ Output face courant=0
WQ Output face peclet=0
WQ Output face adv mass=0
WQ Output face disp mass=0
WQ Output cell mass=0
WQ Output cell source sink temp=0
WQ Output cell source sink nsm=0
WQ Output MaxMinRange=-1
WQ Daily Max Min Mean=-1
WQ Daily Range=0
WQ Daily Time=0
WQ Create Restart=0
WQ Fixed Restart=0
WQ System Summary=0
WQ Use Fixed Temperature=0
Sorting and Armoring Iterations= 10
XS Update Threshold= 0.02
Hydraulics Update Threshold= 0.02
Energy Slope Method= 1
Volume Change Method= 0
XS Weighting Method= 0
Number of US Weighted Cross Sections= 1
Number of DS Weighted Cross Sections= 1
Upstream XS Weight=0.25
Main XS Weight=0.5
Downstream XS Weight=0.25
Number of DS XS's Weighted with US Boundary= 1
Upstream Boundary Weight= 1
Weight of XSs Associated with US Boundary= 0
Number of US XS's Weighted with DS Boundary= 1
Downstream Boundary Weight= 0.5
Weight of XSs Associated with DS Boundary= 0.5
Sediment Output Level= 4
Mass or Volume Output= 0
Output Increment Type= 1
Profile and TS Output Increment= 10
XS Output Flag= 0
XS Output Increment= 10
Disregard all LS=0
Disregard all Conn=0
Disregard all Breaches=0
Disregard all Pumps=0

--- WOODSONS GULLY.f01 (steady flow) ---

Flow Title=Multiple
Program Version=4.10
Number of Profiles= 7
Profile Names=10-year,25-year,50-year,1pct_min,100-year,1pct_plu,500-year
River Rch & RM=WOODSONS GULLY,Reach-1         ,61165
     292     364     466     196     592    1788     984
River Rch & RM=WOODSONS GULLY,Reach-1         ,57794
     516     657     851     362    1092    3298    1858
River Rch & RM=WOODSONS GULLY,Reach-1         ,49575
     556     707     913     386    1167    3524    1971
River Rch & RM=WOODSONS GULLY,Reach-1         ,42624
     869    1130    1484     637    1923    5807    3344
River Rch & RM=WOODSONS GULLY,Reach-1         ,39201
    1152    1535    2049     895    2703    8163    4861
River Rch & RM=WOODSONS GULLY,Reach-1         ,38778
    1152    1535    2049     895    2703    8163    4861
River Rch & RM=WOODSONS GULLY,Reach-1         ,36353
     920    1192    1562     669    2019    6097    3488
River Rch & RM=WOODSONS GULLY,Reach-1         ,25042
    1156    1518    2004     865    2613    7891    4591
River Rch & RM=WOODSONS GULLY,Reach-1         ,14030
    1338    1771    2352    1021    3082    9307    5473
River Rch & RM=WOODSONS GULLY,Reach-1         ,6380
    1425    1892    2521    1097    3312   10002    5913
Boundary for River Rch & Prof#=WOODSONS GULLY,Reach-1         , 1
Up Type= 0
Dn Type= 3
Dn Slope=0.005
Boundary for River Rch & Prof#=WOODSONS GULLY,Reach-1         , 2
Up Type= 0
Dn Type= 3
Dn Slope=0.005
Boundary for River Rch & Prof#=WOODSONS GULLY,Reach-1         , 3
Up Type= 0
Dn Type= 3
Dn Slope=0.005
Boundary for River Rch & Prof#=WOODSONS GULLY,Reach-1         , 4
Up Type= 0
Dn Type= 3
Dn Slope=0.005
Boundary for River Rch & Prof#=WOODSONS GULLY,Reach-1         , 5
Up Type= 0
Dn Type= 3
Dn Slope=0.005
Boundary for River Rch & Prof#=WOODSONS GULLY,Reach-1         , 6
Up Type= 0
Dn Type= 3
Dn Slope=0.005
Boundary for River Rch & Prof#=WOODSONS GULLY,Reach-1         , 7
Up Type= 0
Dn Type= 3
Dn Slope=0.005
DSS Import GetInterval= 0
DSS Import GetPeak= 0
DSS Import FillOption= 0

--- WOODSONS GULLY.g01 (geometry) ---

Geom Title=Existing Conditions
Program Version=4.10

River Reach=WOODSONS GULLY  ,Reach-1
Reach XY= 30
       3855959.5     10053335.23      3857120.52     10052631.58
      3857376.57     10051073.77      3858695.92      10049234.5
      3861603.71     10047065.44      3862339.58     10045707.02
        3864500.     10045297.86      3867248.24     10042456.86
      3868558.24     10041856.86      3871628.24     10042806.86
      3872918.24     10041986.86      3873368.24     10042426.86
      3873258.24     10041126.86      3870953.67     10040309.94
      3872048.24     10039666.86      3872028.24     10038836.86
      3872578.24     10039366.86      3874938.24     10039296.86
      3875438.24     10038826.86      3874568.24     10038556.86
      3874638.24     10037026.86      3875628.24     10036696.86
       3876470.9     10035055.02      3878258.24     10035886.86
      3878668.24     10036846.86      3879468.24     10036726.86
      3879958.24     10035766.86      3882738.24     10034556.86
      3883168.24     10034826.86      3883088.24     10032846.86

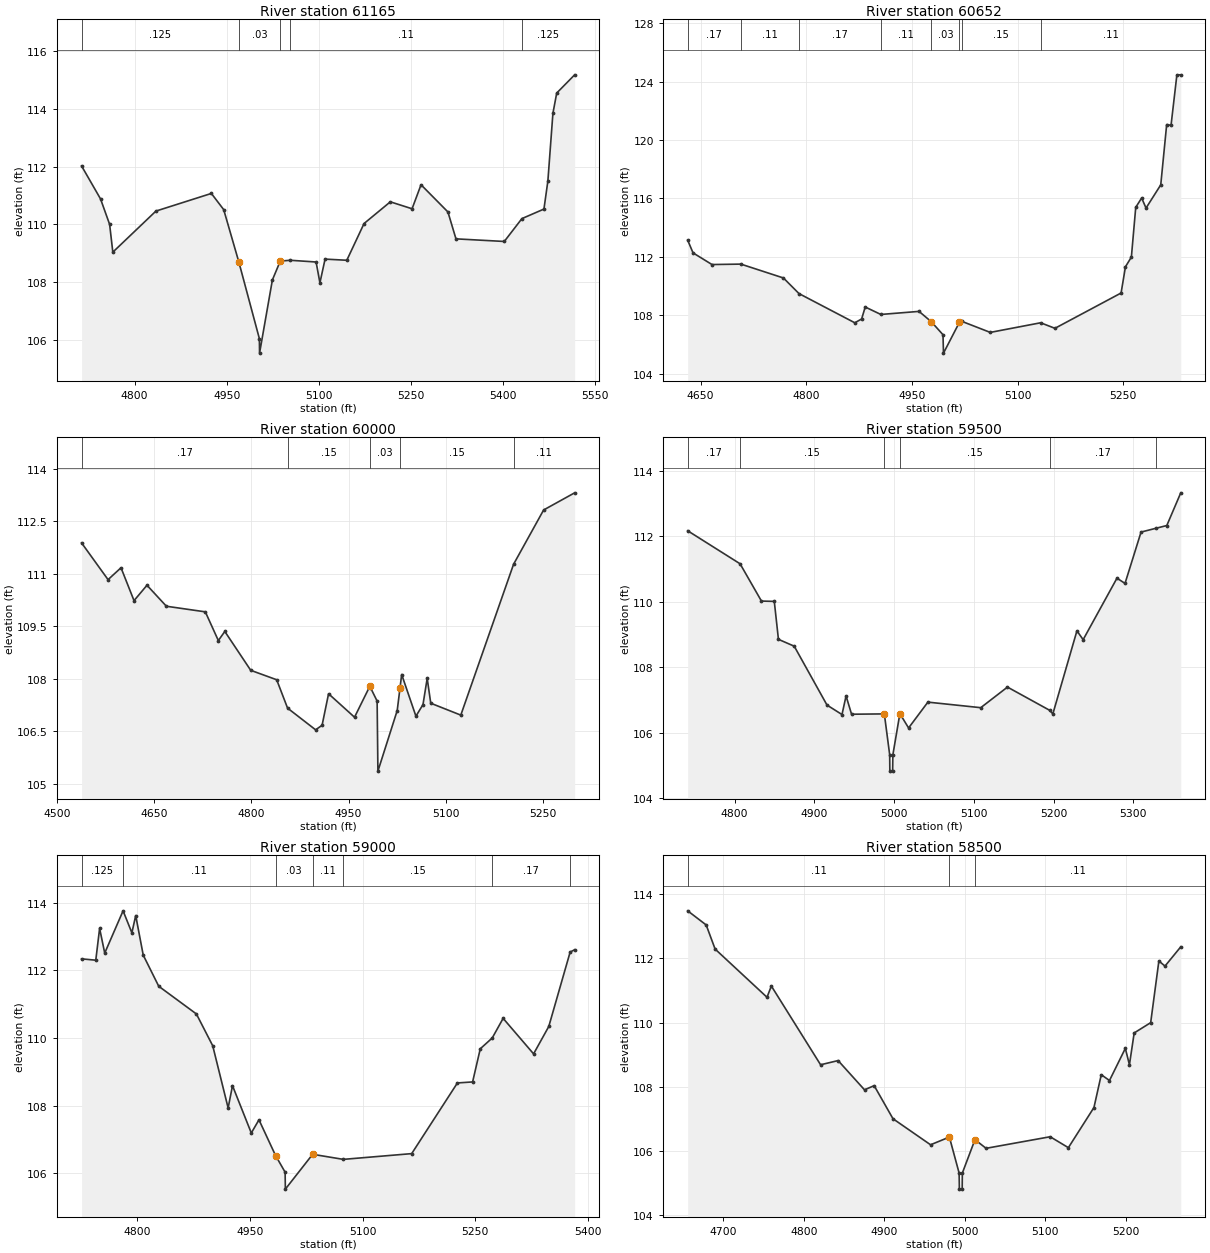
Type RM Length L Ch R = 1 ,61165   ,513,513,513
BEGIN DESCRIPTION:
WOODSONS GULLY 120.0
END DESCRIPTION:
XS GIS Cut Line= 3
      3855999.24     10053621.83       3856024.3     10053308.02
      3855632.89     10053016.09
#Sta/Elev= 30
  4713.6  112.02  4744.5  110.88  4759.3     110  4764.5  109.04  4834.7  110.46
    4925  111.07  4945.1  110.51 4969.86108.6921  5003.2  106.05  5003.5  105.55
  5024.4  108.08  5037.2  108.73  5053.3  108.76  5095.6   108.7  5101.8  107.98
  5110.2   108.8  5145.6  108.76  5173.7  110.03  5216.5  110.78  5251.9  110.54
  5266.5  111.37  5310.3  110.43  5323.4   109.5  5402.1  109.41  5430.8   110.2
  5466.7  110.53  5473.1   111.5  5481.3  113.84  5487.5  114.54  5516.7  115.17
#Mann= 5 ,-1 , 0
  4713.6    .125       0 4969.86     .03       0  5037.2    .125       0
  5053.3     .11       0  5430.8    .125       0
Bank Sta=4969.86,5037.2
XS Rating Curve= 0 ,0
Exp/Cntr=0.3,0.1

Type RM Length L Ch R = 1 ,60652   ,652,652,652
BEGIN DESCRIPTION:
WOODSONS GULLY 119.0
END DESCRIPTION:
XS GIS Cut Line= 3
      3856761.92     10053097.04      3856404.31     10053038.02
      3856202.95     10052767.22
#Sta/Elev= 30
  4631.6  113.14  4639.2  112.27  4666.1  111.47  4707.1   111.5  4767.5  110.55
  4789.6  109.48  4868.8  107.48  4878.5  107.74  4883.6  108.56  4905.8  108.05
    4960  108.26 4977.37107.5544    4994  106.66  4994.7   105.4  5017.3  107.51
  5020.6  107.58  5061.1  106.82  5132.6  107.48  5152.9   107.1  5246.8  109.52
    5253  111.32  5261.4  111.98  5267.6  115.39    5276  116.03  5282.2  115.34
  5303.1  116.93  5311.5  121.06  5317.7  121.01    5326  124.47  5331.5  124.47
#Mann= 8 ,-1 , 0
  4631.6     .17       0  4707.1     .11       0  4789.6     .17       0
  4905.8     .11       0 4977.37     .03       0  5017.3     .11       0
  5020.6     .15       0  5132.6     .11       0
Bank Sta=4977.37,5017.3
XS Rating Curve= 0 ,0
Exp/Cntr=0.3,0.1

Type RM Length L Ch R = 1 ,60000   ,500,500,500
BEGIN DESCRIPTION:
WOODSONS GULLY 118.0
END DESCRIPTION:
XS GIS Cut Line= 3
      3856947.81     10053171.91      3856922.53      10052710.4
      3856800.16     10052437.37
#Sta/Elev= 30
  4537.8  111.88  4578.7  110.83  4598.7  111.17  4618.8  110.23  4638.8  110.67
  4668.8  110.07  4728.9  109.91    4749  109.09    4759  109.35    4799  108.24
  4839.1  107.97  4855.9  107.16  4899.2  106.54  4909.2  106.67  4919.2  107.57
  4959.3   106.9  4982.9107.7836  4994.2  107.36  4995.4  105.36  5025.2  107.09
 5029.52107.7349  5032.1  108.12  5054.1  106.93    5065  107.26  5071.5  108.01
    5077   107.3  5123.4  106.96  5204.9  111.27  5251.3  112.82  5299.2  113.31
#Mann= 5 ,-1 , 0
  4537.8     .17       0  4855.9     .15       0  4982.9     .03       0
 5029.52     .15       0  5204.9     .11       0
Bank Sta=4982.9,5029.52
XS Rating Curve= 0 ,0
Exp/Cntr=0.3,0.1

Type RM Length L Ch R = 1 ,59500   ,500,500,500
BEGIN DESCRIPTION:
WOODSONS GULLY 117.0
END DESCRIPTION:
XS GIS Cut Line= 3
       3857467.9     10052311.06      3857215.96     10052370.24
      3856858.29     10052334.02
#Sta/Elev= 30
  4741.2  112.17  4806.9  111.16  4833.7  110.02  4849.8  110.01    4855  108.85
  4874.8  108.64  4915.9  106.84  4934.7  106.55  4939.8  107.12  4946.7  106.56
  4987.8  106.57  4994.5  105.32  4994.7  104.82  4998.2  104.82  4998.5  105.32
 5007.28106.5782  5018.2  106.14  5042.4  106.93  5108.7  106.76  5142.2  107.39
  5195.1  106.68  5199.1  106.57  5229.3  109.11  5237.1  108.84  5279.5  110.72
  5289.6  110.56  5309.7  112.13    5329  112.25    5342  112.33  5359.5  113.33
#Mann= 6 ,-1 , 0
  4741.2     .17       0  4806.9     .15       0  4987.8     .03       0
 5007.28     .15       0  5195.1     .17       0    5329     .11       0
Bank Sta=4987.8,5007.28
XS Rating Curve= 0 ,0
Exp/Cntr=0.3,0.1

Type RM Length L Ch R = 1 ,59000   ,500,500,500
BEGIN DESCRIPTION:
WOODSONS GULLY 116.0
END DESCRIPTION:
XS GIS Cut Line= 3
      3857467.82     10051811.08      3857201.14      10051872.2
      3856823.92     10051933.09
#Sta/Elev= 30
  4726.4  112.34  4745.3   112.3  4750.4  113.24  4757.2  112.51  4781.6  113.76
  4793.3  113.11  4798.4  113.62  4808.4  112.45    4829  111.53  4879.1  110.71
  4900.8  109.77  4921.3  107.93  4927.1  108.59  4952.1  107.19  4962.3  107.58
 4984.36106.5241  4997.1  106.03  4997.4  105.53  5033.7  106.56  5074.5  106.41
  5165.4  106.58  5226.2  108.67  5246.4   108.7  5256.6  109.68  5272.5     110
    5287  110.58  5327.5  109.53  5347.7  110.34  5376.1  112.54  5382.1  112.61
#Mann= 7 ,-1 , 0
  4726.4    .125       0  4781.6     .11       0 4984.36     .03       0
  5033.7     .11       0  5074.5     .15       0  5272.5     .17       0
  5376.1     .11       0
Bank Sta=4984.36,5033.7
XS Rating Curve= 0 ,0
Exp/Cntr=0.3,0.1

Type RM Length L Ch R = 1 ,58500   ,531,531,531
BEGIN DESCRIPTION:
WOODSONS GULLY 115.0
END DESCRIPTION:
XS GIS Cut Line= 3
      3857629.12     10051527.43      3857313.72      10051389.1
      3857051.27     10051332.45
#Sta/Elev= 30
  4655.6  113.48  4678.6  113.04  4689.7  112.29  4754.2  110.79  4759.6  111.14
  4820.8  108.69  4842.6  108.82  4875.4  107.91  4887.4  108.04  4910.8  107.01
  4957.5   106.2  4980.9  106.44    4993  105.32  4993.3  104.82  4996.8  104.82
    4997  105.32  5012.7  106.36  5026.5  106.09  5106.2  106.45  5128.8  106.11
  5160.6  107.36  5169.7  108.38  5179.9   108.2  5199.6   109.2  5204.7  108.69
  5210.6  109.68  5231.1     110  5241.3  111.92  5248.9  111.76  5268.5  112.36
#Mann= 3 , 0 , 0
  4655.6     .11       0  4980.9     .03       0  5012.7     .11       0
Bank Sta=4980.9,5012.7
XS Rating Curve= 0 ,0
Exp/Cntr=0.3,0.1

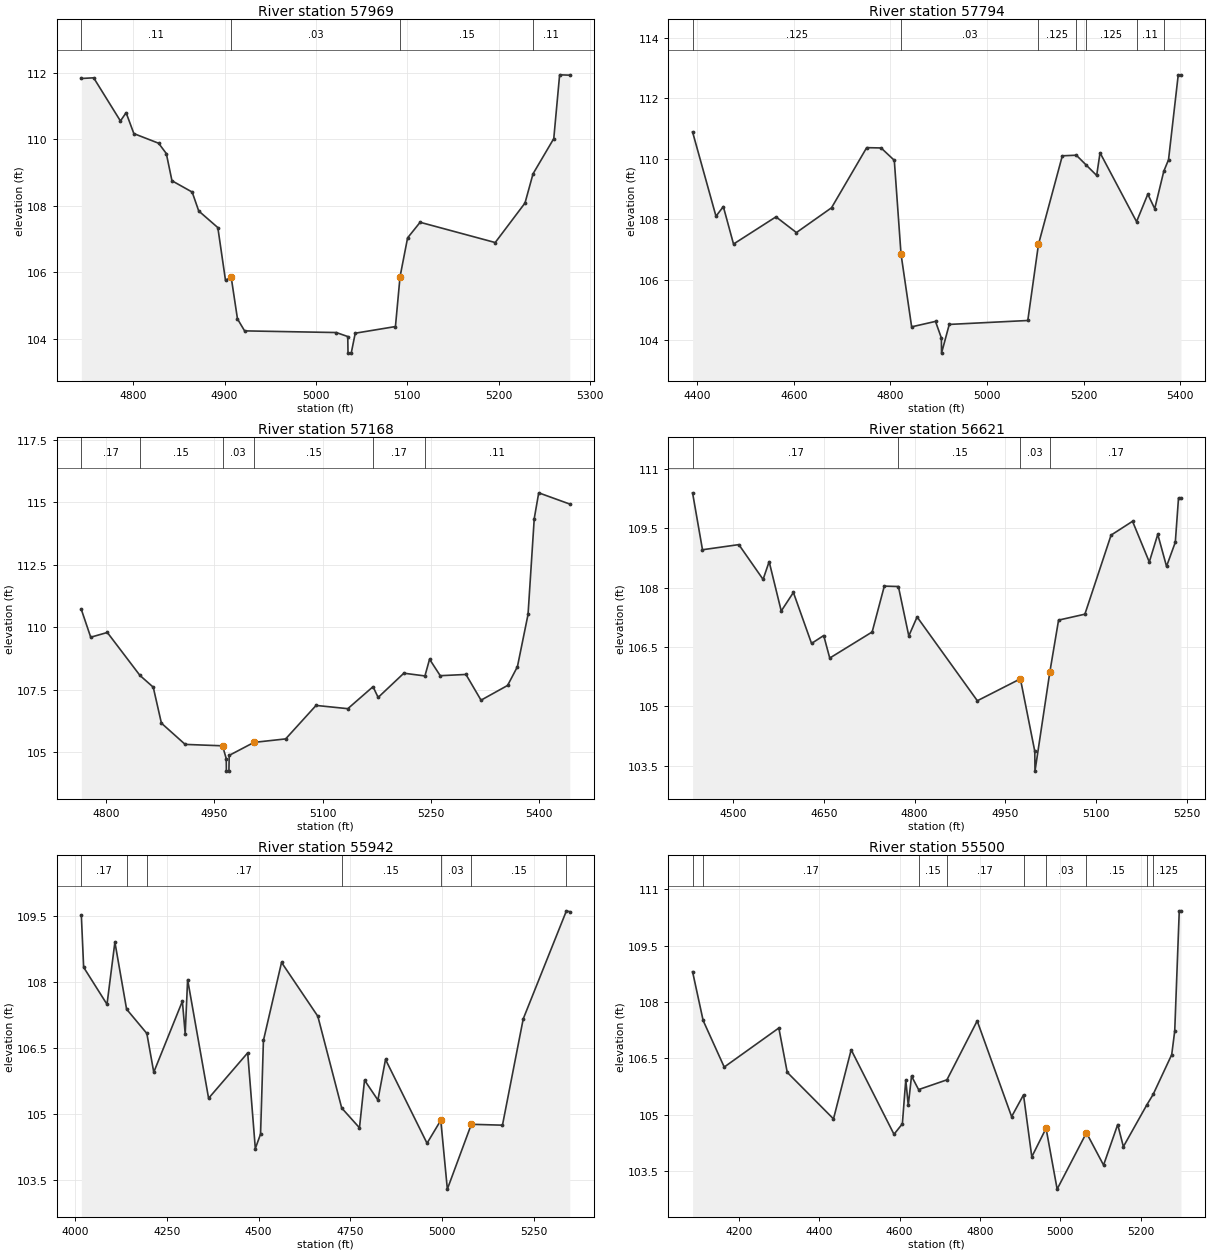
Type RM Length L Ch R = 1 ,57969   ,175,175,175
BEGIN DESCRIPTION:
WOODSONS GULLY 114.0
END DESCRIPTION:
XS GIS Cut Line= 3
      3857695.62     10051052.73      3857392.14     10050829.81
      3857241.14     10050783.14
#Sta/Elev= 30
  4743.3  111.83  4756.8  111.85  4786.1  110.55  4792.3   110.8  4800.8  110.17
  4827.9  109.88  4836.3  109.57  4842.5  108.75  4864.6  108.41  4871.8  107.84
  4892.7  107.34  4901.1  105.75  4907.3  105.85  4914.2  104.59    4922  104.23
  5022.3  104.18  5034.9  104.06  5035.2  103.56  5038.7  103.56  5043.1  104.16
  5087.1  104.36 5092.13105.8609  5100.4  107.03  5114.1   107.5  5196.3  106.89
  5228.9  108.08  5237.7  108.96  5260.4  110.02  5266.8  111.94  5277.9  111.93
#Mann= 4 ,-1 , 0
  4743.3     .11       0  4907.3     .03       0 5092.13     .15       0
  5237.7     .11       0
Bank Sta=4907.3,5092.13
XS Rating Curve= 0 ,0
Exp/Cntr=0.3,0.1

Type RM Length L Ch R = 1 ,57794   ,626,626,626
BEGIN DESCRIPTION:
WOODSONS GULLY 113.0
END DESCRIPTION:
XS GIS Cut Line= 4
        3858107.     10051130.07      3857782.07       10050922.
      3857612.28     10050777.03      3857303.98     10050518.73
#Sta/Elev= 30
  4390.5  110.89    4439   108.1  4454.2  108.42  4475.3  107.18  4563.2  108.08
  4605.5  107.56  4678.2  108.38    4751  110.37  4780.9  110.36  4808.2  109.95
  4822.1  106.85  4844.1  104.44  4893.5  104.62  4905.7  104.07    4906  103.57
    4922  104.52  5084.6  104.65  5106.7  107.17  5156.1   110.1  5185.1  110.12
  5205.8  109.79  5227.2  109.45  5234.2   110.2  5309.8  107.92  5333.1  108.83
  5347.4  108.35  5366.2  109.59    5376  109.97  5396.1  112.78  5401.8  112.78
#Mann= 7 ,-1 , 0
  4390.5    .125       0  4822.1     .03       0  5106.7    .125       0
  5185.1     .11       0  5205.8    .125       0  5309.8     .11       0
  5366.2    .125       0
Bank Sta=4822.1,5106.7
XS Rating Curve= 0 ,0
Exp/Cntr=0.3,0.1

Type RM Length L Ch R = 1 ,57168   ,547,547,547
BEGIN DESCRIPTION:
WOODSONS GULLY 112.0
END DESCRIPTION:
XS GIS Cut Line= 3
      3858186.42      10050571.9      3858101.12     10050385.28
      3857717.81     10050111.05
#Sta/Elev= 30
  4765.8  110.71  4778.8   109.6  4801.8  109.79    4847  108.07  4865.4   107.6
  4876.7  106.16  4909.6  105.31  4961.4105.2536  4966.5  104.74  4966.7  104.24
  4970.2  104.24  4970.6  104.87  5004.9  105.39  5048.8  105.53  5090.9  106.87
  5134.9  106.74  5169.8  107.62  5176.9  107.19  5212.5  108.16  5241.7  108.05
  5248.1  108.72  5262.9  108.06  5298.5  108.11  5319.4  107.08  5356.2  107.67
  5369.8  108.42  5384.5  110.51  5393.1  114.35  5399.3  115.38  5442.3  114.93
#Mann= 6 ,-1 , 0
  4765.8     .17       0    4847     .15       0  4961.4     .03       0
  5004.9     .15       0  5169.8     .17       0  5241.7     .11       0
Bank Sta=4961.4,5004.9
XS Rating Curve= 0 ,0
Exp/Cntr=0.3,0.1

Type RM Length L Ch R = 1 ,56621   ,679,679,679
BEGIN DESCRIPTION:
WOODSONS GULLY 111.0
END DESCRIPTION:
XS GIS Cut Line= 4
      3858528.99     10050507.41      3858507.77     10050175.67
      3858325.95     10050025.91      3858136.35     10049879.54
#Sta/Elev= 30
  4432.8   110.4  4449.2  108.96  4509.3  109.09  4549.4  108.21  4559.4  108.66
  4579.4  107.41  4599.5  107.88  4629.5  106.59  4649.6  106.79  4659.6  106.22
  4729.7  106.88  4749.8  108.04  4773.1  108.03  4790.3  106.78    4804  107.26
  4903.6  105.14  4974.8105.6951  4998.6  103.86  4998.9  103.36  5023.6  105.88
  5037.9  107.18  5081.4  107.33  5124.7  109.33  5160.2  109.68  5187.9  108.65
  5201.9  109.35  5216.4  108.54  5230.9  109.15  5236.2  110.27  5240.3  110.27
#Mann= 4 ,-1 , 0
  4432.8     .17       0  4773.1     .15       0  4974.8     .03       0
  5023.6     .17       0
Bank Sta=4974.8,5023.6
XS Rating Curve= 0 ,0
Exp/Cntr=0.3,0.1

Type RM Length L Ch R = 1 ,55942   ,442,442,442
BEGIN DESCRIPTION:
WOODSONS GULLY 110.0
END DESCRIPTION:
XS GIS Cut Line= 3
      3859146.76     10050251.02      3858515.19      10049501.6
      3858267.78     10049251.58
#Sta/Elev= 30
  4016.6  109.51  4022.9  108.33  4086.6  107.49  4108.1   108.9    4140  107.38
  4195.2  106.83  4214.1  105.95  4292.1  107.56  4299.8  106.82  4306.4  108.05
  4363.6  105.36  4470.2  106.39    4491  104.22  4505.3  104.55  4513.1  106.67
  4562.5  108.44  4661.4  107.22  4726.5  105.14    4775  104.69  4788.8  105.77
  4825.2  105.32    4846  106.24  4959.2  104.34  4996.7  104.86  5014.6   103.3
    5080  104.77  5164.9  104.75  5221.5  107.16  5339.3  109.61  5348.4  109.59
#Mann= 7 ,-1 , 0
  4016.6     .17       0    4140     .11       0  4195.2     .17       0
  4726.5     .15       0  4996.7     .03       0    5080     .15       0
  5339.3     .17       0
Bank Sta=4996.7,5080
XS Rating Curve= 0 ,0
Exp/Cntr=0.3,0.1

Type RM Length L Ch R = 1 ,55500   ,465,465,465
BEGIN DESCRIPTION:
WOODSONS GULLY 109.0
END DESCRIPTION:
XS GIS Cut Line= 3
      3859527.96     10049701.44      3858788.87     10049161.86
      3858566.44     10048959.96
#Sta/Elev= 30
  4084.9  108.81  4111.2  107.51  4163.7  106.27  4299.6  107.31  4320.5  106.13
  4435.6  104.89  4479.6  106.73  4586.2  104.48    4607  104.76  4615.5  105.93
  4621.7  105.25  4629.8  106.03  4647.4  105.67  4717.9  105.93  4793.2   107.5
  4878.9  104.95  4908.5  105.53  4929.1  103.88  4964.6  104.64  4992.2  103.02
  5065.1  104.52  5107.7  103.66  5142.9  104.74    5157  104.15  5215.2  105.26
    5231  105.54  5277.3   106.6  5284.8  107.23  5296.1  110.43  5300.4  110.43
#Mann= 9 ,-1 , 0
  4084.9     .15       0  4111.2     .17       0  4647.4     .15       0
  4717.9     .17       0  4908.5     .15       0  4964.6     .03       0
  5065.1     .15       0  5215.2     .11       0    5231    .125       0
Bank Sta=4964.6,5065.1
XS Rating Curve= 0 ,0
Exp/Cntr=0.3,0.1

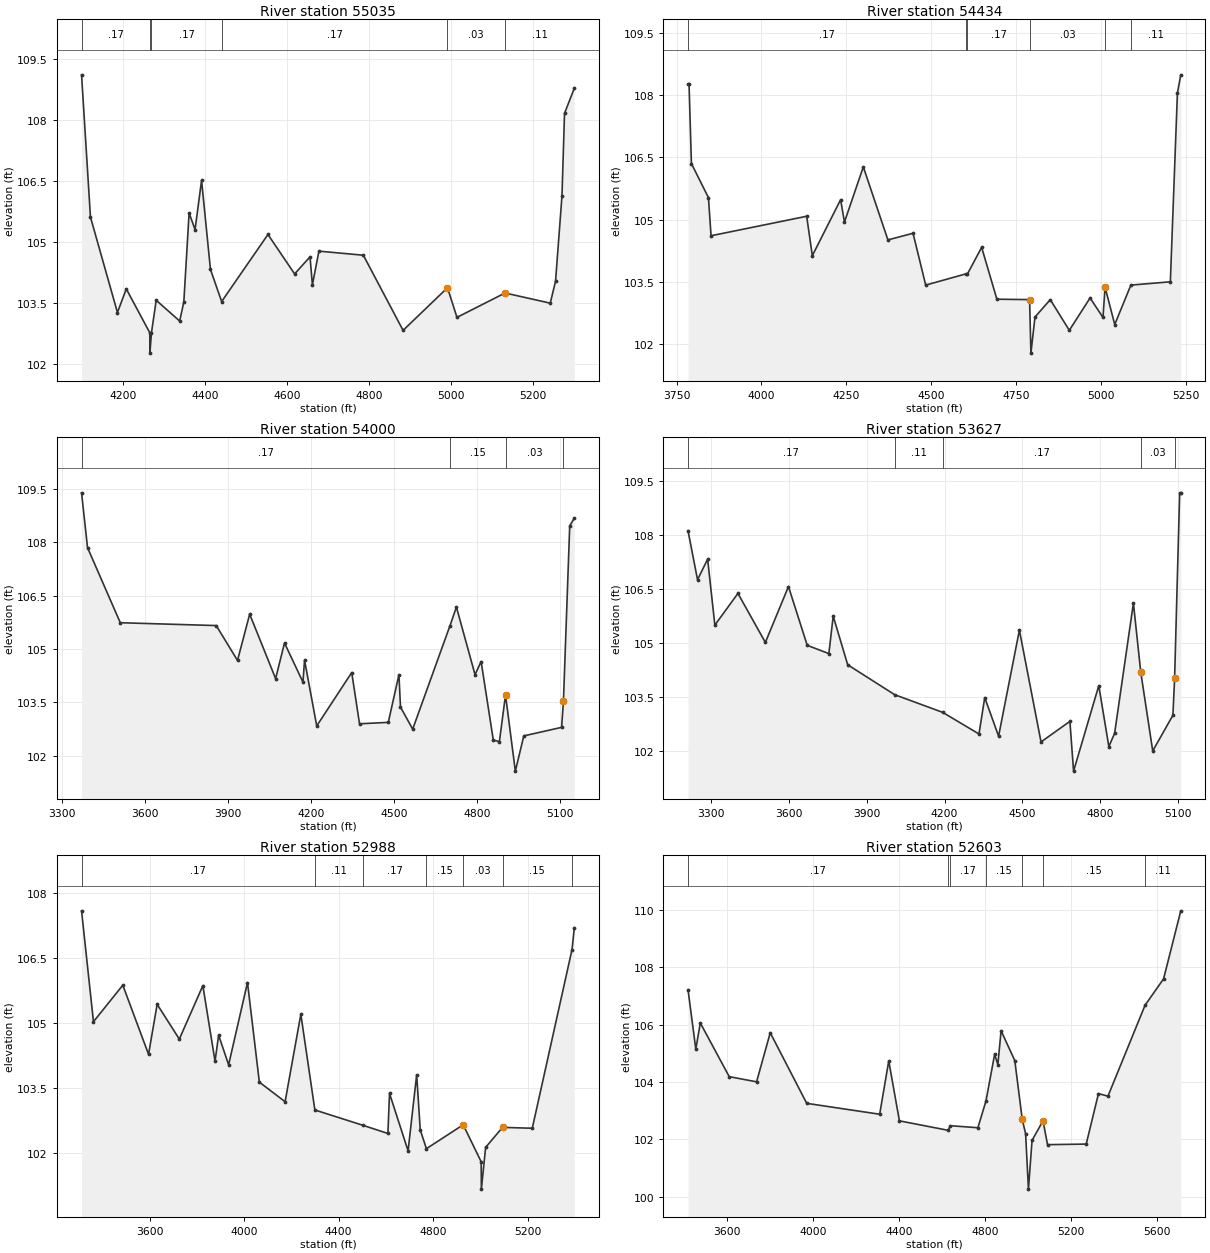
Type RM Length L Ch R = 1 ,55035   ,601,601,601
BEGIN DESCRIPTION:
WOODSONS GULLY 108.0
END DESCRIPTION:
XS GIS Cut Line= 3
      3859946.74      10049320.3      3859157.55     10048877.47
      3859007.52     10048620.39
#Sta/Elev= 30
  4098.1  109.11  4119.8  105.61  4185.7  103.26  4207.3  103.84  4264.7  102.76
  4264.9  102.26  4268.7  102.76  4280.3  103.56  4337.6  103.05  4347.7  103.52
  4360.6  105.71  4375.1   105.3    4391  106.51  4412.7  104.32    4440  103.53
    4553  105.18  4618.1  104.21  4655.7  104.63  4661.5  103.94  4677.4  104.77
  4785.8  104.67  4882.8  102.82  4991.2  103.87  5014.3  103.14  5131.7  103.74
    5242  103.49  5254.9  104.03  5270.6  106.13  5276.8  108.16  5300.7  108.78
#Mann= 6 ,-1 , 0
  4098.1     .17       0  4264.7     .12       0  4268.7     .17       0
    4440     .17       0  4991.2     .03       0  5131.7     .11       0
Bank Sta=4991.2,5131.7
XS Rating Curve= 0 ,0
Exp/Cntr=0.3,0.1

Type RM Length L Ch R = 1 ,54434   ,434,434,434
BEGIN DESCRIPTION:
WOODSONS GULLY 107.0
END DESCRIPTION:
XS GIS Cut Line= 3
      3860718.24     10049072.38      3859632.13     10048519.86
      3859455.46     10048369.59
#Sta/Elev= 30
  3783.9  108.27  3786.9  108.27  3793.9  106.35    3844  105.53  3851.7  104.61
  4133.2  105.08  4149.8  104.13  4233.1  105.48  4244.4  104.94  4299.9  106.27
  4372.3  104.51  4446.3  104.67  4483.5  103.42  4601.6  103.69  4606.5  103.69
  4648.2  104.33  4693.1  103.08  4789.4  103.07  4793.2  101.78  4805.3  102.65
  4850.2  103.07  4906.3  102.33  4967.4  103.11  5005.4  102.64  5011.5  103.37
    5040  102.47  5087.5  103.42  5203.7   103.5  5224.5  108.05  5234.4  108.49
#Mann= 6 ,-1 , 0
  3783.9     .17       0  4601.6     .15       0  4606.5     .17       0
  4789.4     .03       0  5011.5     .15       0  5087.5     .11       0
Bank Sta=4789.4,5011.5
XS Rating Curve= 0 ,0
Exp/Cntr=0.3,0.1

Type RM Length L Ch R = 1 ,54000   ,373,373,373
BEGIN DESCRIPTION:
WOODSONS GULLY 106.0
END DESCRIPTION:
XS GIS Cut Line= 3
      3861347.01     10048941.19      3859905.62     10048182.22
      3859815.44     10048059.36
#Sta/Elev= 30
    3371  109.39  3392.6  107.85    3511  105.74  3857.9  105.66  3934.8  104.68
  3978.8  105.98  4072.6  104.17  4104.7  105.17  4171.5  104.07  4177.1  104.69
  4221.2  102.84  4347.7  104.34  4375.9   102.9  4479.9  102.94  4518.4  104.28
    4524  103.37  4568.1  102.75  4703.1  105.66  4726.2  106.18  4793.5  104.28
  4815.5  104.65  4859.6  102.44  4881.6   102.4  4903.7  103.71  4939.2  101.57
  4969.8  102.56  5106.5   102.8  5113.1  103.53  5135.8  108.46  5152.4  108.68
#Mann= 4 ,-1 , 0
    3371     .17       0  4703.1     .15       0  4903.7     .03       0
  5113.1    .125       0
Bank Sta=4903.7,5113.1
XS Rating Curve= 0 ,0
Exp/Cntr=0.3,0.1

Type RM Length L Ch R = 1 ,53627   ,639,639,639
BEGIN DESCRIPTION:
WOODSONS GULLY 105.0
END DESCRIPTION:
XS GIS Cut Line= 3
      3861778.07     10048741.38      3860184.21       10047936.
      3860096.34     10047859.19
#Sta/Elev= 30
  3209.7  108.11  3246.4  106.75  3285.4  107.32  3313.3  105.49  3402.4  106.37
  3508.3  105.01  3597.5  106.56  3669.9  104.93  3753.5   104.7  3770.2  105.74
  3826.2  104.39  4007.7  103.56    4193  103.07  4333.1  102.47  4355.3  103.48
  4408.8  102.41  4489.1  105.35  4572.6  102.25  4684.1  102.82  4698.3  101.44
  4795.6  103.81  4834.5  102.12  4856.8  102.49  4929.3   106.1  4957.8  104.18
  5003.9     102  5081.8  102.99  5088.4  104.01  5107.9  109.16  5112.2  109.16
#Mann= 5 ,-1 , 0
  3209.7     .17       0  4007.7     .11       0    4193     .17       0
  4957.8     .03       0  5088.4     .15       0
Bank Sta=4957.8,5088.4
XS Rating Curve= 0 ,0
Exp/Cntr=0.3,0.1

Type RM Length L Ch R = 1 ,52988   ,385,385,385
BEGIN DESCRIPTION:
WOODSONS GULLY 104.0
END DESCRIPTION:
XS GIS Cut Line= 3
      3861988.91     10048611.01      3860567.46     10047698.16
      3860217.89     10047511.09
#Sta/Elev= 30
  3311.6  107.58    3362  105.03  3486.2  105.87  3595.2  104.28  3631.6  105.43
  3725.4  104.63  3825.1  105.86  3876.6  104.12  3891.8  104.72  3934.1  104.04
    4014  105.93  4064.2  103.64  4173.2  103.19  4239.8   105.2  4299.2     103
  4501.3  102.65  4608.3  102.46  4615.2  103.38  4693.8  102.06  4730.1  103.81
  4745.3  102.54  4771.4  102.11    4927  102.66  5003.1  101.81    5004  101.18
    5022  102.14  5093.5   102.6  5219.5  102.58  5387.7  106.69  5397.4  107.19
#Mann= 7 ,-1 , 0
  3311.6     .17       0  4299.2     .11       0  4501.3     .17       0
  4771.4     .15       0    4927     .03       0  5093.5     .15       0
  5387.7    .125       0
Bank Sta=4927,5093.5
XS Rating Curve= 0 ,0
Exp/Cntr=0.3,0.1

Type RM Length L Ch R = 1 ,52603   ,516,516,516
BEGIN DESCRIPTION:
WOODSONS GULLY 103.0
END DESCRIPTION:
XS GIS Cut Line= 3
      3861989.93     10048600.07      3861195.88     10047785.29
      3860236.47      10047141.5
#Sta/Elev= 30
  3418.3  107.22  3454.5  105.15  3475.6  106.06  3610.1  104.19  3737.4  104.01
  3800.9  105.72  3970.7  103.26  4310.2  102.88  4352.4  104.74    4402  102.65
  4628.8  102.32  4639.5  102.48  4767.2  102.41  4805.1  103.35  4845.2  104.97
  4860.2  104.61  4875.2  105.79    4939  104.75  4973.5102.7076  4989.3   102.2
  5002.5  100.27  5019.3  101.97  5070.3  102.65  5091.3  101.82  5271.3  101.84
  5328.4   103.6  5372.5  103.51  5545.2  106.68  5631.4   107.6  5711.4  109.97
#Mann= 7 ,-1 , 0
  3418.3     .17       0  4628.8     .11       0  4639.5     .17       0
  4805.1     .15       0  4973.5     .03       0  5070.3     .15       0
  5545.2     .11       0
Bank Sta=4973.5,5070.3
XS Rating Curve= 0 ,0
Exp/Cntr=0.3,0.1

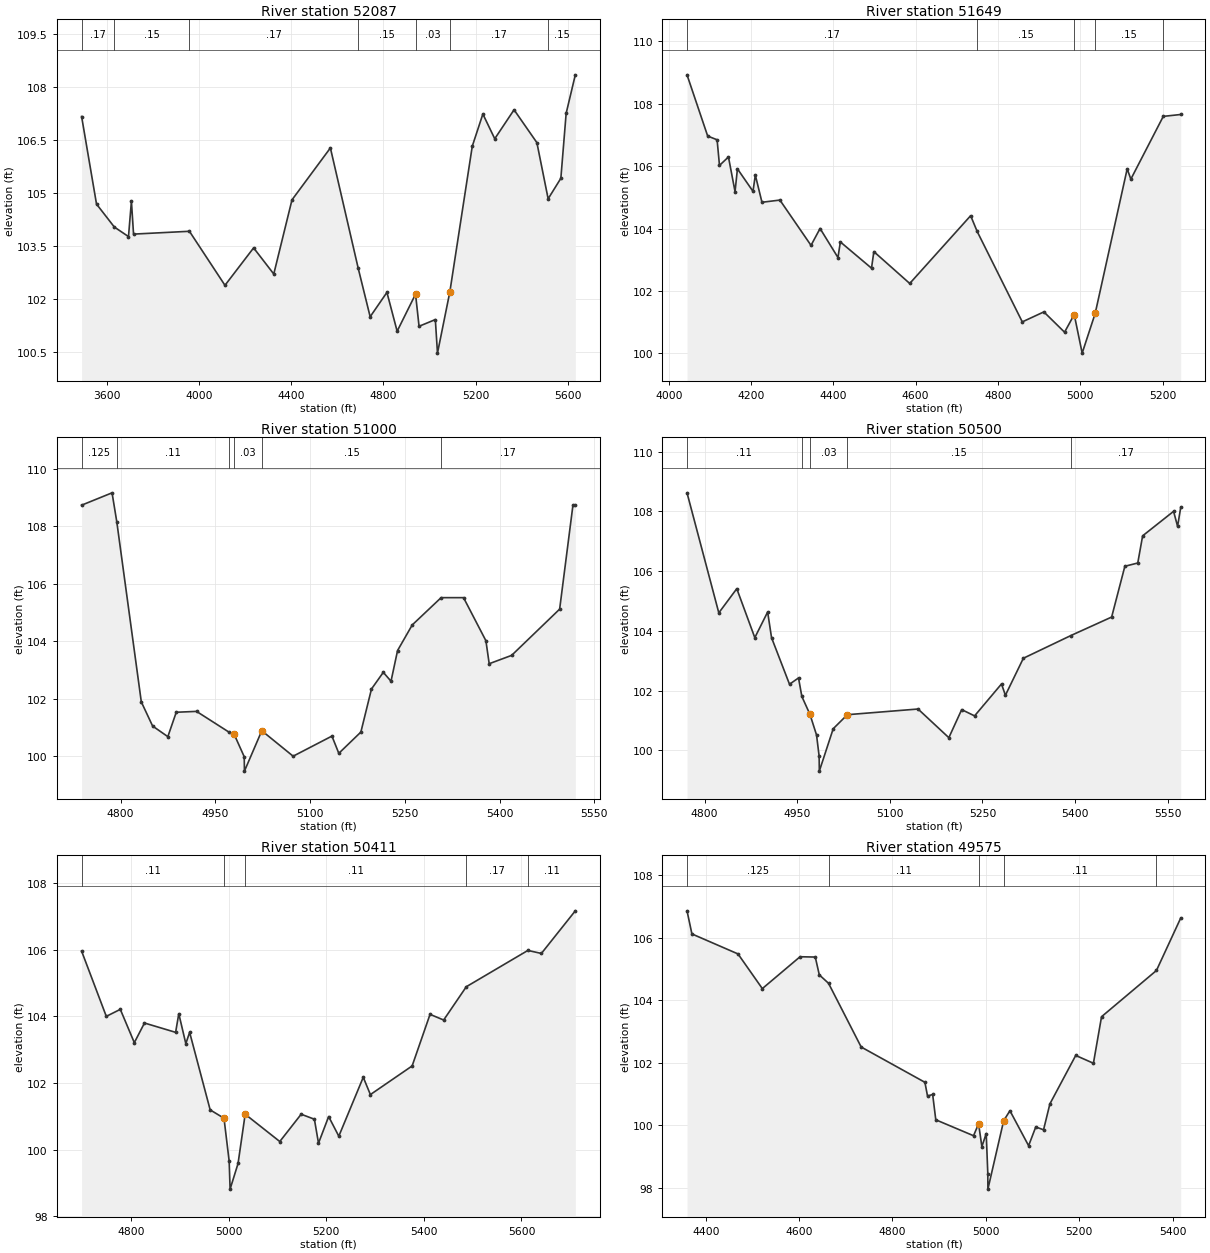
Type RM Length L Ch R = 1 ,52087   ,438,438,438
BEGIN DESCRIPTION:
WOODSONS GULLY 102.0
END DESCRIPTION:
XS GIS Cut Line= 3
      3862528.91     10048130.02      3861261.47     10047315.91
      3860996.38     10046739.75
#Sta/Elev= 30
  3491.9  107.16  3556.6  104.68  3633.8  104.03  3695.2  103.76  3707.9  104.76
  3717.1  103.83  3959.4  103.91  4113.5  102.38  4237.7  103.44  4325.1   102.7
  4404.1   104.8  4570.6  106.27  4691.3  102.86    4743  101.49  4815.7  102.18
    4860  101.08  4939.8  102.13    4955  101.22  5025.6  101.41  5034.9  100.46
  5088.4  102.19  5185.8  106.32  5231.7  107.23  5283.2  106.53  5366.9  107.35
  5465.9  106.42  5514.7  104.83  5569.8  105.41  5592.8  107.25  5632.5  108.34
#Mann= 7 ,-1 , 0
  3491.9     .17       0  3633.8     .15       0  3959.4     .17       0
  4691.3     .15       0  4939.8     .03       0  5088.4     .17       0
  5514.7     .15       0
Bank Sta=4939.8,5088.4
XS Rating Curve= 0 ,0
Exp/Cntr=0.3,0.1

Type RM Length L Ch R = 1 ,51649   ,649,649,649
BEGIN DESCRIPTION:
WOODSONS GULLY 101.0
END DESCRIPTION:
XS GIS Cut Line= 3
      3862441.88      10047524.1      3861607.39     10047065.56
      3861467.87      10046861.1
#Sta/Elev= 30
  4044.5  108.92  4094.7  106.96  4117.6  106.84  4123.4  106.02  4145.2  106.29
  4161.2  105.18    4167  105.91  4204.8  105.19  4210.5  105.71  4226.6  104.84
  4270.2  104.91  4345.8  103.46  4367.8     104  4411.3  103.07  4417.1  103.57
  4492.8  102.73  4498.5  103.26  4585.7  102.24  4733.7  104.41  4749.4  103.91
  4859.2  101.01  4911.6  101.33  4961.9  100.68  4985.4101.2452  5004.7  100.01
  5036.3  101.28  5114.1  105.91    5123  105.58  5201.8  107.59  5244.2  107.65
#Mann= 5 ,-1 , 0
  4044.5     .17       0  4749.4     .15       0  4985.4     .03       0
  5036.3     .15       0  5201.8     .17       0
Bank Sta=4985.4,5036.3
XS Rating Curve= 0 ,0
Exp/Cntr=0.3,0.1

Type RM Length L Ch R = 1 ,51000   ,500,500,500
BEGIN DESCRIPTION:
WOODSONS GULLY 100.0
END DESCRIPTION:
XS GIS Cut Line= 3
      3862117.84     10046561.07      3861868.73      10046481.2
       3861365.5      10046611.4
#Sta/Elev= 30
  4738.4  108.74  4786.6  109.17  4794.1  108.16  4832.9  101.89  4850.8  101.05
  4874.9  100.68  4888.2  101.53  4920.3  101.56  4971.5  100.84  4979.3  100.79
  4995.8   99.98  4996.1   99.48  5023.6100.8862  5073.2     100  5134.6   100.7
  5145.5   100.1  5180.4  100.84  5197.2  102.34  5215.9  102.92  5228.1  102.61
  5238.5  103.68  5261.7  104.57  5307.4  105.52  5342.9  105.52  5378.3  104.02
  5383.5  103.22    5419  103.51    5495  105.12    5516  108.73  5519.8  108.73
#Mann= 6 ,-1 , 0
  4738.4    .125       0  4794.1     .11       0  4971.5     .15       0
  4979.3     .03       0  5023.6     .15       0  5307.4     .17       0
Bank Sta=4979.3,5023.6
XS Rating Curve= 0 ,0
Exp/Cntr=0.3,0.1

Type RM Length L Ch R = 1 ,50500   ,89,89,89
BEGIN DESCRIPTION:
WOODSONS GULLY 99.0
END DESCRIPTION:
XS GIS Cut Line= 3
      3862221.55     10046230.17      3862084.24      10046047.4
      3861628.61     10045703.09
#Sta/Elev= 30
  4771.4  108.62  4822.9   104.6    4852  105.41  4881.2  103.77    4902  104.63
  4908.3  103.77  4937.4  102.21    4952  102.42  4957.4   101.8 4970.51101.2018
  4981.2  100.51  4985.4    99.8  4985.7    99.3  5008.2  100.72  5031.1  101.19
  5145.6  101.38  5195.5  100.42  5216.3  101.36  5237.2  101.15  5280.8  102.22
  5287.1  101.84  5316.2  103.08  5393.1  103.84  5459.2  104.46  5480.6  106.16
  5501.5  106.27  5509.4  107.18  5559.5     108    5566   107.5  5571.1  108.13
#Mann= 5 ,-1 , 0
  4771.4     .11       0  4957.4     .15       0 4970.51     .03       0
  5031.1     .15       0  5393.1     .17       0
Bank Sta=4970.51,5031.1
XS Rating Curve= 0 ,0
Exp/Cntr=0.3,0.1

Type RM Length L Ch R = 1 ,50411   ,836,836,836
BEGIN DESCRIPTION:
WOODSONS GULLY 98.0
END DESCRIPTION:
XS GIS Cut Line= 3
      3862371.23     10046168.78      3862137.77     10045976.67
      3861569.17     10045553.05
#Sta/Elev= 30
  4698.9  105.96  4749.5     104  4778.2  104.21  4806.9  103.21  4827.7   103.8
  4891.5  103.52    4898  104.08  4912.4  103.18  4920.2  103.52  4962.3  101.19
  4990.6  100.94  5001.2   99.65  5003.1   98.81  5019.4   99.58    5034  101.06
  5104.9  100.24  5148.7  101.06  5175.8  100.91  5184.2  100.19    5205  100.99
  5225.8   100.4  5275.9  102.17  5290.5  101.65    5376  102.51  5412.7  104.06
  5440.6  103.89    5487  104.89  5613.1  105.98  5640.8  105.89  5710.3  107.17
#Mann= 5 ,-1 , 0
  4698.9     .11       0  4990.6     .03       0    5034     .11       0
    5487     .17       0  5613.1     .11       0
Bank Sta=4990.6,5034
XS Rating Curve= 0 ,0
Exp/Cntr=0.3,0.1

Type RM Length L Ch R = 1 ,49575   ,527,527,527
BEGIN DESCRIPTION:
WOODSONS GULLY 97.0
END DESCRIPTION:
XS GIS Cut Line= 3
      3863058.58     10046172.31      3862799.71     10045586.15
        3862654.     10045195.84
#Sta/Elev= 30
    4360  106.86  4370.5  106.12  4469.2  105.48  4521.3  104.37  4602.1  105.39
  4634.7  105.38  4643.3  104.81  4663.1  104.54    4733   102.5  4869.5  101.37
  4875.1  100.93  4886.1  100.98  4892.8  100.17  4973.6   99.66  4984.5  100.04
  4991.5   99.31  5000.8   99.73  5004.2   98.45  5004.4   97.95  5038.2  100.14
  5051.6  100.46  5091.6   99.34  5106.9   99.94  5123.6   99.85  5137.2  100.68
  5192.5  102.23  5230.4  101.98  5247.8  103.47  5365.4  104.95  5417.4  106.63
#Mann= 5 ,-1 , 0
    4360    .125       0  4663.1     .11       0  4984.5     .03       0
  5038.2     .11       0  5365.4     .17       0
Bank Sta=4984.5,5038.2
XS Rating Curve= 0 ,0
Exp/Cntr=0.3,0.1

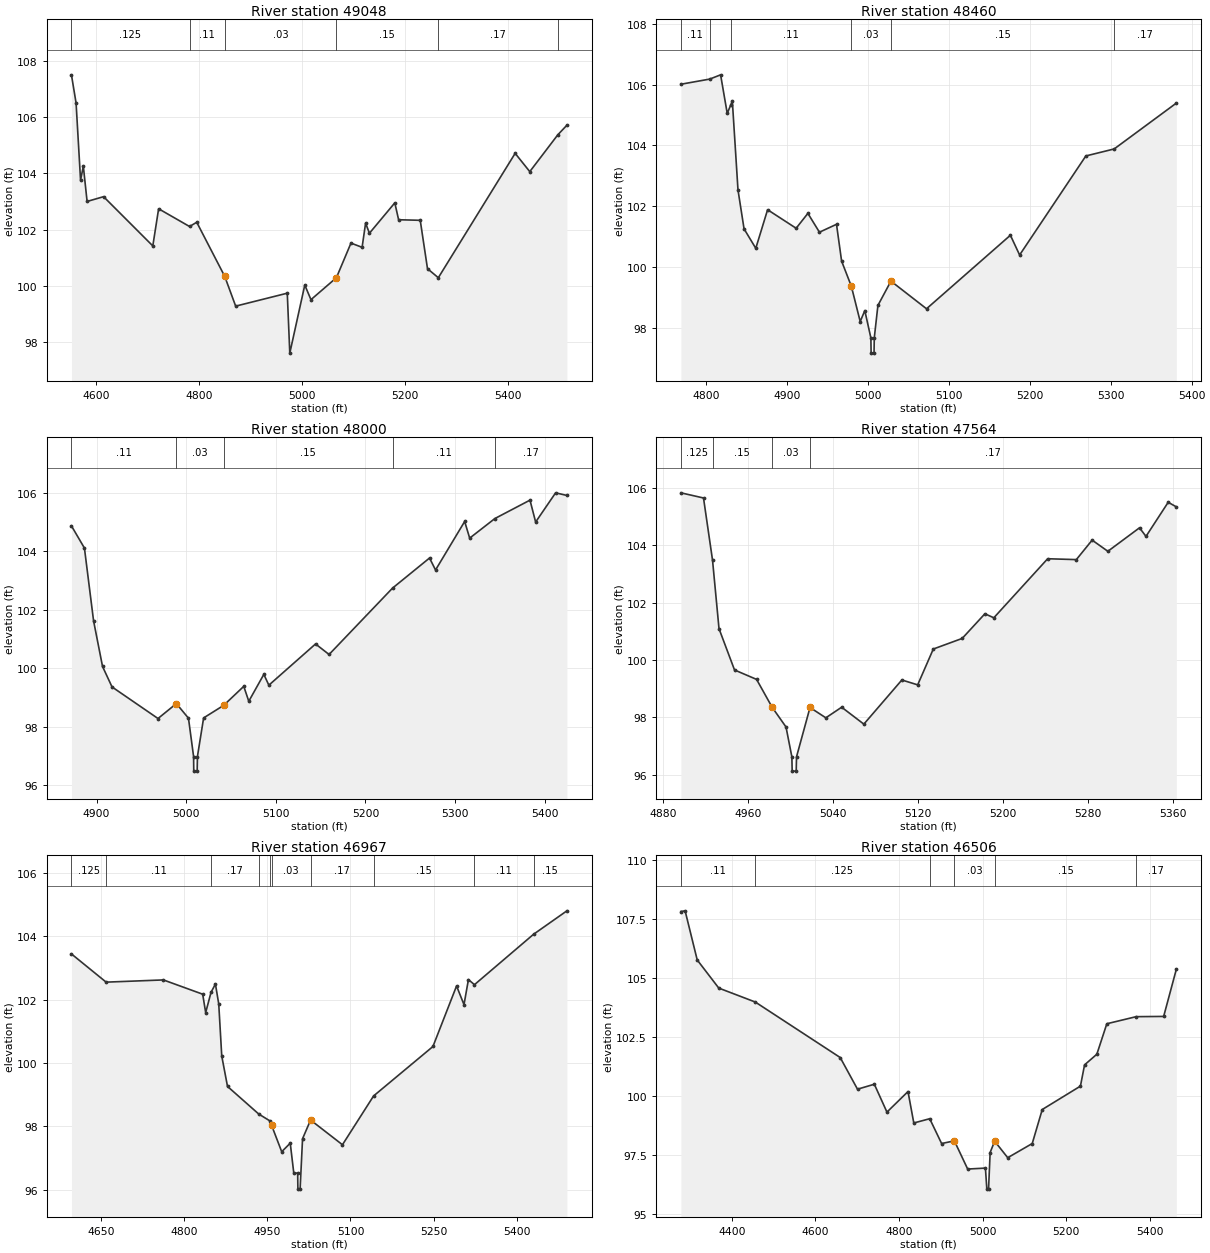
Type RM Length L Ch R = 1 ,49048   ,588,588,588
BEGIN DESCRIPTION:
WOODSONS GULLY 96.0
END DESCRIPTION:
XS GIS Cut Line= 3
      3863450.31     10045909.48      3863290.17     10045485.02
      3862946.27     10045110.53
#Sta/Elev= 30
  4551.6   107.5  4560.6   106.5  4569.3  103.76  4574.7  104.25    4582     103
    4614  103.17  4709.6  101.42  4720.9  102.74  4780.9  102.11  4794.9  102.26
  4849.2  100.34  4870.5   99.28  4970.7   99.74  4975.6   97.61  5004.7  100.03
  5016.7   99.51  5066.1  100.29  5094.4  101.52    5116  101.37  5122.8  102.23
  5130.2  101.87  5179.5  102.95  5186.9  102.35  5228.9  102.33    5243  100.61
    5264  100.29  5413.2  104.71  5441.6  104.06  5496.1  105.37  5513.7  105.71
#Mann= 6 ,-1 , 0
  4551.6    .125       0  4780.9     .11       0  4849.2     .03       0
  5066.1     .15       0    5264     .17       0  5496.1     .11       0
Bank Sta=4849.2,5066.1
XS Rating Curve= 0 ,0
Exp/Cntr=0.3,0.1

Type RM Length L Ch R = 1 ,48460   ,460,460,460
BEGIN DESCRIPTION:
WOODSONS GULLY 95.0
END DESCRIPTION:
XS GIS Cut Line= 3
      3863913.86     10045614.36      3863752.41     10045490.66
      3863558.24     10045130.45
#Sta/Elev= 30
  4768.5  106.01  4804.2  106.18  4817.6  106.32  4825.8  105.05    4830  105.32
  4832.1  105.46  4839.1  102.53  4846.6  101.25  4861.1  100.61  4875.7  101.88
    4911  101.27  4925.5  101.76  4939.8  101.14  4960.9   101.4  4967.2  100.19
 4979.2699.36064  4990.2    98.2  4995.9   98.56  5003.4   97.66  5003.7   97.16
  5007.3   97.16  5007.6   97.66  5012.1   98.73  5028.2   99.53  5072.2   98.62
  5175.9  101.04  5187.3  100.39  5269.2  103.65  5304.2  103.88  5381.1  105.39
#Mann= 6 ,-1 , 0
  4768.5     .11       0  4804.2    .125       0    4830     .11       0
 4979.26     .03       0  5028.2     .15       0  5304.2     .17       0
Bank Sta=4979.26,5028.2
XS Rating Curve= 0 ,0
Exp/Cntr=0.3,0.1

Type RM Length L Ch R = 1 ,48000   ,436,436,436
BEGIN DESCRIPTION:
WOODSONS GULLY 94.0
END DESCRIPTION:
XS GIS Cut Line= 3
       3864181.7     10045515.17      3864152.98     10045390.33
      3863964.22     10045009.77
#Sta/Elev= 30
  4871.9  104.87  4886.4  104.11  4896.6  101.62  4906.6  100.06  4917.2   99.36
  4968.5   98.28    4989   98.79  5002.5   98.29  5008.2   96.98  5008.4   96.48
  5012.2   96.48  5012.5   96.98  5019.4    98.3  5041.8   98.73  5064.2   99.38
  5069.8   98.87  5086.6   99.79  5092.2   99.42  5144.3  100.83  5159.4  100.47
  5230.2  102.74  5271.5  103.77  5278.2  103.36  5310.7  105.02  5316.3  104.45
  5344.4  105.12  5383.6  105.75  5389.9     105  5412.2     106  5424.8  105.91
#Mann= 5 ,-1 , 0
  4871.9     .11       0    4989     .03       0  5041.8     .15       0
  5230.2     .11       0  5344.4     .17       0
Bank Sta=4989,5041.8
XS Rating Curve= 0 ,0
Exp/Cntr=0.3,0.1

Type RM Length L Ch R = 1 ,47564   ,597,597,597
BEGIN DESCRIPTION:
WOODSONS GULLY 93.0
END DESCRIPTION:
XS GIS Cut Line= 3
      3864594.42     10045354.64      3864534.74     10045274.34
      3864326.43     10044972.73
#Sta/Elev= 30
  4896.9  105.83  4918.2  105.65  4926.7  103.48  4932.8  101.09  4947.4   99.65
  4968.2   99.32  4982.8   98.35  4995.9   97.66  5001.4   96.62  5001.7   96.12
  5005.5   96.12  5005.8   96.62  5018.5   98.34  5033.4   97.98  5048.3   98.35
  5069.2   97.76    5105    99.3  5119.9   99.13  5134.6  100.38  5161.8  100.75
  5183.2  101.61  5191.6  101.47  5242.3  103.53  5269.3   103.5  5284.2  104.18
    5299  103.79  5328.8  104.61  5334.9  104.31  5355.8   105.5  5363.5  105.34
#Mann= 4 ,-1 , 0
  4896.9    .125       0  4926.7     .15       0  4982.8     .03       0
  5018.5     .17       0
Bank Sta=4982.8,5018.5
XS Rating Curve= 0 ,0
Exp/Cntr=0.3,0.1

Type RM Length L Ch R = 1 ,46967   ,461,461,461
BEGIN DESCRIPTION:
WOODSONS GULLY 92.0
END DESCRIPTION:
XS GIS Cut Line= 3
      3865216.88     10045060.53       3864842.9     10044901.08
      3864462.48     10044596.31
#Sta/Elev= 30
  4596.5  103.44  4659.1  102.55  4762.4  102.62  4833.3  102.17  4838.7  101.59
  4848.4  102.23  4856.3  102.49  4862.3  101.86  4867.7  100.22  4878.1   99.26
  4934.4   98.39  4953.9   98.18  4957.598.03976  4975.9    97.2  4991.3   97.47
  4997.6   96.54  5004.7   96.52  5005.1   96.02  5009.1   96.02  5013.5   97.61
    502898.19944  5085.5   97.42  5141.7   98.96  5248.8  100.52  5291.4  102.43
  5304.8  101.84  5312.8  102.63  5323.7  102.47  5430.3  104.06  5490.5   104.8
#Mann= 10 ,-1 , 0
  4596.5    .125       0  4659.1     .11       0  4848.4     .17       0
  4934.4     .11       0  4953.9     .17       0  4957.5     .03       0
    5028     .17       0  5141.7     .15       0  5323.7     .11       0
  5430.3     .15       0
Bank Sta=4957.5,5028
XS Rating Curve= 0 ,0
Exp/Cntr=0.3,0.1

Type RM Length L Ch R = 1 ,46506   ,506,506,506
BEGIN DESCRIPTION:
WOODSONS GULLY 91.0
END DESCRIPTION:
XS GIS Cut Line= 3
       3865767.9     10044611.08      3865111.49     10044533.89
      3864625.42     10044334.25
#Sta/Elev= 30
  4277.7  107.81  4287.8  107.84  4316.8  105.76  4368.4  104.57  4455.8  103.98
  4659.2  101.63  4700.6  100.29  4740.9   100.5  4771.1   99.32  4821.5  100.19
  4835.4   98.86  4873.5   99.04    4902   97.99  4932.598.10423  4964.4   96.91
  5006.9   96.95  5010.3   96.06  5014.4   96.06  5018.2   97.61    5029   98.09
  5060.3   97.39    5119   97.99    5143   99.43  5234.4  100.42  5244.3  101.32
  5273.7  101.77  5297.6  103.06  5367.9  103.36  5433.7  103.37  5464.1  105.37
#Mann= 6 ,-1 , 0
  4277.7     .11       0  4455.8    .125       0  4873.5     .15       0
  4932.5     .03       0    5029     .15       0  5367.9     .17       0
Bank Sta=4932.5,5029
XS Rating Curve= 0 ,0
Exp/Cntr=0.3,0.1