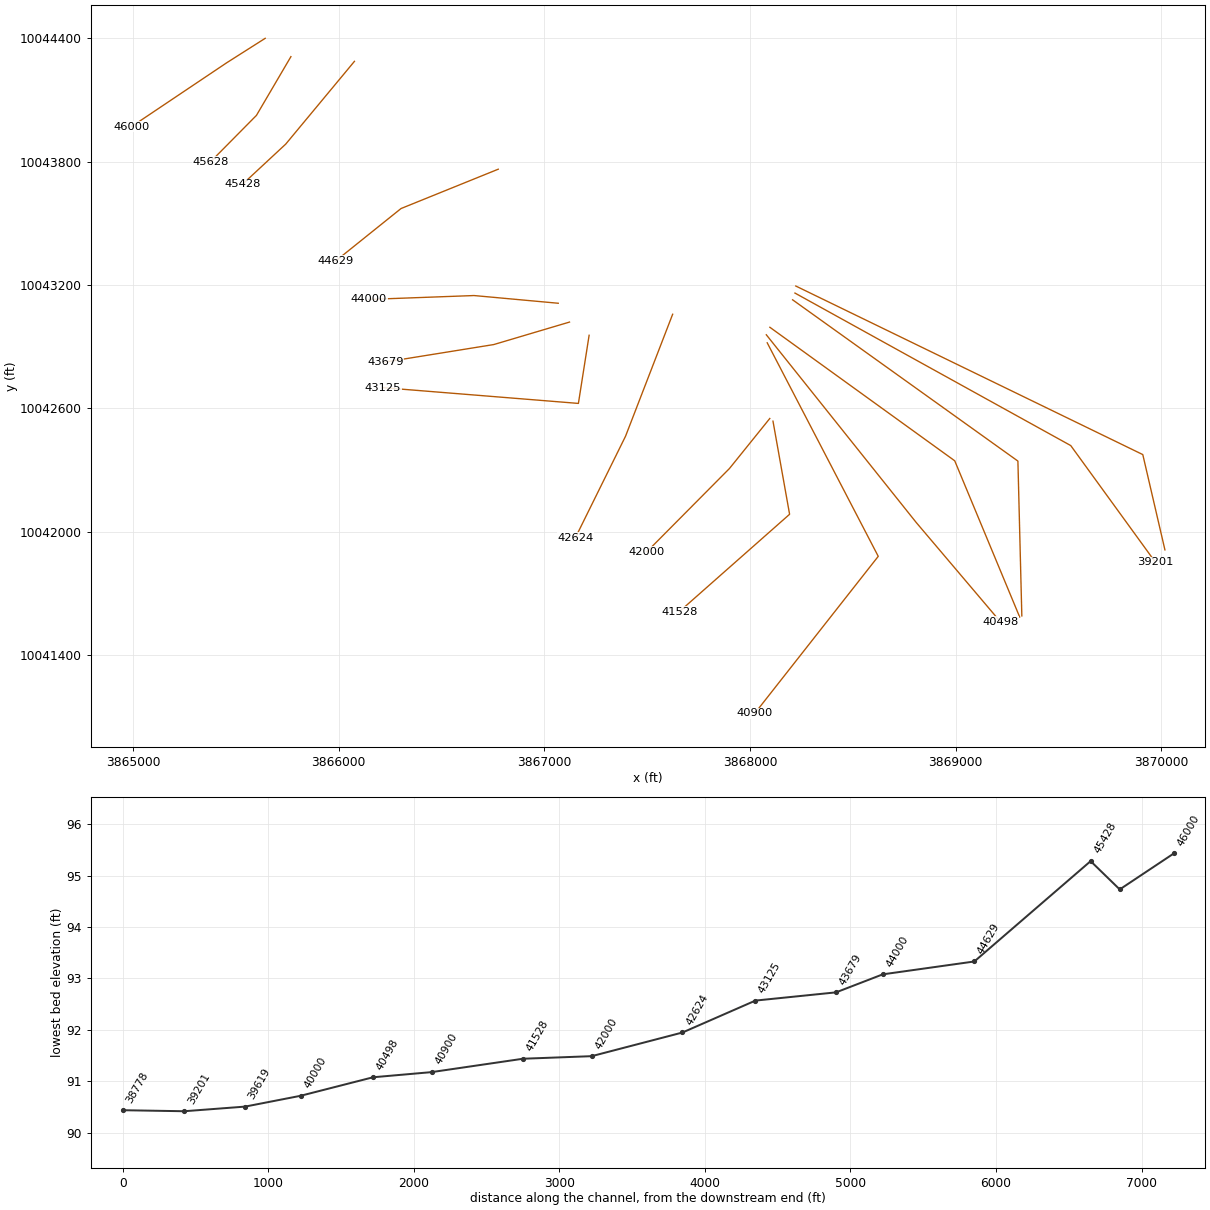
HEC-RAS study WOODSONS GULLY.prj: WOODSONS GULLY Base Level Engineering

--- WOODSONS GULLY.g01 (geometry) --- (continued)

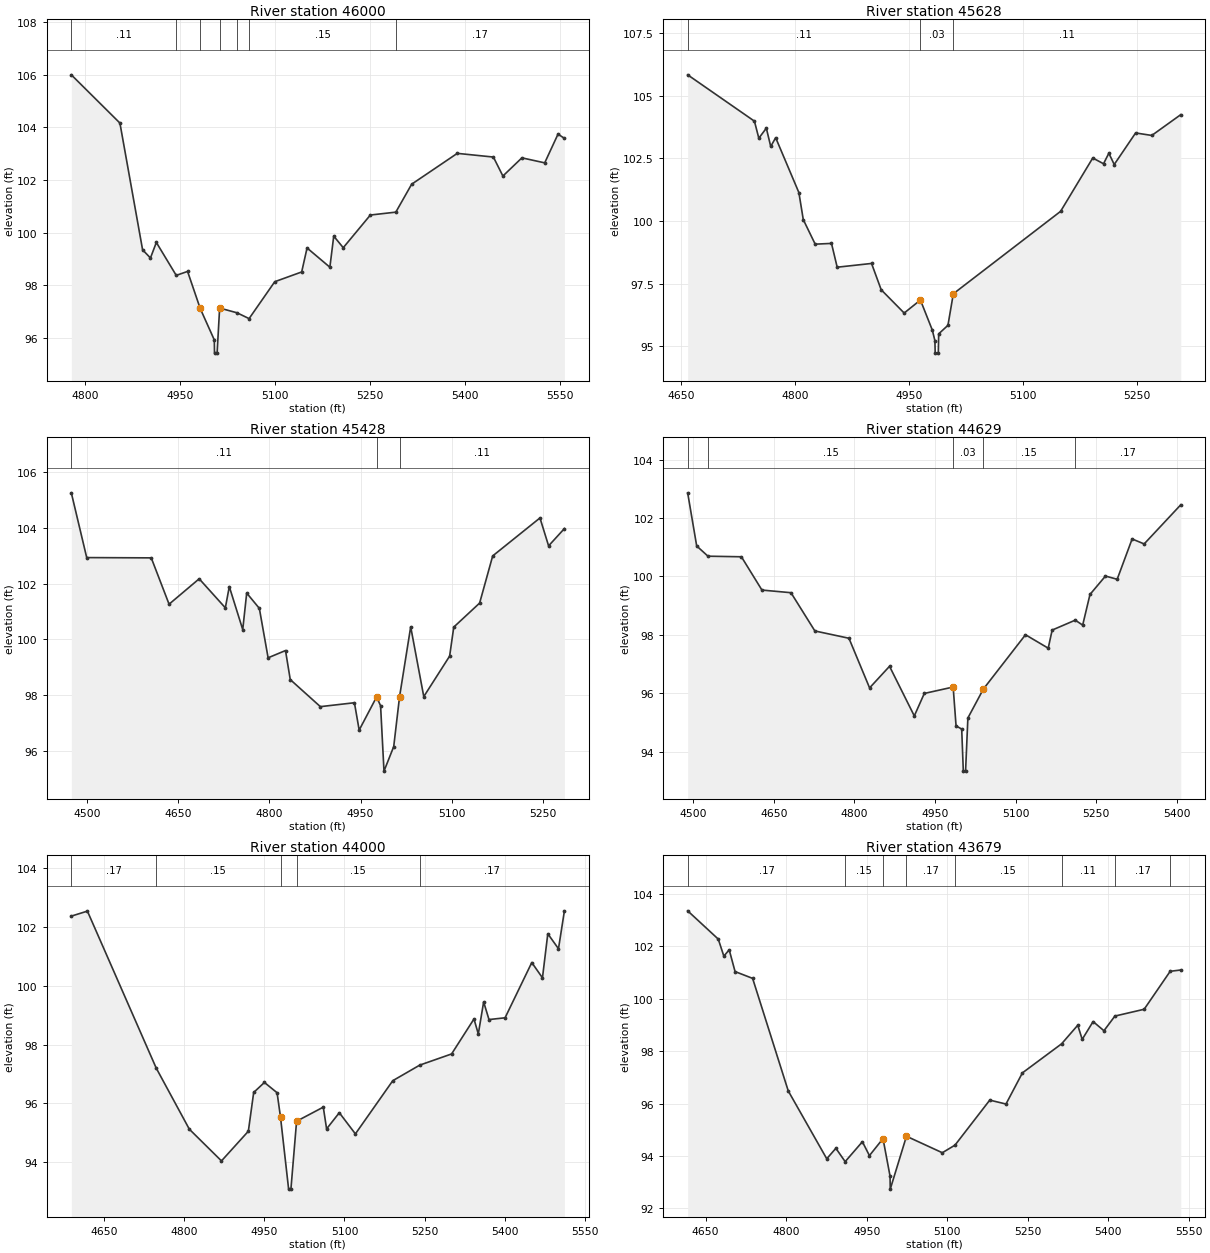
Type RM Length L Ch R = 1 ,46000   ,372,372,372
BEGIN DESCRIPTION:
WOODSONS GULLY 90.0
END DESCRIPTION:
XS GIS Cut Line= 3
      3865642.76     10044400.23      3865456.16     10044281.64
      3864993.49     10043971.14
#Sta/Elev= 30
  4778.9  105.99  4855.6  104.16  4891.4   99.35  4903.8   99.04  4913.1   99.63
  4944.5   98.38  4962.4   98.53 4982.3397.12435  5004.6   95.93  5004.9   95.43
    5009   95.43    5013   97.14  5040.5   96.96  5059.5   96.74    5100   98.14
  5142.5   98.51    5151   99.42    5187   98.69  5193.1   99.87  5208.1   99.43
  5250.9  100.67  5291.1  100.78  5316.1  101.84  5388.1  103.01  5445.1  102.87
  5460.1  102.15  5490.1  102.84  5526.1  102.65  5547.1  103.74  5557.2  103.58
#Mann= 7 ,-1 , 0
  4778.9     .11       0  4944.5    .125       0 4982.33     .03       0
    5013    .125       0  5040.5     .11       0  5059.5     .15       0
  5291.1     .17       0
Bank Sta=4982.33,5013
XS Rating Curve= 0 ,0
Exp/Cntr=0.3,0.1

Type RM Length L Ch R = 1 ,45628   ,200,200,200
BEGIN DESCRIPTION:
WOODSONS GULLY 89.0
END DESCRIPTION:
XS GIS Cut Line= 3
      3865767.87      10044311.1      3865600.21     10044025.21
      3865376.24     10043798.64
#Sta/Elev= 30
  4658.3  105.84  4746.3  103.99  4752.1  103.31    4762  103.71  4767.8  102.98
  4774.3  103.33  4804.9  101.14  4810.7  100.06  4826.4   99.08  4847.9   99.11
  4855.4   98.16  4900.7   98.31  4913.4   97.26  4943.7   96.33  4965.1   96.85
  4980.8   95.65  4984.2   95.23  4984.6   94.73  4988.7   94.73  4989.2    95.5
  5001.4   95.84  5008.5    97.1  5149.9  100.39  5192.3  102.52  5206.5  102.29
  5213.5  102.71  5220.6  102.26  5248.8  103.52  5270.1  103.42  5308.3  104.25
#Mann= 3 , 0 , 0
  4658.3     .11       0  4965.1     .03       0  5008.5     .11       0
Bank Sta=4965.1,5008.5
XS Rating Curve= 0 ,0
Exp/Cntr=0.3,0.1

Type RM Length L Ch R = 1 ,45428   ,799,799,799
BEGIN DESCRIPTION:
WOODSONS GULLY 88.0
END DESCRIPTION:
XS GIS Cut Line= 3
      3866076.74      10044288.2      3865742.57     10043885.45
      3865532.21     10043689.82
#Sta/Elev= 30
  4474.6  105.25  4499.9  102.93    4606  102.92  4635.3  101.26  4684.8  102.17
  4727.8  101.13  4734.3  101.89  4756.4  100.35  4762.9  101.66  4783.7  101.11
  4798.1   99.34  4826.7    99.6  4834.5   98.56    4884   97.59    4940   97.73
  4947.8   96.75  4976.5   97.94    4983   97.62  4988.6   95.28  5004.6   96.16
 5014.2197.94953  5032.5  100.45    5054   97.95  5096.5    99.4  5103.3  100.44
  5145.8   101.3  5167.3  102.99    5245  104.35  5259.2  103.35  5285.2  103.97
#Mann= 3 , 0 , 0
  4474.6     .11       0  4976.5     .03       0 5014.21     .11       0
Bank Sta=4976.5,5014.21
XS Rating Curve= 0 ,0
Exp/Cntr=0.3,0.1

Type RM Length L Ch R = 1 ,44629   ,629,629,629
BEGIN DESCRIPTION:
WOODSONS GULLY 87.0
END DESCRIPTION:
XS GIS Cut Line= 3
      3866775.98      10043763.4      3866303.33       10043572.
      3865985.59     10043316.76
#Sta/Elev= 30
  4489.9  102.86  4506.7  101.04  4527.7  100.69  4589.9  100.67  4628.1   99.53
  4682.1   99.44  4726.6   98.13    4790   97.88  4828.4   96.18  4865.5   96.92
  4911.6   95.22  4930.2   95.99  4983.9   96.21  4989.3   94.88  4999.8   94.77
  5002.8   93.33    5007   93.33  5011.3   95.15  5040.1   96.14  5118.5      98
  5160.8   97.54  5168.1   98.16  5211.1    98.5  5224.9   98.33  5238.5   99.38
  5267.3  100.01  5289.1    99.9  5316.9  101.28  5339.3  101.11  5407.4  102.45
#Mann= 5 ,-1 , 0
  4489.9     .17       0  4527.7     .15       0  4983.9     .03       0
  5040.1     .15       0  5211.1     .17       0
Bank Sta=4983.9,5040.1
XS Rating Curve= 0 ,0
Exp/Cntr=0.3,0.1

Type RM Length L Ch R = 1 ,44000   ,321,321,321
BEGIN DESCRIPTION:
WOODSONS GULLY 86.0
END DESCRIPTION:
XS GIS Cut Line= 3
      3867067.82     10043111.07      3866658.24     10043148.57
      3866146.78     10043129.73
#Sta/Elev= 30
  4588.7  102.37  4618.8  102.54  4747.6    97.2  4809.6   95.12  4869.8   94.04
  4920.1   95.05  4930.1   96.37  4950.2   96.71  4973.9   96.36  4980.3   95.53
  4995.5   93.08  4999.8   93.08  5010.4   95.39  5060.4   95.87  5066.6   95.13
  5090.4   95.68  5120.5   94.96  5190.5   96.77    5241    97.3  5300.6   97.68
  5342.5   98.87  5350.6   98.36  5360.6   99.45  5370.6   98.85  5400.7   98.91
  5450.7  100.79  5470.7  100.27  5480.7  101.77  5500.7  101.26  5511.8  102.55
#Mann= 5 ,-1 , 0
  4588.7     .17       0  4747.6     .15       0  4980.3     .03       0
  5010.4     .15       0    5241     .17       0
Bank Sta=4980.3,5010.4
XS Rating Curve= 0 ,0
Exp/Cntr=0.3,0.1

Type RM Length L Ch R = 1 ,43679   ,554,554,554
BEGIN DESCRIPTION:
WOODSONS GULLY 85.0
END DESCRIPTION:
XS GIS Cut Line= 3
      3867122.47     10043019.49      3866754.39     10042910.11
      3866226.59     10042825.03
#Sta/Elev= 30
  4616.5  103.36  4673.5  102.28  4683.9  101.63  4693.9  101.87  4704.8  101.04
  4737.5  100.78  4803.9   96.48  4875.6   93.89  4892.6   94.29  4909.9   93.78
    4942   94.54  4955.1   94.01  4980.4   94.66  4993.5   93.23  4993.9   92.73
  5024.1   94.75  5090.9   94.12  5114.5   94.41  5179.3   96.13  5209.5   95.98
  5240.1   97.17  5313.1   98.28  5343.2   98.99  5351.5   98.45  5371.8   99.13
    5392   98.78  5412.4   99.34  5466.9    99.6  5515.4  101.05  5535.1   101.1
#Mann= 8 ,-1 , 0
  4616.5     .17       0  4909.9     .15       0  4980.4     .03       0
  5024.1     .17       0  5114.5     .15       0  5313.1     .11       0
  5412.4     .17       0  5515.4     .11       0
Bank Sta=4980.4,5024.1
XS Rating Curve= 0 ,0
Exp/Cntr=0.3,0.1

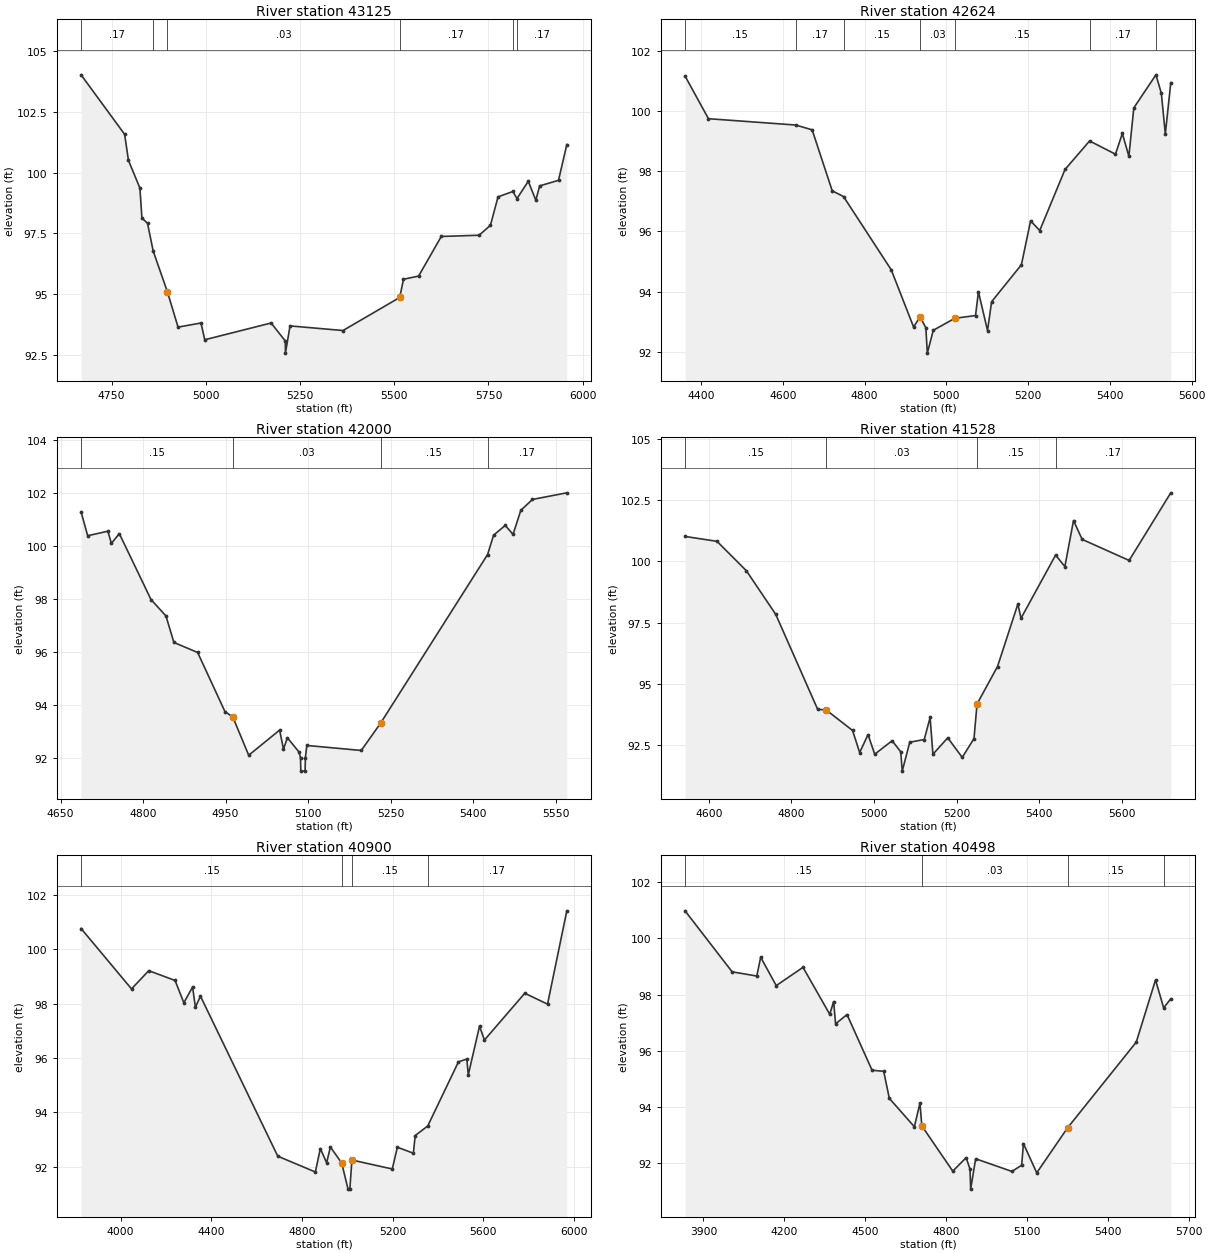
Type RM Length L Ch R = 1 ,43125   ,501,501,501
BEGIN DESCRIPTION:
WOODSONS GULLY 84.0
END DESCRIPTION:
XS GIS Cut Line= 3
      3867217.94     10042955.28      3867165.85     10042623.65
      3866215.94     10042700.35
#Sta/Elev= 30
  4669.2  104.02  4784.8  101.57  4794.9   100.5  4825.3   99.36  4830.6   98.13
  4845.5   97.91  4860.5   96.77  4898.3   95.09  4926.5   93.64  4987.3   93.81
  4997.4   93.12  5173.4   93.81    5211   93.07  5211.4   92.57  5223.6   93.69
  5364.1    93.5  5514.6   94.86  5524.6   95.61  5564.7   95.74  5624.9   97.37
  5725.2   97.42  5755.3   97.83  5775.4      99  5814.8   99.22  5825.7   98.93
  5855.7   99.64  5875.7   98.86  5885.8   99.45  5935.9   99.68  5957.9  101.15
#Mann= 6 ,-1 , 0
  4669.2     .17       0  4860.5     .15       0  4898.3     .03       0
  5514.6     .17       0  5814.8     .11       0  5825.7     .17       0
Bank Sta=4898.3,5514.6
XS Rating Curve= 0 ,0
Exp/Cntr=0.3,0.1

Type RM Length L Ch R = 1 ,42624   ,624,624,624
BEGIN DESCRIPTION:
WOODSONS GULLY 83.0
END DESCRIPTION:
XS GIS Cut Line= 3
      3867624.18     10043057.66      3867395.02     10042463.93
      3867150.79     10041969.15
#Sta/Elev= 30
  4360.7  101.17    4418   99.75  4631.2   99.54  4671.6   99.38  4720.8   97.35
  4748.4   97.16  4865.2   94.72  4919.8   92.82  4935.9   93.16  4949.8   92.79
  4953.4   91.95    4968   92.71  5020.8   93.11  5071.3    93.2  5078.4   93.99
  5100.7    92.7  5110.6   93.66  5183.5   94.89    5206   96.35  5228.4   96.03
  5290.2   98.06  5350.3   99.01  5413.6   98.57  5430.5   99.26  5446.4    98.5
  5458.5  100.11  5512.6  101.21  5525.8   100.6  5535.6   99.24  5548.9  100.95
#Mann= 7 ,-1 , 0
  4360.7     .15       0  4631.2     .17       0  4748.4     .15       0
  4935.9     .03       0  5020.8     .15       0  5350.3     .17       0
  5512.6     .15       0
Bank Sta=4935.9,5020.8
XS Rating Curve= 0 ,0
Exp/Cntr=0.3,0.1

Type RM Length L Ch R = 1 ,42000   ,472,472,472
BEGIN DESCRIPTION:
WOODSONS GULLY 82.0
END DESCRIPTION:
XS GIS Cut Line= 3
      3868096.41      10042550.3      3867900.31     10042306.86
      3867498.77     10041901.88
#Sta/Elev= 30
  4687.4  101.28  4699.4  100.38  4736.1  100.55  4742.5  100.09  4756.9  100.46
  4814.5   97.97  4841.7   97.35  4856.1   96.35  4899.3   95.97  4948.9   93.74
  4963.3   93.53  4992.1   92.09  5048.3   93.04  5055.3   92.32  5062.4   92.75
  5083.6   92.21  5086.3   91.99  5086.8   91.49  5094.6   91.49  5095.1   91.99
  5097.7   92.46  5196.7   92.27  5232.1   93.31  5426.3   99.67  5437.2   100.4
  5458.4  100.77  5472.6  100.43  5486.7  101.34  5507.9  101.75  5570.3     102
#Mann= 4 ,-1 , 0
  4687.4     .15       0  4963.3     .03       0  5232.1     .15       0
  5426.3     .17       0
Bank Sta=4963.3,5232.1
XS Rating Curve= 0 ,0
Exp/Cntr=0.3,0.1

Type RM Length L Ch R = 1 ,41528   ,628,628,628
BEGIN DESCRIPTION:
WOODSONS GULLY 81.0
END DESCRIPTION:
XS GIS Cut Line= 3
      3868112.03     10042537.27      3868192.76     10042084.15
       3867656.3     10041610.19
#Sta/Elev= 30
  4542.5  101.02  4619.9  100.82    4691   99.62  4762.1   97.84  4863.7   93.96
    4884   93.94  4948.1    93.1  4965.3    92.2  4985.6   92.93  5001.8   92.13
  5043.9   92.68  5064.8   92.23  5068.4   91.44  5086.6   92.62  5121.7   92.73
  5135.9   93.63  5142.7   92.13  5178.6    92.8  5213.7      92  5242.2   92.77
  5249.5   94.18  5299.1   95.71  5348.4   98.26    5356   97.68  5439.8  100.26
  5462.2   99.79  5483.1  101.67    5504   100.9  5617.8  100.04  5718.6   102.8
#Mann= 4 ,-1 , 0
  4542.5     .15       0    4884     .03       0  5249.5     .15       0
  5439.8     .17       0
Bank Sta=4884,5249.5
XS Rating Curve= 0 ,0
Exp/Cntr=0.3,0.1

Type RM Length L Ch R = 1 ,40900   ,402,402,402
BEGIN DESCRIPTION:
WOODSONS GULLY 80.0
END DESCRIPTION:
XS GIS Cut Line= 3
      3868083.95     10042918.54      3868623.86     10041879.51
      3868023.42     10041115.31
#Sta/Elev= 30
  3825.7  100.76  4048.2   98.54  4124.2   99.21  4240.4   98.85    4279   98.03
  4317.6   98.61    4330   97.87  4352.5   98.27  4693.5   92.39  4859.2   91.81
  4881.3   92.67    4909   92.15  4925.5   92.73  4975.4   92.14  5003.4   91.18
  5011.4   91.18  5020.4   92.25  5198.5   91.92    5221   92.72  5291.6    92.5
  5299.7   93.15  5354.9    93.5  5490.6   95.86  5527.4   95.96  5533.8   95.38
  5583.5   97.17  5605.1   96.66  5783.1   98.38  5883.5   97.98  5968.5  101.41
#Mann= 4 ,-1 , 0
  3825.7     .15       0  4975.4     .03       0  5020.4     .15       0
  5354.9     .17       0
Bank Sta=4975.4,5020.4
XS Rating Curve= 0 ,0
Exp/Cntr=0.3,0.1

Type RM Length L Ch R = 1 ,40498   ,498,498,498
BEGIN DESCRIPTION:
WOODSONS GULLY 79.0
END DESCRIPTION:
XS GIS Cut Line= 3
      3868079.58     10042957.65      3868808.24     10042044.55
      3869217.87     10041561.05
#Sta/Elev= 30
  3831.8  100.98  4006.5   98.81    4098   98.66  4112.4   99.33  4170.1   98.32
  4269.4   98.97  4368.6    97.3    4383   97.75  4390.3   96.96  4432.7   97.29
  4525.6   95.31  4568.8   95.27  4589.6   94.31  4682.5    93.3  4703.3   94.14
  4710.2   93.33    4825   91.72  4874.6    92.2    4889   91.79  4891.4   91.08
  4909.9   92.16  5044.3   91.71  5080.6   91.93  5087.1    92.7  5136.5   91.66
  5250.8   93.26  5505.7   96.31  5577.1   98.52  5607.3   97.53  5633.7   97.85
#Mann= 4 ,-1 , 0
  3831.8     .15       0  4710.2     .03       0  5250.8     .15       0
  5607.3     .17       0
Bank Sta=4710.2,5250.8
XS Rating Curve= 0 ,0
Exp/Cntr=0.3,0.1

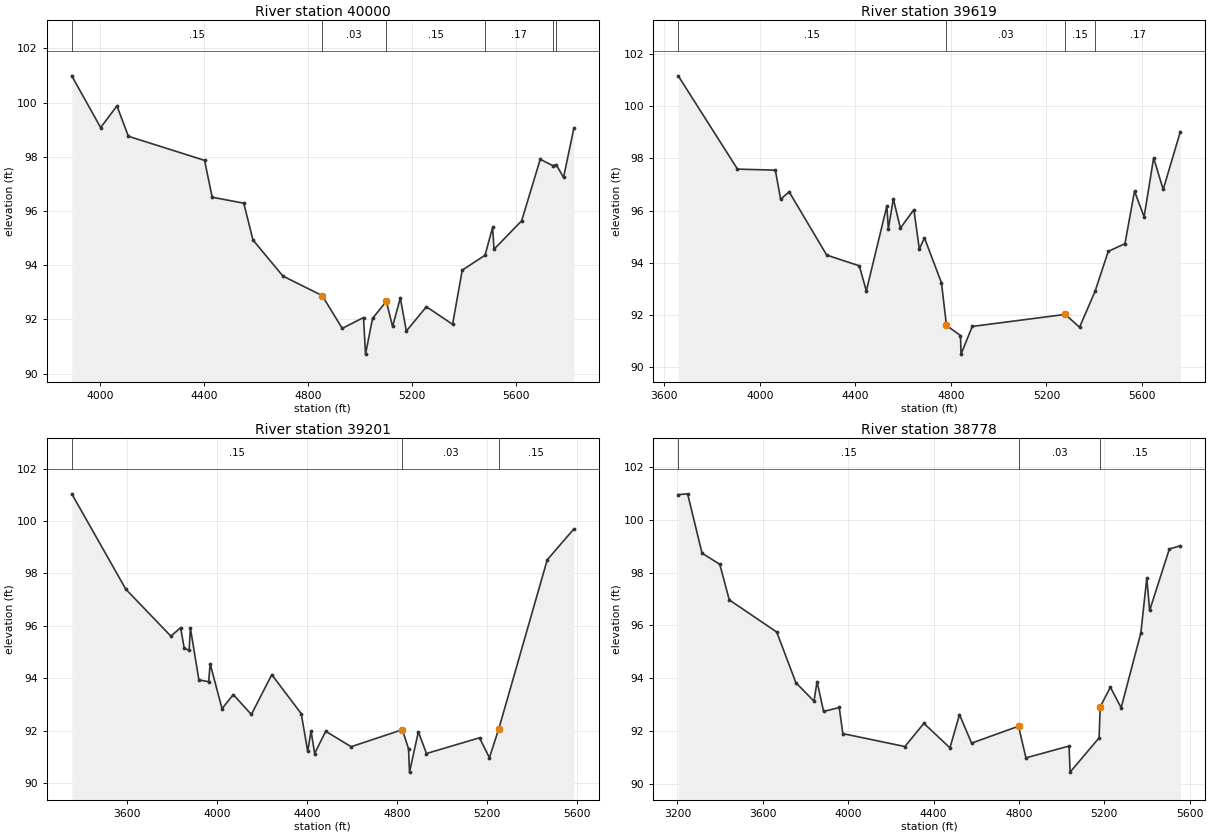
Type RM Length L Ch R = 1 ,40000   ,381,381,381
BEGIN DESCRIPTION:
WOODSONS GULLY 78.0
END DESCRIPTION:
XS GIS Cut Line= 3
      3868096.91     10042994.12       3868995.8     10042344.43
       3869311.5     10041584.39
#Sta/Elev= 30
  3890.9  100.99    4002   99.08  4064.8   99.88  4108.7   98.76  4401.9   97.87
  4431.3   96.51  4552.8   96.29  4588.3   94.93  4703.6    93.6  4854.5   92.88
  4931.8   91.67  5013.7   92.07  5021.3   90.72  5048.4   92.04  5101.5   92.67
  5125.4   91.74  5155.2   92.79  5178.5   91.57  5255.6   92.47  5356.4   91.82
  5393.5   93.82  5481.3   94.37  5510.4    95.4  5515.8   94.59  5622.1   95.64
  5693.7   97.91  5741.3   97.68  5755.4   97.71  5783.3   97.24    5823   99.05
#Mann= 6 ,-1 , 0
  3890.9     .15       0  4854.5     .03       0  5101.5     .15       0
  5481.3     .17       0  5741.3     .15       0  5755.4     .17       0
Bank Sta=4854.5,5101.5
XS Rating Curve= 0 ,0
Exp/Cntr=0.3,0.1

Type RM Length L Ch R = 1 ,39619   ,418,418,418
BEGIN DESCRIPTION:
WOODSONS GULLY 77.0
END DESCRIPTION:
XS GIS Cut Line= 3
      3868207.48     10043127.77      3869302.97     10042343.05
      3869322.07     10041589.54
#Sta/Elev= 30
    3659  101.16    3907   97.59  4065.4   97.55  4087.5   96.44  4123.2   96.72
  4280.4    94.3  4416.7   93.89  4446.2   92.93  4532.2   96.18  4538.3    95.3
  4559.2   96.45  4588.7   95.33  4645.2   96.04  4668.1   94.53  4689.4   94.96
  4760.7   93.24  4781.6   91.61  4840.3   91.22  4842.6   90.51  4889.5   91.57
  5278.6   92.03  5338.6   91.54  5403.4   92.91  5458.7   94.44  5528.7   94.74
  5568.7   96.75  5608.7   95.76  5648.7   98.02  5688.7   96.81  5760.3   99.02
#Mann= 4 ,-1 , 0
    3659     .15       0  4781.6     .03       0  5278.6     .15       0
  5403.4     .17       0
Bank Sta=4781.6,5278.6
XS Rating Curve= 0 ,0
Exp/Cntr=0.3,0.1

Type RM Length L Ch R = 1 ,39201   ,423,423,423
BEGIN DESCRIPTION:
Mapping XS 26df1587
END DESCRIPTION:
XS GIS Cut Line= 3
      3868218.81     10043160.67      3869559.93     10042418.49
      3869972.24     10041849.94
#Sta/Elev= 30
  3352.7  101.04  3593.3    97.4  3793.8   95.61  3837.3   95.93  3853.3   95.15
  3875.1   95.07  3880.8   95.92  3918.6   93.94  3962.1   93.87  3968.8   94.55
  4021.6   92.84  4071.6   93.38  4152.2   92.62  4243.1   94.14  4374.3   92.65
  4403.1   91.21  4417.9      92  4433.9   91.13  4483.1   91.98  4596.5   91.39
  4824.4   92.04  4851.9   91.31  4856.2   90.42  4895.6   91.96  4931.7   91.13
  5167.8   91.73  5211.9   90.97  5253.6   92.07  5469.3   98.52  5587.8    99.7
#Mann= 3 , 0 , 0
  3352.7     .15       0  4824.4     .03       0  5253.6     .15       0
Bank Sta=4824.4,5253.6
XS Rating Curve= 0 ,0
Exp/Cntr=0.3,0.1

Type RM Length L Ch R = 1 ,38778   ,330,330,330
BEGIN DESCRIPTION:
WOODSONS GULLY 76.0
END DESCRIPTION:
XS GIS Cut Line= 3
      3868222.79     10043194.94      3869910.26     10042374.65
      3870017.86     10041911.05
#Sta/Elev= 30
  3203.8  100.96  3247.7  100.99  3315.3   98.74  3398.4   98.32  3442.9   96.97
  3665.3   95.75    3755   93.83  3839.7   93.13  3854.3   93.87  3884.8   92.74
    3958   92.89    3975    91.9  4265.7   91.41  4354.7   92.29  4476.8   91.36
  4521.5   92.62  4578.1   91.54  4798.1   92.18  4832.8   90.98  5034.8   91.43
  5039.7   90.44  5175.5   91.74  5180.6   92.91  5228.4   93.66  5278.8   92.88
  5371.2   95.72    5399    97.8  5412.3   96.57  5504.7    98.9    5556   99.02
#Mann= 3 , 0 , 0
  3203.8     .15       0  4798.1     .03       0  5180.6     .15       0
Bank Sta=4798.1,5180.6
XS Rating Curve= 0 ,0
Exp/Cntr=0.3,0.1