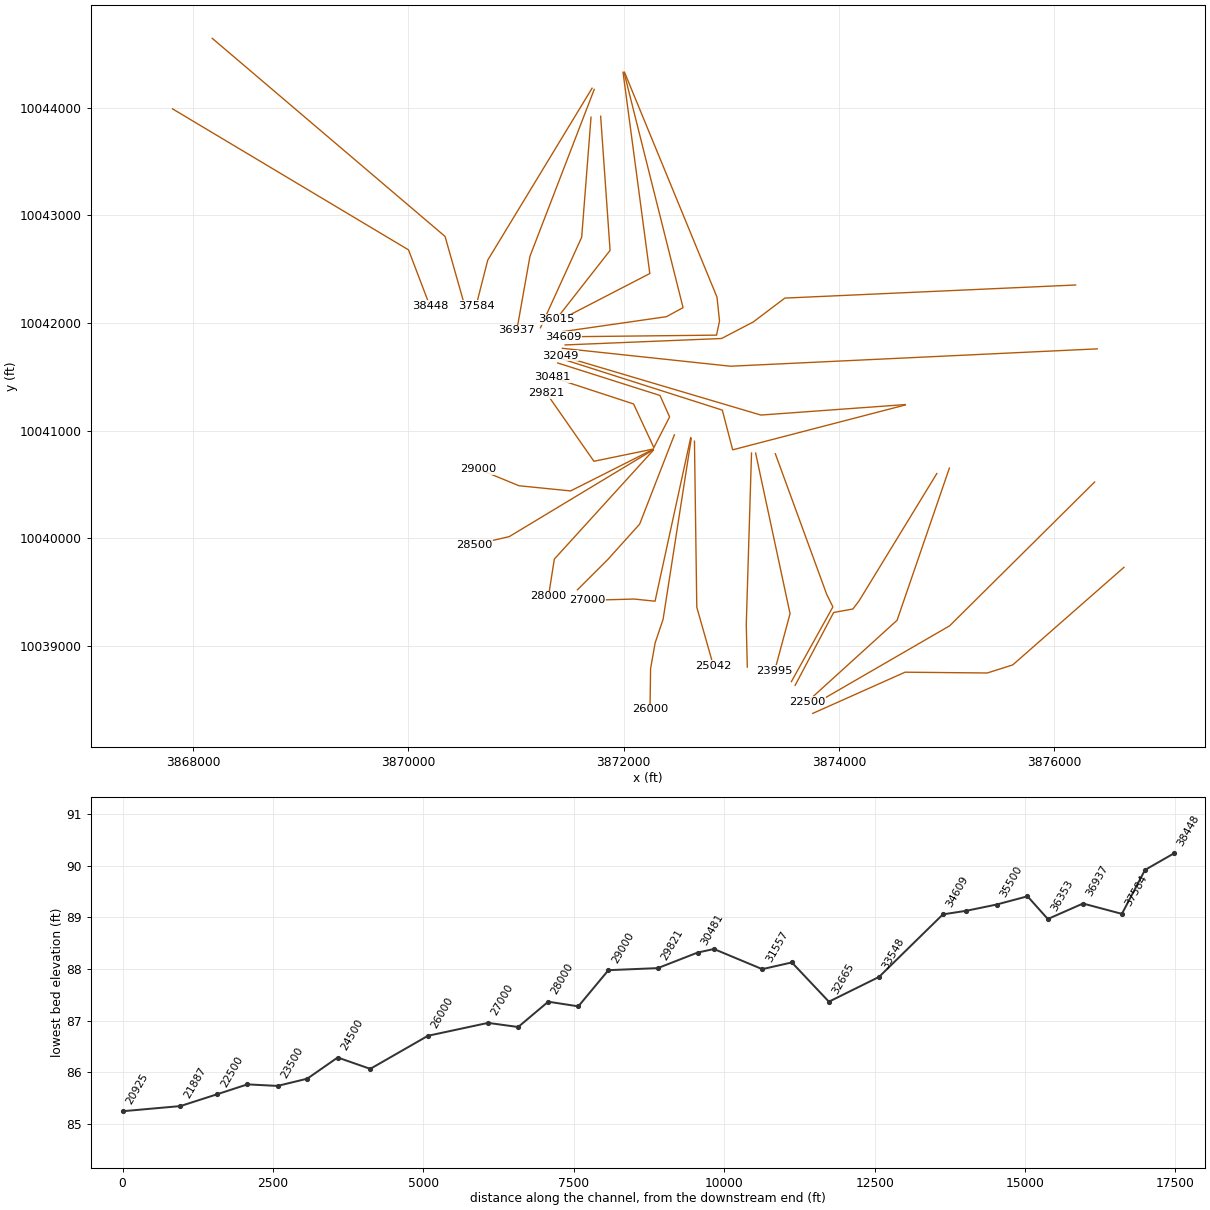
HEC-RAS study WOODSONS GULLY.prj: WOODSONS GULLY Base Level Engineering

--- WOODSONS GULLY.g01 (geometry) --- (continued)

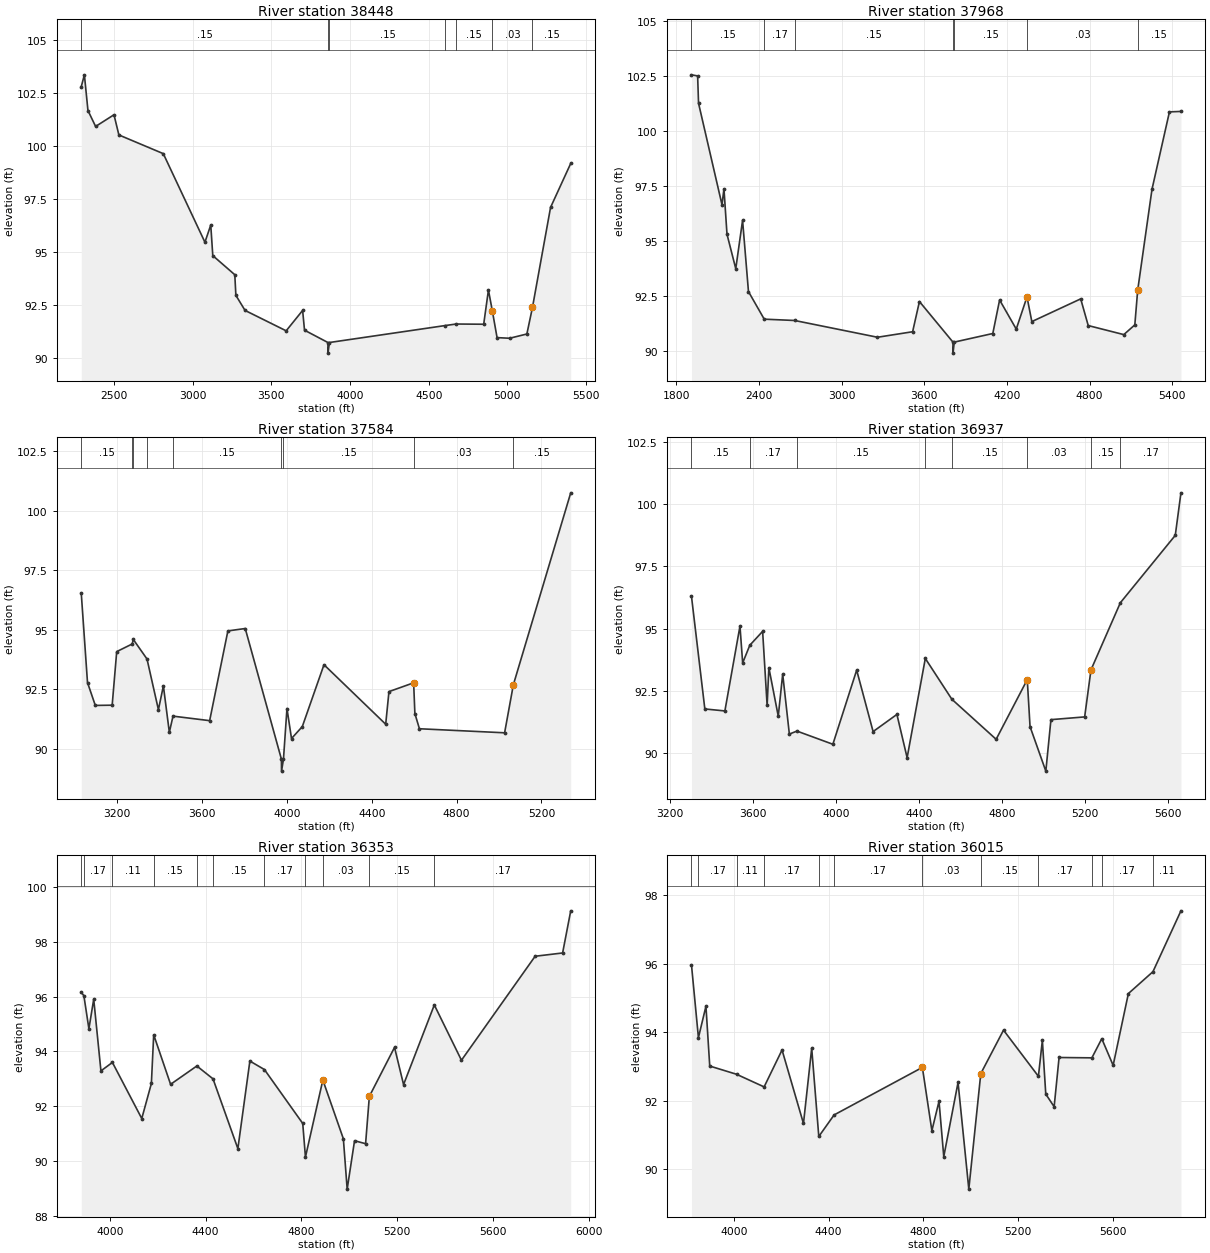
Type RM Length L Ch R = 1 ,38448   ,480,480,480
BEGIN DESCRIPTION:
WOODSONS GULLY 75.0
END DESCRIPTION:
XS GIS Cut Line= 3
      3867810.86     10043990.54      3870002.71     10042679.77
       3870200.2     10042161.08
#Sta/Elev= 30
  2293.2  102.78    2313  103.34  2335.7  101.66  2384.3  100.91    2501  101.46
  2532.1  100.51  2814.2   99.63  3078.7   95.46  3115.7   96.27  3128.6   94.83
  3268.4   93.93  3275.2   92.96  3333.5   92.25  3594.7   91.29  3699.2   92.25
  3711.2   91.32  3859.8   90.74  3860.3   90.24  3869.4   90.74  4606.4   91.54
  4674.4   91.61  4849.3    91.6  4879.4   93.21  4904.1   92.23  4934.2   90.97
  5013.8   90.94  5123.5   91.14    5159   92.39    5274    97.1  5402.1   99.17
#Mann= 7 ,-1 , 0
  2293.2     .15       0  3859.8     .12       0  3869.4     .15       0
  4606.4     .17       0  4674.4     .15       0  4904.1     .03       0
    5159     .15       0
Bank Sta=4904.1,5159
XS Rating Curve= 0 ,0
Exp/Cntr=0.3,0.1

Type RM Length L Ch R = 1 ,37968   ,384,384,384
BEGIN DESCRIPTION:
WOODSONS GULLY 74.0
END DESCRIPTION:
XS GIS Cut Line= 3
       3868179.8     10044645.91      3870342.12     10042804.77
      3870536.57     10042118.98
#Sta/Elev= 30
  1910.8  102.54  1955.5  102.49  1962.1  101.25  2132.3   96.65  2146.6   97.37
  2168.6   95.31  2232.3   93.75  2281.7   95.94  2324.5   92.71  2438.9   91.46
  2659.8    91.4    3261   90.64    3516   90.89  3565.4   92.26  3808.7   90.42
  3809.2   89.92  3818.3   90.42    4098   90.81  4147.4   92.33  4268.2   91.01
  4346.1   92.47  4381.3   91.35    4736   92.38  4790.6   91.17  5048.8   90.76
  5128.8    91.2  5149.6   92.77  5253.5   97.35  5380.1  100.86  5463.6  100.88
#Mann= 7 ,-1 , 0
  1910.8     .15       0  2438.9     .17       0  2659.8     .15       0
  3808.7     .12       0  3818.3     .15       0  4346.1     .03       0
  5149.6     .15       0
Bank Sta=4346.1,5149.6
XS Rating Curve= 0 ,0
Exp/Cntr=0.3,0.1

Type RM Length L Ch R = 1 ,37584   ,647,647,647
BEGIN DESCRIPTION:
WOODSONS GULLY 73.0
END DESCRIPTION:
XS GIS Cut Line= 3
      3871707.55     10044182.09      3870738.82     10042584.43
      3870630.31     10042159.06
#Sta/Elev= 30
  3030.9   96.54  3060.3   92.79  3097.1   91.83  3176.6   91.84    3198   94.09
  3270.8   94.41  3276.3    94.6  3340.8   93.78  3394.6   91.65    3418   92.65
  3446.1    90.7  3463.4   91.38  3636.1   91.19  3722.1   94.96  3803.9   95.06
  3974.5   89.57    3975   89.07  3984.1   89.57  4000.6    91.7    4022   90.44
  4072.9   90.94  4175.1   93.54    4466   91.04  4481.4   92.41  4597.8   92.78
  4603.6   91.49    4625   90.85  5026.6   90.68  5067.9    92.7  5338.3  100.76
#Mann= 9 ,-1 , 0
  3030.9     .15       0  3270.8     .17       0  3276.3     .15       0
  3340.8     .17       0  3463.4     .15       0  3974.5     .12       0
  3984.1     .15       0  4597.8     .03       0  5067.9     .15       0
Bank Sta=4597.8,5067.9
XS Rating Curve= 0 ,0
Exp/Cntr=0.3,0.1

Type RM Length L Ch R = 1 ,36937   ,584,584,584
BEGIN DESCRIPTION:
WOODSONS GULLY 72.0
END DESCRIPTION:
XS GIS Cut Line= 3
      3871727.84     10044171.34      3871130.75     10042619.58
      3871009.06     10041934.17
#Sta/Elev= 30
  3304.1    96.3  3368.5   91.77  3465.1   91.69  3537.8    95.1  3550.8   93.62
  3585.1   94.33    3647   94.89  3668.7   91.91    3677   93.43  3722.3   91.48
  3743.7   93.17  3775.8   90.76  3812.4   90.88  3985.5   90.35  4100.2   93.33
  4179.4   90.86  4294.1   91.55  4343.3   89.81    4431    93.8  4558.9   92.16
  4772.3   90.55  4922.3   92.95  4935.7   91.06  5011.8   89.27  5036.4   91.34
  5198.9   91.45  5229.3   93.34  5370.9   96.04  5635.6   98.75  5662.9  100.46
#Mann= 8 ,-1 , 0
  3304.1     .15       0  3585.1     .17       0  3812.4     .15       0
    4431     .17       0  4558.9     .15       0  4922.3     .03       0
  5229.3     .15       0  5370.9     .17       0
Bank Sta=4922.3,5229.3
XS Rating Curve= 0 ,0
Exp/Cntr=0.3,0.1

Type RM Length L Ch R = 1 ,36353   ,338,338,338
BEGIN DESCRIPTION:
WOODSONS GULLY 71.0
END DESCRIPTION:
XS GIS Cut Line= 3
      3871698.12     10043912.88      3871611.21     10042796.86
      3871228.54     10041955.83
#Sta/Elev= 30
  3880.6   96.16  3891.5   96.04  3912.5   94.83  3932.6   95.91  3962.7   93.29
  4010.6    93.6  4133.2   91.55  4173.3   92.83    4183   94.61  4253.5    92.8
  4363.1   93.47  4430.6      93  4534.4   90.45  4584.5   93.65  4645.2   93.34
  4805.2   91.37  4816.5   90.14 4889.1692.95589  4974.8   90.81  4990.7   88.97
  5021.5   90.74  5067.6   90.63  5083.3   92.36  5188.4   94.15  5226.1   92.79
  5354.5    95.7  5467.8   93.68  5775.4   97.48  5890.1    97.6    5924   99.14
#Mann= 11 ,-1 , 0
  3880.6     .15       0  3891.5     .17       0  4010.6     .11       0
    4183     .15       0  4363.1     .17       0  4430.6     .15       0
  4645.2     .17       0  4816.5     .15       0 4889.16     .03       0
  5083.3     .15       0  5354.5     .17       0
Bank Sta=4889.16,5083.3
XS Rating Curve= 0 ,0
Exp/Cntr=0.3,0.1

Type RM Length L Ch R = 1 ,36015   ,515,515,515
BEGIN DESCRIPTION:
WOODSONS GULLY 70.0
END DESCRIPTION:
XS GIS Cut Line= 3
      3871787.39     10043921.97      3871874.95     10042674.72
      3871374.15      10042034.3
#Sta/Elev= 30
    3822   95.97  3851.3   93.84    3883   94.76    3899   93.01  4011.8   92.77
  4128.2    92.4  4203.8   93.48  4294.1   91.33  4328.8   93.53  4358.7   90.95
  4423.2   91.58  4795.3   92.97  4835.4   91.12  4865.5   91.98  4885.5   90.36
  4945.7   92.53  4991.1   89.41  5041.6   92.79  5137.4   94.06  5284.5   92.71
  5301.1   93.76  5315.5   92.19  5350.8   91.82  5371.6   93.26  5509.9   93.25
  5551.6   93.81  5599.5   93.03  5663.7   95.13  5767.3   95.77  5885.3   97.55
#Mann= 12 ,-1 , 0
    3822     .15       0  3851.3     .17       0  4011.8     .11       0
  4128.2     .17       0  4358.7     .15       0  4423.2     .17       0
  4795.3     .03       0  5041.6     .15       0  5284.5     .17       0
  5509.9     .11       0  5551.6     .17       0  5767.3     .11       0
Bank Sta=4795.3,5041.6
XS Rating Curve= 0 ,0
Exp/Cntr=0.3,0.1

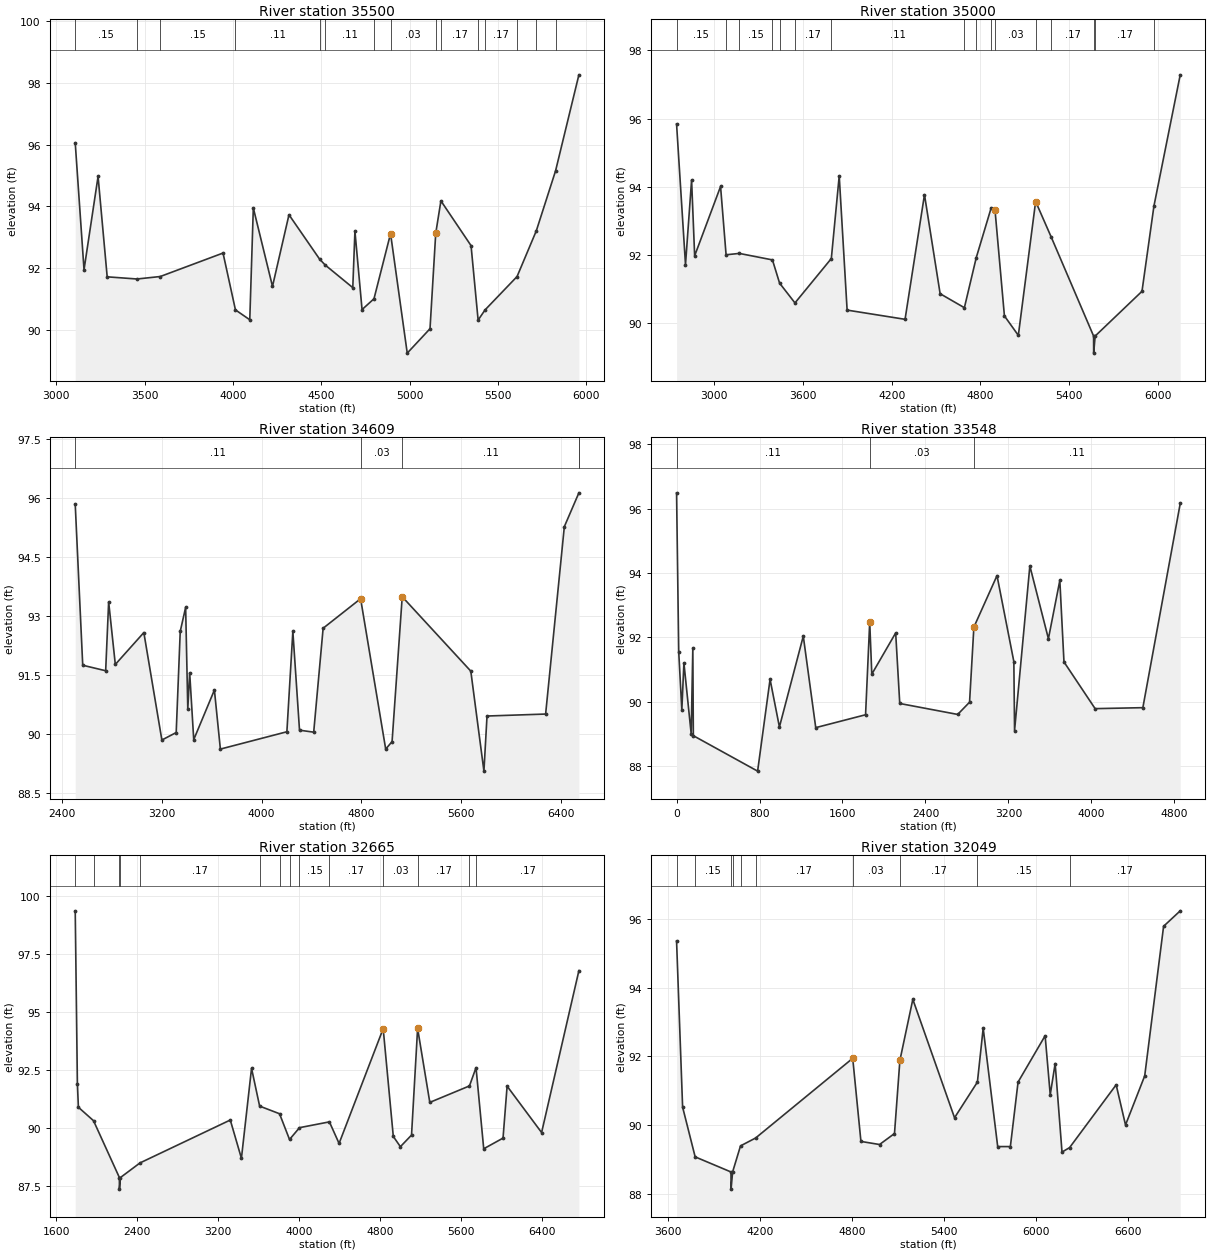
Type RM Length L Ch R = 1 ,35500   ,500,500,500
BEGIN DESCRIPTION:
WOODSONS GULLY 69.0
END DESCRIPTION:
XS GIS Cut Line= 3
      3871995.29     10044330.41      3872244.13     10042459.74
       3871388.1     10042016.99
#Sta/Elev= 30
  3107.1   96.06  3156.9   91.95  3236.4   94.97    3288   91.72  3456.8   91.65
  3588.3   91.73  3943.7   92.49    4014   90.65  4095.1   90.33  4115.2   93.95
  4223.7   91.41    4317   93.73  4490.7   92.29  4522.5    92.1  4678.2   91.37
  4690.3    93.2  4730.6   90.66  4798.2   91.01    4892   93.12  4986.4   89.25
  5115.3   90.04  5147.7   93.13    5177   94.18  5347.6   92.73  5387.6   90.32
    5427   90.65  5608.1   91.73    5717   93.21  5825.9   95.15    5958   98.26
#Mann= 15 ,-1 , 0
  3107.1     .15       0  3456.8     .17       0  3588.3     .15       0
    4014     .11       0  4490.7     .17       0  4522.5     .11       0
  4798.2     .15       0    4892     .03       0  5147.7     .15       0
    5177     .17       0  5387.6     .15       0    5427     .17       0
  5608.1     .11       0    5717     .17       0  5825.9     .11       0
Bank Sta=4892,5147.7
XS Rating Curve= 0 ,0
Exp/Cntr=0.3,0.1

Type RM Length L Ch R = 1 ,35000   ,391,391,391
BEGIN DESCRIPTION:
WOODSONS GULLY 68.0
END DESCRIPTION:
XS GIS Cut Line= 4
       3872004.6     10044329.66      3872552.86     10042142.74
      3872398.48     10042058.64      3871433.22     10041919.76
#Sta/Elev= 30
  2745.4   95.84  2805.8   91.72    2847    94.2  2867.7   91.98  3042.9   94.01
  3080.2   92.01  3169.5   92.05  3393.7   91.86    3442   91.18  3545.9    90.6
  3791.9    91.9  3845.2   94.32  3898.6   90.39  4290.4   90.12  4421.7   93.77
  4527.5   90.87  4691.5   90.46    4772   91.93  4872.4   93.38  4898.6   93.32
  4962.2   90.22  5056.3   89.65  5173.3   93.57  5279.6   92.52  5565.2   89.63
  5565.7   89.13  5575.7   89.63  5892.4   90.94  5973.3   93.44    6151   97.28
#Mann= 16 ,-1 , 0
  2745.4     .15       0  3080.2     .17       0  3169.5     .15       0
  3393.7     .11       0    3442     .15       0  3545.9     .17       0
  3791.9     .11       0  4691.5     .15       0    4772     .11       0
  4872.4     .17       0  4898.6     .03       0  5173.3     .11       0
  5279.6     .17       0  5565.2     .12       0  5575.7     .17       0
  5973.3     .11       0
Bank Sta=4898.6,5173.3
XS Rating Curve= 0 ,0
Exp/Cntr=0.3,0.1

Type RM Length L Ch R = 1 ,34609   ,1061,1061,1061
BEGIN DESCRIPTION:
WOODSONS GULLY 67.0
END DESCRIPTION:
XS GIS Cut Line= 5
      3872009.31     10044330.12       3872868.1     10042240.07
      3872891.55     10042018.12      3872863.76      10041887.2
      3871441.07      10041871.6
#Sta/Elev= 30
  2505.7   95.84  2565.9   91.75  2749.9   91.61  2773.8   93.36  2827.2   91.77
    3056   92.58  3200.6   89.85  3315.5   90.04  3347.9   92.61  3391.2   93.22
  3408.5   90.64  3423.6   91.56  3456.1   89.86  3621.9   91.12  3669.8   89.62
  4203.2   90.06  4251.1   92.61  4304.5    90.1  4418.3   90.05  4493.9   92.69
  4794.5   93.44  4995.7   89.62  5046.8   89.81  5128.2   93.49  5678.3    91.6
  5783.5   89.06  5808.3   90.46  6278.3   90.51  6428.3   95.27  6545.1   96.13
#Mann= 5 ,-1 , 0
  2505.7     .11       0  4794.5     .03       0  5128.2     .11       0
  6545.1     .11       0  6545.1     .11       0
Bank Sta=4794.5,5128.2
XS Rating Curve= 0 ,0
Exp/Cntr=0.3,0.1

Type RM Length L Ch R = 1 ,33548   ,834,834,834
XS GIS Cut Line= 5
      3876198.61     10042353.17      3873498.24     10042231.47
       3873204.9      10042009.6      3872910.63     10041855.95
      3871457.51     10041796.06
#Sta/Elev= 30
       0   96.49    20.8   91.56    50.8   89.75    70.8   91.21   140.9   89.01
   156.8   91.67   161.8   88.95   781.6   87.85   901.7    90.7   991.8   89.22
    1222   92.04  1342.1    89.2  1822.6    89.6  1862.6   92.48  1882.7   90.86
  2112.9   92.14  2152.3   89.95    2711   89.61  2825.4   89.99  2867.1   92.32
  3090.1   93.92  3252.5   91.25  3259.4   89.11  3406.8   94.22  3585.8   91.96
  3695.9   93.77  3735.9   91.24  4036.2   89.79  4496.6   89.82    4857   96.16
#Mann= 3 , 0 , 0
       0     .11       0  1862.6     .03       0  2867.1     .11       0
Bank Sta=1862.6,2867.1
XS Rating Curve= 0 ,0
Exp/Cntr=0.3,0.1

Type RM Length L Ch R = 1 ,32665   ,616,616,616
BEGIN DESCRIPTION:
WOODSONS GULLY 63.0
END DESCRIPTION:
XS GIS Cut Line= 3
      3876399.23     10041759.61      3872993.97     10041598.14
      3871432.11     10041764.74
#Sta/Elev= 30
  1785.4   99.37  1806.8   91.92  1816.8    90.9  1966.3   90.32    2222   87.87
  2222.5   87.37  2232.5   87.87  2425.8    88.5  3318.5   90.35  3428.6    88.7
  3528.7   92.58  3608.5   90.95  3805.6   90.62  3904.2   89.51  4002.8   90.02
  4298.4   90.27  4394.2   89.34  4830.2   94.29  4930.3   89.64  5000.4    89.2
  5110.5    89.7  5170.6    94.3  5291.1   91.11  5683.3   91.82  5748.2   92.61
  5824.2   89.11  6015.2   89.57  6055.5   91.81  6396.5   89.81  6765.2   96.79
#Mann= 14 ,-1 , 0
  1785.4     .11       0  1966.3     .17       0    2222     .12       0
  2232.5     .17       0  2425.8     .17       0  3608.5     .15       0
  3805.6     .17       0  3904.2     .11       0  4002.8     .15       0
  4298.4     .17       0  4830.2     .03       0  5170.6     .17       0
  5683.3     .15       0  5748.2     .17       0
Bank Sta=4830.2,5170.6
XS Rating Curve= 0 ,0
Exp/Cntr=0.3,0.1

Type RM Length L Ch R = 1 ,32049   ,492,492,492
BEGIN DESCRIPTION:
WOODSONS GULLY 62.0
END DESCRIPTION:
XS GIS Cut Line= 3
      3874617.19     10041241.72      3873275.63     10041144.25
      3871415.74     10041695.99
#Sta/Elev= 30
  3654.9   95.36  3694.3   90.52  3776.2   89.07  4009.9   88.63  4010.4   88.13
  4020.4   88.63    4072   89.39  4170.6   89.62  4803.891.94228  4857.4   89.52
  4978.8   89.43  5076.3   89.75  5111.591.88076  5195.9   93.66  5467.9   90.21
  5617.1   91.25  5654.8   92.82  5749.4   89.37  5832.1   89.37  5882.3   91.25
  6058.8    92.6  6092.1   90.88  6124.2   91.79  6168.9   89.21  6218.4   89.34
  6522.1   91.17  6583.1      90  6708.3   91.43  6831.5   95.79    6940   96.24
#Mann= 10 ,-1 , 0
  3654.9     .17       0  3776.2     .15       0  4009.9     .12       0
  4020.4     .15       0    4072     .11       0  4170.6     .17       0
  4803.8     .03       0  5111.5     .17       0  5617.1     .15       0
  6218.4     .17       0
Bank Sta=4803.8,5111.5
XS Rating Curve= 0 ,0
Exp/Cntr=0.3,0.1

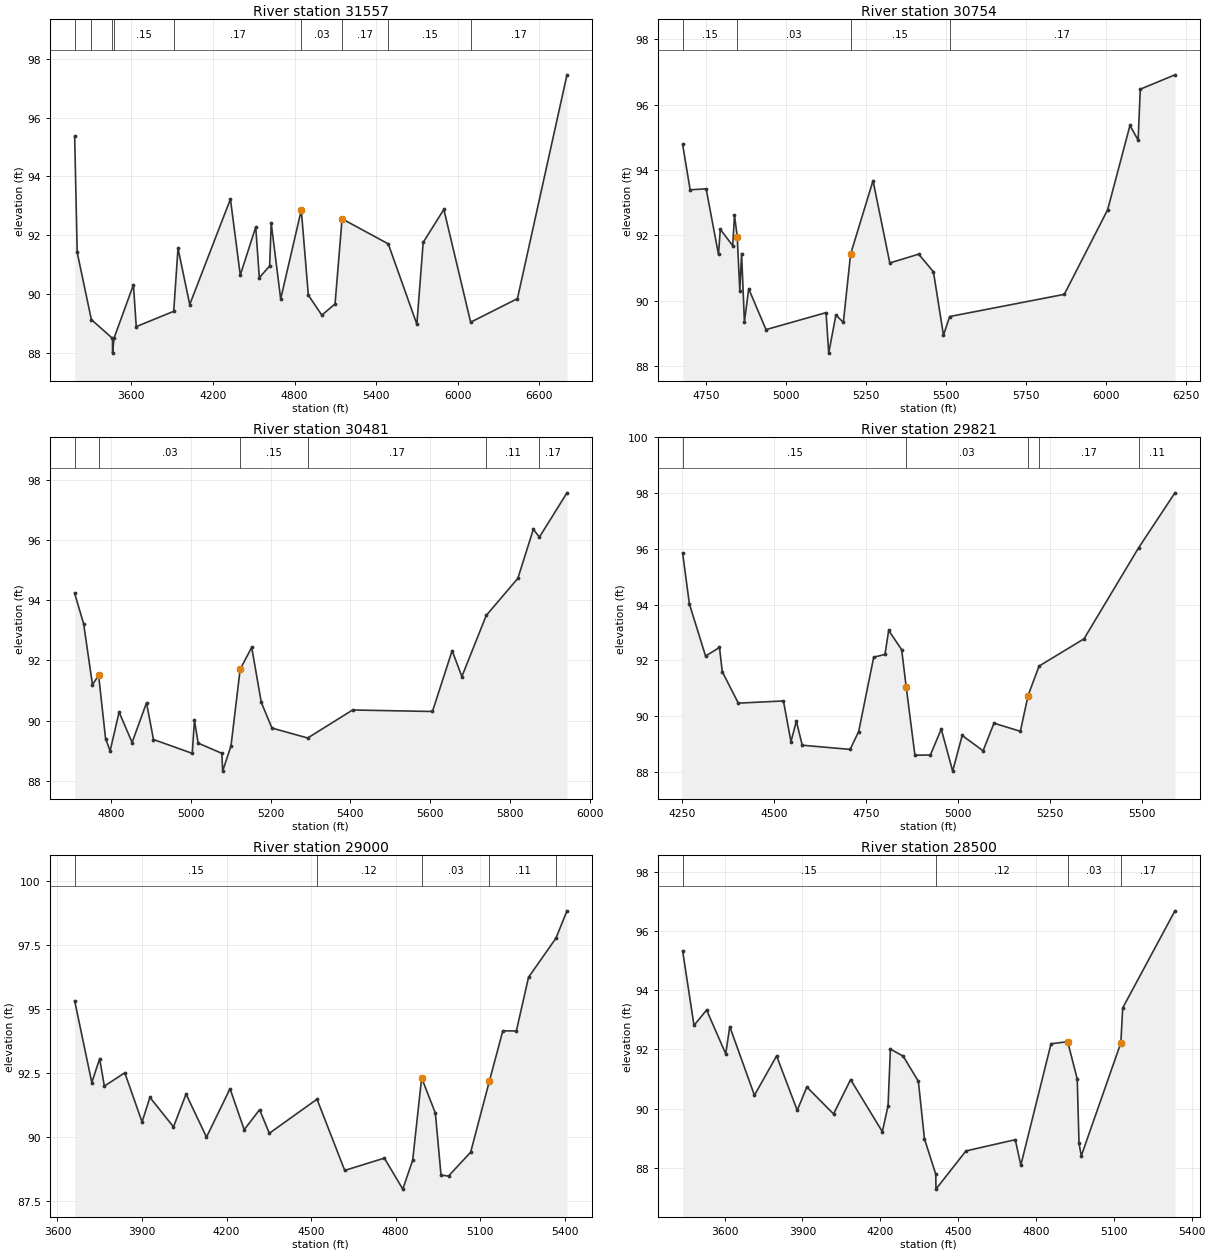
Type RM Length L Ch R = 1 ,31557   ,803,803,803
BEGIN DESCRIPTION:
WOODSONS GULLY 61.0
END DESCRIPTION:
XS GIS Cut Line= 4
      3874615.95     10041237.72      3873013.78     10040821.12
      3872917.43     10041190.36      3871411.06     10041671.53
#Sta/Elev= 30
  3183.6   95.36  3202.3   91.42  3306.3   89.14  3461.7    88.5  3462.2      88
  3472.3    88.5  3615.6   90.32  3636.3    88.9  3911.7   89.42  3943.1   91.56
  4029.4   89.65  4328.5   93.23  4400.9   90.65  4514.5   92.28  4540.8   90.56
  4616.7   90.96  4628.2   92.41  4697.8   89.84  4849.3   92.86    4901   89.97
  5000.2   89.29  5097.4   89.67    5149   92.56  5488.4   91.71  5698.7   88.98
  5745.1   91.76    5897   92.88    6094   89.05  6437.9   89.85    6802   97.45
#Mann= 9 ,-1 , 0
  3183.6     .17       0  3306.3     .15       0  3461.7     .12       0
  3472.3     .15       0  3911.7     .17       0  4849.3     .03       0
    5149     .17       0  5488.4     .15       0    6094     .17       0
Bank Sta=4849.3,5149
XS Rating Curve= 0 ,0
Exp/Cntr=0.3,0.1

Type RM Length L Ch R = 1 ,30754   ,273,273,273
BEGIN DESCRIPTION:
WOODSONS GULLY 60.0
END DESCRIPTION:
XS GIS Cut Line= 4
      3872280.05     10040839.22      3872427.86     10041126.86
      3872338.73     10041326.37      3871388.19     10041628.46
#Sta/Elev= 30
  4676.6   94.78  4700.1   93.39  4750.1   93.42  4788.8   91.41  4794.4   92.18
  4833.2   91.68  4838.8   92.61  4847.3   91.96  4855.4    90.3    4861   91.44
  4869.8   89.34  4883.2   90.36  4937.3   89.11  5125.1   89.63  5133.4   88.39
  5155.9   89.56  5179.1   89.33  5201.8   91.42  5271.9   93.67  5324.4   91.15
  5414.6   91.42  5460.8   90.88  5492.2   88.94  5511.6   89.51    5870   90.19
  6005.5   92.78  6075.3   95.36  6100.8   94.91  6107.5   96.47  6215.9   96.91
#Mann= 4 ,-1 , 0
  4676.6     .15       0  4847.3     .03       0  5201.8     .15       0
  5511.6     .17       0
Bank Sta=4847.3,5201.8
XS Rating Curve= 0 ,0
Exp/Cntr=0.3,0.1

Type RM Length L Ch R = 1 ,30481   ,660,660,660
BEGIN DESCRIPTION:
WOODSONS GULLY 59.0
END DESCRIPTION:
XS GIS Cut Line= 3
       3872277.7     10040850.68      3872093.07     10041247.59
      3871337.82       10041495.
#Sta/Elev= 30
  4709.7   94.22  4732.2   93.21  4754.3   91.19  4769.7    91.5  4787.1    89.4
  4798.4   88.99    4821   90.28  4853.5   89.27  4889.6   90.59    4907   89.37
  5004.1   88.91  5009.6   90.01  5018.9   89.25  5078.2   88.91  5080.2   88.32
  5101.1   89.16    5124    91.7  5152.9   92.43    5177    90.6  5203.6   89.75
  5293.1   89.42  5405.5   90.35  5605.4    90.3  5654.7   92.32  5679.1   91.46
  5740.1   93.49  5819.2   94.72    5858   96.35  5873.2   96.09  5942.2   97.56
#Mann= 6 ,-1 , 0
  4709.7     .15       0  4769.7     .03       0    5124     .15       0
  5293.1     .17       0  5740.1     .11       0  5873.2     .17       0
Bank Sta=4769.7,5124
XS Rating Curve= 0 ,0
Exp/Cntr=0.3,0.1

Type RM Length L Ch R = 1 ,29821   ,821,821,821
BEGIN DESCRIPTION:
WOODSONS GULLY 58.0
END DESCRIPTION:
XS GIS Cut Line= 3
       3872275.9     10040828.24      3871724.92     10040714.78
      3871282.54     10041349.72
#Sta/Elev= 30
  4252.1   95.85  4270.5   94.02  4314.4   92.15  4352.2   92.46  4359.7   91.59
  4403.3   90.46  4525.8   90.54  4546.2   89.08  4560.9   89.81  4576.8   88.95
  4706.8    88.8    4730   89.44  4770.8   92.11  4801.4   92.21  4811.4   93.07
  4846.7   92.38  4859.1   91.03  4882.7   88.59  4924.6    88.6  4954.2   89.53
  4985.1   88.02    5011    89.3  5067.7   88.75  5097.3   89.74  5168.9   89.45
  5189.8   90.73  5219.6   91.79  5341.7   92.77    5490   96.04  5588.5   98.01
#Mann= 5 ,-1 , 0
  4252.1     .15       0  4859.1     .03       0  5189.8     .15       0
  5219.6     .17       0    5490     .11       0
Bank Sta=4859.1,5189.8
XS Rating Curve= 0 ,0
Exp/Cntr=0.3,0.1

Type RM Length L Ch R = 1 ,29000   ,500,500,500
BEGIN DESCRIPTION:
WOODSONS GULLY 56.0
END DESCRIPTION:
XS GIS Cut Line= 4
      3872273.82     10040825.11      3871508.55     10040439.08
      3871029.17     10040487.15      3870651.77     10040642.44
#Sta/Elev= 30
  3661.1   95.33  3721.9   92.14  3749.8   93.07  3766.5      92    3839   92.52
  3900.3    90.6  3928.2   91.56  4011.8   90.41  4056.4   91.69  4128.9   90.01
  4212.5    91.9  4262.7    90.3  4317.4   91.08  4351.9   90.16  4521.1   91.49
  4619.4   88.71  4760.1   89.19  4825.5   87.98  4860.6   89.11  4892.4   92.32
    4941   90.95  4961.1   88.53  4987.7   88.49  5066.3   89.42  5132.6   92.19
  5180.5   94.16  5228.4   94.15  5271.8   96.25  5368.8   97.77  5408.1   98.84
#Mann= 5 ,-1 , 0
  3661.1     .15       0  4521.1     .12       0  4892.4     .03       0
  5132.6     .11       0  5368.8     .17       0
Bank Sta=4892.4,5132.6
XS Rating Curve= 0 ,0
Exp/Cntr=0.3,0.1

Type RM Length L Ch R = 1 ,28500   ,500,500,500
BEGIN DESCRIPTION:
WOODSONS GULLY 55.0
END DESCRIPTION:
XS GIS Cut Line= 3
      3872275.89     10040821.46      3870938.55     10040014.39
      3870611.67      10039938.4
#Sta/Elev= 30
    3438   95.33  3481.9   92.81  3530.4   93.33  3604.2   91.85  3619.7   92.77
  3714.8   90.45  3800.2   91.78  3879.8   89.94  3916.7   90.73  4019.7   89.82
  4085.5   90.98  4207.8   89.22  4229.9    90.1  4238.9   92.01  4288.3   91.77
  4346.7   90.92  4370.1   88.98  4413.9   87.78  4414.4   87.28    4530   88.57
  4720.2   88.95  4741.6   88.09    4858   92.19  4922.1   92.26    4959      91
  4965.8   88.84  4974.5    88.4  5127.1   92.22  5134.2    93.4  5335.6   96.68
#Mann= 4 ,-1 , 0
    3438     .15       0  4413.9     .12       0  4922.1     .03       0
  5127.1     .17       0
Bank Sta=4922.1,5127.1
XS Rating Curve= 0 ,0
Exp/Cntr=0.3,0.1

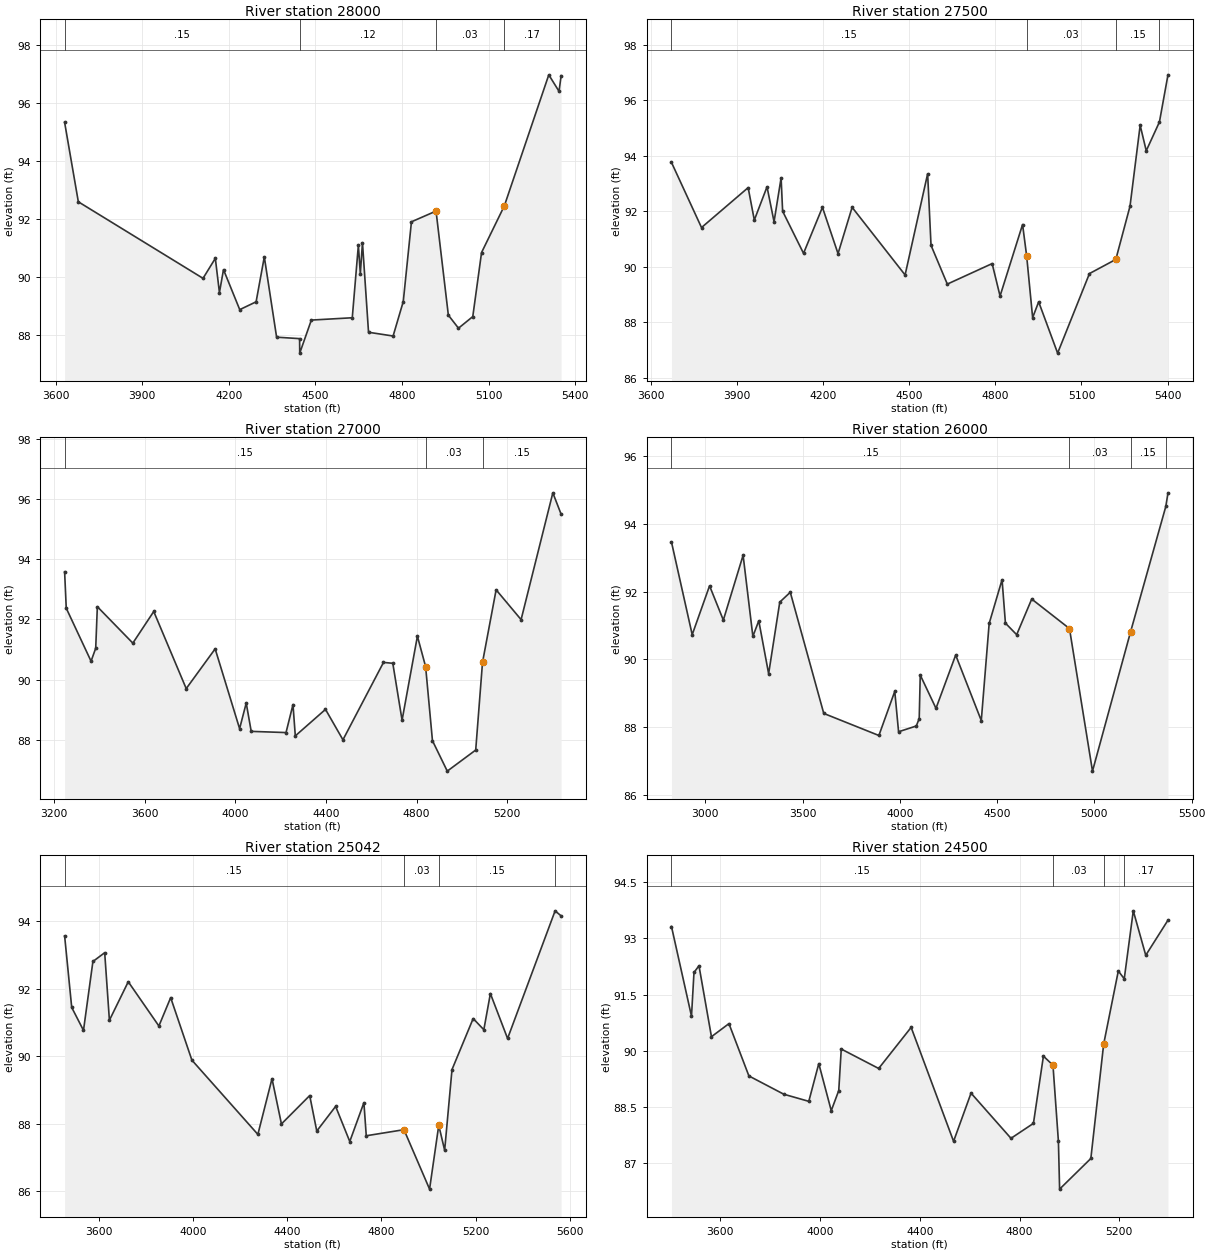
Type RM Length L Ch R = 1 ,28000   ,500,500,500
BEGIN DESCRIPTION:
WOODSONS GULLY 54.0
END DESCRIPTION:
XS GIS Cut Line= 3
      3872277.46     10040818.33      3871357.23     10039805.43
      3871302.81     10039458.88
#Sta/Elev= 30
  3631.5   95.33    3679   92.59  4110.8   89.95  4153.4   90.64  4167.6   89.46
  4181.7   90.25  4237.9   88.87  4294.6   89.14    4323   90.69  4365.6   87.92
  4445.2   87.87  4445.7   87.37  4485.9   88.51  4627.6   88.59  4648.7   91.09
  4655.5   90.11  4662.9   91.18  4683.9   88.09    4769   87.96  4804.2   89.15
  4832.5    91.9  4917.7   92.27  4960.3   88.68  4995.4   88.23  5044.9   88.63
  5075.3   90.84  5154.2   92.45  5308.1   96.97  5343.6    96.4  5350.8   96.94
#Mann= 5 ,-1 , 0
  3631.5     .15       0  4445.2     .12       0  4917.7     .03       0
  5154.2     .17       0  5343.6     .15       0
Bank Sta=4917.7,5154.2
XS Rating Curve= 0 ,0
Exp/Cntr=0.3,0.1

Type RM Length L Ch R = 1 ,27500   ,500,500,500
BEGIN DESCRIPTION:
WOODSONS GULLY 53.0
END DESCRIPTION:
XS GIS Cut Line= 4
       3872472.1     10040960.22      3872149.69     10040130.72
      3871855.91     10039803.77      3871571.65     10039520.08
#Sta/Elev= 30
  3670.5   93.76  3775.2   91.41  3937.8   92.85  3959.3   91.68  4003.6   92.88
  4028.1   91.62  4052.7    93.2    4058      92  4130.9   90.48  4196.8   92.14
  4251.2   90.47  4300.3   92.14    4485    89.7  4563.6   93.35  4575.4   90.77
  4632.2   89.37  4788.5   90.11  4816.1   88.94  4894.6   91.52  4908.8   90.39
  4929.7   88.16  4950.7   88.73  5016.8   86.88  5127.8   89.75  5219.7   90.26
  5269.2   92.18  5304.6    95.1  5325.8   94.18  5371.8   95.22  5401.6   96.92
#Mann= 4 ,-1 , 0
  3670.5     .15       0  4908.8     .03       0  5219.7     .15       0
  5371.8     .17       0
Bank Sta=4908.8,5219.7
XS Rating Curve= 0 ,0
Exp/Cntr=0.3,0.1

Type RM Length L Ch R = 1 ,27000   ,1000,1000,1000
BEGIN DESCRIPTION:
WOODSONS GULLY 52.0
END DESCRIPTION:
XS GIS Cut Line= 4
      3872623.99     10040935.03      3872292.83     10039413.99
      3872098.24     10039434.12      3871661.41     10039421.84
#Sta/Elev= 30
  3247.7   93.58  3254.9   92.37  3364.3   90.61  3384.8   91.04    3392   92.42
  3548.5   91.21  3640.7   92.26  3783.9    89.7  3911.5   91.02  4019.3   88.37
  4048.5   89.22  4070.5   88.28    4224   88.24  4254.7   89.17  4264.9   88.13
    4398   89.01    4475      88  4653.8   90.57  4694.8   90.54  4735.7   88.65
  4803.3   91.44  4839.5   90.43  4869.7   87.97    4935   86.96  5060.4   87.66
  5090.4   90.57  5150.4   92.98  5260.5   91.99  5400.5    96.2    5437   95.49
#Mann= 3 , 0 , 0
  3247.7     .15       0  4839.5     .03       0  5090.4     .15       0
Bank Sta=4839.5,5090.4
XS Rating Curve= 0 ,0
Exp/Cntr=0.3,0.1

Type RM Length L Ch R = 1 ,26000   ,958,958,958
BEGIN DESCRIPTION:
WOODSONS GULLY 50.0
END DESCRIPTION:
XS GIS Cut Line= 5
      3872628.77     10040924.42      3872367.23     10039245.12
      3872293.29     10039025.43      3872251.15     10038786.86
      3872245.87      10038408.6
#Sta/Elev= 30
  2826.4   93.46  2932.9   90.73  3022.1   92.17  3092.9   91.16  3194.5   93.07
  3244.7   90.68  3275.1   91.14  3325.7   89.58    3383   91.69    3437   91.98
  3609.1   88.41  3892.4   87.76    3974   89.06  3993.6   87.87  4084.7   88.04
  4099.7   88.26    4105   89.54  4185.9   88.56  4287.1   90.13  4418.7    88.2
  4459.2   91.06  4525.5   92.35  4542.8   91.07  4600.6   90.73  4677.9   91.78
    4872   90.91  4990.3   86.71  5185.8   90.81  5367.2   94.51  5378.3   94.91
#Mann= 4 ,-1 , 0
  2826.4     .15       0    4872     .03       0  5185.8     .15       0
  5367.2     .11       0
Bank Sta=4872,5185.8
XS Rating Curve= 0 ,0
Exp/Cntr=0.3,0.1

Type RM Length L Ch R = 1 ,25042   ,542,542,542
BEGIN DESCRIPTION:
WOODSONS GULLY 48.0
END DESCRIPTION:
XS GIS Cut Line= 3
      3872658.78     10040901.17       3872680.4     10039357.98
      3872834.35     10038815.54
#Sta/Elev= 30
  3455.5   93.57  3485.6   91.45  3535.6   90.77  3575.6   92.81  3625.6   93.07
  3645.6   91.07  3725.6   92.21  3855.6    90.9  3905.6   91.74  3995.6   89.89
  4275.7   87.69  4335.7   89.34  4375.7      88  4495.7   88.84  4525.7   87.79
  4605.7   88.52  4665.7   87.48  4725.7   88.63  4735.7   87.65  4895.7   87.83
  5004.4   86.07  5043.4   87.96  5068.4   87.22  5099.6   89.61  5189.4   91.12
  5234.7   90.79  5262.5   91.86  5335.5   90.53  5537.2   94.31  5562.7   94.16
#Mann= 4 ,-1 , 0
  3455.5     .15       0  4895.7     .03       0  5043.4     .15       0
  5537.2     .17       0
Bank Sta=4895.7,5043.4
XS Rating Curve= 0 ,0
Exp/Cntr=0.3,0.1

Type RM Length L Ch R = 1 ,24500   ,505,505,505
BEGIN DESCRIPTION:
WOODSONS GULLY 47.0
END DESCRIPTION:
XS GIS Cut Line= 3
      3873188.69     10040791.22       3873139.9     10039196.86
       3873149.6     10038801.98
#Sta/Elev= 30
  3404.9   93.32  3485.1   90.92  3495.1   92.09  3515.1   92.27  3565.1   90.37
  3635.2   90.72  3715.2   89.32  3855.3   88.83  3955.3   88.64  3995.3   89.65
  4045.3   88.39  4075.4   88.93  4085.4   90.04  4235.4   89.52  4365.5   90.62
  4535.6   87.57  4605.6   88.86  4765.7   87.65  4855.7   88.05  4895.7   89.85
    4934 89.6078  4955.8   87.57  4960.6   86.29  5085.8   87.11  5137.2 90.1712
  5195.9   92.13  5219.7   91.92  5255.9   93.74  5305.9   92.55    5395   93.49
#Mann= 4 ,-1 , 0
  3404.9     .15       0    4934     .03       0  5137.2     .15       0
  5219.7     .17       0
Bank Sta=4934,5137.2
XS Rating Curve= 0 ,0
Exp/Cntr=0.3,0.1

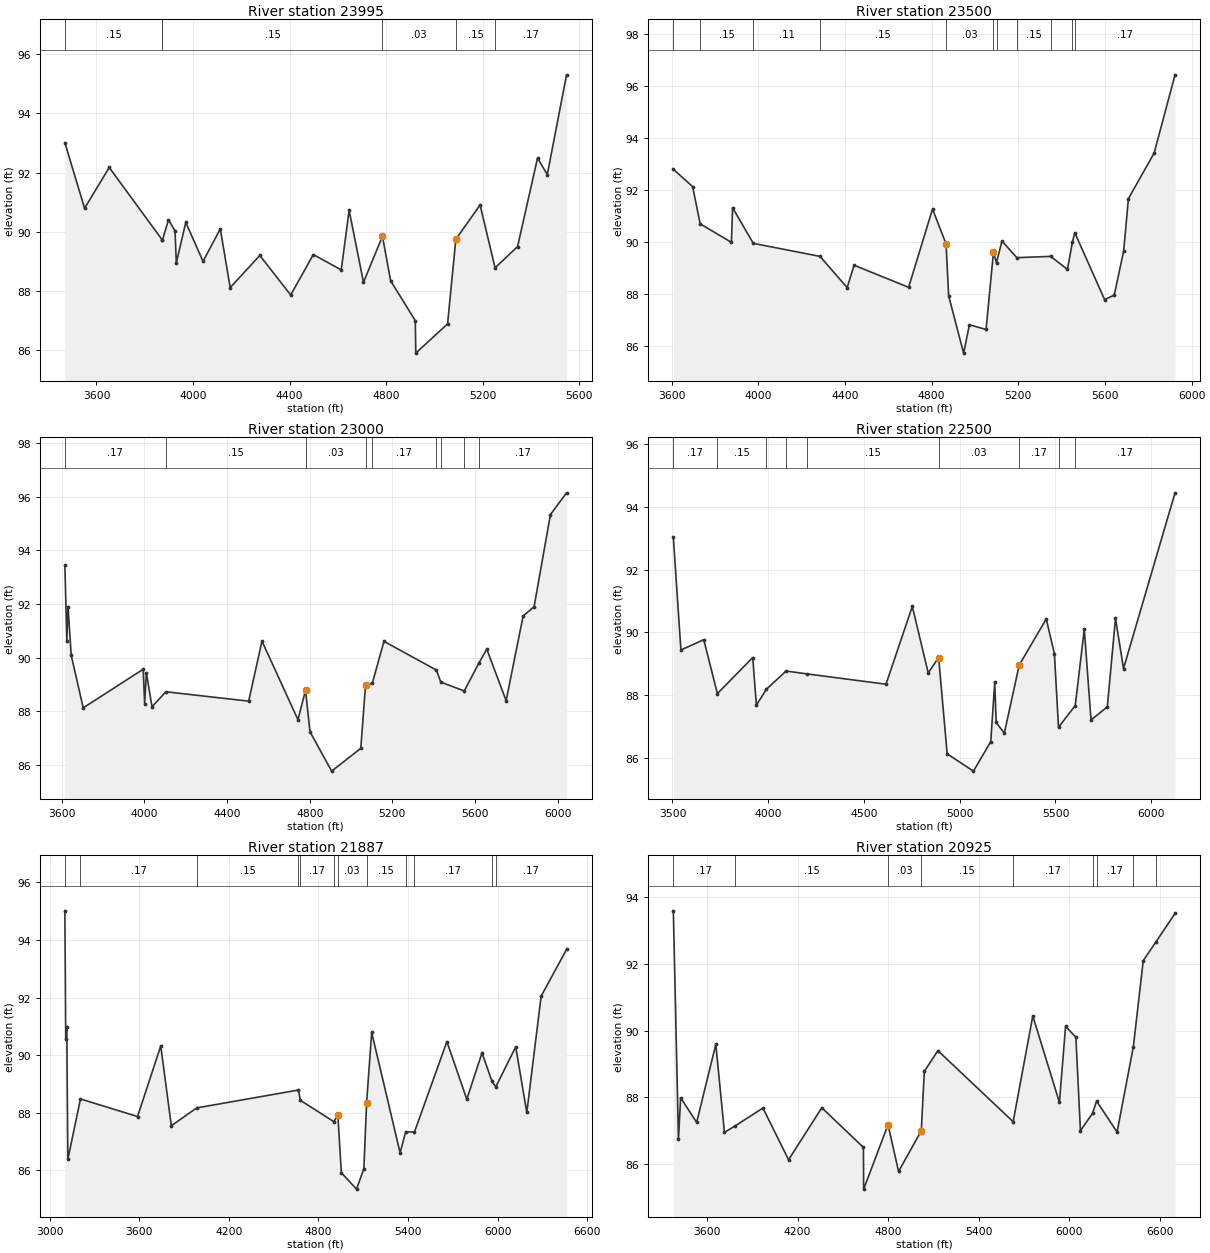
Type RM Length L Ch R = 1 ,23995   ,495,495,495
BEGIN DESCRIPTION:
WOODSONS GULLY 46.0
END DESCRIPTION:
XS GIS Cut Line= 3
      3873226.87     10040790.82      3873546.59     10039298.19
      3873403.13     10038765.04
#Sta/Elev= 30
  3469.3   93.01  3550.9   90.79  3653.1   92.17  3873.3   89.71  3873.5   89.71
  3898.6    90.4  3925.8   90.02    3931   88.94  3970.2   90.31  4041.7   88.99
  4113.3   90.09  4154.2    88.1    4277   89.19  4404.9   87.85  4498.7   89.22
  4614.4    88.7    4647   90.72  4706.5   88.28  4785.1   89.84    4819   88.33
  4921.3   86.98  4923.1   85.88  5054.9   86.87  5089.2   89.74  5189.6    90.9
  5251.7   88.77  5344.9   89.49  5427.7   92.49    5468   91.93  5547.9   95.31
#Mann= 6 ,-1 , 0
  3469.3     .15       0  3873.3     .11       0  3873.5     .15       0
  4785.1     .03       0  5089.2     .15       0  5251.7     .17       0
Bank Sta=4785.1,5089.2
XS Rating Curve= 0 ,0
Exp/Cntr=0.3,0.1

Type RM Length L Ch R = 1 ,23500   ,500,500,500
BEGIN DESCRIPTION:
WOODSONS GULLY 45.0
END DESCRIPTION:
XS GIS Cut Line= 4
      3873409.76     10040784.79      3873887.35     10039476.86
      3873944.49     10039361.15      3873559.07     10038666.69
#Sta/Elev= 30
  3607.6   92.81  3696.7   92.14  3731.5   90.71  3875.7      90    3881   91.33
  3976.8   89.96  4284.5   89.46    4410   88.26  4441.9   89.12  4693.7   88.27
  4803.9   91.28  4866.4   89.94  4878.4   87.94  4947.5   85.74  4974.2   86.83
  5051.1   86.65  5085.1   89.61  5099.3   89.22  5124.5   90.05  5193.2   89.41
  5349.1   89.46  5426.6   88.96  5449.7   90.01  5460.7   90.37  5598.1    87.8
  5642.8   87.97  5686.3   89.67  5708.1   91.68  5826.8   93.43  5923.3   96.44
#Mann= 11 ,-1 , 0
  3607.6     .17       0  3731.5     .15       0  3976.8     .11       0
  4284.5     .15       0  4866.4     .03       0  5085.1     .15       0
  5099.3     .17       0  5193.2     .15       0  5349.1     .17       0
  5449.7     .15       0  5460.7     .17       0
Bank Sta=4866.4,5085.1
XS Rating Curve= 0 ,0
Exp/Cntr=0.3,0.1

Type RM Length L Ch R = 1 ,23000   ,500,500,500
BEGIN DESCRIPTION:
WOODSONS GULLY 44.0
END DESCRIPTION:
XS GIS Cut Line= 5
      3874909.77     10040600.73      3874188.24     10039418.16
      3874130.33     10039341.58      3873951.44     10039309.07
      3873593.78     10038631.96
#Sta/Elev= 30
  3614.7   93.46  3624.1   90.64  3629.9   91.91  3645.4   90.09  3703.5   88.13
  3993.9   89.57  4000.9   88.29  4009.3   89.44  4036.5   88.17  4103.5   88.73
  4504.6   88.38  4568.9   90.62  4743.1   87.69  4779.9   88.79  4801.2   87.24
  4906.3   85.77  5047.4   86.62  5070.3   88.98  5103.2   89.05  5159.5   90.61
  5413.2   89.54  5434.8   89.09  5548.3   88.76  5619.8   89.81  5657.3   90.32
    5751    88.4  5833.4   91.56  5886.3    91.9  5965.5   95.34  6043.6   96.15
#Mann= 9 ,-1 , 0
  3614.7     .17       0  4103.5     .15       0  4779.9     .03       0
  5070.3     .15       0  5103.2     .17       0  5413.2     .15       0
  5434.8     .17       0  5548.3     .15       0  5619.8     .17       0
Bank Sta=4779.9,5070.3
XS Rating Curve= 0 ,0
Exp/Cntr=0.3,0.1

Type RM Length L Ch R = 1 ,22500   ,613,613,613
BEGIN DESCRIPTION:
WOODSONS GULLY 43.0
END DESCRIPTION:
XS GIS Cut Line= 3
      3875026.53     10040651.24      3874540.66     10039236.86
      3873708.55     10038480.79
#Sta/Elev= 30
  3504.5   93.03  3544.1   89.44  3663.3   89.77  3734.4   88.05  3919.1    89.2
  3938.2   87.68  3990.5   88.19  4093.1   88.77  4201.3   88.68  4614.9   88.35
  4752.4   90.83  4835.5   88.71  4889.8    89.2  4934.5   86.13  5071.6   85.58
    5162   86.52  5182.9   88.41  5190.3   87.13  5232.9   86.79  5310.6   88.96
  5451.9   90.43  5494.4   89.32  5515.8   86.98  5603.2   87.67  5650.5    90.1
  5685.7   87.21  5770.8   87.63  5813.4   90.45  5855.3   88.85  6124.3   94.45
#Mann= 9 ,-1 , 0
  3504.5     .17       0  3734.4     .15       0  3990.5     .11       0
  4093.1     .17       0  4201.3     .15       0  4889.8     .03       0
  5310.6     .17       0  5515.8     .15       0  5603.2     .17       0
Bank Sta=4889.8,5310.6
XS Rating Curve= 0 ,0
Exp/Cntr=0.3,0.1

Type RM Length L Ch R = 1 ,21887   ,962,962,962
BEGIN DESCRIPTION:
WOODSONS GULLY 42.0
END DESCRIPTION:
XS GIS Cut Line= 3
      3876375.29     10040521.67      3875028.24     10039184.85
      3873763.21     10038452.13
#Sta/Elev= 30
  3102.2   95.01  3107.9   90.56  3114.9   90.99    3122   86.38  3206.5   88.48
  3588.7   87.87  3744.3   90.32    3815   87.55  3985.4   88.17  4666.6   88.79
  4679.5   88.43  4904.1   87.69  4930.387.92886  4953.5   85.92  5055.4   85.35
  5104.5   86.06  5122.888.34515  5156.8   90.79  5347.1   86.61  5384.5   87.34
  5443.1   87.33  5660.5   90.47  5793.8   88.47  5895.7   90.08    5962    89.1
    5988    88.9  6121.4   90.29  6195.6   88.01  6291.7   92.05  6461.9   93.67
#Mann= 12 ,-1 , 0
  3102.2     .11       0  3206.5     .17       0  3985.4     .15       0
  4666.6     .11       0  4679.5     .17       0  4904.1     .15       0
  4930.3     .03       0  5122.8     .15       0  5384.5     .15       0
  5443.1     .17       0    5962     .15       0    5988     .17       0
Bank Sta=4930.3,5122.8
XS Rating Curve= 0 ,0
Exp/Cntr=0.3,0.1

Type RM Length L Ch R = 1 ,20925   ,1425,1425,1425
BEGIN DESCRIPTION:
WOODSONS GULLY 40.0
END DESCRIPTION:
XS GIS Cut Line= 5
      3876647.83     10039728.95      3875614.81     10038821.94
      3875378.24     10038746.86      3874614.81     10038754.23
      3873758.01     10038371.41
#Sta/Elev= 30
  3377.1   93.59  3411.1   86.74  3425.3   87.99  3531.6   87.25  3658.7   89.59
  3715.7   86.95  3788.3   87.15  3970.9   87.68  4140.8   86.13  4360.9   87.69
    4637    86.5  4638.3   85.25    4800   87.18  4869.8   85.78  5020.4      87
  5040.4   88.78  5130.4    89.4  5629.1   87.27  5759.4   90.44  5935.7   87.85
  5976.6   90.13  6044.9    89.8    6075      87  6155.1   87.52  6181.9   87.89
    6318   86.96  6425.8   89.52  6491.4    92.1  6575.6   92.66  6701.9   93.51
#Mann= 9 ,-1 , 0
  3377.1     .17       0  3788.3     .15       0    4800     .03       0
  5020.4     .15       0  5629.1     .17       0  6155.1     .15       0
  6181.9     .17       0  6425.8     .11       0  6575.6     .17       0
Bank Sta=4800,5020.4
XS Rating Curve= 0 ,0
Exp/Cntr=0.3,0.1