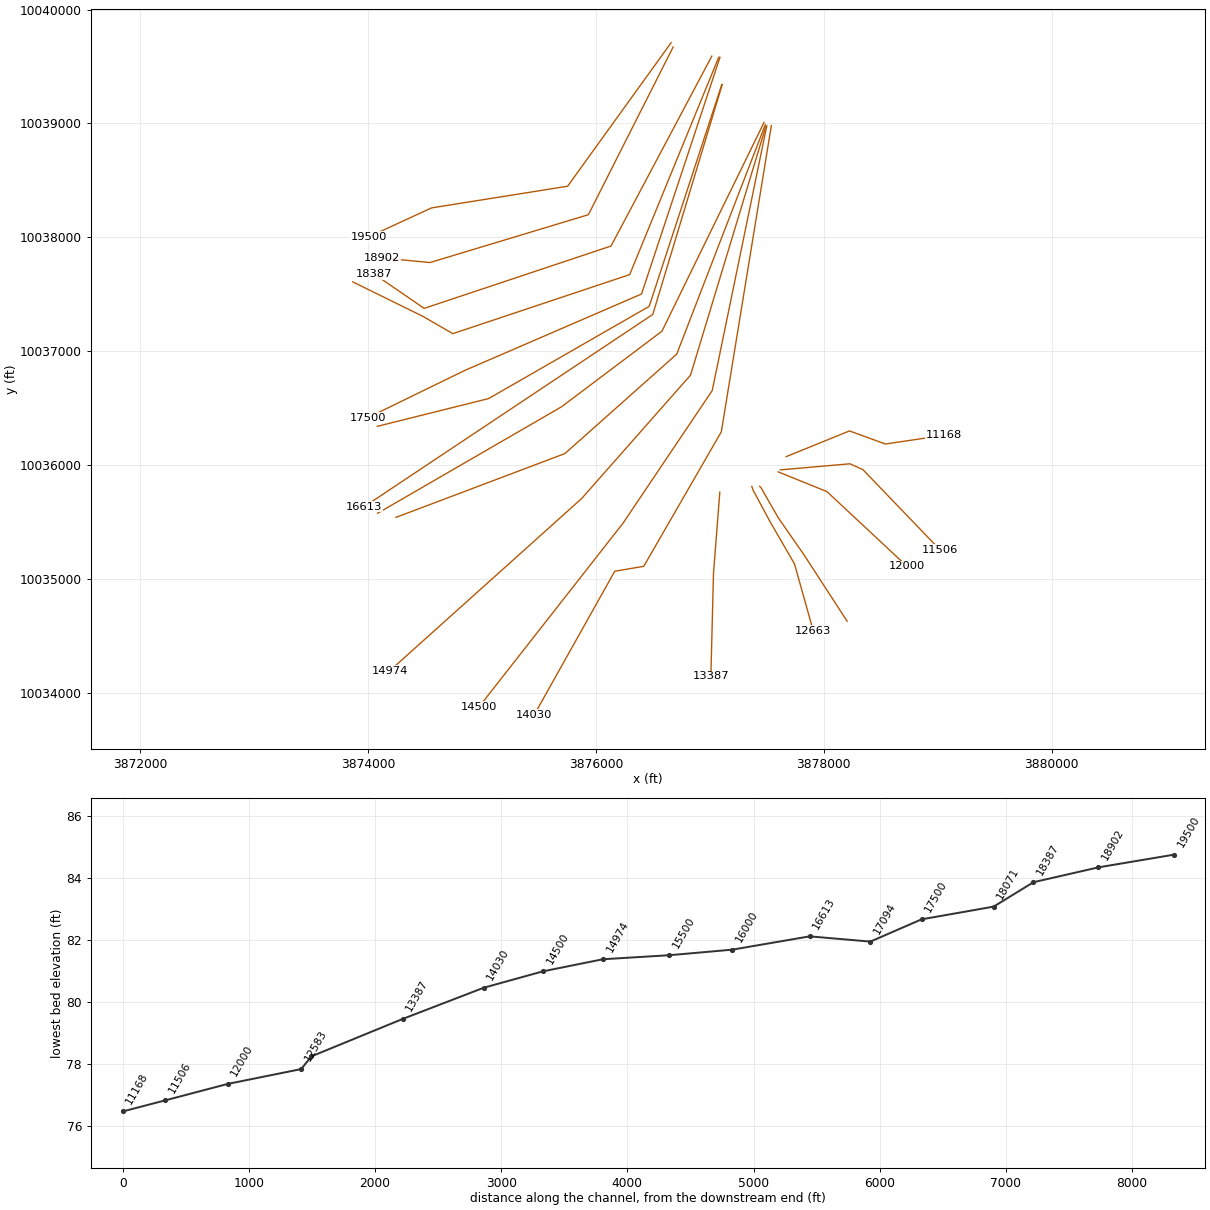
HEC-RAS study WOODSONS GULLY.prj: WOODSONS GULLY Base Level Engineering

--- WOODSONS GULLY.g01 (geometry) --- (continued)

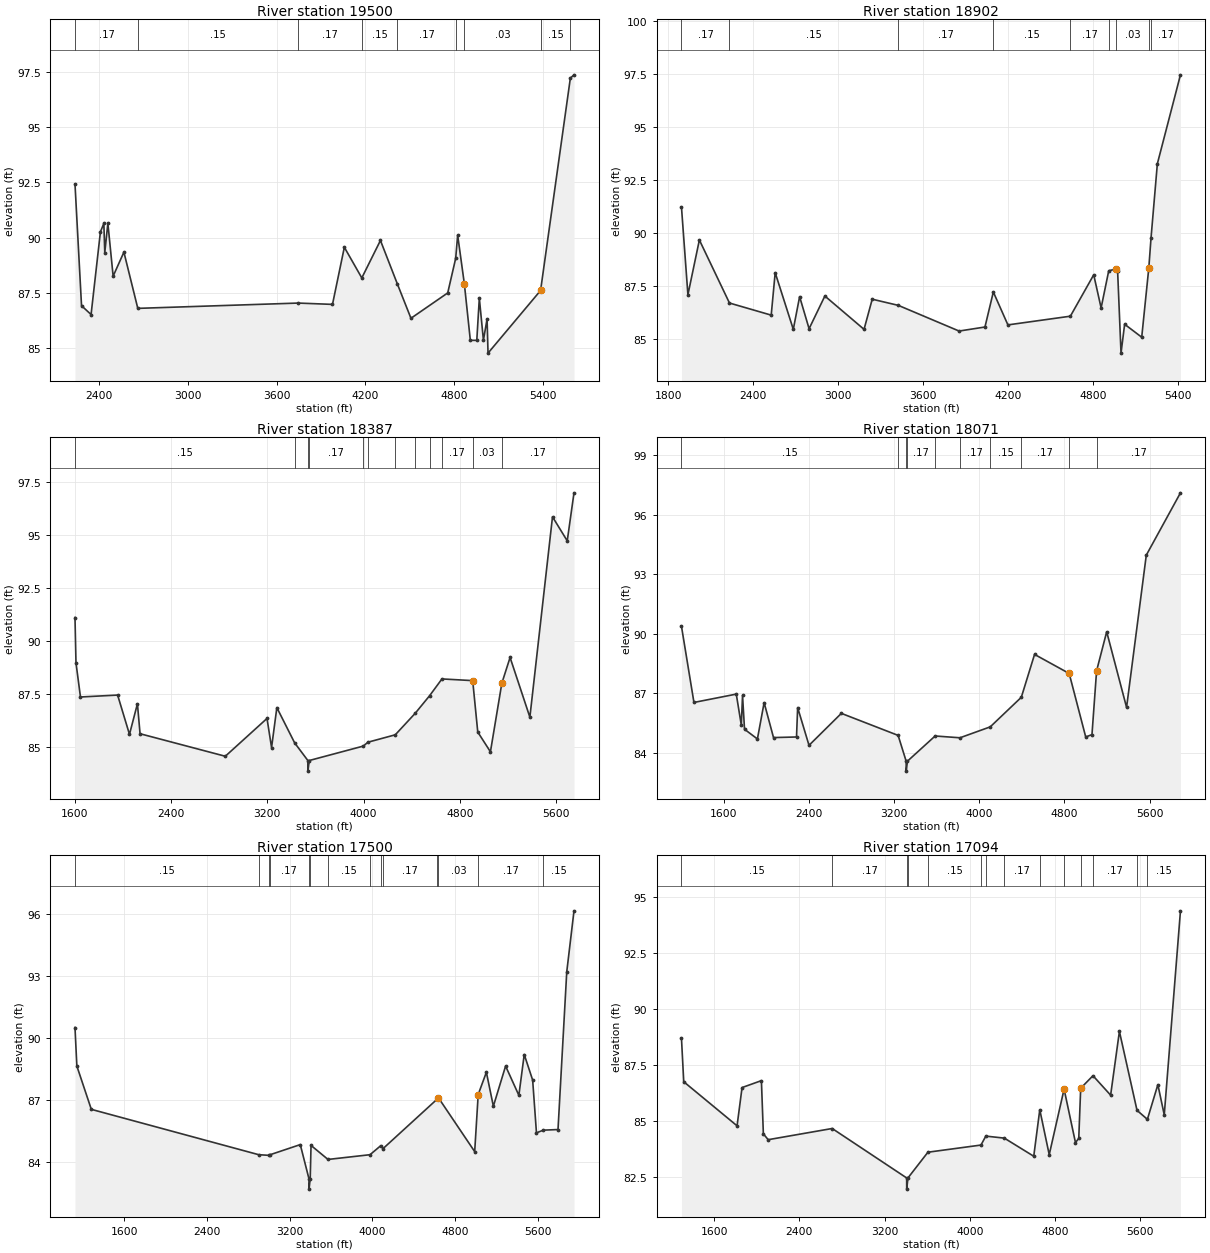
Type RM Length L Ch R = 1 ,19500   ,598,598,598
BEGIN DESCRIPTION:
WOODSONS GULLY 37.0
END DESCRIPTION:
XS GIS Cut Line= 4
      3876660.67     10039709.25      3875752.11     10038448.71
      3874558.24     10038258.36      3874004.33     10038003.08
#Sta/Elev= 30
  2237.2   92.43  2281.4   86.91  2345.9   86.51  2409.1   90.26  2432.2   90.64
  2438.5   89.32  2459.4   90.65    2495   88.25  2567.8   89.34  2661.7   86.79
  3745.9   87.03  3977.6   86.97  4057.7   89.56  4175.7   88.17  4301.7   89.87
  4415.9    87.9  4507.9   86.34  4756.4   87.49  4810.3   89.06  4823.6   90.11
  4868.7   87.91  4909.3   85.34  4952.9   85.34    4970   87.25  4997.7   85.35
  5022.4   86.31  5028.8   84.76    5384    87.6  5585.3   97.23  5609.9   97.38
#Mann= 9 ,-1 , 0
  2237.2     .17       0  2661.7     .15       0  3745.9     .17       0
  4175.7     .15       0  4415.9     .17       0  4810.3     .15       0
  4868.7     .03       0    5384     .15       0  5585.3     .15       0
Bank Sta=4868.7,5384
XS Rating Curve= 0 ,0
Exp/Cntr=0.3,0.1

Type RM Length L Ch R = 1 ,18902   ,515,515,515
BEGIN DESCRIPTION:
WOODSONS GULLY 36.0
END DESCRIPTION:
XS GIS Cut Line= 4
       3876678.5      10039671.8      3875934.23     10038198.49
      3874544.62     10037778.48      3874125.43      10037818.2
#Sta/Elev= 30
  1893.3   91.24  1938.9    87.1  2019.8   89.68  2232.3   86.71    2527   86.14
  2555.1   88.14    2683   85.47  2727.6   87.01  2794.5    85.5  2905.9   87.04
  3182.5   85.47  3240.3   86.89  3424.5    86.6  3853.6   85.39  4036.3   85.58
  4095.3   87.23  4198.3   85.68  4639.4   86.09  4804.2   88.04  4856.4   86.48
  4910.2   88.23  4960.9   88.31    4973   88.21    4997   84.35  5022.5   85.71
  5143.1    85.1  5193.3   88.37  5208.8   89.77  5253.5   93.27  5416.7   97.46
#Mann= 9 ,-1 , 0
  1893.3     .17       0  2232.3     .15       0  3424.5     .17       0
  4095.3     .15       0  4639.4     .17       0  4910.2     .15       0
  4960.9     .03       0  5193.3     .15       0  5208.8     .17       0
Bank Sta=4960.9,5193.3
XS Rating Curve= 0 ,0
Exp/Cntr=0.3,0.1

Type RM Length L Ch R = 1 ,18387   ,316,316,316
BEGIN DESCRIPTION:
WOODSONS GULLY 35.0
END DESCRIPTION:
XS GIS Cut Line= 5
       3877017.8     10039591.24      3876132.93     10037923.33
      3874847.36     10037494.19      3874492.97     10037376.01
      3874054.98      10037676.8
#Sta/Elev= 30
  1601.3    91.1  1609.5   88.97  1646.8   87.36  1955.7   87.45  2054.3    85.6
  2120.3   87.04  2142.2   85.63  2850.9   84.57  3197.6   86.35  3235.4   84.98
  3279.4   86.86  3427.3    85.2  3537.1   84.37  3537.6   83.87  3548.9   84.37
  3998.8   85.05  4035.8   85.23  4263.9   85.58  4429.2   86.59  4549.2   87.42
  4651.9   88.21  4907.4   88.13  4949.6   85.71  5054.9   84.78  5149.788.00685
  5218.2   89.22  5382.8   86.41  5570.9   95.84  5693.4   94.71  5749.6   96.97
#Mann= 12 ,-1 , 0
  1601.3     .15       0  3427.3     .17       0  3537.1     .12       0
  3548.9     .17       0  3998.8     .15       0  4035.8     .17       0
  4263.9     .15       0  4429.2     .17       0  4549.2     .15       0
  4651.9     .17       0  4907.4     .03       0  5149.7     .17       0
Bank Sta=4907.4,5149.7
XS Rating Curve= 0 ,0
Exp/Cntr=0.3,0.1

Type RM Length L Ch R = 1 ,18071   ,571,571,571
BEGIN DESCRIPTION:
WOODSONS GULLY 34.0
END DESCRIPTION:
XS GIS Cut Line= 5
      3877078.59     10039581.51      3876296.88     10037672.53
      3874744.52     10037153.95      3874483.38     10037305.01
      3873866.32     10037608.58
#Sta/Elev= 30
  1200.8   90.38  1318.1   86.54  1715.9   86.96  1763.2    85.4  1774.7   86.89
  1793.3   85.19  1914.5    84.7  1977.6   86.53  2065.8   84.77  2281.9    84.8
  2292.6   86.28  2399.4   84.38  2703.3   85.99  3236.8   84.88  3312.2   83.58
  3312.7   83.08    3324   83.58  3584.5   84.85  3817.9   84.76  4102.3   85.31
  4394.3    86.8  4518.7   88.96  4844.1      88  4999.5    84.8  5058.2   84.92
  5101.5   88.13  5196.5    90.1  5383.3   86.29  5568.6   93.96  5889.7    97.1
#Mann= 10 ,-1 , 0
  1200.8     .15       0  3236.8     .17       0  3312.2     .12       0
    3324     .17       0  3584.5     .15       0  3817.9     .17       0
  4102.3     .15       0  4394.3     .17       0  4844.1     .03       0
  5101.5     .17       0
Bank Sta=4844.1,5101.5
XS Rating Curve= 0 ,0
Exp/Cntr=0.3,0.1

Type RM Length L Ch R = 1 ,17500   ,406,406,406
BEGIN DESCRIPTION:
WOODSONS GULLY 33.0
END DESCRIPTION:
XS GIS Cut Line= 4
      3877089.32     10039580.99      3876400.83     10037502.22
      3874852.78     10036832.32       3873998.4     10036416.04
#Sta/Elev= 30
  1123.4   90.51  1141.5   88.64  1281.3   86.54  2900.7   84.34    2997   84.31
  3005.6   84.33  3302.7   84.83  3386.7   83.17  3387.2   82.67  3398.8   83.17
  3406.7   84.79  3570.8   84.11  3977.4   84.34  4081.7   84.78  4104.3   84.64
  4625.6   87.03  4639.2    87.1  4989.8   84.49 5023.7387.25941  5102.8   88.34
  5170.4   86.69  5288.7   88.64  5417.1   87.22    5469    89.2  5550.5   87.96
  5587.3    85.4  5653.1   85.53  5795.7   85.56  5880.3   93.21  5950.4   96.17
#Mann= 14 ,-1 , 0
  1123.4     .15       0  2900.7     .17       0    2997     .15       0
  3005.6     .17       0  3386.7     .12       0  3398.8     .17       0
  3570.8     .15       0  3977.4     .17       0  4081.7     .15       0
  4104.3     .17       0  4625.6     .15       0  4639.2     .03       0
 5023.73     .17       0  5653.1     .15       0
Bank Sta=4639.2,5023.73
XS Rating Curve= 0 ,0
Exp/Cntr=0.3,0.1

Type RM Length L Ch R = 1 ,17094   ,481,481,481
BEGIN DESCRIPTION:
WOODSONS GULLY 32.0
END DESCRIPTION:
XS GIS Cut Line= 4
      3877105.21     10039341.38       3876468.1     10037393.71
       3875058.7     10036583.78      3874082.13     10036340.02
#Sta/Elev= 30
  1294.4    88.7  1315.8   86.75  1816.1   84.78  1862.9   86.49  2044.4    86.8
  2062.8   84.42  2108.1   84.16  2708.5   84.66  3407.1   82.45  3407.6   81.95
  3419.2   82.45  3606.5    83.6  4104.2   83.92  4149.6   84.32  4323.4   84.23
  4599.3   83.42  4655.9    85.5  4744.5   83.49    4884   86.42  4990.7   84.03
  5021.6   84.22  5039.7   86.46    5155   87.02  5320.5   86.15  5402.9      89
  5568.2   85.47  5665.4   85.07  5763.7   86.62  5823.6   85.27  5975.7   94.39
#Mann= 14 ,-1 , 0
  1294.4     .15       0  2708.5     .17       0  3407.1     .12       0
  3419.2     .17       0  3606.5     .15       0  4104.2     .17       0
  4149.6     .15       0  4323.4     .17       0  4655.9     .15       0
    4884     .03       0  5039.7     .15       0    5155     .17       0
  5568.2     .11       0  5665.4     .15       0
Bank Sta=4884,5039.7
XS Rating Curve= 0 ,0
Exp/Cntr=0.3,0.1

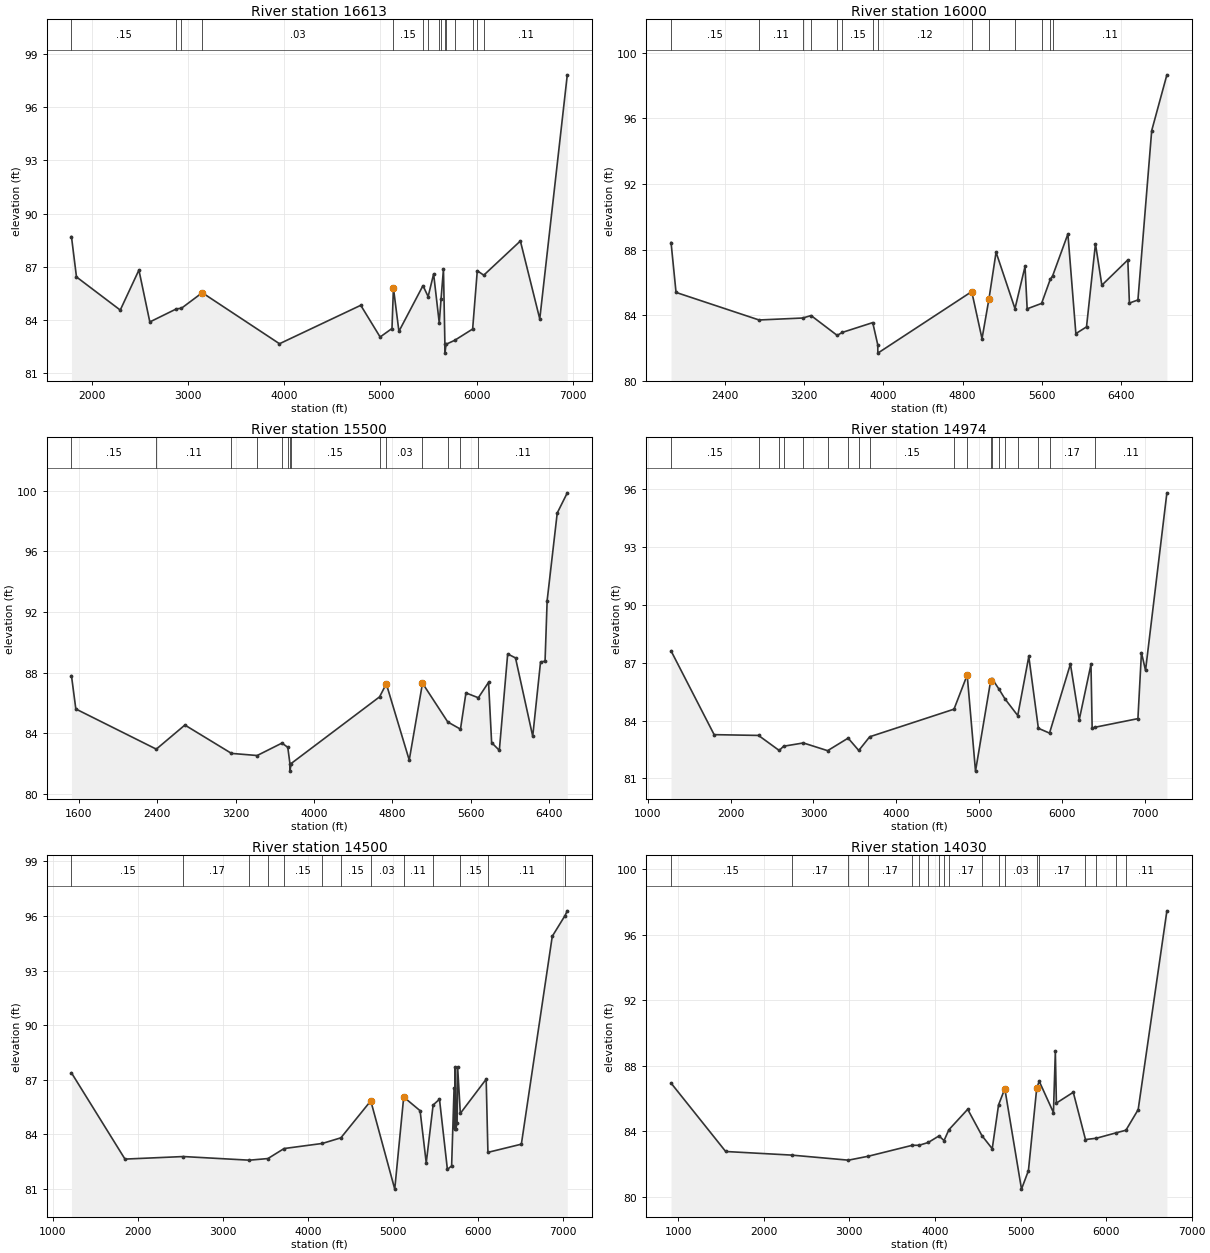
Type RM Length L Ch R = 1 ,16613   ,613,613,613
BEGIN DESCRIPTION:
WOODSONS GULLY 31.0
END DESCRIPTION:
XS GIS Cut Line= 3
      3877109.13     10039342.07      3876499.66     10037322.54
      3873968.35     10035635.08
#Sta/Elev= 30
  1789.3    88.7  1841.5   86.42  2296.3   84.55  2490.2   86.81  2603.5   83.88
  2880.6   84.62  2931.3   84.65  3148.2   85.53  3950.8   82.65  4795.1   84.82
  4996.4   83.03  5119.6   83.51  5134.6    85.8  5191.7   83.35  5441.6   85.93
  5495.2   85.31  5552.3   86.59  5610.8   83.82  5629.7    85.2  5654.4   86.87
  5669.4   82.62  5669.9   82.12  5681.5   82.62  5770.1   82.84  5957.6   83.48
  6005.8   86.77  6073.2   86.52  6453.6   88.45    6655   84.05    6941   97.83
#Mann= 15 ,-1 , 0
  1789.3     .15       0  2880.6     .17       0  2931.3     .15       0
  3148.2     .03       0  5134.6     .15       0  5441.6     .17       0
  5495.2     .11       0  5610.8     .15       0  5629.7     .11       0
  5669.4     .12       0  5681.5     .11       0  5770.1     .15       0
  5957.6     .11       0  6005.8     .15       0  6073.2     .11       0
Bank Sta=3148.2,5134.6
XS Rating Curve= 0 ,0
Exp/Cntr=0.3,0.1

Type RM Length L Ch R = 1 ,16000   ,500,500,500
BEGIN DESCRIPTION:
WOODSONS GULLY 30.0
END DESCRIPTION:
XS GIS Cut Line= 4
      3877476.02     10039009.03      3876580.46     10037175.83
      3875698.24     10036511.39      3874084.47     10035576.53
#Sta/Elev= 30
  1855.3   88.43  1905.6   85.39  2744.5   83.71  3186.3   83.83    3270   83.98
  3533.9   82.77    3584   82.95    3893   83.55    3944   82.19  3944.5   81.69
  4893.3   85.44  4997.1   82.57  5067.2   84.99  5139.1   87.84  5330.1    84.4
  5431.7   86.97  5453.2   84.39    5599   84.72  5686.2   86.18  5710.6    86.4
  5864.9   88.95  5945.3   82.88  6052.9   83.29  6143.3   88.35  6207.9   85.83
  6470.4   87.37  6486.2   84.74  6572.3   84.93  6711.5   95.25    6865   98.65
#Mann= 14 ,-1 , 0
  1855.3     .15       0  2744.5     .11       0  3186.3     .17       0
    3270     .11       0  3533.9     .17       0    3584     .15       0
    3893     .17       0    3944     .12       0  4893.3     .03       0
  5067.2     .17       0  5330.1     .15       0    5599     .11       0
  5686.2     .17       0  5710.6     .11       0
Bank Sta=4893.3,5067.2
XS Rating Curve= 0 ,0
Exp/Cntr=0.3,0.1

Type RM Length L Ch R = 1 ,15500   ,526,526,526
BEGIN DESCRIPTION:
WOODSONS GULLY 29.0
END DESCRIPTION:
XS GIS Cut Line= 4
      3877487.82     10038990.68      3876709.86     10036974.27
      3875728.24     10036100.74      3874245.51     10035540.33
#Sta/Elev= 30
  1524.7   87.81  1569.4   85.61  2390.5   82.96  2682.4   84.55  3157.8   82.68
  3420.1   82.54  3673.1   83.36  3732.5   83.08  3754.3   82.01  3754.8   81.51
  3766.4   82.01  4669.4   86.41  4737.9   87.27    4972   82.24  5107.3   87.31
  5365.6   84.75  5494.9   84.28  5550.8   86.67  5677.4   86.35  5781.5   87.37
  5812.9   83.39  5891.5   82.88  5976.7   89.24  6056.6   88.98  6232.3   83.81
  6312.1   88.71  6358.1   88.76  6379.5   92.76  6482.5   98.54  6585.1   99.87
#Mann= 14 ,-1 , 0
  1524.7     .15       0  2390.5     .11       0  3157.8     .17       0
  3420.1     .15       0  3673.1     .17       0  3732.5     .15       0
  3754.3     .12       0  3766.4     .15       0  4669.4     .17       0
  4737.9     .03       0  5107.3     .17       0  5365.6     .15       0
  5494.9     .17       0  5677.4     .11       0
Bank Sta=4737.9,5107.3
XS Rating Curve= 0 ,0
Exp/Cntr=0.3,0.1

Type RM Length L Ch R = 1 ,14974   ,474,474,474
BEGIN DESCRIPTION:
WOODSONS GULLY 28.0
END DESCRIPTION:
XS GIS Cut Line= 4
      3877490.56     10038968.78        3876831.     10036789.89
      3875876.65     10035707.31       3874191.4     10034193.55
#Sta/Elev= 30
  1281.1   87.61  1801.1   83.27  2336.8   83.23  2586.7   82.45  2639.3   82.67
  2878.1   82.84    3171   82.44  3418.5   83.09  3546.8   82.45  3678.8   83.16
  4696.4   84.59  4855.6   86.36    4956   81.38  5138.8   86.06  5158.3   86.15
  5240.7   85.62    5312   85.12  5465.7   84.26  5599.3   87.32  5714.7    83.6
  5849.4   83.35  6101.6   86.93  6208.5   84.05  6349.8   86.91    6364   83.61
  6394.4   83.65  6916.4    84.1    6959   87.52  7008.3    86.6  7266.1    95.8
#Mann= 19 ,-1 , 0
  1281.1     .15       0  2336.8     .11       0  2586.7     .17       0
  2639.3     .11       0  2878.1     .17       0    3171     .15       0
  3418.5     .11       0  3546.8     .17       0  3678.8     .15       0
  4696.4     .17       0  4855.6     .03       0  5138.8     .15       0
  5158.3     .17       0  5240.7     .11       0    5312     .15       0
  5465.7     .17       0  5714.7     .15       0  5849.4     .17       0
  6394.4     .11       0
Bank Sta=4855.6,5138.8
XS Rating Curve= 0 ,0
Exp/Cntr=0.3,0.1

Type RM Length L Ch R = 1 ,14500   ,470,470,470
BEGIN DESCRIPTION:
WOODSONS GULLY 27.0
END DESCRIPTION:
XS GIS Cut Line= 4
      3877500.31     10038979.23      3877021.43     10036654.23
      3876237.29     10035487.81      3874974.64     10033876.24
#Sta/Elev= 30
  1220.7   87.38  1849.6   82.64  2535.3   82.78    3312   82.58  3529.6   82.67
  3719.4   83.22    4169    83.5  4387.1   83.81    4738   85.84  5019.7   80.99
    5125   86.05  5317.5    85.3  5389.7   82.43  5470.6   85.61  5545.4   85.93
  5638.5   82.07  5688.2   82.27  5717.1   86.56  5723.5   84.27  5731.6    87.7
  5737.9   84.31  5752.4   84.65  5758.7   87.69  5790.3   85.15  6094.1   87.03
  6114.6   83.01  6507.6   83.46  6870.8   94.88  7020.7   96.02  7047.3   96.28
#Mann= 13 ,-1 , 0
  1220.7     .15       0  2535.3     .17       0    3312     .11       0
  3529.6     .17       0  3719.4     .15       0    4169     .17       0
  4387.1     .15       0    4738     .03       0    5125     .11       0
  5470.6     .17       0  5790.3     .15       0  6114.6     .11       0
  7020.7     .17       0
Bank Sta=4738,5125
XS Rating Curve= 0 ,0
Exp/Cntr=0.3,0.1

Type RM Length L Ch R = 1 ,14030   ,643,643,643
BEGIN DESCRIPTION:
WOODSONS GULLY 26.0
END DESCRIPTION:
XS GIS Cut Line= 5
      3877540.24     10038981.02      3877101.17      10036292.1
      3876420.35     10035110.64      3876165.61     10035067.22
      3875458.05     10033804.71
#Sta/Elev= 30
   916.7   86.94    1555   82.76  2324.6   82.54    2989   82.23    3221   82.47
  3736.2   83.14    3815   83.14  3921.5   83.31  4047.1   83.71  4106.8   83.43
  4163.2   84.09  4382.9   85.34  4549.2   83.73  4669.6   82.93  4743.6   85.61
  4816.7    86.6  5011.6   80.46  5092.6   81.59    5190   86.65    5219   87.05
  5384.9   85.14  5407.1   88.88  5419.3   85.72  5616.6   86.38  5759.2   83.49
  5886.1   83.57  6116.6    83.9  6231.8   84.06    6375   85.32  6710.5   97.47
#Mann= 19 ,-1 , 0
   916.7     .15       0  2324.6     .17       0    2989     .11       0
    3221     .17       0  3736.2     .15       0    3815     .11       0
  3921.5     .15       0  4047.1     .17       0  4106.8     .15       0
  4163.2     .17       0  4549.2     .15       0  4743.6     .17       0
  4816.7     .03       0    5190     .11       0    5219     .17       0
  5759.2     .15       0  5886.1     .11       0  6116.6     .15       0
  6231.8     .11       0
Bank Sta=4816.7,5190
XS Rating Curve= 0 ,0
Exp/Cntr=0.3,0.1

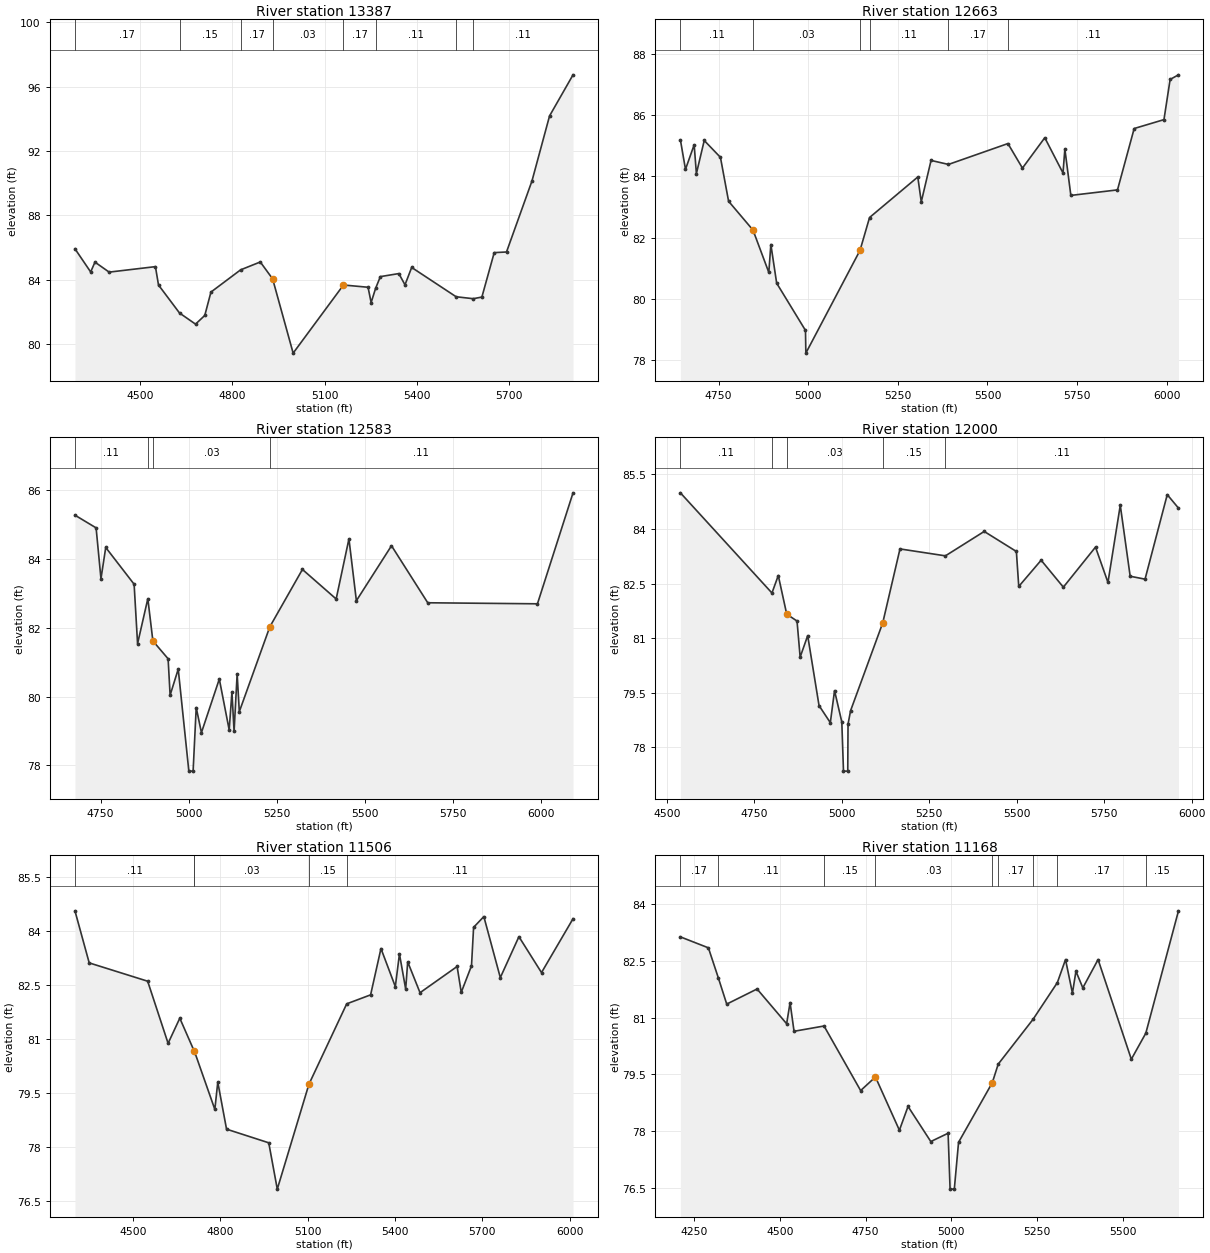
Type RM Length L Ch R = 1 ,13387   ,724,724,724
BEGIN DESCRIPTION:
WOODSONS GULLY 25.0
END DESCRIPTION:
XS GIS Cut Line= 3
      3877087.78     10035761.98      3877032.33     10035044.37
      3877009.39     10034144.81
#Sta/Elev= 30
  4287.7   85.93  4338.8   84.49  4352.8    85.1  4398.9   84.48  4549.4   84.82
  4559.4   83.68  4627.8   81.94  4679.8   81.25  4709.9   81.79  4729.9   83.24
  4826.3   84.62  4890.4   85.11  4930.5   84.06  4997.2   79.45  5160.8   83.68
  5240.8   83.54  5250.8   82.59  5265.3   83.47  5280.8    84.2  5340.9   84.39
  5360.9   83.69  5382.6   84.77  5527.2   82.95  5582.6   82.83  5610.9   82.93
    5651   85.69    5691   85.73  5773.8   90.14    5831   94.18  5907.3   96.73
#Mann= 8 ,-1 , 0
  4287.7     .17       0  4627.8     .15       0  4826.3     .17       0
  4930.5     .03       0  5160.8     .17       0  5265.3     .11       0
  5527.2     .17       0  5582.6     .11       0
Bank Sta=4930.5,5160.8
XS Rating Curve= 0 ,0
Exp/Cntr=0.3,0.1

Type RM Length L Ch R = 1 ,12663   ,80,80,80
BEGIN DESCRIPTION:
WOODSONS GULLY 24.0
END DESCRIPTION:
XS GIS Cut Line= 5
      3877368.71     10035811.59      3877382.29     10035775.13
      3877529.35      10035502.2      3877743.39     10035131.69
      3877908.67     10034542.04
#Sta/Elev= 30
  4643.5   85.19  4657.7   84.23  4681.9   85.03  4688.1   84.09    4710   85.17
  4755.2   84.62  4777.9   83.19    4846   82.25  4890.1   80.87  4895.8   81.78
    4912   80.52  4992.4   78.98  4993.4   78.24  5144.5   81.59  5171.1   82.66
  5305.6   83.98  5315.3   83.17  5342.6   84.52  5391.2   84.39    5557   85.07
  5597.5   84.27  5659.8   85.26  5710.6   84.11  5715.8   84.89  5732.5   83.38
  5862.6   83.56  5909.1   85.56  5992.2   85.85  6009.4   87.16  6032.7   87.31
#Mann= 6 ,-1 , 0
  4643.5     .11       0    4846     .03       0  5144.5     .15       0
  5171.1     .11       0  5391.2     .17       0    5557     .11       0
Bank Sta=4846,5144.5
XS Rating Curve= 0 ,0
Exp/Cntr=0.3,0.1

Type RM Length L Ch R = 1 ,12583   ,583,583,583
BEGIN DESCRIPTION:
WOODSONS GULLY 23.0
END DESCRIPTION:
XS GIS Cut Line= 5
        3877438.     10035812.62      3877449.42     10035800.88
       3877601.1     10035536.71      3877829.11     10035208.09
      3878205.54     10034627.99
#Sta/Elev= 30
  4677.5   85.28  4737.5   84.91  4751.3   83.43  4764.8   84.34  4845.3   83.27
  4855.1   81.54  4884.2   82.85  4898.5   81.62  4941.7    81.1  4947.4   80.04
  4970.4    80.8  5000.5   77.83  5012.6   77.83  5021.4   79.68  5036.2   78.95
  5086.9   80.51  5114.9   79.03  5122.7   80.13  5128.8   78.99  5137.5   80.66
  5143.6   79.56  5230.1   82.03  5322.6    83.7  5418.3   82.84  5454.5   84.59
  5475.6   82.79  5575.2   84.39    5678   82.73  5989.1    82.7    6090   85.93
#Mann= 4 ,-1 , 0
  4677.5     .11       0  4884.2     .15       0  4898.5     .03       0
  5230.1     .11       0
Bank Sta=4898.5,5230.1
XS Rating Curve= 0 ,0
Exp/Cntr=0.3,0.1

Type RM Length L Ch R = 1 ,12000   ,494,494,494
BEGIN DESCRIPTION:
WOODSONS GULLY 22.0
END DESCRIPTION:
XS GIS Cut Line= 3
      3877600.59     10035939.92      3878028.24      10035766.7
      3878731.56     10035109.78
#Sta/Elev= 30
  4538.6   84.99  4800.3   82.24  4818.4   82.72  4842.5   81.66    4872   81.47
  4880.9   80.48  4902.5   81.07  4934.9   79.15  4967.2   78.68  4979.2   79.56
    5000    78.7  5004.8   77.35    5017   77.35  5017.8   78.64  5025.1   79.01
    5117   81.42  5166.3   83.45  5296.2   83.26  5407.1   83.93    5499   83.38
  5505.8   82.42  5569.8   83.14  5633.3    82.4  5725.2    83.5  5760.8   82.53
    5796   84.65  5824.3    82.7  5866.8   82.62  5930.3   84.94  5962.4   84.57
#Mann= 5 ,-1 , 0
  4538.6     .11       0  4800.3     .15       0  4842.5     .03       0
    5117     .15       0  5296.2     .11       0
Bank Sta=4842.5,5117
XS Rating Curve= 0 ,0
Exp/Cntr=0.3,0.1

Type RM Length L Ch R = 1 ,11506   ,338,338,338
BEGIN DESCRIPTION:
WOODSONS GULLY 21.0
END DESCRIPTION:
XS GIS Cut Line= 4
      3877619.03     10035957.62      3878229.68     10036011.01
      3878343.93     10035959.67      3879018.04      10035258.2
#Sta/Elev= 30
  4300.9   84.57  4349.9   83.12  4550.7   82.61  4620.9   80.88  4661.1   81.58
  4710.8   80.66  4711.3   80.66  4781.5   79.04  4791.6    79.8  4821.7   78.49
  4966.7   78.11    4996   76.82  5104.7   79.74  5234.5   81.98  5316.6   82.23
  5352.2   83.52  5401.5   82.46  5415.7   83.37  5437.1   82.39    5444   83.15
  5486.4   82.29  5613.8   83.02    5628    82.3  5663.2   83.04  5670.4   84.11
  5705.6   84.41  5762.2   82.71  5826.1   83.85  5903.7   82.85    6012   84.35
#Mann= 5 ,-1 , 0
  4300.9     .11       0  4710.8     .15       0  4711.3     .03       0
  5104.7     .15       0  5234.5     .11       0
Bank Sta=4711.3,5104.7
XS Rating Curve= 0 ,0
Exp/Cntr=0.3,0.1

Type RM Length L Ch R = 1 ,11168   ,821,821,821
BEGIN DESCRIPTION:
WOODSONS GULLY 20.0
END DESCRIPTION:
XS GIS Cut Line= 4
      3877670.63     10036073.93      3878226.21     10036299.63
      3878541.03     10036184.76      3879053.97     10036260.47
#Sta/Elev= 30
  4209.4   83.14  4291.1   82.85  4319.9   82.06  4344.6   81.36  4433.1   81.76
  4519.4   80.84  4529.4    81.4    4541   80.64  4628.5   80.78  4735.3   79.07
  4778.5   79.43  4848.4   78.02  4873.6   78.65    4940   77.72  4990.5   77.94
  4996.3   76.46  5008.6   76.46    5021    77.7  5119.5   79.28  5136.7   79.77
  5238.6   80.96  5309.3   81.93  5333.1   82.54  5353.3   81.65  5363.5   82.23
  5383.6   81.79  5428.1   82.54  5525.1    79.9  5567.4   80.59  5662.7   83.83
#Mann= 9 ,-1 , 0
  4209.4     .17       0  4319.9     .11       0  4628.5     .15       0
  4778.5     .03       0  5119.5     .15       0  5136.7     .17       0
  5238.6     .11       0  5309.3     .17       0  5567.4     .15       0
Bank Sta=4778.5,5119.5
XS Rating Curve= 0 ,0
Exp/Cntr=0.3,0.1