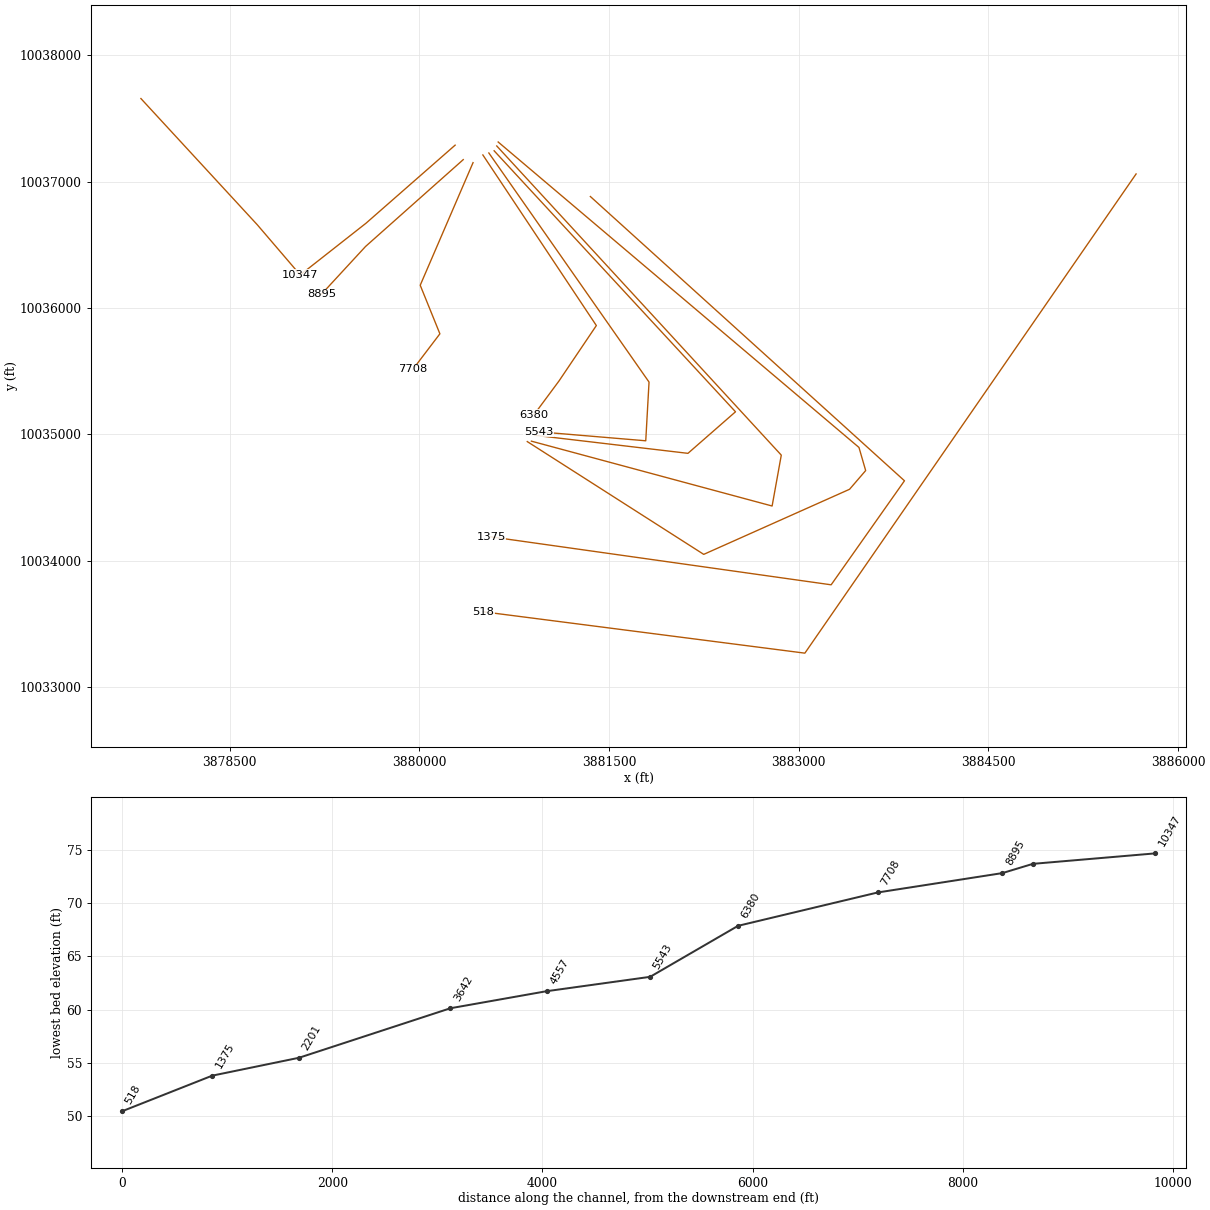
HEC-RAS study WOODSONS GULLY.prj: WOODSONS GULLY Base Level Engineering

--- WOODSONS GULLY.g01 (geometry) --- (continued)

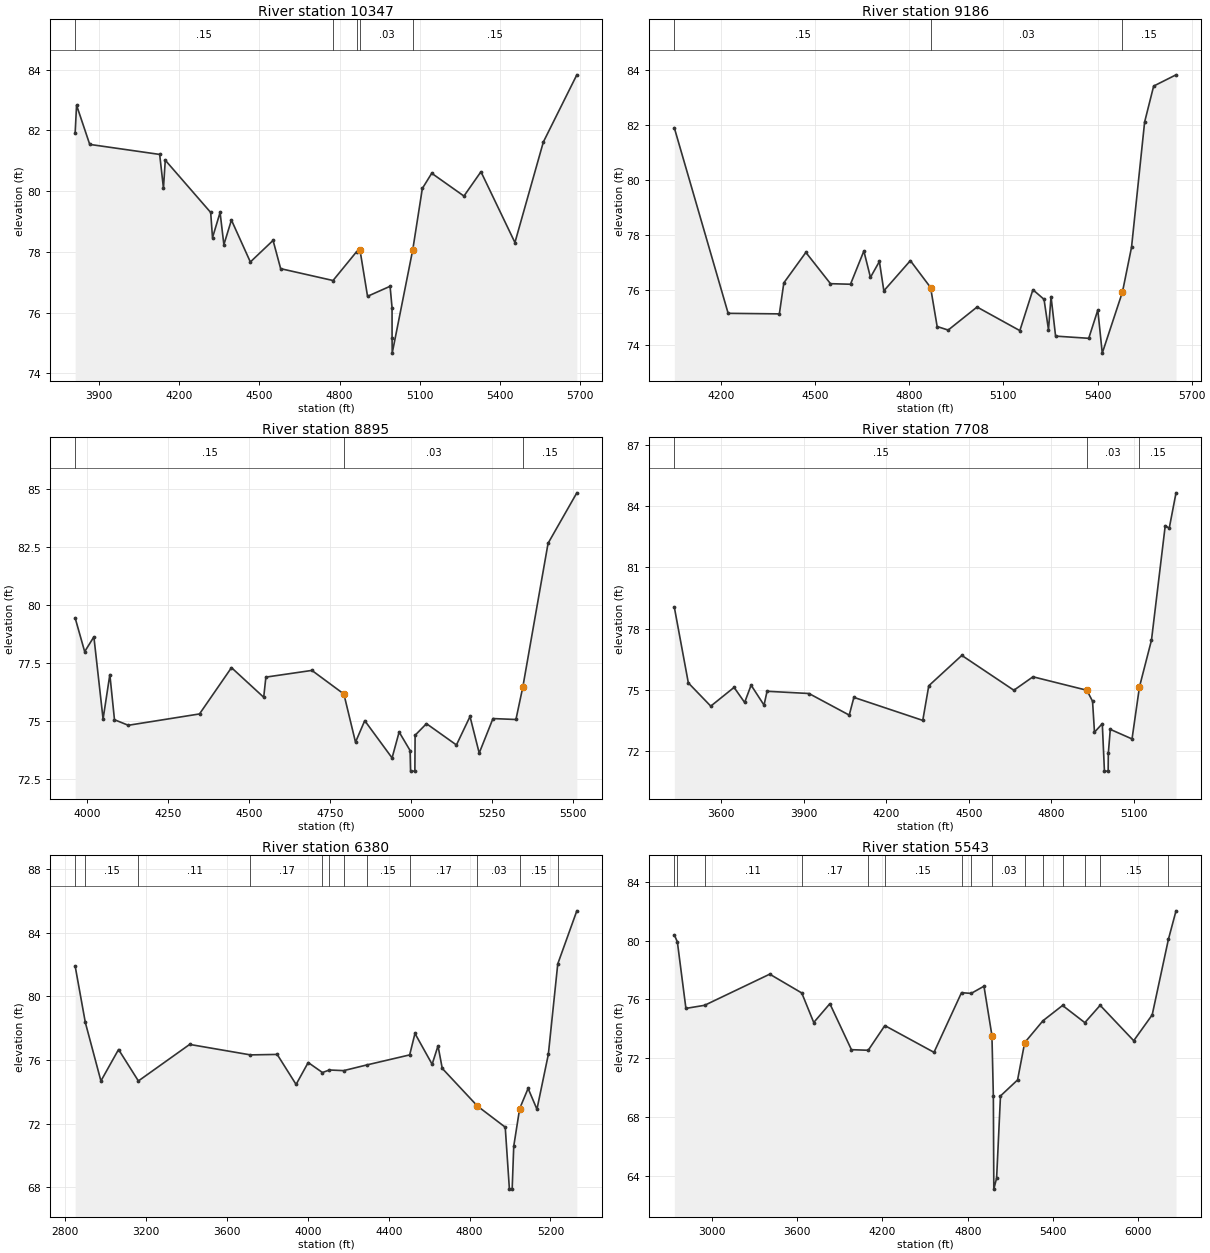
Type RM Length L Ch R = 1 ,10347   ,1161,1161,1161
BEGIN DESCRIPTION:
WOODSONS GULLY 19.0
END DESCRIPTION:
XS GIS Cut Line= 3
      3877797.25     10037657.93      3878717.07     10036659.17
      3879056.12     10036262.78
#Sta/Elev= 30
  3809.6    81.9    3815   82.83  3864.3   81.54  4126.3   81.21  4140.5    80.1
  4147.3   81.02  4317.4    79.3  4324.2   78.47  4352.6    79.3  4366.8   78.24
  4395.1   79.05    4466   77.67  4551.1   78.38  4579.5   77.45  4775.7   77.06
  4864.1   78.01  4876.6   78.07    4905   76.54  4989.4   76.87  4996.8   76.17
  4996.9   75.17  4997.4   74.67  5074.5   78.08  5110.3   80.09  5145.4   80.59
  5266.1   79.84  5329.8   80.64  5457.1   78.31  5563.6   81.62    5689   83.83
#Mann= 5 ,-1 , 0
  3809.6     .15       0  4775.7     .17       0  4864.1     .15       0
  4876.6     .03       0  5074.5     .15       0
Bank Sta=4876.6,5074.5
XS Rating Curve= 0 ,0
Exp/Cntr=0.3,0.1

Type RM Length L Ch R = 1 ,9186    ,291,291,291
BEGIN DESCRIPTION:
WOODSONS GULLY 17.0
END DESCRIPTION:
XS GIS Cut Line= 3
      3880282.17     10037288.95      3879577.31     10036670.89
      3879057.22     10036261.73
#Sta/Elev= 30
    4051    81.9  4222.6   75.14  4385.8   75.12  4400.1   76.25  4470.3   77.36
  4548.8   76.22  4612.6    76.2  4655.2   77.41  4676.2   76.45  4704.7   77.03
  4718.9   75.96  4803.4   77.06  4867.9   76.08  4888.8   74.66  4923.9   74.53
    5016   75.37  5152.4   74.51    5194      76  5229.5   75.65  5243.7   74.54
  5251.8   75.75  5266.3   74.31    5372   74.23  5400.9   75.26  5415.1   73.69
  5479.5   75.92  5508.4   77.55  5550.1   82.11  5578.9   83.42  5650.2   83.83
#Mann= 3 , 0 , 0
    4051     .15       0  4867.9     .03       0  5479.5     .15       0
Bank Sta=4867.9,5479.5
XS Rating Curve= 0 ,0
Exp/Cntr=0.3,0.1

Type RM Length L Ch R = 1 ,8895    ,1187,1187,1187
BEGIN DESCRIPTION:
WOODSONS GULLY 15.0
END DESCRIPTION:
XS GIS Cut Line= 3
      3880346.38     10037174.34      3879573.84     10036486.86
       3879224.9     10036108.41
#Sta/Elev= 30
  3961.9   79.44  3991.4   77.98  4019.8   78.62  4048.2   75.07  4069.1   76.99
  4083.4   75.04    4126    74.8  4345.9   75.29  4444.6   77.29  4544.1   76.01
  4550.8   76.88  4692.9   77.17  4791.6   76.15  4827.5   74.07    4856      75
  4940.4   73.39  4962.2   74.51    4996   73.71  4997.5   72.82  5010.8   72.82
  5011.5   74.37  5046.6   74.87  5139.1   73.95    5181   75.18  5209.4    73.6
  5251.9   75.09  5322.8   75.05    5344   76.45    5422   82.66  5510.8   84.84
#Mann= 3 ,-1 , 0
  3961.9     .15       0  4791.6     .03       0    5344     .15       0
Bank Sta=4791.6,5344
XS Rating Curve= 0 ,0
Exp/Cntr=0.3,0.1

Type RM Length L Ch R = 1 ,7708    ,1328,1328,1328
BEGIN DESCRIPTION:
WOODSONS GULLY 13.0
END DESCRIPTION:
XS GIS Cut Line= 4
      3880423.98     10037150.62      3880006.13      10036179.8
      3880161.73     10035795.25      3879948.97     10035515.03
#Sta/Elev= 30
  3429.9   79.05  3480.9   75.33  3562.4   74.19  3647.1   75.11  3685.5   74.37
    3709   75.22    3756   74.24    3767   74.92  3919.3   74.81  4065.7   73.75
  4082.6   74.62    4333   73.49  4354.8   75.19  4474.9   76.68  4664.1   74.97
  4733.6   75.63  4929.3   74.97  4950.1   74.43  4957.1   72.91  4985.5   73.33
  4993.3      71  5006.8      71  5007.4   71.87  5014.6   73.05  5093.6   72.58
  5120.7   75.14  5164.3   77.43  5214.3   83.05  5228.8   82.92  5253.5   84.66
#Mann= 3 , 0 , 0
  3429.9     .15       0  4929.3     .03       0  5120.7     .15       0
Bank Sta=4929.3,5120.7
XS Rating Curve= 0 ,0
Exp/Cntr=0.3,0.1

Type RM Length L Ch R = 1 ,6380    ,837,837,837
BEGIN DESCRIPTION:
WOODSONS GULLY 11.0
END DESCRIPTION:
XS GIS Cut Line= 4
      3880501.56     10037211.41      3881399.14      10035860.7
      3881103.51     10035421.59      3880906.78     10035155.77
#Sta/Elev= 30
  2848.9   81.92  2899.4   78.36  2976.5   74.68  3063.7   76.66  3161.8   74.68
  3415.5   76.98  3716.4   76.32  3848.4   76.35  3941.9   74.46  4001.8   75.84
  4072.4   75.21  4106.6   75.37  4177.2   75.33  4292.4   75.69  4503.8   76.32
    4530   77.67  4614.9   75.73    4644   76.89    4665   75.47    4839    73.1
  4976.5   71.77  4997.1   67.87  5010.8   67.87  5018.6   70.57  5047.9   72.94
  5089.6   74.21  5133.4    72.9  5189.7   76.35  5236.4   82.05  5330.7   85.39
#Mann= 12 ,-1 , 0
  2848.9     .11       0  2899.4     .15       0  3161.8     .11       0
  3716.4     .17       0  4072.4     .11       0  4106.6     .17       0
  4177.2     .11       0  4292.4     .15       0  4503.8     .17       0
    4839     .03       0  5047.9     .15       0  5236.4     .11       0
Bank Sta=4839,5047.9
XS Rating Curve= 0 ,0
Exp/Cntr=0.3,0.1

Type RM Length L Ch R = 1 ,5543    ,986,986,986
BEGIN DESCRIPTION:
WOODSONS GULLY 9.0
END DESCRIPTION:
XS GIS Cut Line= 4
      3880548.96     10037227.08      3881815.81     10035413.11
      3881789.77     10034948.27      3880941.19     10035019.74
#Sta/Elev= 30
  2735.8   80.38  2757.2   79.91  2817.4   75.38  2948.7   75.59  3407.1   77.71
  3632.4   76.43  3716.7   74.42  3830.1    75.7  3981.9   72.57    4100   72.53
  4216.9   74.21  4562.8   72.39  4756.3   76.45  4824.2    76.4  4914.3   76.89
  4970.4   73.53  4980.4   69.39  4983.6   63.08  5003.3   63.83  5030.5   69.42
  5150.7   70.51  5200.8   73.05  5329.4   74.54  5467.2   75.58    5624   74.41
  5731.7   75.59  5967.8   73.18  6097.9   74.94  6211.7   80.07  6265.5   82.02
#Mann= 15 ,-1 , 0
  2735.8     .11       0  2757.2     .15       0  2948.7     .11       0
  3632.4     .17       0    4100     .11       0  4216.9     .15       0
  4756.3     .17       0  4824.2     .15       0  4970.4     .03       0
  5200.8     .15       0  5329.4     .17       0  5467.2     .11       0
    5624     .17       0  5731.7     .15       0  6211.7     .11       0
Bank Sta=4970.4,5200.8
XS Rating Curve= 0 ,0
Exp/Cntr=0.3,0.1

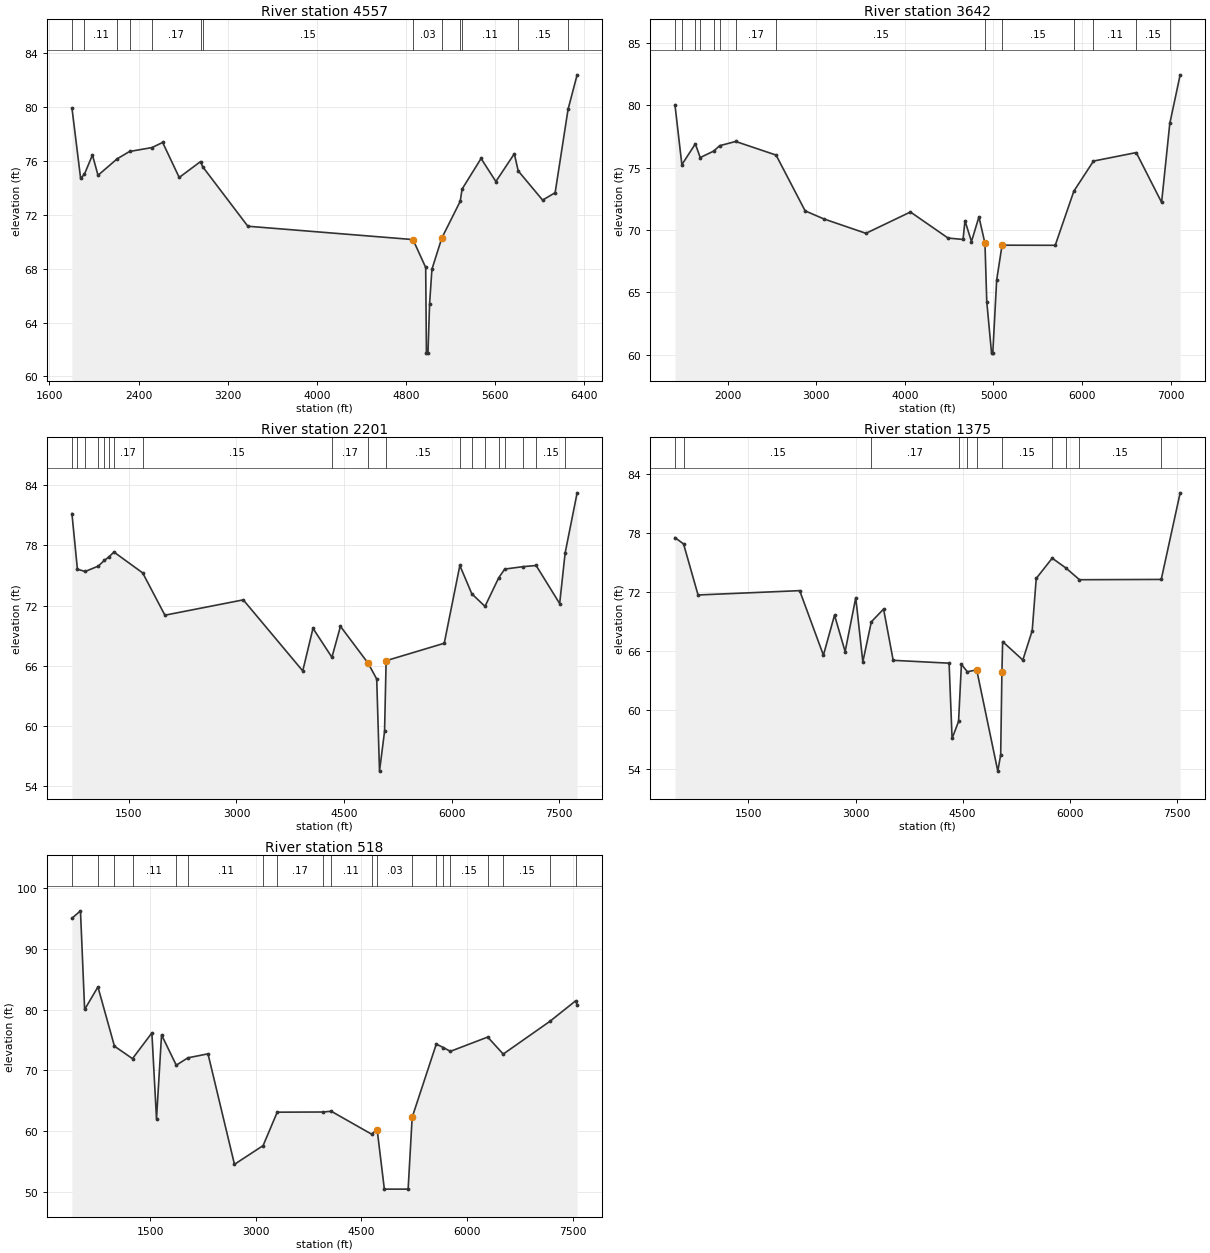
Type RM Length L Ch R = 1 ,4557    ,915,915,915
BEGIN DESCRIPTION:
WOODSONS GULLY 7.0
END DESCRIPTION:
XS GIS Cut Line= 4
      3880590.69     10037244.37      3882499.66     10035177.94
      3882123.53     10034848.88      3880911.95     10034991.99
#Sta/Elev= 30
  1802.3   79.94  1880.4    74.7  1914.3   75.01  1986.5   76.44  2036.3   74.93
  2207.3   76.15  2319.4    76.7  2520.6   76.99  2616.4   77.37    2765   74.77
  2956.4   75.95  2975.3   75.57  3380.8   71.15  4862.6   70.16  4976.5   68.09
    4983   61.73  4996.9   61.73  5011.6   65.41  5032.5   67.96    5121   70.27
  5286.2      73  5303.1   73.91  5473.4   76.18  5606.1   74.47  5771.9   76.53
  5806.5   75.26  6025.7   73.09    6138   73.64    6254   79.83  6335.3   82.39
#Mann= 13 ,-1 , 0
  1802.3     .15       0  1914.3     .11       0  2207.3     .17       0
  2319.4     .11       0  2520.6     .17       0  2956.4     .11       0
  2975.3     .15       0  4862.6     .03       0    5121     .15       0
  5286.2     .17       0  5303.1     .11       0  5806.5     .15       0
    6254     .11       0
Bank Sta=4862.6,5121
XS Rating Curve= 0 ,0
Exp/Cntr=0.3,0.1

Type RM Length L Ch R = 1 ,3642    ,1441,1441,1441
BEGIN DESCRIPTION:
WOODSONS GULLY 5.0
END DESCRIPTION:
XS GIS Cut Line= 4
      3880611.48     10037282.61      3882861.75     10034834.72
      3882789.21     10034431.87      3880885.48     10034945.27
#Sta/Elev= 30
  1402.8   80.03  1480.9   75.23  1632.9    76.9  1688.3    75.8  1840.4   76.32
  1907.2   76.75  2088.9   77.09  2544.9      76  2873.2   71.53  3085.9   70.88
    3560   69.73  4062.5   71.44  4487.3   69.35  4656.8   69.24  4678.4   70.74
  4751.9   69.07  4836.3   71.05  4904.3   68.92  4924.6   64.26  4978.6   60.13
  4992.6   60.13  5036.4   65.98  5097.3   68.78  5697.9   68.77  5908.3   73.11
  6130.1   75.52    6613    76.2  6899.3   72.21  6991.8   78.53  7108.9   82.43
#Mann= 14 ,-1 , 0
  1402.8     .15       0  1480.9     .11       0  1632.9     .17       0
  1688.3     .11       0  1840.4     .17       0  1907.2     .11       0
  2088.9     .17       0  2544.9     .15       0  4904.3     .03       0
  5097.3     .15       0  5908.3     .17       0  6130.1     .11       0
    6613     .15       0  6991.8     .11       0
Bank Sta=4904.3,5097.3
XS Rating Curve= 0 ,0
Exp/Cntr=0.3,0.1

Type RM Length L Ch R = 1 ,2201    ,826,826,826
BEGIN DESCRIPTION:
WOODSONS GULLY 4.0
END DESCRIPTION:
XS GIS Cut Line= 6
      3880622.64     10037313.99      3883476.16     10034895.46
      3883529.09      10034712.4      3883401.74     10034564.41
      3882248.32       10034049.      3880852.77     10034941.97
#Sta/Elev= 30
   705.5   81.18   782.1   75.63     891    75.4  1073.4   75.94  1158.1   76.51
    1219   76.84  1291.7   77.34  1692.4   75.26  2002.5   71.04  3095.5   72.57
  3924.9   65.48  4067.8   69.73  4331.8   66.84    4451   69.93  4836.7   66.25
  4956.6   64.67  4995.6   55.48  5066.1   59.45    5088    66.5  5898.6   68.24
  6116.3      76  6283.2   73.17    6467   71.92  6658.1   74.77    6742   75.64
    6993   75.88  7180.1      76  7508.5    72.2  7584.8   77.25    7752   83.25
#Mann= 19 ,-1 , 0
   705.5     .15       0   782.1     .11       0     891     .17       0
  1073.4     .11       0  1158.1     .17       0    1219     .11       0
  1291.7     .17       0  1692.4     .15       0  4331.8     .17       0
  4836.7     .03       0    5088     .15       0  6116.3     .11       0
  6283.2     .15       0    6467     .17       0  6658.1     .11       0
    6742     .17       0    6993     .11       0  7180.1     .15       0
  7584.8     .11       0
Bank Sta=4836.7,5088
XS Rating Curve= 0 ,0
Exp/Cntr=0.3,0.1

Type RM Length L Ch R = 1 ,1375    ,857,857,857
BEGIN DESCRIPTION:
WOODSONS GULLY 2.0
END DESCRIPTION:
XS GIS Cut Line= 4
      3881351.86     10036882.31      3883835.98     10034631.63
      3883256.06     10033807.97      3880565.85     10034187.74
#Sta/Elev= 30
   471.1   77.53   591.5   76.89   794.7    71.7  2218.1   72.14  2550.6   65.58
    2706   69.65  2854.7   65.95  3003.4   71.42  3102.7    64.9  3221.6   68.97
  3393.3   70.27  3527.8   65.06    4311   64.77  4352.8   57.12  4443.5   58.85
  4483.4   64.65  4567.1    63.9  4697.7   64.09  4993.3    53.8  5033.6   55.47
  5050.9   63.88    5061   66.96  5343.8   65.09    5475   68.07  5531.5   73.38
  5755.2   75.44  5947.3   74.44  6137.2   73.25  7282.6   73.28  7547.4   82.08
#Mann= 11 ,-1 , 0
   471.1     .17       0   591.5     .15       0  3221.6     .17       0
  4443.5     .15       0  4567.1     .17       0  4697.7     .03       0
  5050.9     .15       0  5755.2     .17       0  5947.3     .11       0
  6137.2     .15       0  7282.6     .11       0
Bank Sta=4697.7,5050.9
XS Rating Curve= 0 ,0
Exp/Cntr=0.3,0.1

Type RM Length L Ch R = 1 ,518     ,0,0,0
BEGIN DESCRIPTION:
WOODSONS GULLY 1.0
END DESCRIPTION:
XS GIS Cut Line= 3
      3885667.86     10037061.08      3883048.24     10033266.86
      3880504.05     10033594.55
#Sta/Elev= 30
   389.3   95.02   510.8   96.25   569.8   80.02   758.7   83.73   993.3   73.98
  1249.7   71.93    1525   76.16  1590.6   62.02  1662.3   75.84  1871.4   70.85
  2035.5   72.06  2322.1   72.72  2697.9   54.54  3104.7   57.62  3305.4   63.12
  3955.2   63.15    4073   63.27  4644.5   59.51  4724.7   60.24  4827.1   50.46
  5164.8   50.46  5222.2   62.28  5564.6   74.32  5664.5   73.76  5764.5   73.13
  6295.2   75.48  6515.2   72.68  7177.6   78.06  7542.8   81.43  7565.2   80.81
#Mann= 20 ,-1 , 0
   389.3     .11       0   758.7     .17       0   993.3     .15       0
  1249.7     .11       0  1871.4     .15       0  2035.5     .11       0
  3104.7     .15       0  3305.4     .17       0  3955.2     .17       0
    4073     .11       0  4644.5     .15       0  4724.7     .03       0
  5222.2     .15       0  5564.6     .11       0  5664.5     .17       0
  5764.5     .15       0  6295.2     .17       0  6515.2     .15       0
  7177.6     .11       0  7542.8     .11       0
Bank Sta=4724.7,5222.2
XS Rating Curve= 0 ,0
Exp/Cntr=0.3,0.1

Chan Stop Cuts=-1
Use User Specified Reach Order=0
Composite Channel Slope=5

--- WOODSONS GULLY.g10 (geometry) ---

Geom Title=Existing Conditions
Program Version=4.10

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
River Reach=WOODSONS GULLY  ,Reach-1

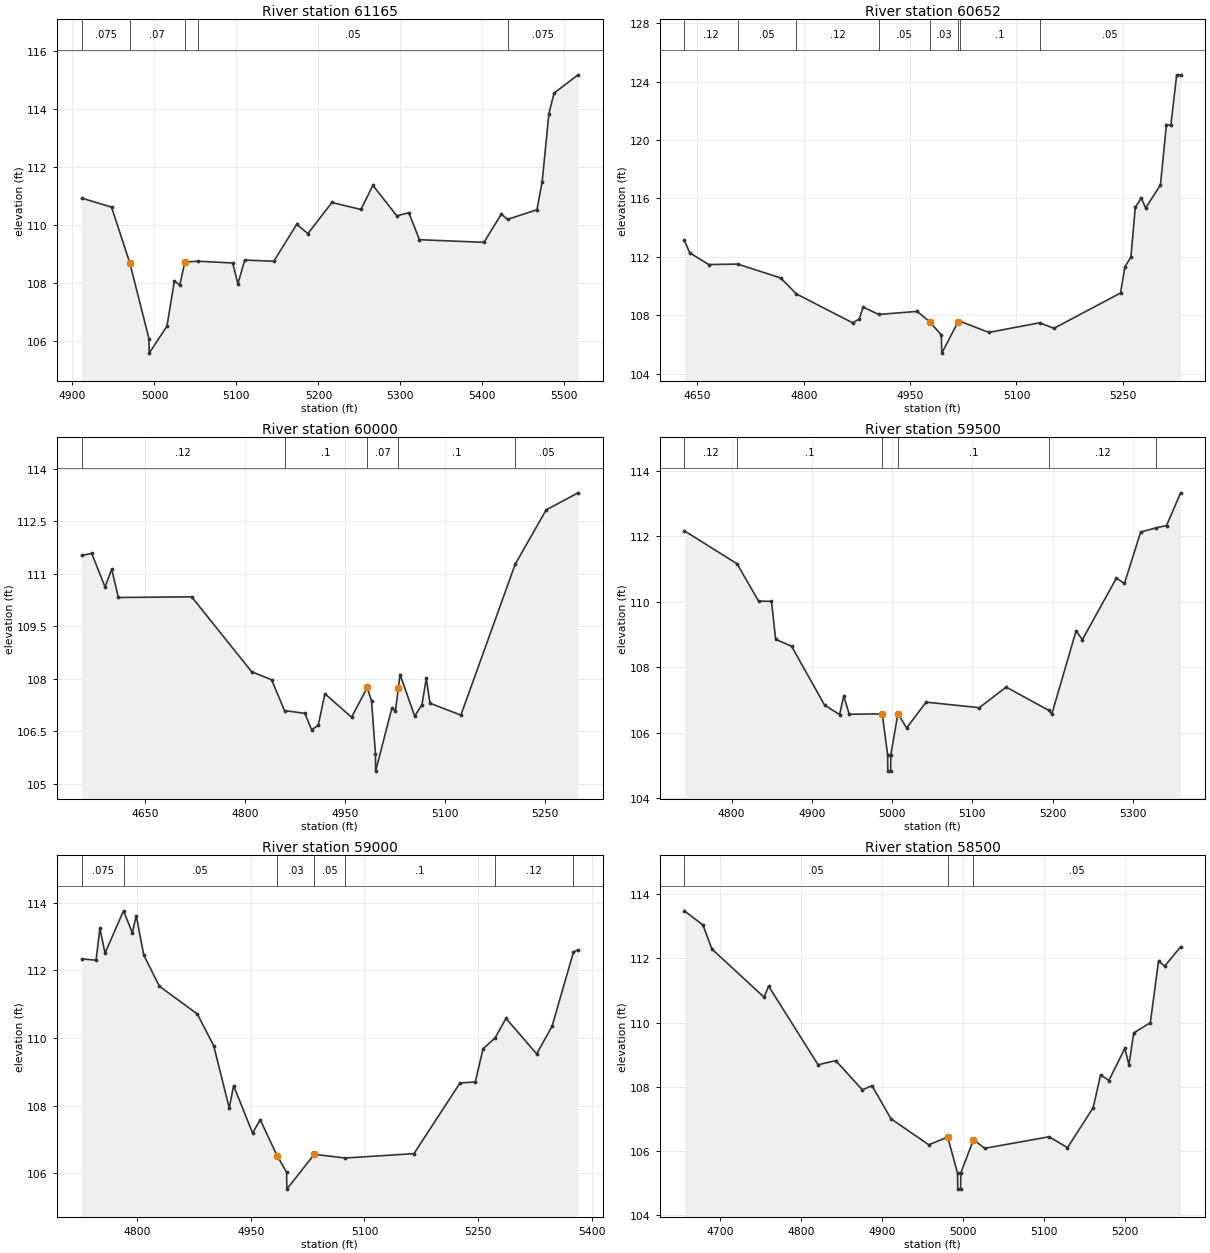
Type RM Length L Ch R = 1 ,61165   ,513,513,513
BEGIN DESCRIPTION:
WOODSONS GULLY 120.0
END DESCRIPTION:
XS GIS Cut Line= 3
      3856022.26     10053425.06       3856024.3     10053308.02
      3855632.85     10053016.06
#Sta/Elev= 30
  4911.3  110.93  4947.7  110.62 4969.86 108.711  4993.3   106.1  4993.6   105.6
  5015.3  106.53  5024.3  108.08  5030.9  107.94  5037.1  108.73  5053.2  108.76
  5095.5   108.7  5101.8  107.98  5110.1   108.8  5145.6  108.76  5173.6  110.03
  5187.2  109.71  5216.5  110.78  5251.9  110.54  5266.5  111.37  5295.7  110.32
  5310.3  110.43  5323.3   109.5    5402  109.41  5423.1  110.38  5430.8   110.2
  5466.6  110.53    5473   111.5  5481.2  113.84  5487.5  114.54  5516.7  115.17
#Mann= 5 ,-1 , 0
  4911.3    .075       0 4969.86     .07       0  5037.1    .075       0
  5053.2     .05       0  5430.8    .075       0
Bank Sta=4969.86,5037.1
XS Rating Curve= 0 ,0
Exp/Cntr=0.3,0.1

Type RM Length L Ch R = 1 ,60652   ,652,652,652
BEGIN DESCRIPTION:
WOODSONS GULLY 119.0
END DESCRIPTION:
XS GIS Cut Line= 3
      3856761.92     10053097.04      3856404.31     10053038.02
      3856202.95     10052767.22
#Sta/Elev= 30
  4631.6  113.14  4639.2  112.27  4666.1  111.47  4707.1   111.5  4767.5  110.55
  4789.6  109.46  4868.8  107.48  4878.5  107.74  4883.6  108.56  4905.8  108.05
    4960  108.26 4977.37 107.554    4994  106.66  4994.7   105.4  5017.3  107.51
  5020.6  107.58  5061.1  106.82  5132.6  107.48  5152.9   107.1  5246.8  109.52
    5253  111.32  5261.4  111.98  5267.6  115.39    5276  116.03  5282.2  115.34
  5303.1  116.93  5311.5  121.06  5317.7  121.01    5326  124.47  5331.5  124.47
#Mann= 8 ,-1 , 0
  4631.6     .12       0  4707.1     .05       0  4789.6     .12       0
  4905.8     .05       0 4977.37     .03       0  5017.3     .05       0
  5020.6      .1       0  5132.6     .05       0
Bank Sta=4977.37,5017.3
XS Rating Curve= 0 ,0
Exp/Cntr=0.3,0.1

Type RM Length L Ch R = 1 ,60000   ,500,500,500
BEGIN DESCRIPTION:
WOODSONS GULLY 118.0
END DESCRIPTION:
XS GIS Cut Line= 3
      3856930.35     10053156.03      3856922.53      10052710.4
      3856800.16     10052437.37
#Sta/Elev= 30
  4554.3  111.52  4569.3  111.58  4589.3  110.62  4599.3  111.13  4609.3  110.32
  4719.3  110.34  4809.3   108.2  4839.3  107.97  4858.7  107.09  4889.3  107.01
  4899.3  106.54  4909.3  106.67  4919.3  107.57  4959.3   106.9  4982.9  107.75
  4989.3  107.36  4995.2  105.86  4995.4  105.36  5019.7  107.15  5025.2  107.09
 5029.52 107.735  5032.1  108.12  5054.1  106.93    5065  107.26  5071.5  108.01
    5077   107.3  5123.4  106.96  5204.9  111.27  5251.3  112.82  5299.2  113.31
#Mann= 5 ,-1 , 0
  4554.3     .12       0  4858.7      .1       0  4982.9     .07       0
 5029.52      .1       0  5204.9     .05       0
Bank Sta=4982.9,5029.52
XS Rating Curve= 0 ,0
Exp/Cntr=0.3,0.1

Type RM Length L Ch R = 1 ,59500   ,500,500,500
BEGIN DESCRIPTION:
WOODSONS GULLY 117.0
END DESCRIPTION:
XS GIS Cut Line= 3
       3857467.9     10052311.06      3857215.96     10052370.24
      3856858.29     10052334.02
#Sta/Elev= 30
  4741.2  112.17  4806.9  111.16  4833.7  110.02  4849.8  110.01    4855  108.85
  4874.8  108.64  4915.9  106.84  4934.7  106.55  4939.8  107.12  4946.7  106.56
  4987.8  106.57  4994.5  105.32  4994.7  104.82  4998.2  104.82  4998.5  105.32
 5007.28 106.578  5018.2  106.14  5042.4  106.93  5108.7  106.76  5142.2  107.39
  5195.1  106.68  5199.1  106.57  5229.3  109.11  5237.1  108.84  5279.5  110.72
  5289.6  110.56  5309.7  112.13    5329  112.26    5342  112.33  5359.5  113.33
#Mann= 6 ,-1 , 0
  4741.2     .12       0  4806.9      .1       0  4987.8     .07       0
 5007.28      .1       0  5195.1     .12       0    5329     .05       0
Bank Sta=4987.8,5007.28
XS Rating Curve= 0 ,0
Exp/Cntr=0.3,0.1

Type RM Length L Ch R = 1 ,59000   ,500,500,500
BEGIN DESCRIPTION:
WOODSONS GULLY 116.0
END DESCRIPTION:
XS GIS Cut Line= 3
      3857467.82     10051811.08      3857201.14      10051872.2
      3856823.92     10051933.09
#Sta/Elev= 30
  4726.4  112.34  4745.3   112.3  4750.4  113.24  4757.2  112.51  4781.6  113.76
  4793.3  113.11  4798.4  113.62  4808.4  112.45    4829  111.53  4879.1  110.71
  4900.8  109.77  4921.3  107.93  4927.1  108.59  4952.1  107.19  4962.3  107.58
 4984.36 106.524  4997.1  106.03  4997.4  105.53  5033.7  106.56  5074.5  106.45
  5165.4  106.58  5226.2  108.67  5246.4   108.7  5256.6  109.68  5272.5     110
    5287  110.58  5327.5  109.53  5347.7  110.34  5376.1  112.54  5382.1  112.61
#Mann= 7 ,-1 , 0
  4726.4    .075       0  4781.6     .05       0 4984.36     .03       0
  5033.7     .05       0  5074.5      .1       0  5272.5     .12       0
  5376.1     .05       0
Bank Sta=4984.36,5033.7
XS Rating Curve= 0 ,0
Exp/Cntr=0.3,0.1

Type RM Length L Ch R = 1 ,58500   ,531,531,531
BEGIN DESCRIPTION:
WOODSONS GULLY 115.0
END DESCRIPTION:
XS GIS Cut Line= 3
      3857629.12     10051527.43      3857313.72      10051389.1
      3857051.27     10051332.45
#Sta/Elev= 30
  4655.6  113.48  4678.6  113.04  4689.7  112.29  4754.2  110.79  4759.6  111.14
  4820.8  108.69  4842.6  108.82  4875.4  107.91  4887.4  108.04  4910.8  107.01
  4957.5   106.2  4980.9  106.44    4993  105.32  4993.3  104.82  4996.8  104.82
    4997  105.32  5012.7  106.36  5026.5  106.09  5106.2  106.45  5128.8  106.11
  5160.6  107.36  5169.7  108.38  5179.9   108.2  5199.6   109.2  5204.7  108.69
  5210.6  109.68  5231.1     110  5241.3  111.92  5248.9  111.76  5268.5  112.36
#Mann= 3 , 0 , 0
  4655.6     .05       0  4980.9     .03       0  5012.7     .05       0
Bank Sta=4980.9,5012.7
XS Rating Curve= 0 ,0
Exp/Cntr=0.3,0.1

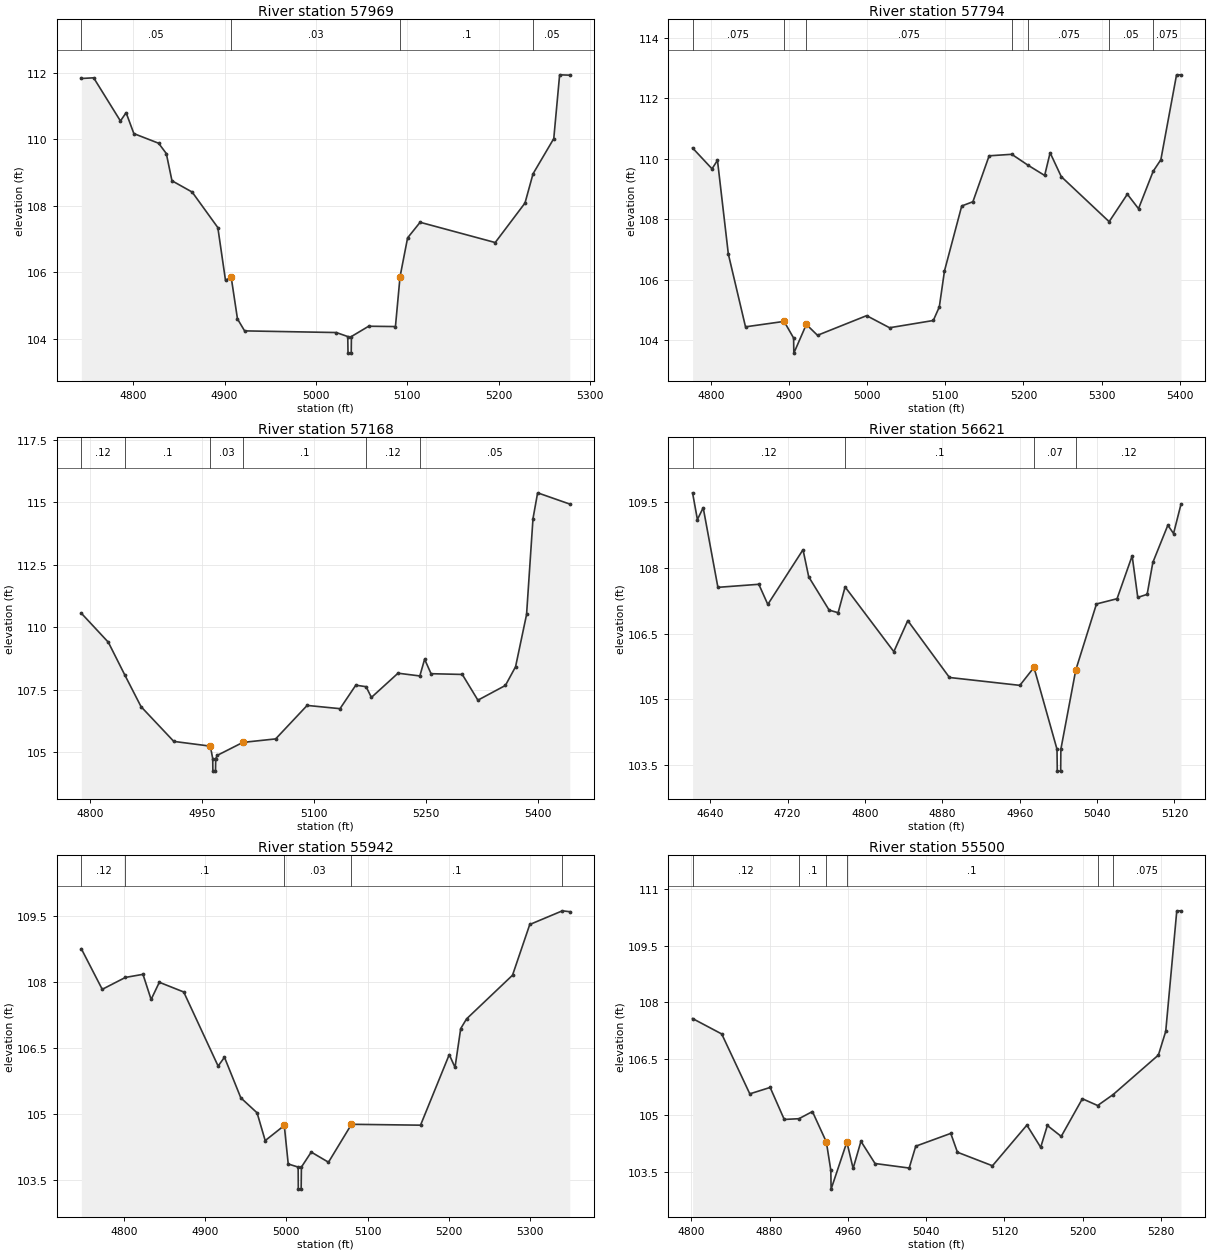
Type RM Length L Ch R = 1 ,57969   ,175,175,175
BEGIN DESCRIPTION:
WOODSONS GULLY 114.0
END DESCRIPTION:
XS GIS Cut Line= 3
      3857695.62     10051052.73      3857392.14     10050829.81
      3857241.14     10050783.14
#Sta/Elev= 30
  4743.3  111.83  4756.8  111.85  4786.1  110.55  4792.3   110.8  4800.8  110.17
  4827.9  109.88  4836.3  109.57  4842.5  108.75  4864.6  108.41  4892.7  107.34
  4901.1  105.75  4907.3  105.85  4914.2  104.59    4922  104.23  5022.3  104.18
  5034.9  104.06  5035.2  103.56  5038.7  103.56  5038.9  104.06  5057.8  104.37
  5087.1  104.36 5092.13 105.861  5100.4  107.03  5114.1   107.5  5196.3  106.89
  5228.9  108.08  5237.7  108.96  5260.4  110.02  5266.8  111.94  5277.9  111.93
#Mann= 4 ,-1 , 0
  4743.3     .05       0  4907.3     .03       0 5092.13      .1       0
  5237.7     .05       0
Bank Sta=4907.3,5092.13
XS Rating Curve= 0 ,0
Exp/Cntr=0.3,0.1

Type RM Length L Ch R = 1 ,57794   ,626,626,626
BEGIN DESCRIPTION:
WOODSONS GULLY 113.0
END DESCRIPTION:
XS GIS Cut Line= 3
       3857782.1     10050922.02      3857612.28     10050777.03
      3857303.98     10050518.73
#Sta/Elev= 30
  4776.3  110.36  4801.2  109.67  4808.2  109.95  4822.1  106.85  4844.1  104.44
  4893.5  104.62  4905.7  104.07    4906  103.57    4922  104.52  4936.3  104.16
  4999.2  104.81  5028.6  104.41  5084.6  104.65  5092.3   105.1  5098.9  106.29
    5121  108.44  5135.3  108.58  5156.1   110.1  5185.1  110.15  5205.8  109.79
  5227.2  109.45  5234.2   110.2  5248.5  109.41  5309.8  107.92  5333.1  108.83
  5347.4  108.35  5366.2  109.59    5376  109.97  5396.1  112.78  5401.8  112.78
#Mann= 7 ,-1 , 0
  4776.3    .075       0  4893.5     .03       0    4922    .075       0
  5185.1     .05       0  5205.8    .075       0  5309.8     .05       0
  5366.2    .075       0
Bank Sta=4893.5,4922
XS Rating Curve= 0 ,0
Exp/Cntr=0.3,0.1

Type RM Length L Ch R = 1 ,57168   ,547,547,547
BEGIN DESCRIPTION:
WOODSONS GULLY 112.0
END DESCRIPTION:
XS GIS Cut Line= 3
      3858140.19     10050563.23      3858101.12     10050385.28
      3857717.81     10050111.05
#Sta/Elev= 30
  4788.8  110.56  4824.9   109.4  4847.1  108.08  4868.7  106.82  4912.5  105.43
  4961.4  105.24  4964.6  104.74  4964.8  104.24  4968.3  104.24  4968.6  104.74
  4970.6  104.87  5004.9  105.39  5048.8  105.53  5090.9  106.87  5134.9  106.74
    5156  107.68  5169.8  107.62  5176.9  107.19  5212.5  108.16  5241.7  108.05
  5248.1  108.72  5256.7  108.14  5298.5  108.11  5319.4  107.08  5356.2  107.67
  5369.8  108.42  5384.5  110.51  5393.1  114.35  5399.3  115.38  5442.3  114.93
#Mann= 6 ,-1 , 0
  4788.8     .12       0  4847.1      .1       0  4961.4     .03       0
  5004.9      .1       0  5169.8     .12       0  5241.7     .05       0
Bank Sta=4961.4,5004.9
XS Rating Curve= 0 ,0
Exp/Cntr=0.3,0.1

Type RM Length L Ch R = 1 ,56621   ,679,679,679
BEGIN DESCRIPTION:
WOODSONS GULLY 111.0
END DESCRIPTION:
XS GIS Cut Line= 3
      3858645.36     10050229.87      3858325.95     10050025.91
      3858217.88     10049961.09
#Sta/Elev= 30
  4621.8  109.72  4626.8  109.11  4632.8  109.38    4648  107.56  4690.3  107.63
  4699.6  107.17    4736  108.42  4741.9   107.8    4763  107.04  4772.3  106.98
  4779.5  107.57  4829.9  106.09  4844.3   106.8  4887.4   105.5  4960.2  105.32
  4974.8  105.73  4998.6  103.86  4998.9  103.36  5002.4  103.36  5002.6  103.86
    5018  105.67  5039.4  107.18  5060.7   107.3  5076.3  108.28  5082.1  107.33
  5091.8   107.4  5097.7  108.13  5113.2  108.98  5119.1  108.79  5126.8  109.46
#Mann= 4 ,-1 , 0
  4621.8     .12       0  4779.5      .1       0  4974.8     .07       0
    5018     .12       0
Bank Sta=4974.8,5018
XS Rating Curve= 0 ,0
Exp/Cntr=0.3,0.1

Type RM Length L Ch R = 1 ,55942   ,442,442,442
BEGIN DESCRIPTION:
WOODSONS GULLY 110.0
END DESCRIPTION:
XS GIS Cut Line= 3
       3858763.5      10049485.1      3858515.19      10049501.6
      3858267.78     10049251.58
#Sta/Elev= 30
  4747.8  108.75  4773.5  107.83    4802   108.1  4823.6  108.17  4833.6   107.6
  4843.7  107.99  4873.7  107.77    4916  106.09  4923.8  106.29  4943.9  105.37
  4963.9  105.03  4973.9   104.4 4997.35 104.743  5002.2  103.87  5014.4   103.8
  5014.6   103.3  5018.1   103.3  5018.4   103.8  5030.5  104.14  5051.7  103.91
    5080  104.77  5164.9  104.75  5200.2  106.35  5207.3  106.06  5214.3  106.94
  5221.5  107.16    5278  108.15  5299.2   109.3  5339.3  109.61  5348.4  109.59
#Mann= 5 ,-1 , 0
  4747.8     .12       0    4802      .1       0 4997.35     .03       0
    5080      .1       0  5339.3     .12       0
Bank Sta=4997.35,5080
XS Rating Curve= 0 ,0
Exp/Cntr=0.3,0.1

Type RM Length L Ch R = 1 ,55500   ,465,465,465
BEGIN DESCRIPTION:
WOODSONS GULLY 109.0
END DESCRIPTION:
XS GIS Cut Line= 3
       3858913.6     10049316.67      3858788.87     10049161.86
      3858566.44     10048959.96
#Sta/Elev= 30
  4801.2  107.57    4831  107.16  4859.7  105.57  4880.5  105.74  4894.9  104.89
  4909.9  104.91  4923.7   105.1 4937.94 104.292  4942.5  103.54  4942.8  103.04
  4958.9  104.29  4965.3  103.59  4973.3  104.31  4987.7  103.72  5022.6   103.6
  5029.3  104.18  5065.1  104.52  5071.9  104.02  5107.7  103.66  5142.9  104.74
    5157  104.15  5163.8  104.73    5178  104.44  5199.6  105.44  5215.2  105.26
    5231  105.55  5277.3   106.6  5284.8  107.23  5296.1  110.43  5300.4  110.43
#Mann= 6 ,-1 , 0
  4801.2     .12       0  4909.9      .1       0 4937.94     .03       0
  4958.9      .1       0  5215.2     .05       0    5231    .075       0
Bank Sta=4937.94,4958.9
XS Rating Curve= 0 ,0
Exp/Cntr=0.3,0.1

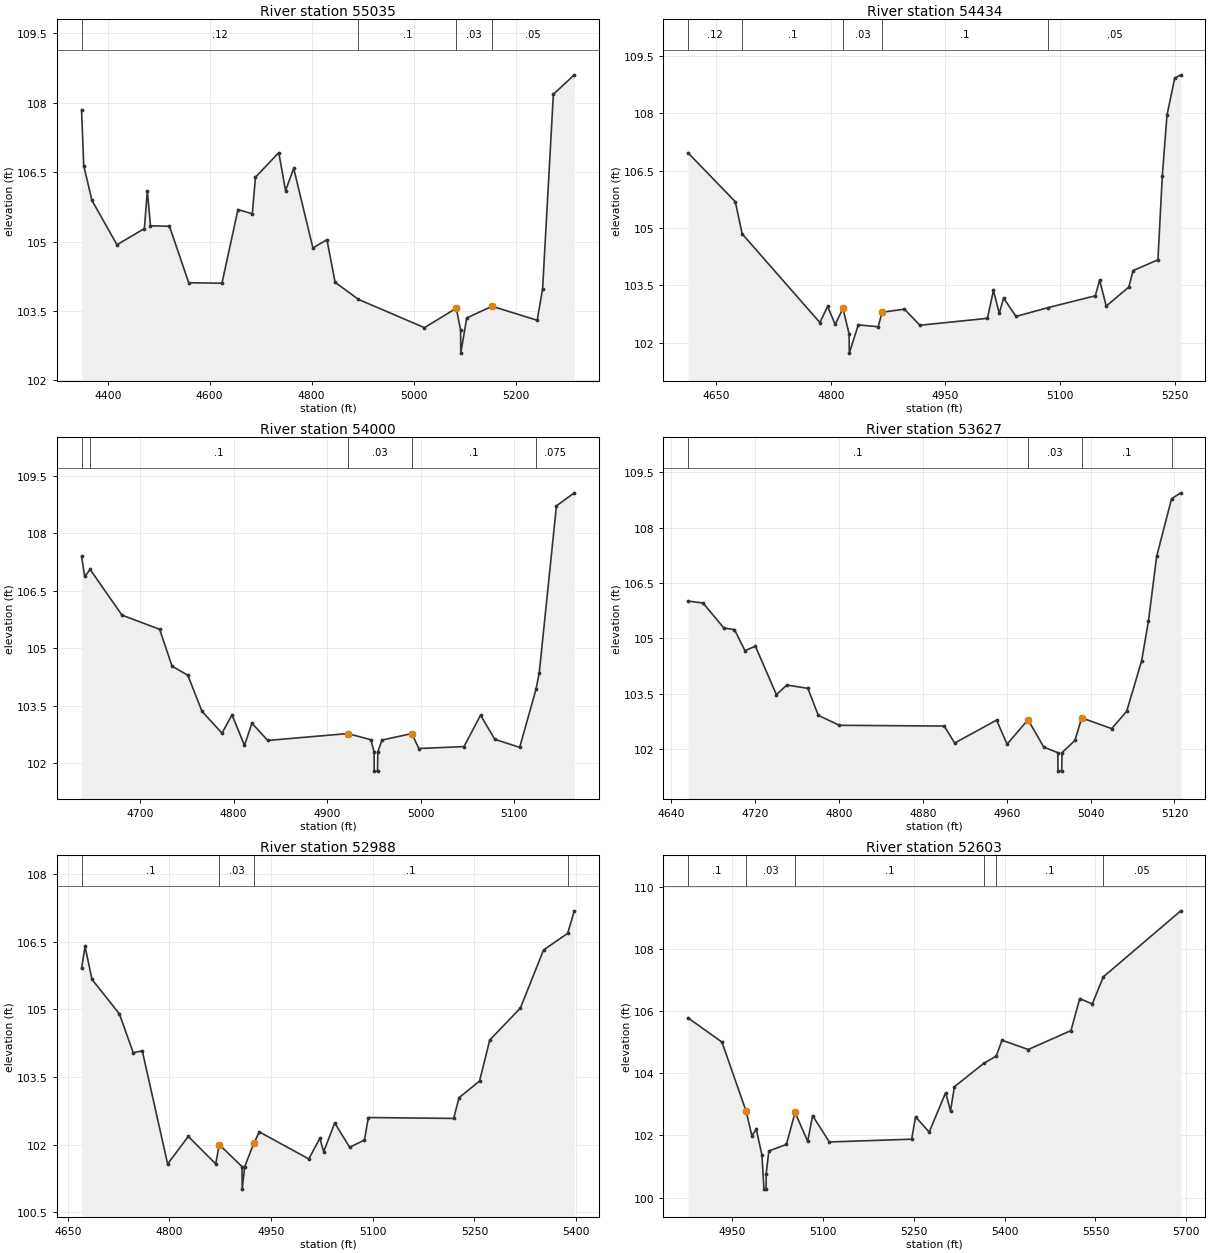
Type RM Length L Ch R = 1 ,55035   ,601,601,601
BEGIN DESCRIPTION:
WOODSONS GULLY 108.0
END DESCRIPTION:
XS GIS Cut Line= 3
      3859475.23     10049449.26      3859157.55     10048877.47
      3859055.36     10048582.27
#Sta/Elev= 30
  4348.7  107.84    4353  106.64    4369  105.89  4418.2  104.93  4471.9  105.28
  4477.7  106.09  4483.9  105.34  4521.1  105.33  4558.9  104.11  4624.1   104.1
  4655.5  105.69  4683.6   105.6  4689.8  106.39  4735.6  106.92  4748.8   106.1
  4764.8  106.58  4802.5  104.86    4830  105.04    4846  104.12  4891.9  103.75
  5021.3  103.14  5083.7  103.56  5092.2  103.09  5092.5  102.59  5104.2  103.35
 5153.79 103.602  5242.4   103.3    5253  103.98  5274.1  108.18  5315.2   108.6
#Mann= 4 ,-1 , 0
  4348.7     .12       0  4891.9      .1       0  5083.7     .03       0
 5153.79     .05       0
Bank Sta=5083.7,5153.79
XS Rating Curve= 0 ,0
Exp/Cntr=0.3,0.1

Type RM Length L Ch R = 1 ,54434   ,434,434,434
BEGIN DESCRIPTION:
WOODSONS GULLY 107.0
END DESCRIPTION:
XS GIS Cut Line= 3
      3860019.29       10048565.      3859632.13     10048519.86
      3859511.13     10048295.15
#Sta/Elev= 30
  4613.2  106.97  4675.1  105.69  4684.1  104.85  4785.8  102.53  4795.9  102.95
  4805.9  102.48    4816   102.9  4824.1  102.23  4824.3  101.73  4836.1  102.47
  4862.1  102.42  4867.2   102.8  4896.5  102.88  4916.7  102.46  5005.1  102.64
    5013  103.37  5020.6  102.77  5026.3  103.17  5042.5  102.69  5084.4  102.92
  5146.3  103.23    5152  103.64  5160.6  102.96  5190.2  103.46  5195.8  103.89
  5228.3  104.17    5234  106.36  5240.1  107.95  5250.2  108.92  5258.2  109.01
#Mann= 5 ,-1 , 0
  4613.2     .12       0  4684.1      .1       0    4816     .03       0
  4867.2      .1       0  5084.4     .05       0
Bank Sta=4816,4867.2
XS Rating Curve= 0 ,0
Exp/Cntr=0.3,0.1

Type RM Length L Ch R = 1 ,54000   ,373,373,373
BEGIN DESCRIPTION:
WOODSONS GULLY 106.0
END DESCRIPTION:
XS GIS Cut Line= 3
      3860033.15     10048521.55      3859905.62     10048182.22
      3859858.11     10048025.15
#Sta/Elev= 30
  4637.5   107.4  4640.9  106.88  4646.7  107.06  4680.7  105.87  4720.9   105.5
  4734.2  104.54  4751.1   104.3  4766.2  103.36  4787.6  102.79  4798.3  103.27
  4811.6  102.47  4819.6  103.05  4836.5   102.6  4921.9  102.78  4946.7  102.62
  4950.1   102.3  4950.3   101.8  4953.8   101.8  4954.1   102.3  4958.5  102.61
  4990.5  102.78  4997.9  102.39  5046.2  102.44  5063.9  103.26  5079.1  102.63
  5105.7  102.42  5123.1  103.93  5126.6  104.36    5145  108.72  5164.1  109.06
#Mann= 5 ,-1 , 0
  4637.5     .12       0  4646.7      .1       0  4921.9     .03       0
  4990.5      .1       0  5123.1    .075       0
Bank Sta=4921.9,4990.5
XS Rating Curve= 0 ,0
Exp/Cntr=0.3,0.1

Type RM Length L Ch R = 1 ,53627   ,639,639,639
BEGIN DESCRIPTION:
WOODSONS GULLY 105.0
END DESCRIPTION:
XS GIS Cut Line= 3
      3860192.02     10048275.38      3860184.21       10047936.
      3860099.99     10047836.15
#Sta/Elev= 30
    4656  106.01  4670.3  105.96  4690.3  105.28  4700.3  105.24  4710.3  104.67
  4720.3  104.79  4740.3  103.48  4750.3  103.74  4770.3  103.65  4780.3  102.92
  4800.4  102.65  4900.4  102.63  4910.4  102.17  4950.4  102.79  4960.4  102.14
  4980.4   102.8  4995.4  102.06  5008.8  101.91    5009  101.41  5012.5  101.41
  5012.8  101.91  5025.1  102.24  5031.6  102.85  5060.2  102.56  5074.5  103.03
  5088.8   104.4  5095.3  105.48  5103.1  107.22  5117.3  108.78  5126.1  108.94
#Mann= 4 ,-1 , 0
    4656      .1       0  4980.4     .03       0  5031.6      .1       0
  5117.3    .075       0
Bank Sta=4980.4,5031.6
XS Rating Curve= 0 ,0
Exp/Cntr=0.3,0.1

Type RM Length L Ch R = 1 ,52988   ,385,385,385
BEGIN DESCRIPTION:
WOODSONS GULLY 104.0
END DESCRIPTION:
XS GIS Cut Line= 3
      3860892.94     10047640.87      3860567.46     10047698.16
      3860217.86     10047511.07
#Sta/Elev= 30
  4670.3  105.91  4675.5   106.4  4685.6  105.67  4726.2   104.9  4746.5  104.04
  4759.9  104.08  4797.3  101.57  4827.8  102.18  4868.3  101.57  4873.4     102
    4907  101.51  4907.3  101.01    4911  101.51 4924.45 102.028  4932.7  102.28
  5005.6  101.68  5021.9  102.14  5027.5  101.84  5043.8  102.48  5065.8  101.94
  5087.7   102.1  5093.4   102.6  5219.3  102.58  5227.2  103.04  5257.5  103.41
  5272.5  104.32  5317.7  105.03  5351.9  106.32  5387.5  106.69  5397.3  107.19
#Mann= 4 ,-1 , 0
  4670.3      .1       0  4873.4     .03       0 4924.45      .1       0
  5387.5    .075       0
Bank Sta=4873.4,4924.45
XS Rating Curve= 0 ,0
Exp/Cntr=0.3,0.1

Type RM Length L Ch R = 1 ,52603   ,516,516,516
BEGIN DESCRIPTION:
WOODSONS GULLY 103.0
END DESCRIPTION:
XS GIS Cut Line= 3
      3860923.02     10047615.14      3860835.17     10047530.53
      3860292.77     10047102.04
#Sta/Elev= 30
  4877.6  105.79  4933.6  105.01  4973.5 102.779    4983  101.99  4990.2   102.2
  4999.6  101.37  5002.9  100.27  5006.4  100.27  5006.6  100.77    5011   101.5
  5039.9  101.71  5054.3  102.74  5075.1  101.81  5083.2  102.64  5110.8  101.79
  5246.7  101.88  5253.1   102.6  5275.6  102.11  5302.8  103.38  5310.8  102.79
  5317.2  103.57  5365.4  104.32  5386.3  104.56  5395.8  105.07  5439.1  104.77
  5509.6  105.38    5524  106.41  5544.8  106.24  5562.9  107.11  5690.8  109.24
#Mann= 6 ,-1 , 0
  4877.6      .1       0  4973.5     .03       0  5054.3      .1       0
  5365.4     .12       0  5386.3      .1       0  5562.9     .05       0
Bank Sta=4973.5,5054.3
XS Rating Curve= 0 ,0
Exp/Cntr=0.3,0.1