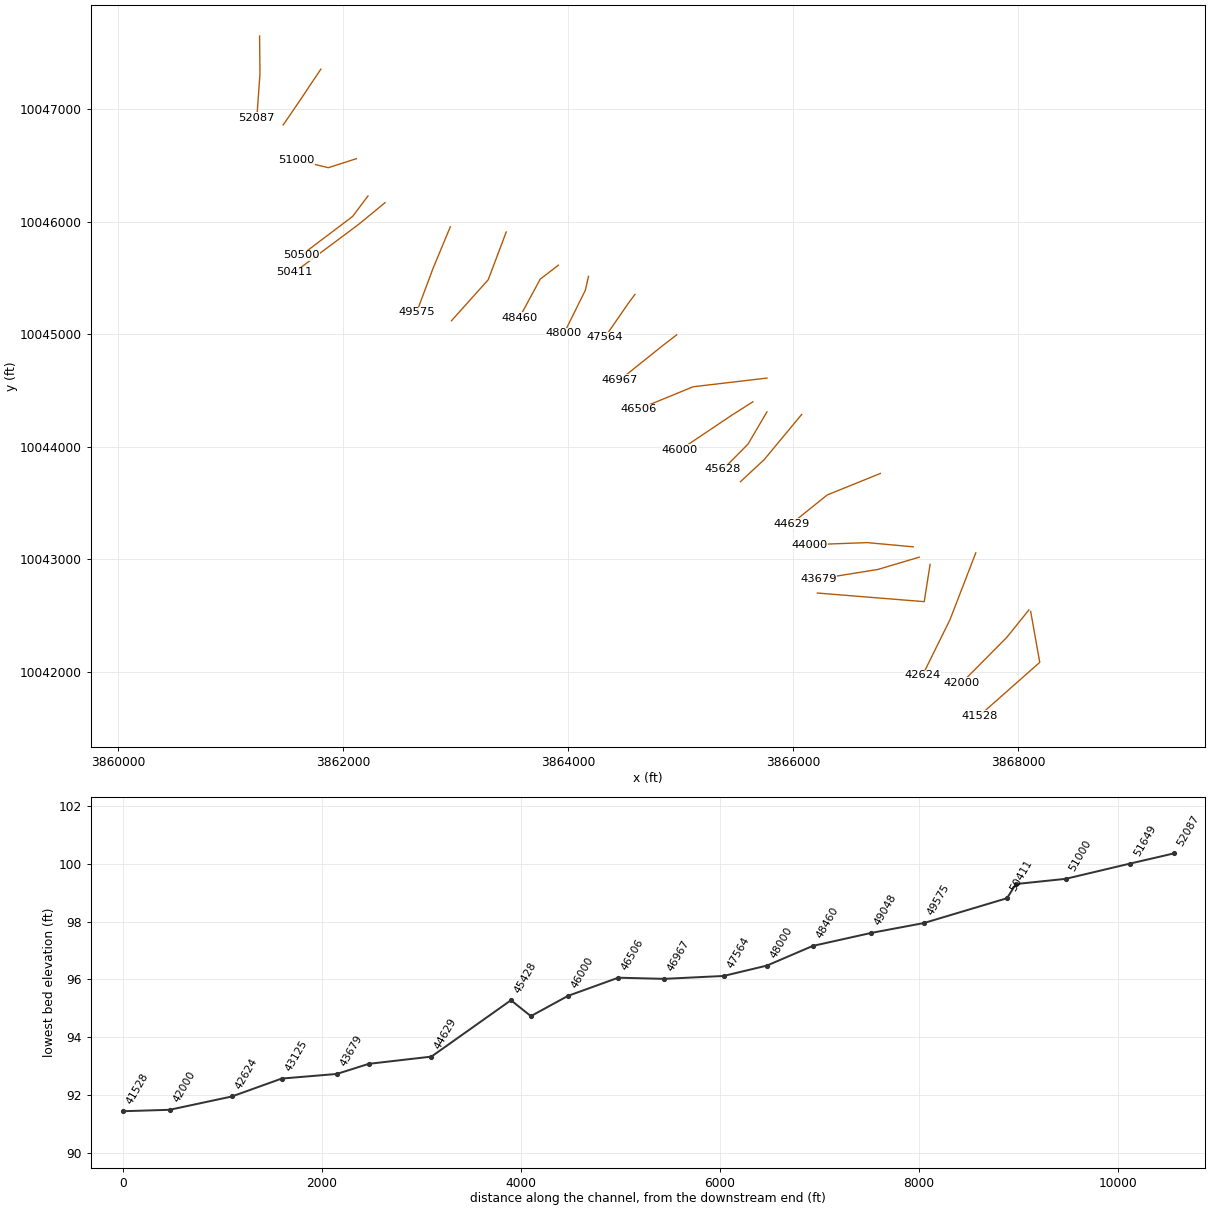
HEC-RAS study WOODSONS GULLY.prj: WOODSONS GULLY Base Level Engineering

--- WOODSONS GULLY.g10 (geometry) --- (continued)

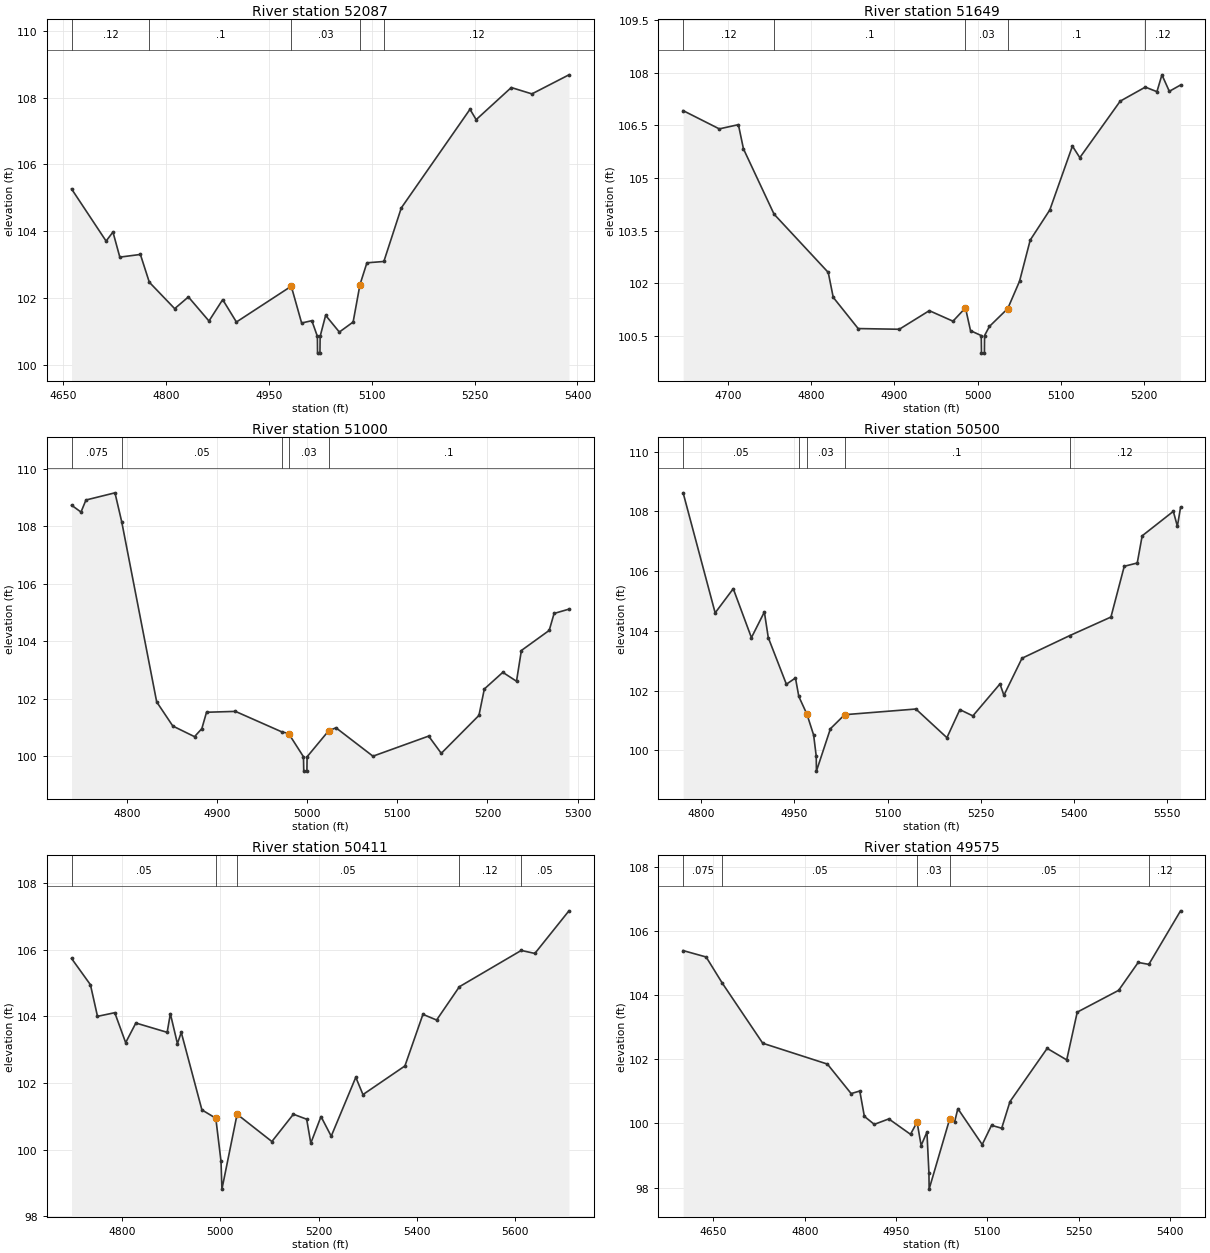
Type RM Length L Ch R = 1 ,52087   ,438,438,438
BEGIN DESCRIPTION:
WOODSONS GULLY 102.0
END DESCRIPTION:
XS GIS Cut Line= 3
      3861257.91     10047651.46      3861261.47     10047315.91
      3861233.38     10046927.19
#Sta/Elev= 30
  4662.3  105.27  4712.7  103.71  4722.7  103.98  4732.7  103.23  4762.7  103.31
  4775.7  102.48  4812.7  101.69  4832.7  102.04  4862.7  101.32  4882.7  101.96
  4902.7  101.29  4982.7  102.36  4997.8  101.26  5012.7  101.33  5020.8  100.86
    5021  100.36  5024.5  100.36  5024.8  100.86  5032.8  101.49  5052.8  100.99
  5072.9  101.29  5082.9  102.41    5093  103.06  5117.7   103.1  5143.1   104.7
  5243.3  107.65  5252.3  107.34  5303.5   108.3  5333.6  108.11  5387.6  108.68
#Mann= 5 ,-1 , 0
  4662.3     .12       0  4775.7      .1       0  4982.7     .03       0
  5082.9      .1       0  5117.7     .12       0
Bank Sta=4982.7,5082.9
XS Rating Curve= 0 ,0
Exp/Cntr=0.3,0.1

Type RM Length L Ch R = 1 ,51649   ,649,649,649
BEGIN DESCRIPTION:
WOODSONS GULLY 101.0
END DESCRIPTION:
XS GIS Cut Line= 3
      3861802.67     10047357.19      3861607.39     10047065.56
      3861467.87      10046861.1
#Sta/Elev= 30
  4645.7  106.92  4689.2   106.4  4712.2  106.52  4718.3  105.83  4755.1  103.97
  4820.3  102.31  4826.3   101.6  4856.3  100.71  4905.8  100.69  4941.9  101.22
  4970.4  100.92  4985.4   101.3  4991.5  100.65  5004.4  100.51  5004.7  100.01
  5008.2  100.01  5008.4  100.51  5014.2  100.77  5036.3  101.28  5050.5  102.06
  5063.3  103.23  5086.9  104.09  5114.1  105.91    5123  105.58  5171.6  107.19
  5201.8  107.59  5215.8  107.46  5221.8  107.94  5230.7  107.47  5244.2  107.65
#Mann= 5 ,-1 , 0
  4645.7     .12       0  4755.1      .1       0  4985.4     .03       0
  5036.3      .1       0  5201.8     .12       0
Bank Sta=4985.4,5036.3
XS Rating Curve= 0 ,0
Exp/Cntr=0.3,0.1

Type RM Length L Ch R = 1 ,51000   ,500,500,500
BEGIN DESCRIPTION:
WOODSONS GULLY 100.0
END DESCRIPTION:
XS GIS Cut Line= 3
      3862117.84     10046561.07      3861868.73      10046481.2
      3861586.58     10046549.93
#Sta/Elev= 30
  4738.4  108.74  4748.9   108.5  4754.4  108.92  4786.6  109.17  4794.1  108.16
  4832.9  101.89  4850.8  101.05  4874.9  100.68    4883  100.96  4888.2  101.53
  4920.3  101.56  4971.5  100.85  4979.3  100.79  4995.8   99.98  4996.1   99.48
  4999.6   99.48  4999.8   99.98  5023.6  100.88  5031.8  100.99  5072.9     100
  5134.7   100.7  5148.7   100.1  5190.5  101.42  5196.5  102.34    5217  102.92
  5232.2  102.61  5237.6  103.68  5268.5  104.38  5273.9  104.97  5290.4  105.12
#Mann= 5 ,-1 , 0
  4738.4    .075       0  4794.1     .05       0  4971.5      .1       0
  4979.3     .03       0  5023.6      .1       0
Bank Sta=4979.3,5023.6
XS Rating Curve= 0 ,0
Exp/Cntr=0.3,0.1

Type RM Length L Ch R = 1 ,50500   ,89,89,89
BEGIN DESCRIPTION:
WOODSONS GULLY 99.0
END DESCRIPTION:
XS GIS Cut Line= 3
      3862221.55     10046230.17      3862084.24      10046047.4
      3861628.61     10045703.09
#Sta/Elev= 30
  4771.4  108.62  4822.9   104.6    4852  105.41  4881.2  103.77    4902  104.63
  4908.3  103.77  4937.4  102.21    4952  102.42  4957.4   101.8 4970.51 101.202
  4981.2  100.51  4985.4    99.8  4985.7    99.3  5008.2  100.72  5031.1  101.19
  5145.6  101.38  5195.5  100.42  5216.3  101.36  5237.2  101.15  5280.8  102.22
  5287.1  101.84  5316.2  103.08  5393.1  103.84  5459.2  104.46  5480.6  106.16
  5501.5  106.27  5509.4  107.18  5559.5     108    5566   107.5  5571.1  108.13
#Mann= 5 ,-1 , 0
  4771.4     .05       0  4957.4      .1       0 4970.51     .03       0
  5031.1      .1       0  5393.1     .12       0
Bank Sta=4970.51,5031.1
XS Rating Curve= 0 ,0
Exp/Cntr=0.3,0.1

Type RM Length L Ch R = 1 ,50411   ,836,836,836
BEGIN DESCRIPTION:
WOODSONS GULLY 98.0
END DESCRIPTION:
XS GIS Cut Line= 3
      3862373.01     10046170.24      3862137.77     10045976.67
      3861569.17     10045553.05
#Sta/Elev= 30
  4696.6  105.74  4735.1  104.95  4749.5     104  4784.7  104.11  4806.9  103.21
  4827.7   103.8  4891.5  103.52    4898  104.08  4912.4  103.18  4920.2  103.52
  4962.3  101.19  4990.6  100.94  5001.2   99.65  5003.1   98.81    5034  101.06
  5104.9  100.24  5148.7  101.06  5175.8  100.91  5184.2  100.19    5205  100.99
  5225.8   100.4  5275.9  102.17  5290.5  101.65    5376  102.51  5412.7  104.06
  5440.6  103.89    5487  104.89  5613.1  105.98  5640.8  105.89  5710.3  107.17
#Mann= 5 ,-1 , 0
  4696.6     .05       0  4990.6     .03       0    5034     .05       0
    5487     .12       0  5613.1     .05       0
Bank Sta=4990.6,5034
XS Rating Curve= 0 ,0
Exp/Cntr=0.3,0.1

Type RM Length L Ch R = 1 ,49575   ,527,527,527
BEGIN DESCRIPTION:
WOODSONS GULLY 97.0
END DESCRIPTION:
XS GIS Cut Line= 3
      3862953.37     10045955.97      3862799.71     10045586.15
        3862654.     10045195.84
#Sta/Elev= 30
  4600.3  105.39  4638.1  105.19  4664.8  104.37  4731.1   102.5  4837.3  101.85
  4876.3  100.93  4890.5  101.01    4898  100.22  4914.3   99.97  4938.2  100.14
  4973.8   99.66  4984.6  100.04  4991.3   99.31  5000.8   99.73  5004.1   98.45
  5004.4   97.95  5038.2  100.14  5046.3  100.05  5051.6  100.46  5091.6   99.34
  5106.9   99.94  5123.6   99.85  5137.2  100.68  5198.3  102.34  5230.4  101.98
  5247.7  103.47  5315.7  104.15  5347.8  105.02  5365.3  104.96  5417.4  106.63
#Mann= 5 ,-1 , 0
  4600.3    .075       0  4664.8     .05       0  4984.6     .03       0
  5038.2     .05       0  5365.3     .12       0
Bank Sta=4984.6,5038.2
XS Rating Curve= 0 ,0
Exp/Cntr=0.3,0.1

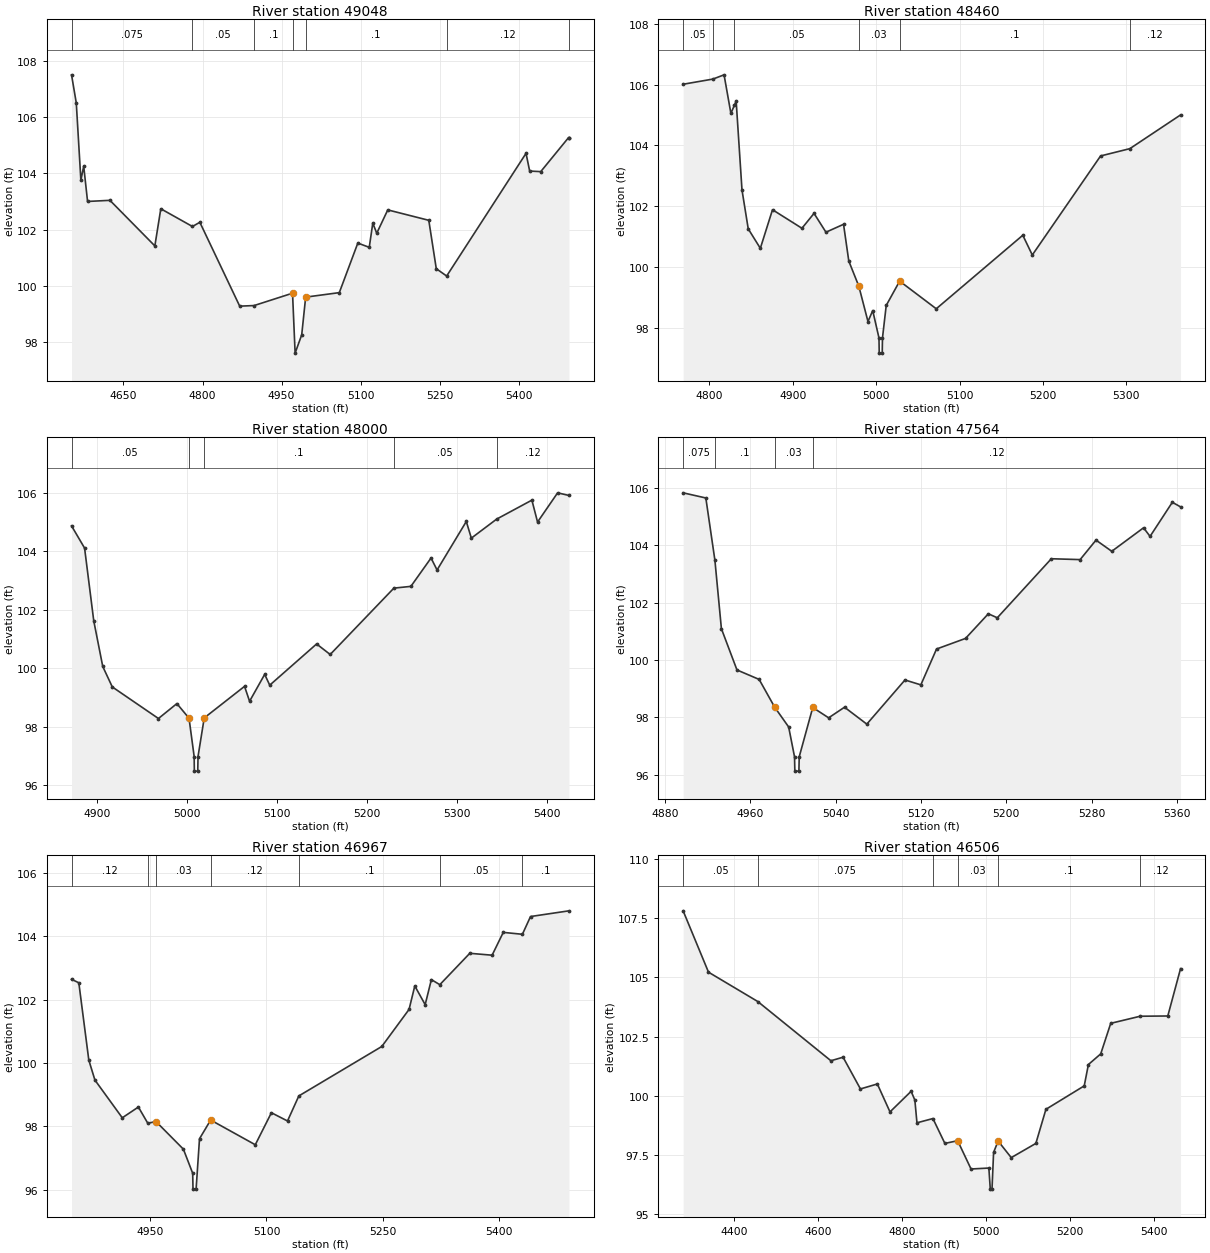
Type RM Length L Ch R = 1 ,49048   ,588,588,588
BEGIN DESCRIPTION:
WOODSONS GULLY 96.0
END DESCRIPTION:
XS GIS Cut Line= 3
      3863450.31     10045909.48      3863290.17     10045485.02
      3862963.34     10045120.43
#Sta/Elev= 30
  4551.6   107.5  4560.6   106.5  4569.3  103.76  4574.7  104.25    4582     103
  4624.4  103.04  4709.6  101.42  4720.9  102.74  4780.9  102.11  4794.9  102.26
  4870.5   99.28  4897.7    99.3  4970.7   99.74  4975.6   97.61  4988.1   98.26
  4995.6    99.6  5059.4   99.76  5094.5  101.52  5116.2  101.37  5122.9  102.23
  5130.4  101.87  5151.3   102.7  5229.1  102.33  5243.3  100.61    5263  100.35
  5413.5  104.71  5420.4  104.08  5441.4  104.06  5494.2  105.27  5494.9  105.27
#Mann= 7 ,-1 , 0
  4551.6    .075       0  4780.9     .05       0  4897.7      .1       0
  4970.7     .03       0  4995.6      .1       0    5263     .12       0
  5494.2     .05       0
Bank Sta=4970.7,4995.6
XS Rating Curve= 0 ,0
Exp/Cntr=0.3,0.1

Type RM Length L Ch R = 1 ,48460   ,460,460,460
BEGIN DESCRIPTION:
WOODSONS GULLY 95.0
END DESCRIPTION:
XS GIS Cut Line= 3
      3863913.86     10045614.36      3863752.41     10045490.66
      3863565.75     10045144.58
#Sta/Elev= 30
  4768.5  106.01  4804.2  106.18  4817.6  106.32  4825.8  105.05    4830  105.32
  4832.1  105.46  4839.1  102.53  4846.6  101.25  4861.1  100.61  4875.7  101.88
    4911  101.27  4925.5  101.76  4939.8  101.14  4960.9   101.4  4967.2  100.19
 4979.26  99.361  4990.2    98.2  4995.9   98.56  5003.4   97.66  5003.7   97.16
  5007.3   97.16  5007.6   97.66  5012.1   98.73  5028.2   99.53  5072.1   98.62
  5175.9  101.04  5187.3  100.39  5269.2  103.65  5304.3  103.89  5365.1     105
#Mann= 6 ,-1 , 0
  4768.5     .05       0  4804.2    .075       0    4830     .05       0
 4979.26     .03       0  5028.2      .1       0  5304.3     .12       0
Bank Sta=4979.26,5028.2
XS Rating Curve= 0 ,0
Exp/Cntr=0.3,0.1

Type RM Length L Ch R = 1 ,48000   ,436,436,436
BEGIN DESCRIPTION:
WOODSONS GULLY 94.0
END DESCRIPTION:
XS GIS Cut Line= 3
       3864181.7     10045515.17      3864152.98     10045390.33
      3863964.22     10045009.77
#Sta/Elev= 30
  4871.9  104.87  4886.4  104.11  4896.6  101.62  4906.6  100.06  4917.2   99.36
  4968.5   98.28    4989   98.79  5002.5   98.29  5008.2   96.98  5008.4   96.48
  5012.2   96.48  5012.5   96.98  5019.4    98.3  5064.2   99.38  5069.8   98.87
  5086.6   99.79  5092.2   99.42  5144.3  100.83  5159.4  100.47  5230.2  102.74
  5249.1   102.8  5271.5  103.77  5278.2  103.36  5310.7  105.02  5316.3  104.45
  5344.4   105.1  5383.6  105.75  5389.9     105  5412.2     106  5424.8  105.91
#Mann= 5 ,-1 , 0
  4871.9     .05       0  5002.5     .03       0  5019.4      .1       0
  5230.2     .05       0  5344.4     .12       0
Bank Sta=5002.5,5019.4
XS Rating Curve= 0 ,0
Exp/Cntr=0.3,0.1

Type RM Length L Ch R = 1 ,47564   ,597,597,597
BEGIN DESCRIPTION:
WOODSONS GULLY 93.0
END DESCRIPTION:
XS GIS Cut Line= 3
      3864594.42     10045354.64      3864534.74     10045274.34
      3864326.43     10044972.73
#Sta/Elev= 30
  4896.9  105.83  4918.2  105.65  4926.7  103.48  4932.8  101.09  4947.4   99.65
  4968.2   99.32  4982.8   98.35  4995.9   97.66  5001.4   96.62  5001.7   96.12
  5005.5   96.12  5005.8   96.62  5018.5   98.34  5033.4   97.98  5048.3   98.35
  5069.2   97.76    5105    99.3  5119.9   99.13  5134.6  100.38  5161.8  100.75
  5183.2  101.61  5191.6  101.47  5242.3  103.53  5269.3   103.5  5284.2  104.18
    5299  103.79  5328.8  104.61  5334.9  104.31  5355.8   105.5  5363.5  105.34
#Mann= 4 ,-1 , 0
  4896.9    .075       0  4926.7      .1       0  4982.8     .03       0
  5018.5     .12       0
Bank Sta=4982.8,5018.5
XS Rating Curve= 0 ,0
Exp/Cntr=0.3,0.1

Type RM Length L Ch R = 1 ,46967   ,461,461,461
BEGIN DESCRIPTION:
WOODSONS GULLY 92.0
END DESCRIPTION:
XS GIS Cut Line= 3
      3864965.51     10044995.48       3864842.9     10044901.08
      3864462.55     10044596.37
#Sta/Elev= 30
  4848.4  102.64  4857.8  102.53  4870.7  100.09  4878.6   99.46  4913.9   98.27
  4934.7   98.61  4946.8    98.1  4957.5   98.15  4992.8   97.28  5004.8   96.52
  5005.2   96.02  5009.2   96.02  5013.6   97.61    5028    98.2  5085.6   97.42
  5106.4   98.43  5127.2   98.17  5141.8   98.96  5248.9  100.52  5284.1  101.69
  5291.5  102.43  5304.9  101.84  5312.9  102.63  5323.8  102.47  5362.5  103.46
  5391.3   103.4  5405.7  104.12  5430.4  104.06  5440.9  104.62  5490.5   104.8
#Mann= 7 ,-1 , 0
  4848.4     .12       0  4946.8     .05       0  4957.5     .03       0
    5028     .12       0  5141.8      .1       0  5323.8     .05       0
  5430.4      .1       0
Bank Sta=4957.5,5028
XS Rating Curve= 0 ,0
Exp/Cntr=0.3,0.1

Type RM Length L Ch R = 1 ,46506   ,506,506,506
BEGIN DESCRIPTION:
WOODSONS GULLY 91.0
END DESCRIPTION:
XS GIS Cut Line= 3
       3865767.9     10044611.08      3865111.49     10044533.89
      3864625.42     10044334.25
#Sta/Elev= 30
  4277.7  107.81  4338.2  105.22  4455.8  103.98  4630.2  101.48  4659.2  101.63
  4700.6  100.29  4740.9   100.5  4771.1   99.32  4821.5  100.19  4830.4   99.82
  4835.4   98.86  4873.5   99.04    4902   97.99  4932.5  98.104  4964.4   96.91
  5006.9   96.95  5010.3   96.06  5014.4   96.06  5018.2   97.61    5029   98.09
  5060.3   97.39    5119   97.99    5143   99.43  5234.4  100.42  5244.3  101.32
  5273.7  101.77  5297.6  103.06  5367.9  103.36  5433.7  103.37  5464.1  105.37
#Mann= 6 ,-1 , 0
  4277.7     .05       0  4455.8    .075       0  4873.5      .1       0
  4932.5     .03       0    5029      .1       0  5367.9     .12       0
Bank Sta=4932.5,5029
XS Rating Curve= 0 ,0
Exp/Cntr=0.3,0.1

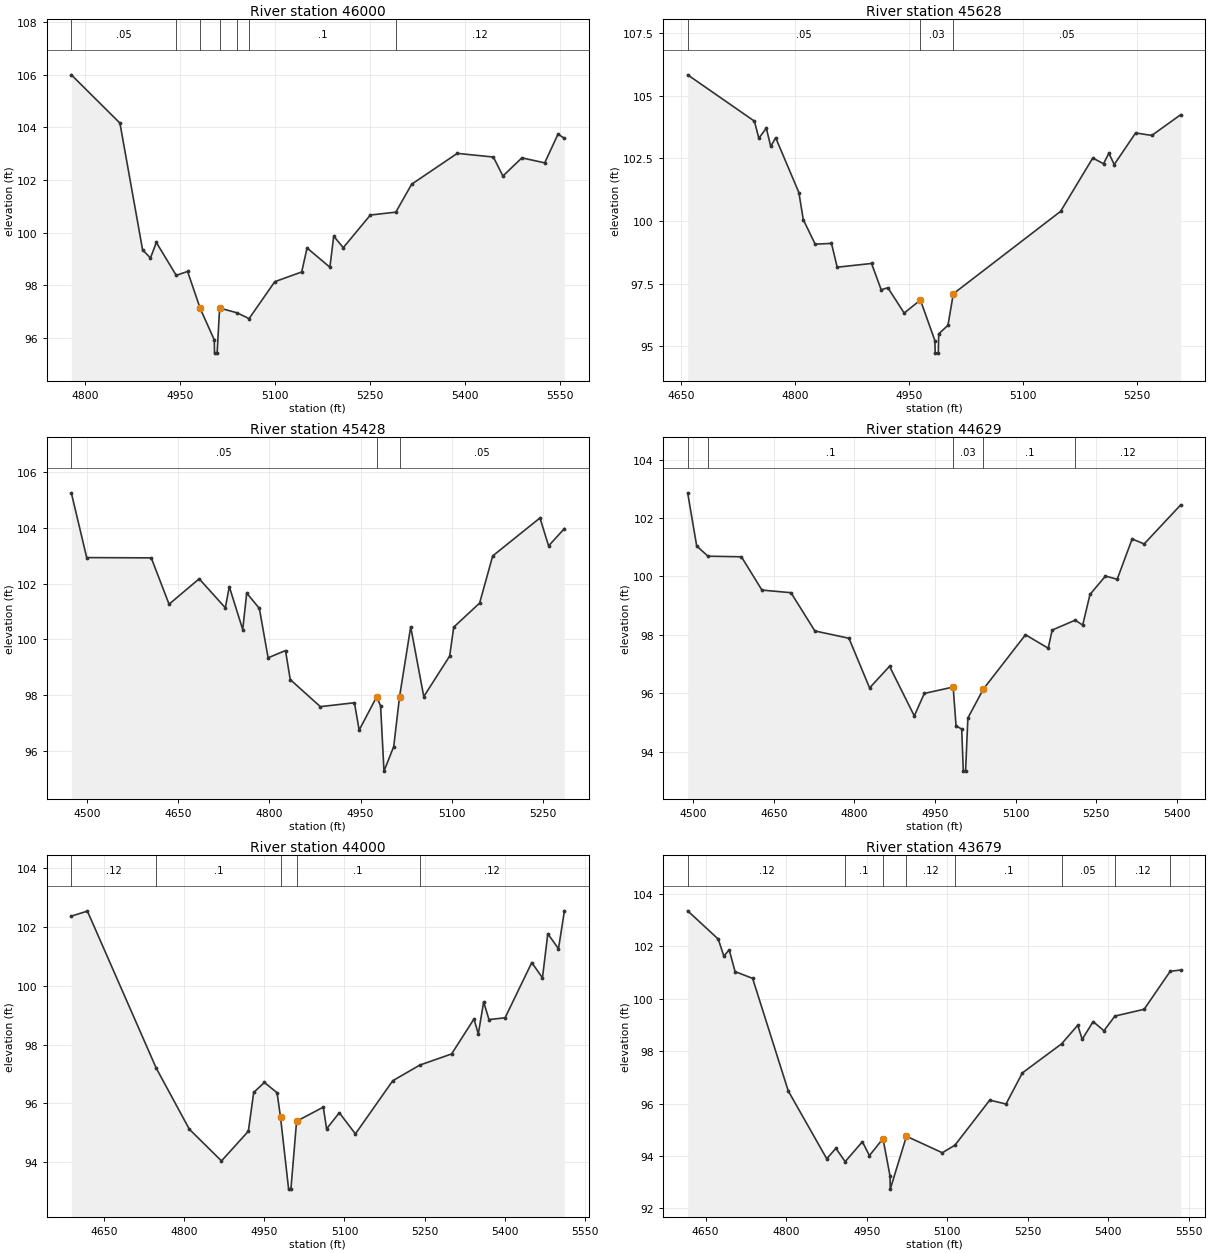
Type RM Length L Ch R = 1 ,46000   ,372,372,372
BEGIN DESCRIPTION:
WOODSONS GULLY 90.0
END DESCRIPTION:
XS GIS Cut Line= 3
      3865642.76     10044400.23      3865456.16     10044281.64
      3864993.49     10043971.14
#Sta/Elev= 30
  4778.9  105.99  4855.6  104.16  4891.4   99.35  4903.8   99.04  4913.1   99.63
  4944.5   98.38  4962.4   98.53 4982.33  97.124  5004.6   95.93  5004.9   95.43
    5009   95.43    5013   97.14  5040.5   96.96  5059.5   96.74    5100   98.14
  5142.5   98.51    5151   99.42    5187   98.69  5193.1   99.87  5208.1   99.43
  5250.9  100.67  5291.1  100.78  5316.1  101.84  5388.1  103.01  5445.1  102.87
  5460.1  102.15  5490.1  102.84  5526.1  102.65  5547.1  103.74  5557.2  103.58
#Mann= 7 ,-1 , 0
  4778.9     .05       0  4944.5    .075       0 4982.33     .03       0
    5013    .075       0  5040.5     .05       0  5059.5      .1       0
  5291.1     .12       0
Bank Sta=4982.33,5013
XS Rating Curve= 0 ,0
Exp/Cntr=0.3,0.1

Type RM Length L Ch R = 1 ,45628   ,200,200,200
BEGIN DESCRIPTION:
WOODSONS GULLY 89.0
END DESCRIPTION:
XS GIS Cut Line= 3
      3865767.87      10044311.1      3865600.21     10044025.21
      3865376.24     10043798.64
#Sta/Elev= 30
  4658.3  105.84  4746.3  103.99  4752.1  103.31    4762  103.71  4767.8  102.98
  4774.3  103.33  4804.9  101.14  4810.7  100.06  4826.4   99.08  4847.9   99.11
  4855.4   98.16  4900.7   98.31  4913.4   97.26  4922.2   97.34  4943.7   96.33
  4965.1   96.85  4984.2   95.23  4984.6   94.73  4988.7   94.73  4989.2    95.5
  5001.4   95.84  5008.5    97.1  5149.9  100.39  5192.3  102.52  5206.5  102.29
  5213.5  102.71  5220.6  102.26  5248.8  103.52  5270.1  103.42  5308.3  104.25
#Mann= 3 , 0 , 0
  4658.3     .05       0  4965.1     .03       0  5008.5     .05       0
Bank Sta=4965.1,5008.5
XS Rating Curve= 0 ,0
Exp/Cntr=0.3,0.1

Type RM Length L Ch R = 1 ,45428   ,799,799,799
BEGIN DESCRIPTION:
WOODSONS GULLY 88.0
END DESCRIPTION:
XS GIS Cut Line= 3
      3866076.74      10044288.2      3865742.57     10043885.45
      3865532.21     10043689.82
#Sta/Elev= 30
  4474.6  105.25  4499.9  102.93    4606  102.92  4635.3  101.26  4684.8  102.17
  4727.8  101.13  4734.3  101.89  4756.4  100.35  4762.9  101.66  4783.7  101.11
  4798.1   99.34  4826.7    99.6  4834.5   98.56    4884   97.59    4940   97.73
  4947.8   96.75  4976.5   97.94    4983   97.62  4988.6   95.28  5004.6   96.16
 5014.21   97.95  5032.5  100.45    5054   97.95  5096.5    99.4  5103.3  100.44
  5145.8   101.3  5167.3  102.99    5245  104.35  5259.2  103.35  5285.2  103.97
#Mann= 3 , 0 , 0
  4474.6     .05       0  4976.5     .03       0 5014.21     .05       0
Bank Sta=4976.5,5014.21
XS Rating Curve= 0 ,0
Exp/Cntr=0.3,0.1

Type RM Length L Ch R = 1 ,44629   ,629,629,629
BEGIN DESCRIPTION:
WOODSONS GULLY 87.0
END DESCRIPTION:
XS GIS Cut Line= 3
      3866775.98      10043763.4      3866303.33       10043572.
      3865985.59     10043316.76
#Sta/Elev= 30
  4489.9  102.86  4506.7  101.04  4527.7  100.69  4589.9  100.67  4628.1   99.53
  4682.1   99.44  4726.6   98.13    4790   97.88  4828.4   96.18  4865.5   96.92
  4911.6   95.22  4930.2   95.99  4983.9   96.21  4989.3   94.88  4999.8   94.77
  5002.8   93.33    5007   93.33  5011.3   95.15  5040.1   96.14  5118.5      98
  5160.8   97.54  5168.1   98.16  5211.1    98.5  5224.9   98.33  5238.5   99.38
  5267.3  100.01  5289.1    99.9  5316.9  101.28  5339.3  101.11  5407.4  102.45
#Mann= 5 ,-1 , 0
  4489.9     .12       0  4527.7      .1       0  4983.9     .03       0
  5040.1      .1       0  5211.1     .12       0
Bank Sta=4983.9,5040.1
XS Rating Curve= 0 ,0
Exp/Cntr=0.3,0.1

Type RM Length L Ch R = 1 ,44000   ,321,321,321
BEGIN DESCRIPTION:
WOODSONS GULLY 86.0
END DESCRIPTION:
XS GIS Cut Line= 3
      3867067.82     10043111.07      3866658.24     10043148.57
      3866146.78     10043129.73
#Sta/Elev= 30
  4588.7  102.37  4618.8  102.54  4747.6    97.2  4809.6   95.12  4869.8   94.04
  4920.1   95.05  4930.1   96.37  4950.2   96.71  4973.9   96.36  4980.3   95.53
  4995.5   93.08  4999.8   93.08  5010.4   95.39  5060.4   95.87  5066.6   95.13
  5090.4   95.68  5120.5   94.96  5190.5   96.77    5241    97.3  5300.6   97.68
  5342.5   98.87  5350.6   98.36  5360.6   99.45  5370.6   98.85  5400.7   98.91
  5450.7  100.79  5470.7  100.27  5480.7  101.77  5500.7  101.26  5511.8  102.55
#Mann= 5 ,-1 , 0
  4588.7     .12       0  4747.6      .1       0  4980.3     .03       0
  5010.4      .1       0    5241     .12       0
Bank Sta=4980.3,5010.4
XS Rating Curve= 0 ,0
Exp/Cntr=0.3,0.1

Type RM Length L Ch R = 1 ,43679   ,554,554,554
BEGIN DESCRIPTION:
WOODSONS GULLY 85.0
END DESCRIPTION:
XS GIS Cut Line= 3
      3867122.47     10043019.49      3866754.39     10042910.11
      3866226.59     10042825.03
#Sta/Elev= 30
  4616.5  103.36  4673.5  102.28  4683.9  101.63  4693.9  101.87  4704.8  101.04
  4737.5  100.78  4803.9   96.48  4875.6   93.89  4892.6   94.29  4909.9   93.78
    4942   94.54  4955.1   94.01  4980.4   94.66  4993.5   93.23  4993.9   92.73
  5024.1   94.75  5090.9   94.12  5114.5   94.41  5179.3   96.13  5209.5   95.98
  5240.1   97.17  5313.1   98.28  5343.2   98.99  5351.5   98.45  5371.8   99.13
    5392   98.78  5412.4   99.34  5466.9    99.6  5515.4  101.05  5535.1   101.1
#Mann= 8 ,-1 , 0
  4616.5     .12       0  4909.9      .1       0  4980.4     .03       0
  5024.1     .12       0  5114.5      .1       0  5313.1     .05       0
  5412.4     .12       0  5515.4     .05       0
Bank Sta=4980.4,5024.1
XS Rating Curve= 0 ,0
Exp/Cntr=0.3,0.1

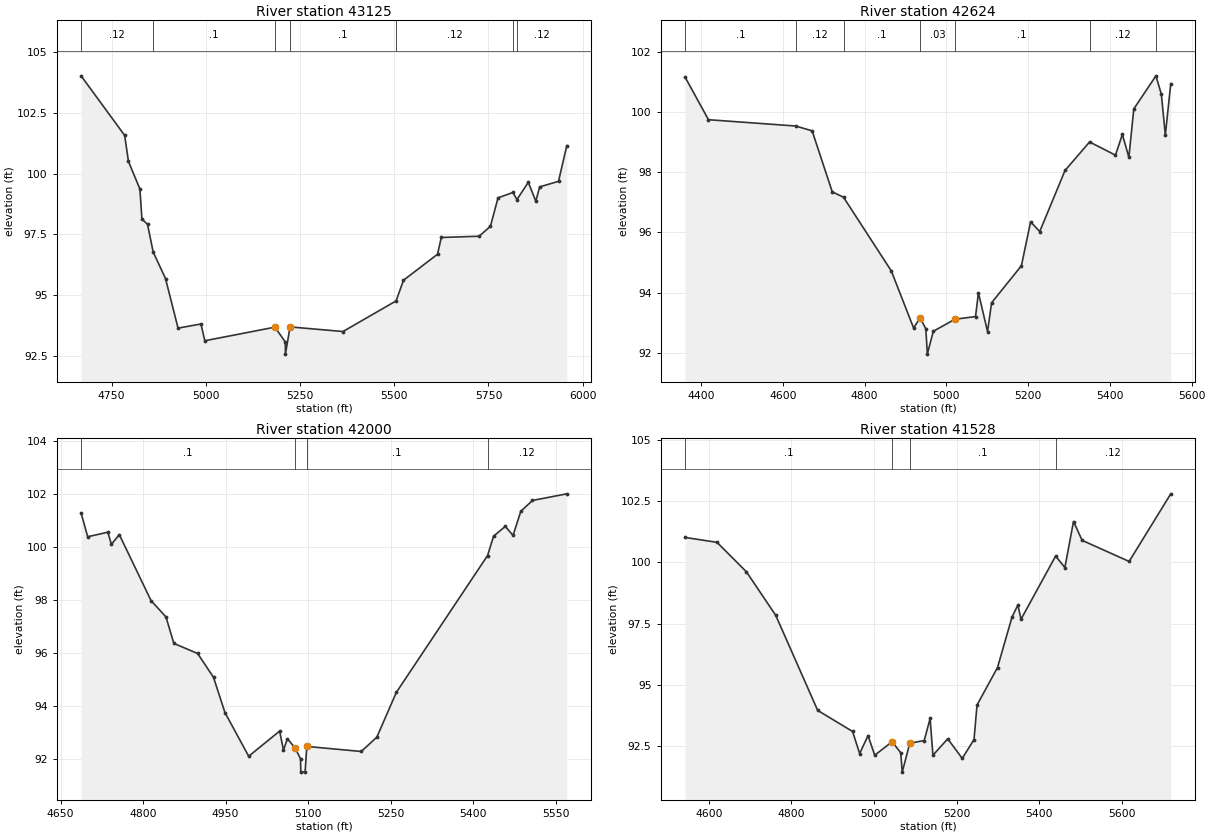
Type RM Length L Ch R = 1 ,43125   ,501,501,501
BEGIN DESCRIPTION:
WOODSONS GULLY 84.0
END DESCRIPTION:
XS GIS Cut Line= 3
      3867217.94     10042955.28      3867165.85     10042623.65
      3866215.94     10042700.35
#Sta/Elev= 30
  4669.2  104.02  4784.8  101.57  4794.9   100.5  4825.3   99.36  4830.6   98.13
  4845.5   97.91  4860.5   96.77  4893.2   95.68  4926.5   93.64  4987.3   93.81
  4997.4   93.12  5183.5   93.68    5211   93.07  5211.4   92.57  5223.6   93.69
  5364.1    93.5    5505   94.76  5524.6   95.61  5614.9   96.68  5624.9   97.37
  5725.2   97.42  5755.3   97.83  5775.4      99  5814.8   99.22  5825.7   98.93
  5855.7   99.64  5875.7   98.86  5885.8   99.45  5935.9   99.68  5957.9  101.15
#Mann= 7 ,-1 , 0
  4669.2     .12       0  4860.5      .1       0  5183.5     .03       0
  5223.6      .1       0    5505     .12       0  5814.8     .05       0
  5825.7     .12       0
Bank Sta=5183.5,5223.6
XS Rating Curve= 0 ,0
Exp/Cntr=0.3,0.1

Type RM Length L Ch R = 1 ,42624   ,624,624,624
BEGIN DESCRIPTION:
WOODSONS GULLY 83.0
END DESCRIPTION:
XS GIS Cut Line= 3
      3867624.18     10043057.66      3867395.02     10042463.93
      3867150.79     10041969.15
#Sta/Elev= 30
  4360.7  101.17    4418   99.75  4631.2   99.54  4671.6   99.38  4720.8   97.35
  4748.4   97.17  4865.2   94.72  4919.8   92.82  4935.9   93.16  4949.8   92.79
  4953.4   91.95    4968   92.71  5020.8   93.11  5071.3    93.2  5078.4   93.99
  5100.7    92.7  5110.6   93.66  5183.5   94.89    5206   96.35  5228.4   96.03
  5290.2   98.06  5350.3   99.01  5413.6   98.57  5430.5   99.26  5446.4    98.5
  5458.5  100.11  5512.6  101.21  5525.8   100.6  5535.6   99.24  5548.9  100.95
#Mann= 7 ,-1 , 0
  4360.7      .1       0  4631.2     .12       0  4748.4      .1       0
  4935.9     .03       0  5020.8      .1       0  5350.3     .12       0
  5512.6      .1       0
Bank Sta=4935.9,5020.8
XS Rating Curve= 0 ,0
Exp/Cntr=0.3,0.1

Type RM Length L Ch R = 1 ,42000   ,472,472,472
BEGIN DESCRIPTION:
WOODSONS GULLY 82.0
END DESCRIPTION:
XS GIS Cut Line= 3
      3868096.41      10042550.3      3867900.31     10042306.86
      3867498.77     10041901.88
#Sta/Elev= 30
  4687.4  101.28  4699.4  100.38  4736.1  100.55  4742.5  100.09  4756.9  100.46
  4814.5   97.97  4841.7   97.35  4856.1   96.35  4899.3   95.97  4928.1   95.07
  4948.9   93.74  4992.1   92.09  5048.3   93.04  5055.3   92.32  5062.4   92.75
  5076.6    92.4  5086.3   91.99  5086.8   91.49  5094.6   91.49  5097.7   92.46
  5196.7   92.27    5225   92.81  5260.4    94.5  5426.3   99.67  5437.2   100.4
  5458.4  100.77  5472.6  100.43  5486.7  101.34  5507.9  101.75  5570.3     102
#Mann= 4 ,-1 , 0
  4687.4      .1       0  5076.6     .03       0  5097.7      .1       0
  5426.3     .12       0
Bank Sta=5076.6,5097.7
XS Rating Curve= 0 ,0
Exp/Cntr=0.3,0.1

Type RM Length L Ch R = 1 ,41528   ,628,628,628
BEGIN DESCRIPTION:
WOODSONS GULLY 81.0
END DESCRIPTION:
XS GIS Cut Line= 3
      3868112.03     10042537.27      3868192.76     10042084.15
       3867656.3     10041610.19
#Sta/Elev= 30
  4542.5  101.02  4619.9  100.82    4691   99.62  4762.1   97.84  4863.7   93.96
  4948.1    93.1  4965.3    92.2  4985.6   92.93  5001.8   92.13  5043.9   92.68
  5064.8   92.23  5068.4   91.44  5086.6   92.62  5121.7   92.73  5135.9   93.63
  5142.7   92.13  5178.6    92.8  5213.7      92  5242.2   92.77  5249.5   94.18
  5299.1   95.71  5334.2   97.77  5348.4   98.26    5356   97.68  5439.8  100.26
  5462.2   99.79  5483.1  101.67    5504   100.9  5617.8  100.04  5718.6   102.8
#Mann= 4 ,-1 , 0
  4542.5      .1       0  5043.9     .03       0  5086.6      .1       0
  5439.8     .12       0
Bank Sta=5043.9,5086.6
XS Rating Curve= 0 ,0
Exp/Cntr=0.3,0.1