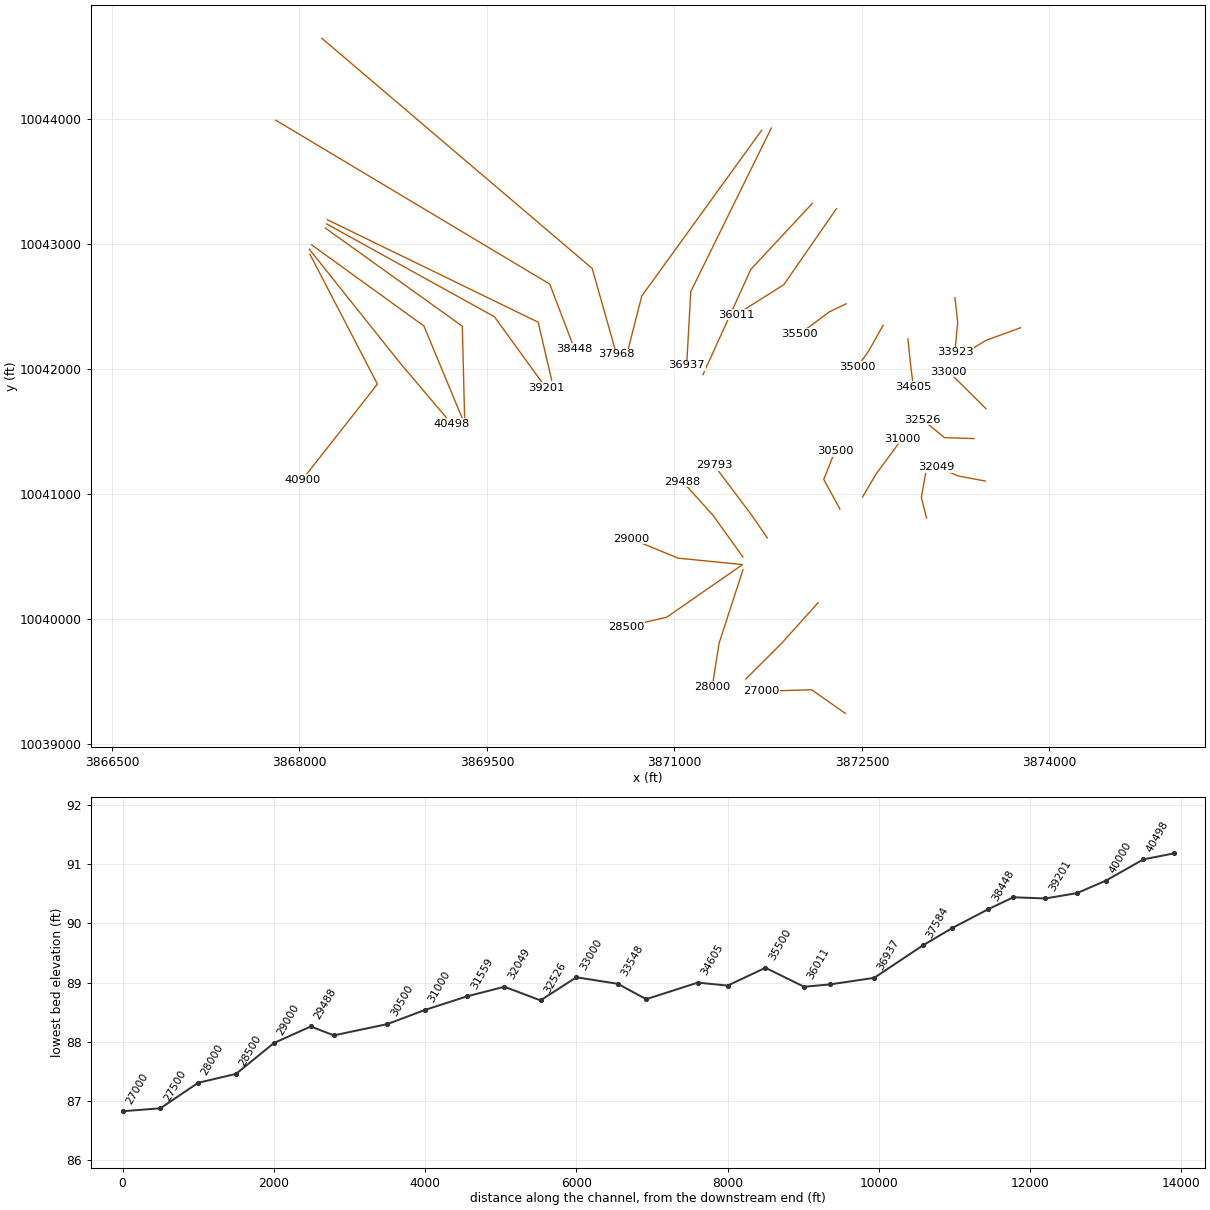
HEC-RAS study WOODSONS GULLY.prj: WOODSONS GULLY Base Level Engineering

--- WOODSONS GULLY.g10 (geometry) --- (continued)

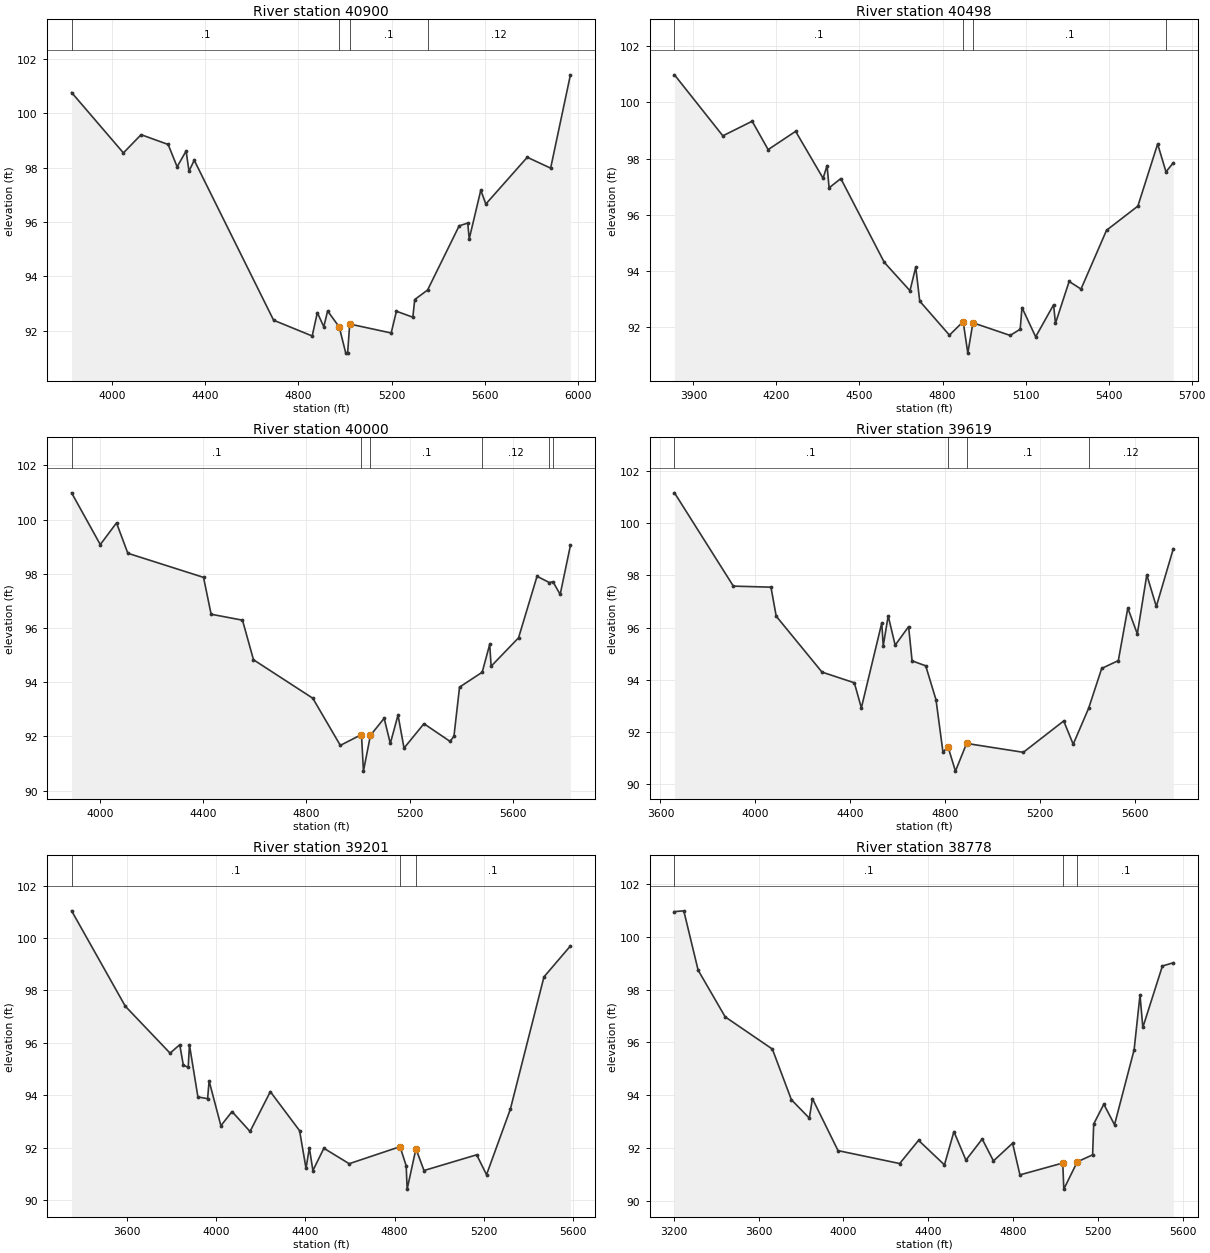
Type RM Length L Ch R = 1 ,40900   ,402,402,402
BEGIN DESCRIPTION:
WOODSONS GULLY 80.0
END DESCRIPTION:
XS GIS Cut Line= 3
      3868083.95     10042918.54      3868623.86     10041879.51
      3868023.42     10041115.31
#Sta/Elev= 30
  3825.7  100.76  4048.2   98.54  4124.2   99.21  4240.4   98.85    4279   98.03
  4317.6   98.61    4330   97.87  4352.5   98.27  4693.5   92.39  4859.2   91.81
  4881.3   92.67    4909   92.15  4925.5   92.73  4975.4   92.14  5003.4   91.18
  5011.4   91.18  5020.4   92.25  5198.5   91.92    5221   92.72  5291.6    92.5
  5299.7   93.15  5354.9    93.5  5490.6   95.86  5527.4   95.96  5533.8   95.38
  5583.5   97.17  5605.1   96.66  5783.1   98.38  5883.5   97.98  5968.5  101.41
#Mann= 4 ,-1 , 0
  3825.7      .1       0  4975.4     .03       0  5020.4      .1       0
  5354.9     .12       0
Bank Sta=4975.4,5020.4
XS Rating Curve= 0 ,0
Exp/Cntr=0.3,0.1

Type RM Length L Ch R = 1 ,40498   ,498,498,498
BEGIN DESCRIPTION:
WOODSONS GULLY 79.0
END DESCRIPTION:
XS GIS Cut Line= 3
      3868079.58     10042957.65      3868808.24     10042044.55
      3869217.87     10041561.05
#Sta/Elev= 30
  3831.8  100.98  4006.5   98.81  4112.4   99.33  4170.1   98.32  4269.4   98.97
  4368.6    97.3    4383   97.75  4390.3   96.96  4432.7   97.29  4589.6   94.31
  4682.5    93.3  4703.3   94.14  4717.7   92.93    4825   91.72  4874.6    92.2
  4891.4   91.08  4909.9   92.16  5044.3   91.71  5080.6   91.93  5087.1    92.7
  5136.5   91.66  5201.2    92.8    5208   92.14  5257.4   93.63  5300.3   93.36
  5392.5   95.45  5505.7   96.31  5577.1   98.52  5607.3   97.53  5633.7   97.85
#Mann= 4 ,-1 , 0
  3831.8      .1       0  4874.6     .03       0  4909.9      .1       0
  5607.3     .12       0
Bank Sta=4874.6,4909.9
XS Rating Curve= 0 ,0
Exp/Cntr=0.3,0.1

Type RM Length L Ch R = 1 ,40000   ,381,381,381
BEGIN DESCRIPTION:
WOODSONS GULLY 78.0
END DESCRIPTION:
XS GIS Cut Line= 3
      3868096.91     10042994.12       3868995.8     10042344.43
       3869311.5     10041584.39
#Sta/Elev= 30
  3890.9  100.99    4002   99.08  4064.8   99.88  4108.7   98.76  4401.9   97.87
  4431.3   96.51  4552.8   96.29  4595.4   94.83  4825.1   93.41  4931.8   91.67
  5013.7   92.07  5021.3   90.72  5048.4   92.04  5101.5   92.67  5125.4   91.74
  5155.2   92.79  5178.5   91.57  5255.6   92.47  5356.4   91.82  5371.8      92
  5393.5   93.82  5481.3   94.37  5510.4    95.4  5515.8   94.59  5622.1   95.64
  5693.7   97.91  5741.3   97.68  5755.4   97.71  5783.3   97.24    5823   99.05
#Mann= 6 ,-1 , 0
  3890.9      .1       0  5013.7     .03       0  5048.4      .1       0
  5481.3     .12       0  5741.3      .1       0  5755.4     .12       0
Bank Sta=5013.7,5048.4
XS Rating Curve= 0 ,0
Exp/Cntr=0.3,0.1

Type RM Length L Ch R = 1 ,39619   ,418,418,418
BEGIN DESCRIPTION:
WOODSONS GULLY 77.0
END DESCRIPTION:
XS GIS Cut Line= 3
      3868207.48     10043127.77      3869302.97     10042343.05
      3869322.07     10041589.54
#Sta/Elev= 30
    3659  101.16    3907   97.59  4065.4   97.55  4087.5   96.44  4280.4    94.3
  4416.7   93.89  4446.2   92.93  4532.2   96.18  4538.3    95.3  4559.2   96.45
  4588.7   95.33  4645.2   96.04  4659.9   94.73  4717.3   94.54  4760.7   93.24
  4790.1   91.23    4811   91.45  4842.6   90.51  4889.5   91.57  5128.6   91.23
  5298.6   92.43  5338.6   91.54  5403.4   92.91  5458.7   94.44  5528.7   94.74
  5568.7   96.75  5608.7   95.76  5648.7   98.02  5688.7   96.81  5760.3   99.02
#Mann= 4 ,-1 , 0
    3659      .1       0    4811     .03       0  4889.5      .1       0
  5403.4     .12       0
Bank Sta=4811,4889.5
XS Rating Curve= 0 ,0
Exp/Cntr=0.3,0.1

Type RM Length L Ch R = 1 ,39201   ,423,423,423
BEGIN DESCRIPTION:
Mapping XS 26df1587
END DESCRIPTION:
XS GIS Cut Line= 3
      3868218.81     10043160.67      3869559.93     10042418.49
      3869972.24     10041849.94
#Sta/Elev= 30
  3352.7  101.04  3593.3    97.4  3793.8   95.61  3837.3   95.93  3853.3   95.15
  3875.1   95.07  3880.8   95.92  3918.6   93.94  3962.1   93.87  3968.8   94.55
  4021.6   92.84  4071.6   93.38  4152.2   92.62  4243.1   94.14  4374.3   92.65
  4403.1   91.21  4417.9      92  4433.9   91.13  4483.1   91.98  4596.5   91.39
  4824.4   92.04  4851.9   91.31  4856.2   90.42  4895.6   91.96  4931.7   91.13
  5167.8   91.73  5211.9   90.97  5318.6   93.47  5469.3   98.52  5587.8    99.7
#Mann= 3 , 0 , 0
  3352.7      .1       0  4824.4     .03       0  4895.6      .1       0
Bank Sta=4824.4,4895.6
XS Rating Curve= 0 ,0
Exp/Cntr=0.3,0.1

Type RM Length L Ch R = 1 ,38778   ,330,330,330
BEGIN DESCRIPTION:
WOODSONS GULLY 76.0
END DESCRIPTION:
XS GIS Cut Line= 3
      3868222.79     10043194.94      3869910.26     10042374.65
      3870017.86     10041911.05
#Sta/Elev= 30
  3203.8  100.96  3247.7  100.99  3315.3   98.74  3442.9   96.97  3665.3   95.75
    3755   93.83  3839.7   93.13  3854.3   93.87    3975    91.9  4265.7   91.41
  4354.7   92.29  4476.8   91.36  4521.5   92.62  4578.1   91.54  4654.9   92.34
  4707.9   91.51  4798.1   92.18  4832.8   90.98  5034.8   91.43  5039.7   90.44
 5103.07  91.474  5175.5   91.74  5180.6   92.91  5228.4   93.66  5278.8   92.88
  5371.2   95.72    5399    97.8  5412.3   96.57  5504.7    98.9    5556   99.02
#Mann= 3 , 0 , 0
  3203.8      .1       0  5034.8     .03       0 5103.07      .1       0
Bank Sta=5034.8,5103.07
XS Rating Curve= 0 ,0
Exp/Cntr=0.3,0.1

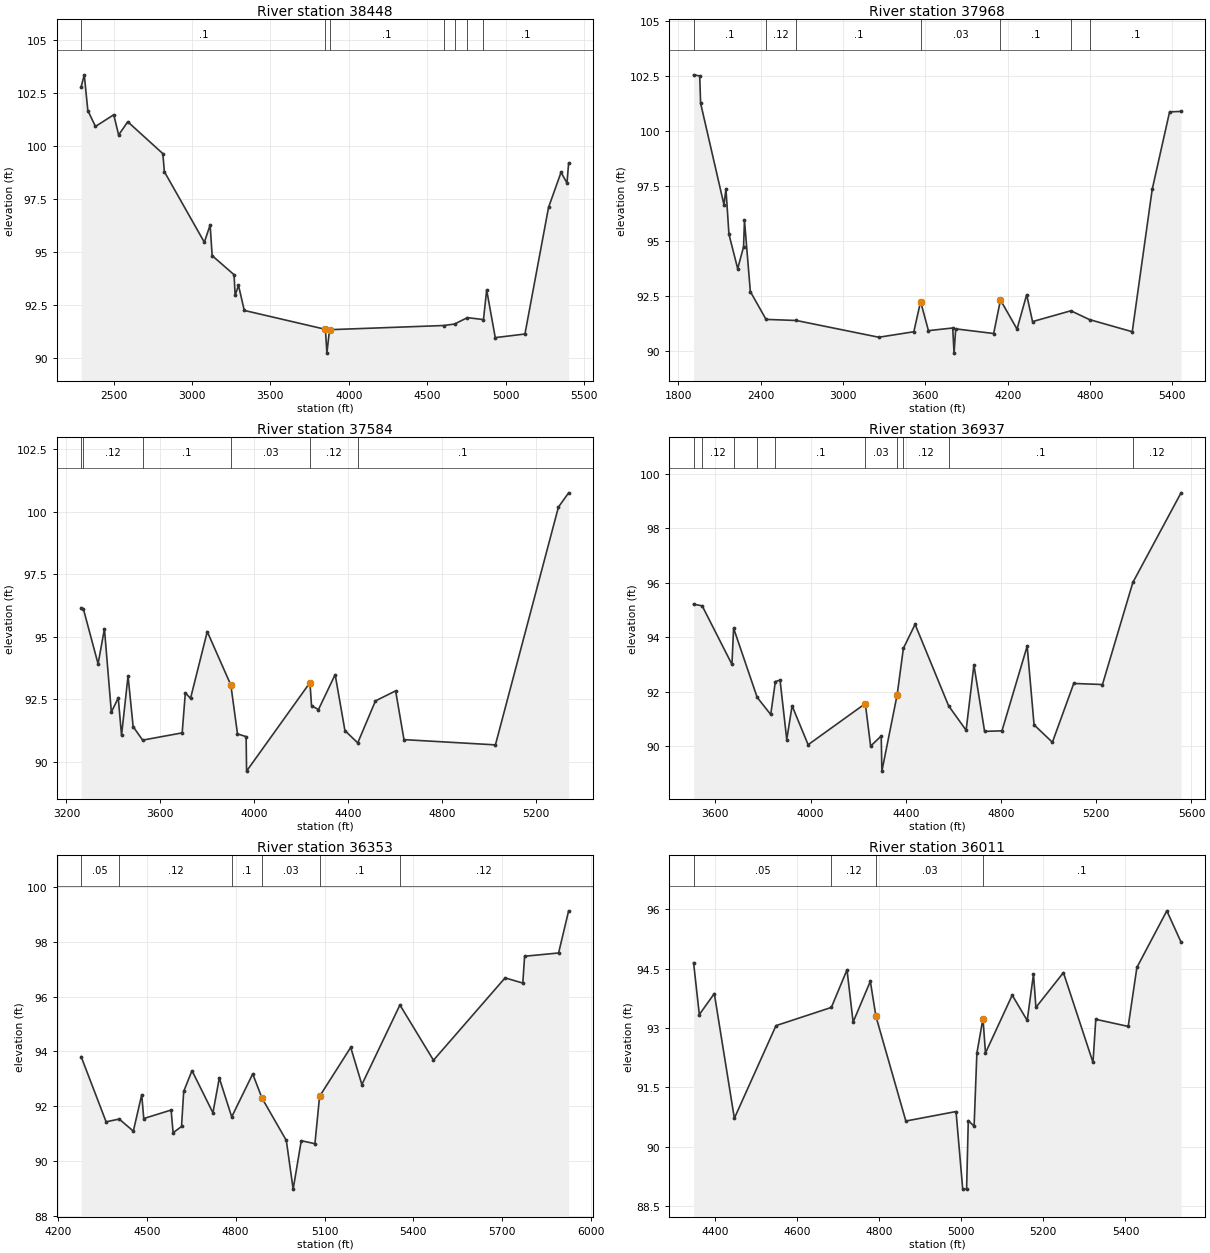
Type RM Length L Ch R = 1 ,38448   ,480,480,480
BEGIN DESCRIPTION:
WOODSONS GULLY 75.0
END DESCRIPTION:
XS GIS Cut Line= 3
      3867810.86     10043990.54      3870002.71     10042679.77
       3870200.2     10042161.08
#Sta/Elev= 30
  2293.2  102.78    2313  103.34  2335.7  101.66  2384.3  100.91    2501  101.46
  2532.1  100.51  2590.5  101.13  2814.2   99.63  2823.9   98.78  3078.7   95.46
  3115.7   96.27  3128.6   94.83  3268.4   93.93  3275.2   92.96  3296.6   93.43
  3333.5   92.25    3851   91.36  3860.3   90.24 3877.31  91.343  4606.4   91.54
  4674.4   91.61  4756.1   91.91    4859   91.82  4879.4   93.21  4934.2   90.97
  5123.5   91.14    5274    97.1  5353.7   98.75  5391.4   98.25  5402.1   99.17
#Mann= 7 ,-1 , 0
  2293.2      .1       0    3851     .03       0 3877.31      .1       0
  4606.4     .12       0  4674.4      .1       0  4756.1     .12       0
    4859      .1       0
Bank Sta=3851,3877.31
XS Rating Curve= 0 ,0
Exp/Cntr=0.3,0.1

Type RM Length L Ch R = 1 ,37968   ,384,384,384
BEGIN DESCRIPTION:
WOODSONS GULLY 74.0
END DESCRIPTION:
XS GIS Cut Line= 3
       3868179.8     10044645.91      3870342.12     10042804.77
      3870536.57     10042118.98
#Sta/Elev= 30
  1910.8  102.54  1955.5  102.49  1962.1  101.25  2132.3   96.65  2146.6   97.37
  2168.6   95.31  2232.3   93.75  2275.1   94.74  2281.7   95.94  2324.5   92.71
  2438.9   91.45  2659.8    91.4    3261   90.64    3516   90.89  3565.4   92.26
  3622.5   90.94  3799.5   91.06  3809.2   89.92  3821.2   91.02    4098   90.81
  4147.4   92.33  4268.2   91.01  4338.4   92.57  4381.3   91.35  4660.5   91.84
  4796.9   91.44    5108   90.89  5253.5   97.35  5380.1  100.86  5463.6  100.88
#Mann= 7 ,-1 , 0
  1910.8      .1       0  2438.9     .12       0  2659.8      .1       0
  3565.4     .03       0  4147.4      .1       0  4660.5     .12       0
  4796.9      .1       0
Bank Sta=3565.4,4147.4
XS Rating Curve= 0 ,0
Exp/Cntr=0.3,0.1

Type RM Length L Ch R = 1 ,37584   ,647,647,647
BEGIN DESCRIPTION:
WOODSONS GULLY 73.0
END DESCRIPTION:
XS GIS Cut Line= 3
      3871698.01     10043910.37      3870738.82     10042584.43
      3870630.31     10042159.06
#Sta/Elev= 30
  3262.8   96.16  3272.5   96.11  3334.8   93.92  3361.9   95.32  3391.3   91.99
  3420.7   92.56  3434.7   91.06  3462.4   93.44  3484.1   91.41  3524.6   90.87
  3692.9   91.16  3706.3   92.76  3728.5   92.54  3799.7   95.21  3900.2   93.07
  3928.4   91.12  3965.2   91.01  3967.1   89.63    4237   93.17  4243.6   92.25
    4273   92.09  4344.2   93.49  4385.9   91.25  4440.4   90.76  4515.9   92.44
  4601.7   92.84  4637.3   90.89  5026.6   90.68  5294.9  100.19  5338.3  100.76
#Mann= 6 ,-1 , 0
  3262.8      .1       0  3272.5     .12       0  3524.6      .1       0
  3900.2     .03       0    4237     .12       0  4440.4      .1       0
Bank Sta=3900.2,4237
XS Rating Curve= 0 ,0
Exp/Cntr=0.3,0.1

Type RM Length L Ch R = 1 ,36937   ,584,584,584
BEGIN DESCRIPTION:
WOODSONS GULLY 72.0
END DESCRIPTION:
XS GIS Cut Line= 3
      3871775.29     10043928.19      3871130.75     10042619.58
       3871098.2     10042031.51
#Sta/Elev= 30
  3508.5   95.21  3544.6   95.15  3669.7      93  3676.6   94.33  3775.6   91.79
  3832.5   91.16  3852.1   92.37  3871.8   92.42  3899.9   90.24  3922.3   91.48
  3989.7   90.05  4229.9   91.56  4252.2      90  4296.7   90.37  4299.5   89.08
  4363.6   91.88  4389.9   93.59    4439   94.47  4579.7   91.48  4653.4   90.58
  4686.1   92.98    4731   90.54    4804   90.56  4909.8   93.67  4938.8   90.78
  5015.8   90.14  5105.5    92.3  5226.1   92.26  5353.8   96.01  5556.2    99.3
#Mann= 10 ,-1 , 0
  3508.5      .1       0  3544.6     .12       0  3676.6     .05       0
  3775.6     .12       0  3852.1      .1       0  4229.9     .03       0
  4363.6      .1       0  4389.9     .12       0  4579.7      .1       0
  5353.8     .12       0
Bank Sta=4229.9,4363.6
XS Rating Curve= 0 ,0
Exp/Cntr=0.3,0.1

Type RM Length L Ch R = 1 ,36353   ,342,342,342
BEGIN DESCRIPTION:
WOODSONS GULLY 71.0
END DESCRIPTION:
XS GIS Cut Line= 3
      3872102.94     10043324.84      3871611.21     10042796.86
      3871228.54     10041955.83
#Sta/Elev= 30
  4278.5   93.81  4362.7   91.43  4406.9   91.53  4454.6   91.09  4482.9   92.42
  4489.8   91.55  4582.1   91.86  4588.9   91.03  4617.3   91.26  4624.6   92.54
  4652.6    93.3  4723.3   91.76  4744.8   93.03  4786.7   91.61  4857.6   93.18
 4889.16  92.291    4971   90.75  4994.1   88.97  5021.5   90.74  5067.6   90.63
  5083.3   92.36  5188.4   94.15  5226.1   92.79  5354.5    95.7  5467.8   93.68
  5709.5   96.69  5769.3    96.5  5775.4   97.48  5890.1    97.6    5924   99.14
#Mann= 6 ,-1 , 0
  4278.5     .05       0  4406.9     .12       0  4786.7      .1       0
 4889.16     .03       0  5083.3      .1       0  5354.5     .12       0
Bank Sta=4889.16,5083.3
XS Rating Curve= 0 ,0
Exp/Cntr=0.3,0.1

Type RM Length L Ch R = 1 ,36011   ,511,511,511
BEGIN DESCRIPTION:
WOODSONS GULLY 70.0
END DESCRIPTION:
XS GIS Cut Line= 3
       3872296.1     10043282.54      3871874.95     10042674.72
      3871496.58     10042435.72
#Sta/Elev= 30
  4348.3   94.65  4362.3   93.34  4398.8   93.87  4447.6   90.72    4549   93.06
  4683.8   93.52  4721.9   94.47  4736.8   93.15  4778.7   94.18 4792.38  93.292
  4865.2   90.65  4987.4   90.89  5003.7   88.93  5013.1   88.93  5017.2   90.66
  5031.4   90.52  5038.1   92.36    5053   93.24  5059.1   92.37  5124.2   93.83
  5160.7   93.19    5176   94.36  5181.9   93.52  5248.9    94.4  5320.9   92.13
  5327.7   93.22  5406.6   93.04  5427.8   94.53  5500.7   95.96  5535.3   95.17
#Mann= 4 ,-1 , 0
  4348.3     .05       0  4683.8     .12       0 4792.38     .03       0
    5053      .1       0
Bank Sta=4792.38,5053
XS Rating Curve= 0 ,0
Exp/Cntr=0.3,0.1

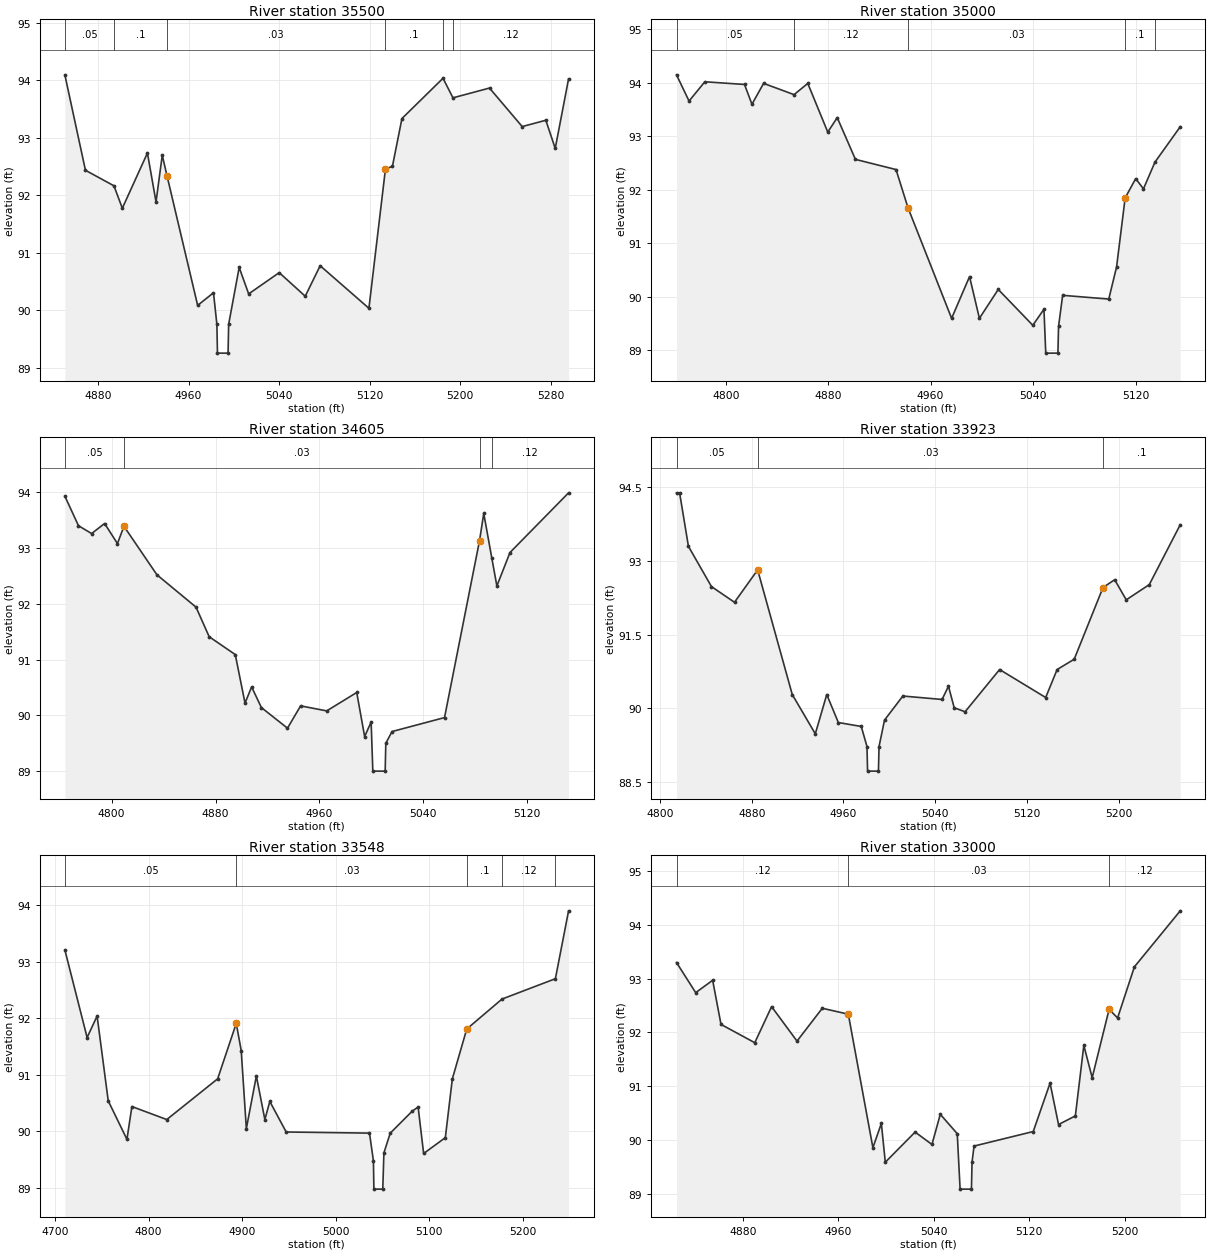
Type RM Length L Ch R = 1 ,35500   ,500,500,500
BEGIN DESCRIPTION:
WOODSONS GULLY 69.0
END DESCRIPTION:
XS GIS Cut Line= 3
      3872373.65     10042521.86      3872239.02     10042457.09
      3872001.77     10042280.27
#Sta/Elev= 30
  4850.6   94.09  4868.8   92.43    4894   92.16  4901.4   91.77  4923.6   92.73
  4931.2   91.88  4936.7   92.69 4940.92  92.333    4968   90.08    4982    90.3
    4985   89.75  4985.5   89.25  4994.9   89.25  4995.4   89.75  5004.7   90.74
  5013.1   90.28  5040.1   90.65  5063.1   90.24  5076.3   90.77  5119.4   90.03
    5134   92.45  5140.2    92.5  5148.6   93.33  5184.9   94.03  5193.7   93.69
    5226   93.86  5254.9   93.19  5275.8    93.3  5284.1   92.81  5295.9   94.02
#Mann= 6 ,-1 , 0
  4850.6     .05       0    4894      .1       0 4940.92     .03       0
    5134      .1       0  5184.9     .05       0  5193.7     .12       0
Bank Sta=4940.92,5134
XS Rating Curve= 0 ,0
Exp/Cntr=0.3,0.1

Type RM Length L Ch R = 1 ,35000   ,395,395,395
BEGIN DESCRIPTION:
WOODSONS GULLY 68.0
END DESCRIPTION:
XS GIS Cut Line= 3
      3872670.14      10042350.3      3872552.86     10042142.74
      3872464.06     10042015.82
#Sta/Elev= 30
  4761.6   94.15  4771.4   93.66  4783.7   94.02  4814.7   93.97  4820.5    93.6
  4829.6   93.99  4853.4   93.78  4864.1   93.99  4879.7   93.08  4887.1   93.35
  4901.3   92.57    4933   92.38 4942.31  91.668  4976.4    89.6  4990.4   90.38
  4998.1    89.6  5012.8   90.14  5039.8   89.47  5048.5   89.77  5049.9   88.95
  5059.4   88.95  5059.9   89.45  5063.1   90.03  5099.1   89.96  5105.2   90.56
  5111.9   91.85  5120.1   92.21  5126.2   92.02  5135.2   92.52  5154.9   93.18
#Mann= 5 ,-1 , 0
  4761.6     .05       0  4853.4     .12       0 4942.31     .03       0
  5111.9      .1       0  5135.2     .05       0
Bank Sta=4942.31,5111.9
XS Rating Curve= 0 ,0
Exp/Cntr=0.3,0.1

Type RM Length L Ch R = 1 ,34605   ,682,682,682
BEGIN DESCRIPTION:
WOODSONS GULLY 67.0
END DESCRIPTION:
XS GIS Cut Line= 3
      3872868.12     10042241.54      3872891.55     10042018.12
      3872912.39     10041856.31
#Sta/Elev= 30
    4764   93.93  4774.5    93.4  4784.6   93.26  4794.6   93.44  4804.5   93.08
  4809.5   93.39  4834.9   92.52    4865   91.94  4875.1   91.41  4895.2   91.09
  4902.7   90.22  4907.8   90.51  4915.3   90.14  4935.4   89.77  4945.5   90.17
  4965.6   90.08  4988.7   90.41  4994.8   89.62  4999.8   89.88  5001.1      89
  5010.6      89  5011.1    89.5  5015.9   89.71  5056.3   89.96 5083.25  93.133
  5086.5   93.62  5092.7   92.82  5096.6   92.32  5106.7   92.92  5151.8   93.99
#Mann= 4 ,-1 , 0
    4764     .05       0  4809.5     .03       0 5083.25      .1       0
  5092.7     .12       0
Bank Sta=4809.5,5083.25
XS Rating Curve= 0 ,0
Exp/Cntr=0.3,0.1

Type RM Length L Ch R = 1 ,33923   ,375,375,375
BEGIN DESCRIPTION:
WOODSONS GULLY 66.0
END DESCRIPTION:
XS GIS Cut Line= 3
      3873244.25      10042571.4      3873266.47     10042374.19
      3873244.33     10042134.16
#Sta/Elev= 30
  4814.3   94.39    4817   94.39  4824.7    93.3  4844.8   92.48  4864.9   92.16
  4885.1   92.82  4915.3   90.28  4935.4   89.48  4945.4   90.28  4955.5   89.71
  4975.5   89.63  4980.5   89.22    4981   88.72  4990.5   88.72    4991   89.22
  4995.8   89.76  5011.8   90.25    5046   90.18  5051.6   90.45  5056.6   90.01
  5066.1   89.93  5096.2   90.79  5136.4   90.22  5146.4   90.79  5161.3      91
  5186.4   92.46  5196.6   92.62  5206.7   92.21  5226.8   92.52  5253.8   93.74
#Mann= 3 , 0 , 0
  4814.3     .05       0  4885.1     .03       0  5186.4      .1       0
Bank Sta=4885.1,5186.4
XS Rating Curve= 0 ,0
Exp/Cntr=0.3,0.1

Type RM Length L Ch R = 1 ,33548   ,548,548,548
BEGIN DESCRIPTION:
WOODSONS GULLY 65.0
END DESCRIPTION:
XS GIS Cut Line= 3
      3873770.23     10042330.61       3873491.6     10042229.05
      3873285.83     10042101.43
#Sta/Elev= 30
  4710.5   93.21  4734.3   91.66    4745   92.04  4756.9   90.54  4776.9   89.86
  4782.2   90.44  4819.5   90.21  4873.9   90.93  4893.8   91.91  4899.1   91.43
  4904.6   90.05  4915.3   90.98  4924.4   90.21  4929.7   90.53  4947.2   89.99
  5036.3   89.97  5040.5   89.48    5041   88.98  5050.5   88.98  5051.7   89.62
  5058.5   89.97  5082.1   90.36  5088.3   90.43  5094.2   89.61  5117.4   89.89
  5124.9   90.93  5140.3   91.81    5178   92.34  5235.1    92.7  5249.2    93.9
#Mann= 5 ,-1 , 0
  4710.5     .05       0  4893.8     .03       0  5140.3      .1       0
    5178     .12       0  5235.1      .1       0
Bank Sta=4893.8,5140.3
XS Rating Curve= 0 ,0
Exp/Cntr=0.3,0.1

Type RM Length L Ch R = 1 ,33000   ,474,474,474
BEGIN DESCRIPTION:
WOODSONS GULLY 64.0
END DESCRIPTION:
XS GIS Cut Line= 3
      3873492.65     10041683.08      3873368.09     10041806.71
      3873192.49     10041979.99
#Sta/Elev= 30
  4824.5    93.3  4840.6   92.74  4854.8   92.97  4861.8   92.15  4890.1   91.81
  4904.2   92.48  4925.5   91.84  4946.7   92.45  4968.5   92.34  4989.1   89.86
  4996.2   90.31  4999.5   89.59  5024.5   90.15  5038.6   89.92  5045.6   90.48
  5059.8   90.12  5062.2   89.09  5071.7   89.09  5072.2   89.59  5073.9   89.89
  5123.5   90.16  5137.6   91.06  5144.7   90.29  5158.8   90.45  5165.9   91.76
  5172.9   91.16  5187.1   92.43  5194.2   92.27  5208.3   93.22  5246.7   94.26
#Mann= 3 , 0 , 0
  4824.5     .12       0  4968.5     .03       0  5187.1     .12       0
Bank Sta=4968.5,5187.1
XS Rating Curve= 0 ,0
Exp/Cntr=0.3,0.1

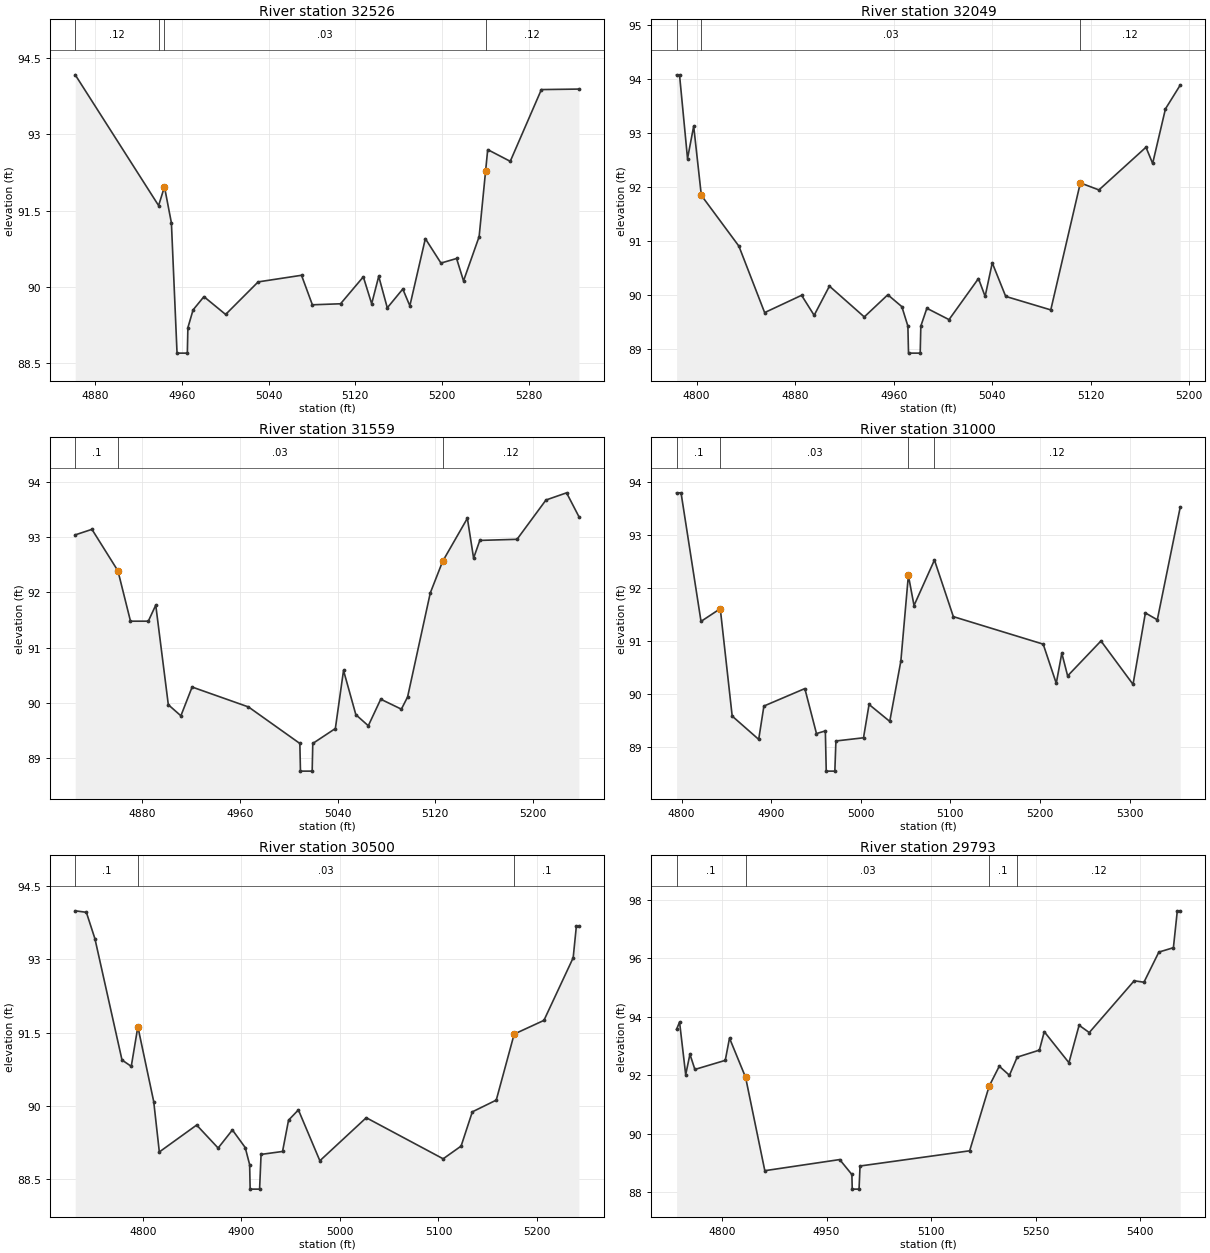
Type RM Length L Ch R = 1 ,32526   ,477,477,477
BEGIN DESCRIPTION:
WOODSONS GULLY 63.0
END DESCRIPTION:
XS GIS Cut Line= 3
      3873396.47     10041443.53      3873161.67      10041450.9
      3872983.88     10041596.17
#Sta/Elev= 30
  4861.7   94.17  4938.6    91.6    4944   91.97  4950.4   91.26  4955.6    88.7
  4965.1    88.7  4965.6    89.2  4970.4   89.55  4980.4   89.81  5000.4   89.46
  5030.4    90.1  5070.4   90.23  5080.4   89.65  5106.4   89.67  5127.4    90.2
  5135.1   89.67  5141.6   90.21  5149.5   89.59  5163.8   89.96  5170.3   89.63
  5184.6   90.95    5199   90.47  5213.4   90.56  5219.8   90.12  5234.2   90.99
 5240.12  92.271  5242.1    92.7  5262.9   92.47  5291.6   93.88  5326.2   93.89
#Mann= 4 ,-1 , 0
  4861.7     .12       0  4938.6      .1       0    4944     .03       0
 5240.12     .12       0
Bank Sta=4944,5240.12
XS Rating Curve= 0 ,0
Exp/Cntr=0.3,0.1

Type RM Length L Ch R = 1 ,32049   ,490,490,490
BEGIN DESCRIPTION:
WOODSONS GULLY 62.0
END DESCRIPTION:
XS GIS Cut Line= 3
      3873487.58     10041103.69      3873272.78     10041144.05
      3873096.78     10041216.52
#Sta/Elev= 30
  4783.7   94.08  4786.1   94.08  4792.6   92.53  4797.6   93.13  4803.8   91.85
  4834.3   90.91  4855.2   89.68  4885.2      90  4895.4   89.63  4907.8   90.17
  4936.1    89.6  4955.2   90.01  4966.6   89.79  4971.5   89.43    4972   88.93
  4981.5   88.93    4982   89.43  4986.9   89.76  5004.9   89.55  5028.8   90.31
  5034.2   89.98    5040    90.6  5050.9   89.98  5087.5   89.73  5111.5   92.08
  5126.6   91.95  5164.8   92.74  5170.2   92.44  5180.6   93.45  5192.6   93.89
#Mann= 3 , 0 , 0
  4783.7     .12       0  4803.8     .03       0  5111.5     .12       0
Bank Sta=4803.8,5111.5
XS Rating Curve= 0 ,0
Exp/Cntr=0.3,0.1

Type RM Length L Ch R = 1 ,31559   ,559,559,559
BEGIN DESCRIPTION:
WOODSONS GULLY 61.0
END DESCRIPTION:
XS GIS Cut Line= 3
      3873017.32     10040807.12      3872975.65     10040972.07
      3873017.85     10041211.04
#Sta/Elev= 30
    4825   93.04  4838.7   93.14    4860   92.39  4870.3   91.48  4884.9   91.48
    4891   91.77  4901.3   89.97  4911.6   89.77  4920.8   90.29    4967   89.93
  5009.1   89.27  5009.6   88.77  5019.2   88.77  5019.7   89.27  5038.2   89.54
  5044.9   90.59    5055   89.79  5065.2   89.59  5075.4   90.07  5092.3   89.89
  5097.4   90.11    5116   91.99  5126.1   92.56  5146.4   93.34  5151.5   92.62
  5156.6   92.94  5187.1   92.96  5210.8   93.67  5227.7    93.8  5237.8   93.37
#Mann= 3 , 0 , 0
    4825      .1       0    4860     .03       0  5126.1     .12       0
Bank Sta=4860,5126.1
XS Rating Curve= 0 ,0
Exp/Cntr=0.3,0.1

Type RM Length L Ch R = 1 ,31000   ,500,500,500
BEGIN DESCRIPTION:
WOODSONS GULLY 60.0
END DESCRIPTION:
XS GIS Cut Line= 3
      3872506.14     10040977.52      3872610.06     10041155.04
      3872821.25     10041442.38
#Sta/Elev= 30
  4794.3    93.8  4799.3    93.8  4821.6   91.37  4843.1   91.61  4856.4   89.58
    4886   89.14  4891.8   89.77  4937.5    90.1  4950.5   89.25  4960.4    89.3
  4961.4   88.54    4971   88.54  4972.2   89.11    5003   89.17  5009.2    89.8
  5032.3   89.48  5044.7   90.62  5053.1   92.24  5059.4   91.67  5082.2   92.53
  5103.3   91.46  5203.6   90.94  5218.2    90.2  5224.4   90.77  5230.9   90.34
  5268.1      91  5303.9   90.18  5317.7   91.53    5331    91.4  5356.6   93.53
#Mann= 4 ,-1 , 0
  4794.3      .1       0  4843.1     .03       0  5053.1      .1       0
  5082.2     .12       0
Bank Sta=4843.1,5053.1
XS Rating Curve= 0 ,0
Exp/Cntr=0.3,0.1

Type RM Length L Ch R = 1 ,30500   ,707,707,707
BEGIN DESCRIPTION:
WOODSONS GULLY 59.0
END DESCRIPTION:
XS GIS Cut Line= 3
      3872323.86     10040881.15      3872194.67     10041116.86
      3872284.78      10041342.1
#Sta/Elev= 30
  4731.2   93.99  4742.5   93.96  4751.2   93.42  4778.7   90.94  4788.1   90.81
  4794.8   91.62  4810.9   90.09  4816.6   89.06  4854.5   89.61  4876.3   89.14
  4890.8   89.51  4903.8   89.15  4908.3    88.8  4908.8    88.3  4918.4    88.3
  4919.9   89.01  4941.7   89.07  4947.8   89.71  4957.8   89.92  4979.6   88.88
  5026.7   89.76  5104.8   88.92    5123   89.18  5134.4   89.88  5158.7   90.12
  5176.9   91.47  5207.1   91.75  5236.8   93.03    5240   93.67  5242.6   93.67
#Mann= 3 , 0 , 0
  4731.2      .1       0  4794.8     .03       0  5176.9      .1       0
Bank Sta=4794.8,5176.9
XS Rating Curve= 0 ,0
Exp/Cntr=0.3,0.1

Type RM Length L Ch R = 1 ,29793   ,305,305,305
BEGIN DESCRIPTION:
WOODSONS GULLY 58.0
END DESCRIPTION:
XS GIS Cut Line= 3
      3871743.12      10040649.4      3871619.42     10040829.09
      3871316.03     10041232.74
#Sta/Elev= 30
  4734.6   93.57  4738.9   93.82  4747.7   92.02  4753.8   92.72  4760.9    92.2
  4804.5   92.51  4810.6   93.27  4833.7   91.93  4861.3   88.74  4968.8   89.12
  4986.3   88.61  4986.8   88.11  4996.6   88.11    4998    88.9  5155.4   89.42
  5183.4   91.63  5197.9   92.31  5212.5      92  5223.6   92.62  5255.5   92.86
  5262.5   93.49  5297.9   92.43  5312.5   93.71  5327.1   93.46  5391.6   95.23
  5405.6   95.18    5427   96.21  5447.9   96.36  5453.5   97.62  5457.7   97.62
#Mann= 4 ,-1 , 0
  4734.6      .1       0  4833.7     .03       0  5183.4      .1       0
  5223.6     .12       0
Bank Sta=4833.7,5183.4
XS Rating Curve= 0 ,0
Exp/Cntr=0.3,0.1

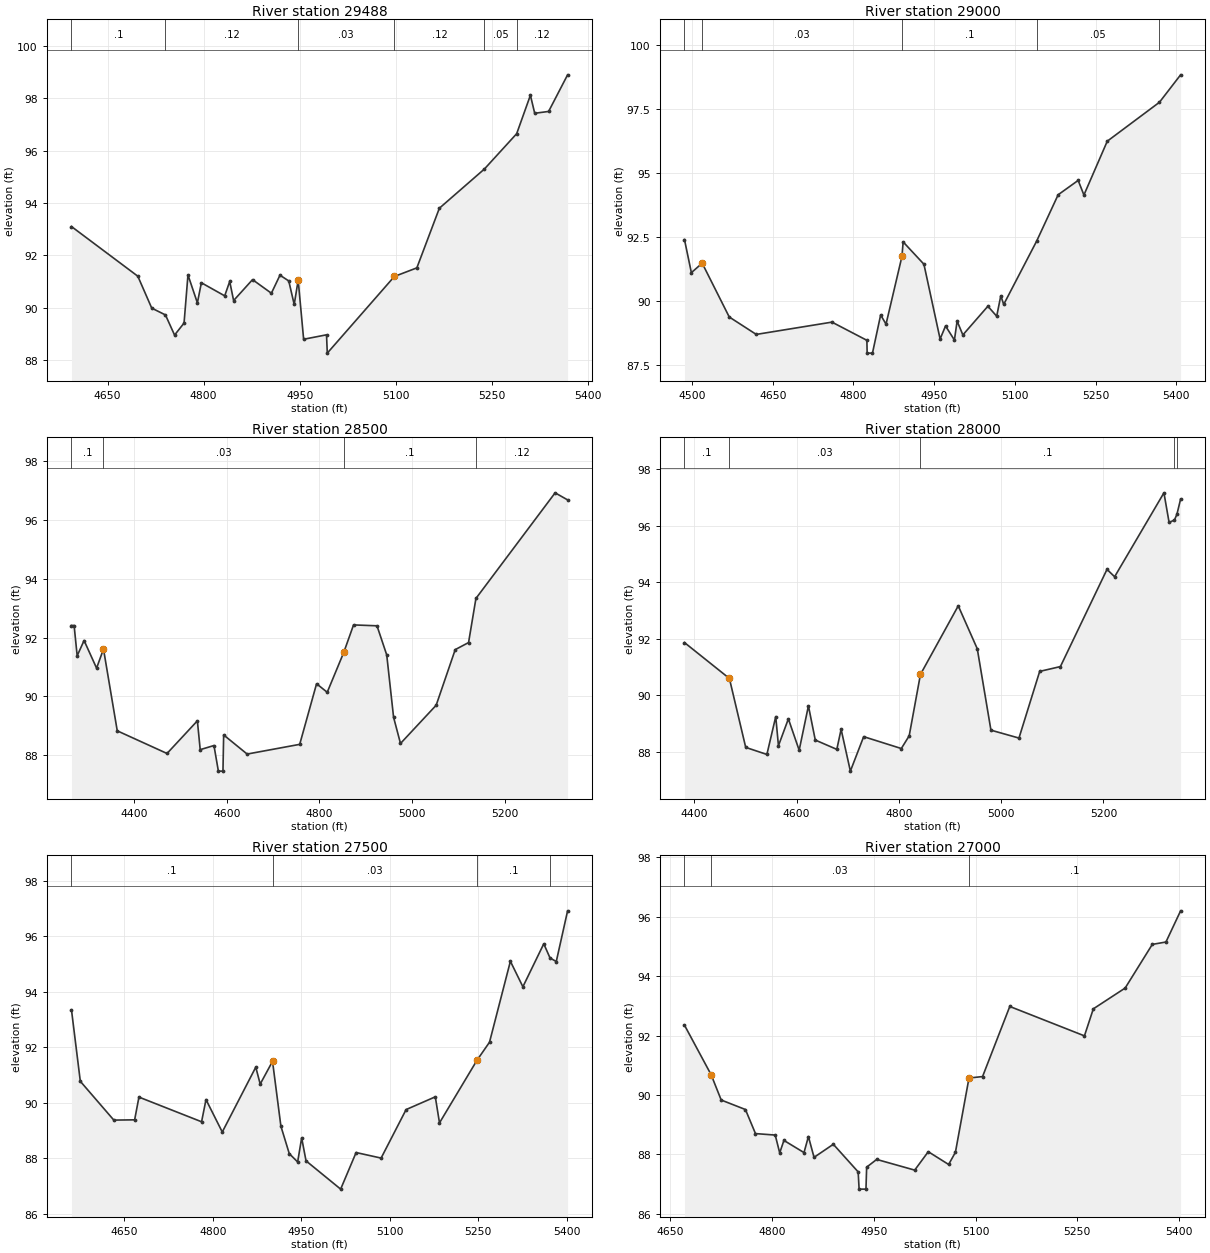
Type RM Length L Ch R = 1 ,29488   ,488,488,488
BEGIN DESCRIPTION:
WOODSONS GULLY 57.0
END DESCRIPTION:
XS GIS Cut Line= 3
      3871547.83     10040497.02      3871308.22     10040830.39
      3871064.72     10041099.94
#Sta/Elev= 30
  4593.8    93.1  4697.3    91.2    4719   89.98  4740.4   89.72  4754.6   88.95
  4769.4   89.41  4775.5   91.25  4790.2   90.18  4796.4   90.95  4832.8   90.45
  4840.6      91  4846.7   90.27  4876.2   91.07  4905.6   90.55    4919   91.24
  4932.7   91.02  4941.2   90.12  4947.4   91.05  4955.9   88.79  4991.6   88.96
  4992.8   88.26  5097.4   91.19  5132.5   91.52  5167.6    93.8  5237.9    95.3
  5288.2   96.65  5309.6   98.12  5316.3   97.43    5338    97.5  5367.6    98.9
#Mann= 6 ,-1 , 0
  4593.8      .1       0  4740.4     .12       0  4947.4     .03       0
  5097.4     .12       0  5237.9     .05       0  5288.2     .12       0
Bank Sta=4947.4,5097.4
XS Rating Curve= 0 ,0
Exp/Cntr=0.3,0.1

Type RM Length L Ch R = 1 ,29000   ,500,500,500
BEGIN DESCRIPTION:
WOODSONS GULLY 56.0
END DESCRIPTION:
XS GIS Cut Line= 3
      3871540.61     10040435.87      3871029.17     10040487.15
      3870651.77     10040642.44
#Sta/Elev= 30
    4486   92.41  4498.8   91.12  4518.9   91.49  4569.2   89.39  4619.4   88.71
  4760.1   89.19    4825   88.48  4825.5   87.98  4835.4   87.98  4850.6   89.47
  4860.6   89.11  4890.2  91.755  4892.4   92.32    4931   91.45  4961.1   88.53
  4971.2   89.04  4987.7   88.49  4992.7   89.23  5003.4   88.69  5049.9   89.81
  5066.3   89.42  5073.9   90.22  5079.3   89.88  5140.5   92.35  5180.5   94.16
  5217.7   94.72  5228.4   94.15  5271.8   96.25  5368.8   97.77  5408.1   98.84
#Mann= 5 ,-1 , 0
    4486      .1       0  4518.9     .03       0  4890.2      .1       0
  5140.5     .05       0  5368.8     .12       0
Bank Sta=4518.9,4890.2
XS Rating Curve= 0 ,0
Exp/Cntr=0.3,0.1

Type RM Length L Ch R = 1 ,28500   ,500,500,500
BEGIN DESCRIPTION:
WOODSONS GULLY 55.0
END DESCRIPTION:
XS GIS Cut Line= 3
      3871542.28      10040433.6      3870938.55     10040014.39
      3870611.67      10039938.4
#Sta/Elev= 30
    4265   92.41  4270.7   92.41  4277.3   91.38  4292.2    91.9  4319.2   90.96
  4334.1   91.61  4363.8   88.83  4471.2   88.06  4536.7   89.17  4542.8   88.19
  4572.5   88.33    4582   87.46  4591.9   87.46  4593.4   88.69  4644.1   88.04
  4757.5   88.37  4793.9   90.43  4816.9   90.14  4852.7    91.5  4873.7   92.43
  4924.3    92.4  4945.3   91.41  4960.1   89.29    4975    88.4    5052    89.7
  5093.1   91.59  5121.9   91.83  5137.8   93.33  5308.7   96.92  5335.6   96.68
#Mann= 4 ,-1 , 0
    4265      .1       0  4334.1     .03       0  4852.7      .1       0
  5137.8     .12       0
Bank Sta=4334.1,4852.7
XS Rating Curve= 0 ,0
Exp/Cntr=0.3,0.1

Type RM Length L Ch R = 1 ,28000   ,500,500,500
BEGIN DESCRIPTION:
WOODSONS GULLY 54.0
END DESCRIPTION:
XS GIS Cut Line= 3
      3871548.42     10040394.27      3871357.23     10039805.43
      3871302.81     10039458.88
#Sta/Elev= 30
  4380.9   91.86  4468.7   90.59  4500.6   88.15    4542    87.9  4559.3   89.24
  4564.6   88.21    4584   89.16  4605.1   88.05  4623.2   89.62  4636.6   88.41
  4678.7   88.08  4687.1   88.79  4705.2   87.31  4731.2   88.53  4804.8   88.11
  4820.2   88.56 4842.17  90.731  4916.1   93.16  4953.3   91.64    4980   88.76
  5034.8   88.48  5075.3   90.84  5115.8   91.01  5206.9   94.45  5221.8   94.19
  5318.2   97.16  5328.3   96.11  5338.8    96.2  5343.6    96.4  5350.8   96.94
#Mann= 5 ,-1 , 0
  4380.9      .1       0  4468.7     .03       0 4842.17      .1       0
  5338.8     .12       0  5343.6      .1       0
Bank Sta=4468.7,4842.17
XS Rating Curve= 0 ,0
Exp/Cntr=0.3,0.1

Type RM Length L Ch R = 1 ,27500   ,500,500,500
BEGIN DESCRIPTION:
WOODSONS GULLY 53.0
END DESCRIPTION:
XS GIS Cut Line= 3
      3872149.72     10040130.76      3871855.91     10039803.77
      3871571.65     10039520.08
#Sta/Elev= 30
  4560.4   93.35  4575.4   90.77  4632.2   89.37  4667.5   89.38  4674.8    90.2
    4781   89.31  4788.5   90.11  4816.1   88.94  4872.9   91.28  4880.4   90.67
  4901.3   91.49  4915.5   89.15  4929.7   88.16  4943.9   87.86  4950.7   88.73
  4958.1    87.9  5016.8   86.88    5043    88.2  5085.4      88  5127.8   89.75
  5177.3   90.21  5184.4   89.27    5248   91.53  5269.2   92.18  5304.6    95.1
  5325.8   94.18  5361.2   95.73  5371.8   95.22  5382.4   95.09  5401.6   96.92
#Mann= 4 ,-1 , 0
  4560.4      .1       0  4901.3     .03       0    5248      .1       0
  5371.8     .12       0
Bank Sta=4901.3,5248
XS Rating Curve= 0 ,0
Exp/Cntr=0.3,0.1

Type RM Length L Ch R = 1 ,27000   ,564,564,564
BEGIN DESCRIPTION:
WOODSONS GULLY 52.0
END DESCRIPTION:
XS GIS Cut Line= 3
      3872367.26     10039245.09      3872098.24     10039434.12
      3871696.21      10039422.2
#Sta/Elev= 30
  4671.2   92.35  4710.5   90.68  4725.3   89.83    4761   89.51  4775.8    88.7
  4804.9   88.65  4811.5   88.05  4817.7   88.47  4847.3   88.06  4853.8    88.6
  4862.1    87.9  4890.5   88.34  4927.1   87.41  4928.5   86.83  4938.6   86.83
  4939.6   87.57  4954.4   87.83  5010.4   87.47  5030.4   88.09  5060.4   87.66
  5070.4   88.07  5090.4   90.57  5110.4   90.62  5150.5   92.98  5260.5   91.99
  5273.6    92.9  5320.5    93.6  5360.5   95.07  5380.6   95.15  5402.2    96.2
#Mann= 3 , 0 , 0
  4671.2      .1       0  4710.5     .03       0  5090.4      .1       0
Bank Sta=4710.5,5090.4
XS Rating Curve= 0 ,0
Exp/Cntr=0.3,0.1