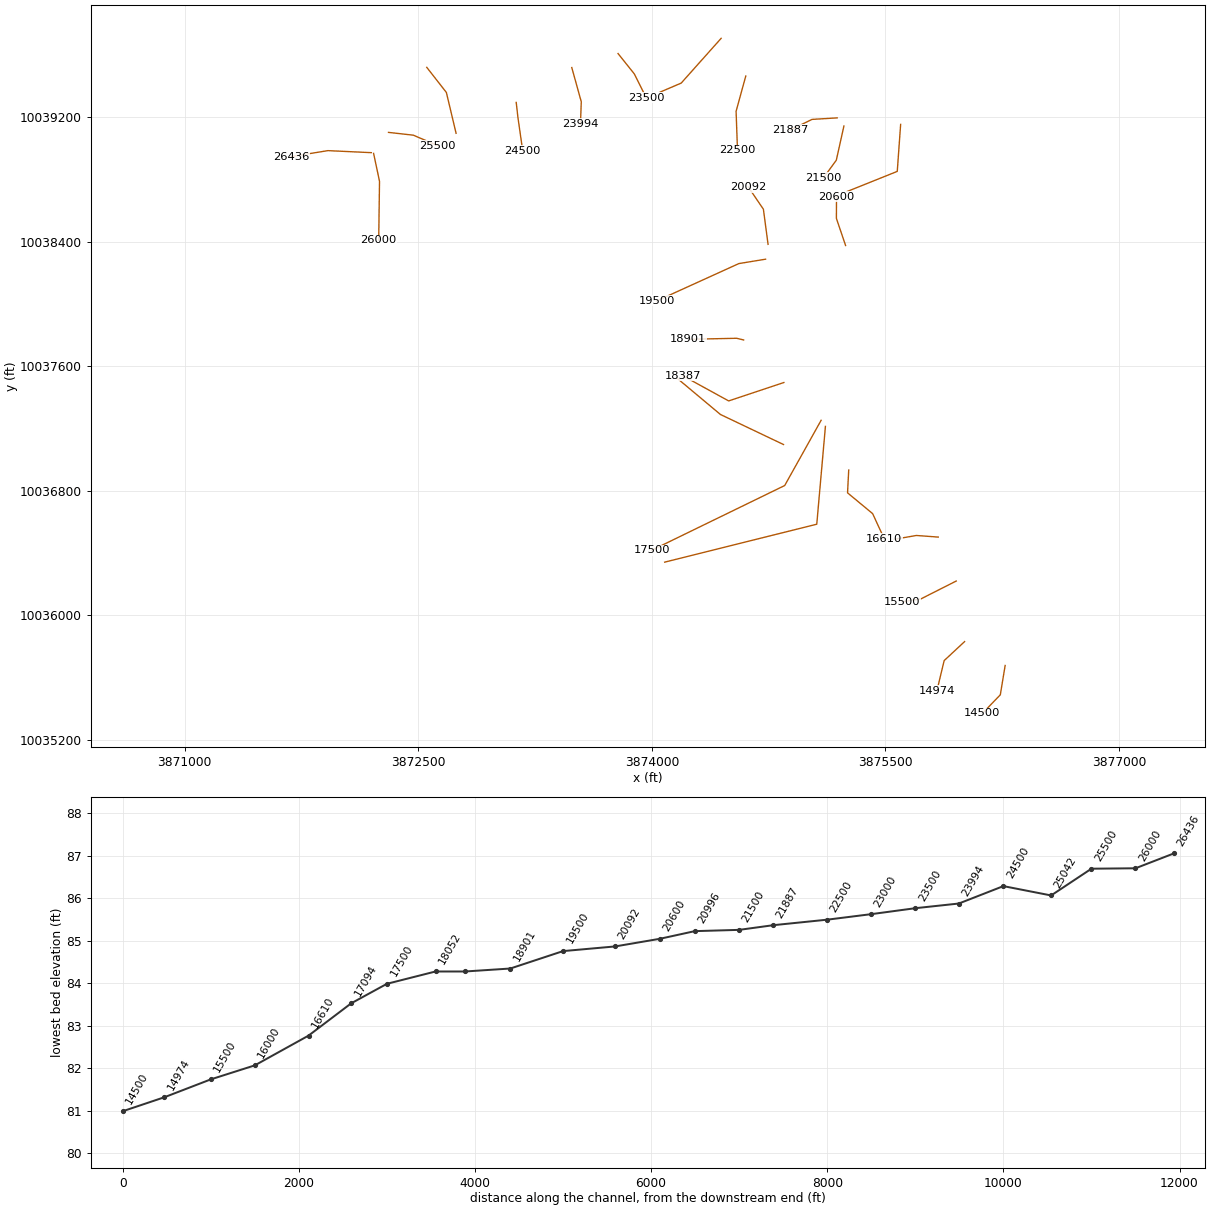
HEC-RAS study WOODSONS GULLY.prj: WOODSONS GULLY Base Level Engineering

--- WOODSONS GULLY.g10 (geometry) --- (continued)

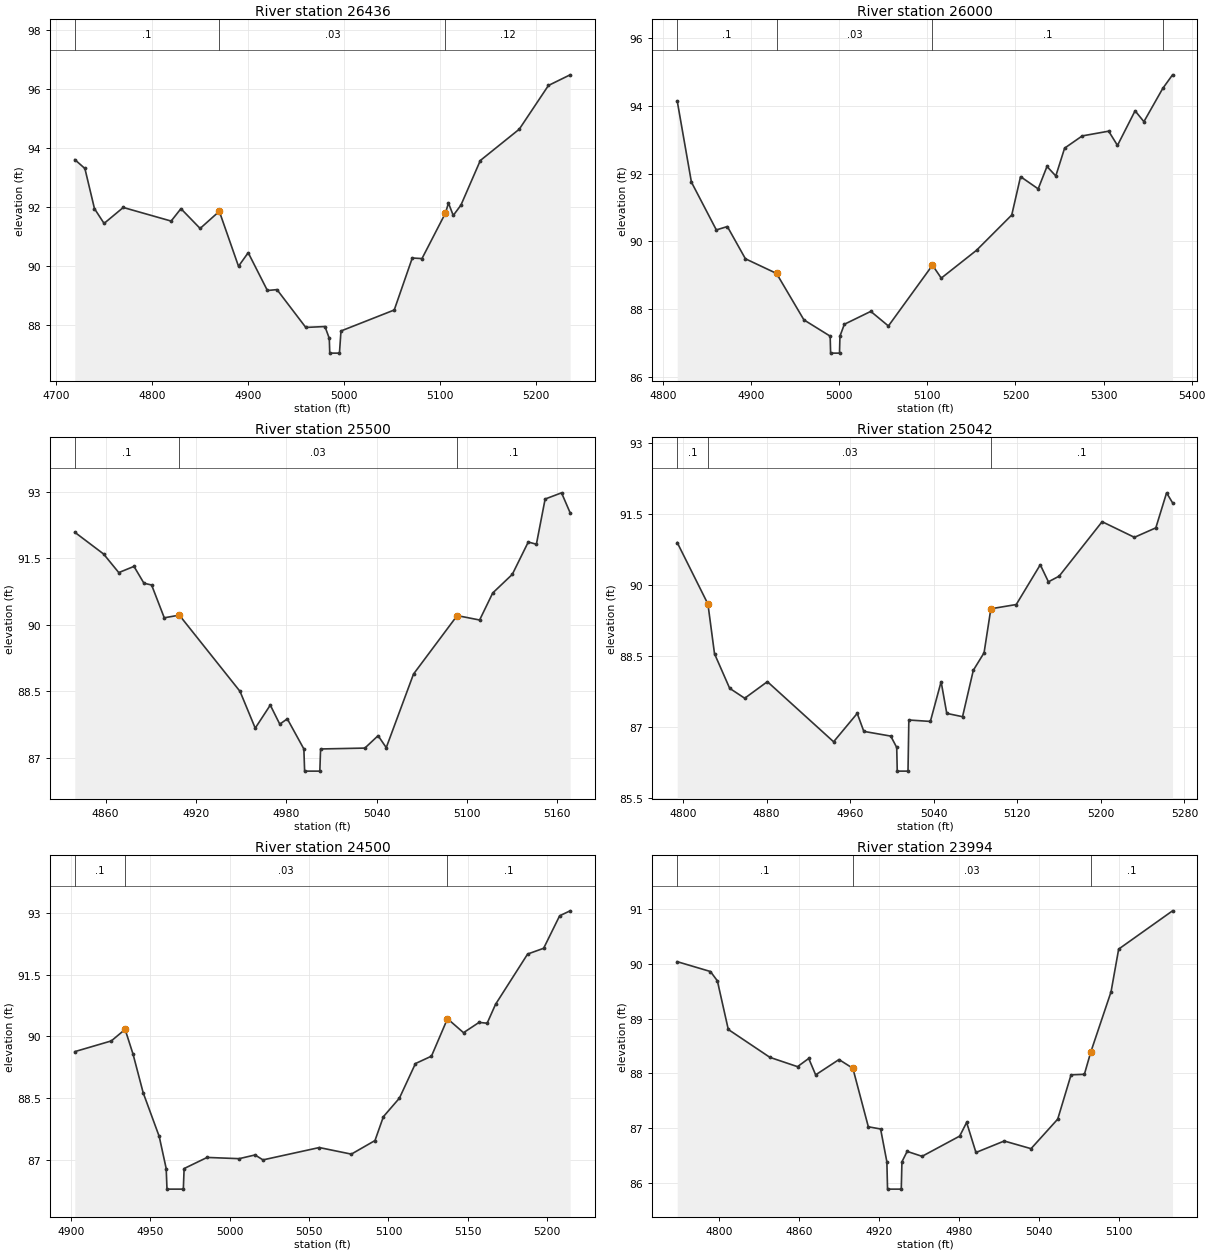
Type RM Length L Ch R = 1 ,26436   ,436,436,436
BEGIN DESCRIPTION:
WOODSONS GULLY 51.0
END DESCRIPTION:
XS GIS Cut Line= 3
      3872198.31     10038971.16      3871919.66     10038984.18
      3871685.51     10038946.02
#Sta/Elev= 30
  4719.6   93.61  4730.1   93.31  4740.1   91.95  4750.1   91.45  4770.1   91.99
    4820   91.53  4830.2   91.95  4850.2   91.28  4870.2   91.86  4890.2      90
  4900.3   90.46  4920.3   89.18  4930.3   89.21  4960.3   87.93  4980.3   87.96
  4984.8   87.56  4985.3   87.06  4995.4   87.06    4997   87.81  5052.5   88.52
  5071.3   90.28  5081.4   90.26 5105.86    91.8    5109   92.14    5114   91.72
    5122   92.07  5142.2   93.58  5182.8   94.64  5213.2   96.12  5235.8   96.48
#Mann= 3 , 0 , 0
  4719.6      .1       0  4870.2     .03       0 5105.86     .12       0
Bank Sta=4870.2,5105.86
XS Rating Curve= 0 ,0
Exp/Cntr=0.3,0.1

Type RM Length L Ch R = 1 ,26000   ,500,500,500
BEGIN DESCRIPTION:
WOODSONS GULLY 50.0
END DESCRIPTION:
XS GIS Cut Line= 3
      3872213.07     10038966.78      3872251.15     10038786.86
      3872245.87      10038408.6
#Sta/Elev= 30
  4816.1   94.14  4832.2   91.75  4860.5   90.34    4873   90.44  4893.5   89.49
 4928.82  89.058  4959.9   87.69  4989.7   87.21  4990.2   86.71  5000.3   86.71
  5000.8   87.21  5005.8   87.56  5035.8   87.94  5055.8   87.51  5105.8    89.3
  5115.8   88.92  5155.8   89.74  5195.8   90.78  5205.8   91.91  5225.8   91.55
  5235.8   92.21  5245.8   91.93  5255.8   92.75  5275.8   93.11  5305.8   93.25
  5315.8   92.83  5335.8   93.85  5345.8   93.53  5367.2   94.51  5378.3   94.91
#Mann= 4 ,-1 , 0
  4816.1      .1       0 4928.82     .03       0  5105.8      .1       0
  5367.2     .05       0
Bank Sta=4928.82,5105.8
XS Rating Curve= 0 ,0
Exp/Cntr=0.3,0.1

Type RM Length L Ch R = 1 ,25500   ,458,458,458
BEGIN DESCRIPTION:
WOODSONS GULLY 49.0
END DESCRIPTION:
XS GIS Cut Line= 3
      3872308.83     10039101.37      3872468.24      10039083.5
      3872623.11     10039017.13
#Sta/Elev= 30
  4839.6   92.09  4858.7    91.6  4868.8   91.18  4878.9   91.32  4885.5   90.94
  4890.6    90.9    4899   90.16    4909   90.22  4949.3    88.5  4959.4   87.67
  4969.4   88.19  4975.7   87.76  4980.7   87.88  4991.7    87.2  4992.2    86.7
  5002.3    86.7  5002.8    87.2  5032.2   87.22    5041    87.5  5046.4   87.23
  5064.5   88.89  5093.5   90.21  5108.4   90.11  5117.1   90.72  5130.1   91.14
  5140.7   91.87  5146.1   91.82  5151.9   92.84  5162.8   92.98  5168.5   92.53
#Mann= 3 , 0 , 0
  4839.6      .1       0    4909     .03       0  5093.5      .1       0
Bank Sta=4909,5093.5
XS Rating Curve= 0 ,0
Exp/Cntr=0.3,0.1

Type RM Length L Ch R = 1 ,25042   ,542,542,542
BEGIN DESCRIPTION:
WOODSONS GULLY 48.0
END DESCRIPTION:
XS GIS Cut Line= 3
       3872554.7      10039519.1       3872680.4     10039357.98
      3872742.72     10039095.53
#Sta/Elev= 30
  4794.5    90.9  4823.9    89.6  4830.2   88.55  4844.7   87.82  4859.1   87.61
  4880.8   87.96  4944.2   86.69  4966.8   87.29  4973.1   86.91  4998.9   86.81
  5004.6   86.57  5005.1   86.07  5015.4   86.07  5016.2   87.15  5036.8   87.12
  5047.1   87.96  5052.5   87.29  5067.6   87.22  5077.9    88.2  5088.2   88.57
  5094.7    89.5    5119   89.59    5142   90.43  5149.8   90.07  5160.1   90.19
  5201.2   91.34  5232.1   91.01  5252.6   91.21  5262.9   91.95  5268.6   91.74
#Mann= 3 , 0 , 0
  4794.5      .1       0  4823.9     .03       0  5094.7      .1       0
Bank Sta=4823.9,5094.7
XS Rating Curve= 0 ,0
Exp/Cntr=0.3,0.1

Type RM Length L Ch R = 1 ,24500   ,506,506,506
BEGIN DESCRIPTION:
WOODSONS GULLY 47.0
END DESCRIPTION:
XS GIS Cut Line= 3
      3873128.87     10039293.94       3873139.9     10039196.86
      3873170.31     10038984.53
#Sta/Elev= 30
  4902.3   89.63  4925.3   89.89    4934   90.17    4939   89.57  4945.4   88.63
  4955.5   87.57  4959.9   86.79  4960.4   86.29  4970.7   86.29  4971.2   86.79
  4985.7   87.06  5005.9   87.03  5015.9   87.12  5020.9      87  5056.4    87.3
  5076.6   87.14  5091.5   87.47  5096.8   88.05  5106.9    88.5    5117   89.34
  5127.1   89.52  5137.2   90.43  5147.3   90.09  5157.1   90.34  5162.2   90.32
  5167.5   90.78  5187.7      92  5197.8   92.14  5207.9   92.93  5214.5   93.05
#Mann= 3 , 0 , 0
  4902.3      .1       0    4934     .03       0  5137.2      .1       0
Bank Sta=4934,5137.2
XS Rating Curve= 0 ,0
Exp/Cntr=0.3,0.1

Type RM Length L Ch R = 1 ,23994   ,494,494,494
BEGIN DESCRIPTION:
WOODSONS GULLY 46.0
END DESCRIPTION:
XS GIS Cut Line= 3
      3873485.64     10039518.01      3873546.59     10039298.19
      3873541.42       10039155.
#Sta/Elev= 30
  4768.8   90.04  4793.7   89.86  4798.9   89.69  4807.1    88.8  4838.3   88.29
    4859   88.12  4867.4   88.27  4872.6   87.97  4890.1   88.25  4900.5   88.09
  4912.1   87.02  4921.3   86.98    4926   86.38  4926.5   85.88  4936.8   85.88
  4937.3   86.38  4941.2   86.57  4952.4   86.48  4980.6   86.85  4985.8    87.1
  4992.8   86.55    5014   86.76  5034.1   86.62  5054.1   87.16  5064.1   87.97
  5074.1   87.98 5078.84  88.383  5094.1   89.49  5099.8   90.27  5140.2   90.97
#Mann= 3 , 0 , 0
  4768.8      .1       0  4900.5     .03       0 5078.84      .1       0
Bank Sta=4900.5,5078.84
XS Rating Curve= 0 ,0
Exp/Cntr=0.3,0.1

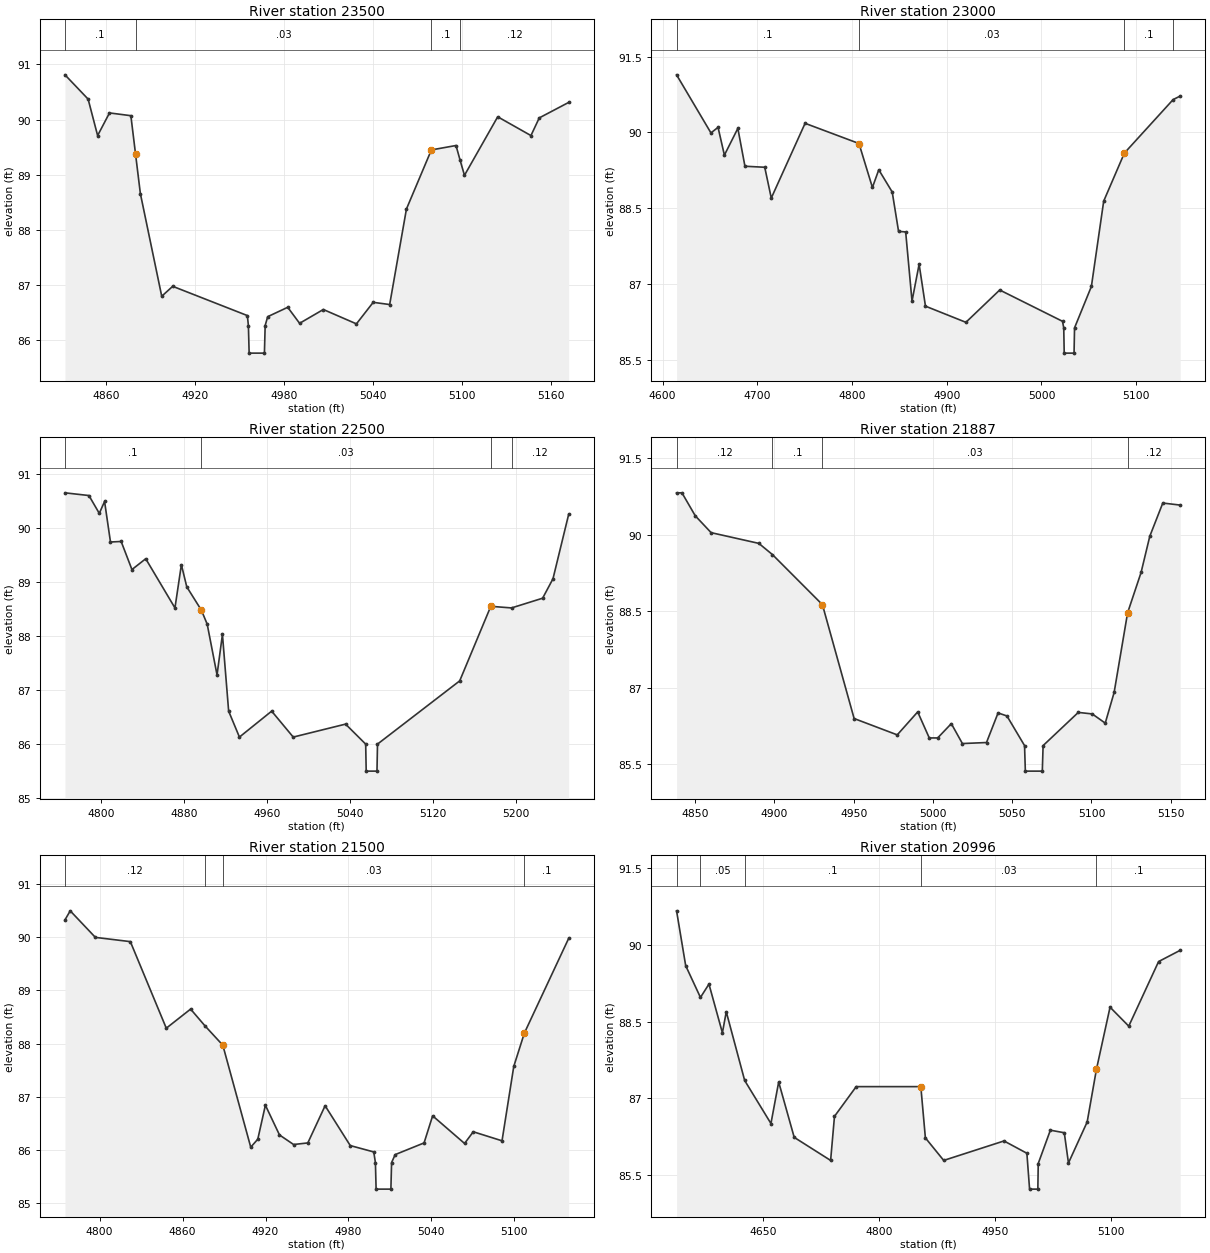
Type RM Length L Ch R = 1 ,23500   ,500,500,500
BEGIN DESCRIPTION:
WOODSONS GULLY 45.0
END DESCRIPTION:
XS GIS Cut Line= 3
      3873782.77     10039607.83      3873887.35     10039476.86
      3873964.15     10039323.18
#Sta/Elev= 30
  4832.4   90.81    4848   90.37  4854.4   89.71  4862.4   90.12  4876.8   90.07
 4879.93   89.38  4883.2   88.66  4897.6    86.8    4905   86.98  4955.3   86.45
    4956   86.27  4956.5   85.77  4966.8   85.77  4967.3   86.27    4969   86.43
  4982.5    86.6  4990.5   86.31  5006.5   86.56  5028.8    86.3  5040.1   86.69
  5051.2   86.65  5062.5   88.38  5079.3   89.45  5095.9   89.53  5098.7   89.26
  5101.6   88.99    5124   90.05  5146.4   89.71    5152   90.03  5171.8   90.31
#Mann= 4 ,-1 , 0
  4832.4      .1       0 4879.93     .03       0  5079.3      .1       0
  5098.7     .12       0
Bank Sta=4879.93,5079.3
XS Rating Curve= 0 ,0
Exp/Cntr=0.3,0.1

Type RM Length L Ch R = 1 ,23000   ,500,500,500
BEGIN DESCRIPTION:
WOODSONS GULLY 44.0
END DESCRIPTION:
XS GIS Cut Line= 3
      3874444.67     10039705.74      3874188.24     10039418.16
      3874053.57     10039360.47
#Sta/Elev= 30
  4614.7   91.14    4651   89.99  4658.5    90.1  4665.2   89.55  4679.4   90.08
  4686.9   89.33  4707.8   89.31  4714.7    88.7  4750.4   90.18  4807.3   89.78
  4821.5   88.91  4828.2   89.26  4842.4   88.82  4849.1   88.04  4856.6   88.03
  4863.3   86.66  4870.8   87.39  4877.5   86.56  4920.2   86.24  4955.9   86.88
  5022.2   86.26  5023.5   86.13    5024   85.63  5034.4   85.63  5034.9   86.13
  5052.7   86.95  5065.7   88.64  5087.5   89.59    5139   90.65  5146.5   90.72
#Mann= 4 ,-1 , 0
  4614.7      .1       0  4807.3     .03       0  5087.5      .1       0
    5139     .12       0
Bank Sta=4807.3,5087.5
XS Rating Curve= 0 ,0
Exp/Cntr=0.3,0.1

Type RM Length L Ch R = 1 ,22500   ,613,613,613
BEGIN DESCRIPTION:
WOODSONS GULLY 43.0
END DESCRIPTION:
XS GIS Cut Line= 3
      3874602.86     10039463.38      3874540.66     10039236.86
      3874549.68     10038986.03
#Sta/Elev= 30
  4765.1   90.65  4788.2    90.6  4798.2   90.27  4803.3   90.49    4809   89.74
  4819.3   89.75  4829.7   89.23    4843   89.43  4871.2   88.52  4877.4   89.32
  4882.6   88.91  4896.7  88.478  4902.3   88.22  4911.8   87.28    4917   88.03
    4923   86.61  4933.4   86.13  4964.5   86.61  4985.3   86.13  5035.8   86.37
  5055.2      86  5055.7    85.5  5066.1    85.5  5066.6      86  5145.9   87.17
  5175.9   88.55  5195.9   88.52  5225.9    88.7  5235.9   89.06    5251   90.25
#Mann= 4 ,-1 , 0
  4765.1      .1       0  4896.7     .03       0  5175.9      .1       0
  5195.9     .12       0
Bank Sta=4896.7,5175.9
XS Rating Curve= 0 ,0
Exp/Cntr=0.3,0.1

Type RM Length L Ch R = 1 ,21887   ,387,387,387
BEGIN DESCRIPTION:
WOODSONS GULLY 42.0
END DESCRIPTION:
XS GIS Cut Line= 3
      3875189.64     10039194.61      3875028.24     10039184.85
      3874888.01      10039116.5
#Sta/Elev= 30
  4838.3   90.82  4841.7   90.82  4850.1   90.37  4860.1   90.04  4890.2   89.83
  4898.8   89.61  4930.3   88.63  4950.3    86.4  4977.5   86.08  4990.4   86.53
  4997.7   86.02    5003   86.02  5011.6    86.3  5018.6   85.91  5033.8   85.93
  5041.1   86.51  5046.7   86.45  5057.8   85.87  5058.3   85.37    5069   85.37
  5069.5   85.87  5091.7   86.52  5100.5   86.49  5108.7   86.31  5114.3   86.91
  5122.8   88.47  5131.3   89.26  5136.8   89.97    5145   90.62    5156   90.58
#Mann= 4 ,-1 , 0
  4838.3     .12       0  4898.8      .1       0  4930.3     .03       0
  5122.8     .12       0
Bank Sta=4930.3,5122.8
XS Rating Curve= 0 ,0
Exp/Cntr=0.3,0.1

Type RM Length L Ch R = 1 ,21500   ,504,504,504
BEGIN DESCRIPTION:
WOODSONS GULLY 41.0
END DESCRIPTION:
XS GIS Cut Line= 3
      3875233.06     10039142.58      3875184.21     10038922.84
       3875102.3     10038810.17
#Sta/Elev= 30
  4774.9   90.33  4778.7    90.5  4796.9      90  4822.2   89.92  4848.2   88.29
  4865.8   88.65    4876   88.34  4889.1   87.97  4909.3   86.05  4914.4    86.2
  4919.9   86.84  4930.1   86.28  4940.3    86.1  4950.6   86.13  4963.1   86.83
  4981.3   86.08  4998.3   85.96  4999.5   85.76    5000   85.26  5010.7   85.26
  5011.2   85.76  5013.8   85.91  5034.7   86.13  5040.9   86.64    5064   86.12
  5070.3   86.34  5091.1   86.17  5099.6   87.57 5107.25  88.197  5139.3   89.98
#Mann= 4 ,-1 , 0
  4774.9     .12       0    4876      .1       0  4889.1     .03       0
 5107.25      .1       0
Bank Sta=4889.1,5107.25
XS Rating Curve= 0 ,0
Exp/Cntr=0.3,0.1

Type RM Length L Ch R = 1 ,20996   ,396,396,396
BEGIN DESCRIPTION:
WOODSONS GULLY 40.0
END DESCRIPTION:
XS GIS Cut Line= 3
      3875597.27     10039152.84      3875575.57     10038850.76
      3875251.89     10038720.94
#Sta/Elev= 30
  4538.4   90.66  4550.2   89.59  4569.3   88.97  4580.3   89.23  4597.7   88.28
  4602.7   88.69  4626.5   87.35  4660.5   86.51  4670.5   87.32  4690.6   86.24
  4737.7   85.79  4742.7   86.65  4770.8   87.23  4854.4   87.23  4860.3   86.23
    4884   85.79    4962   86.17  4991.6   85.93  4995.1   85.23  5005.8   85.23
  5006.3   85.73    5022   86.38    5040   86.33  5045.4   85.74  5069.6   86.54
 5081.62  87.569  5099.2   88.78  5123.4   88.41    5162   89.67    5190   89.89
#Mann= 5 ,-1 , 0
  4538.4      .1       0  4569.3     .05       0  4626.5      .1       0
  4854.4     .03       0 5081.62      .1       0
Bank Sta=4854.4,5081.62
XS Rating Curve= 0 ,0
Exp/Cntr=0.3,0.1

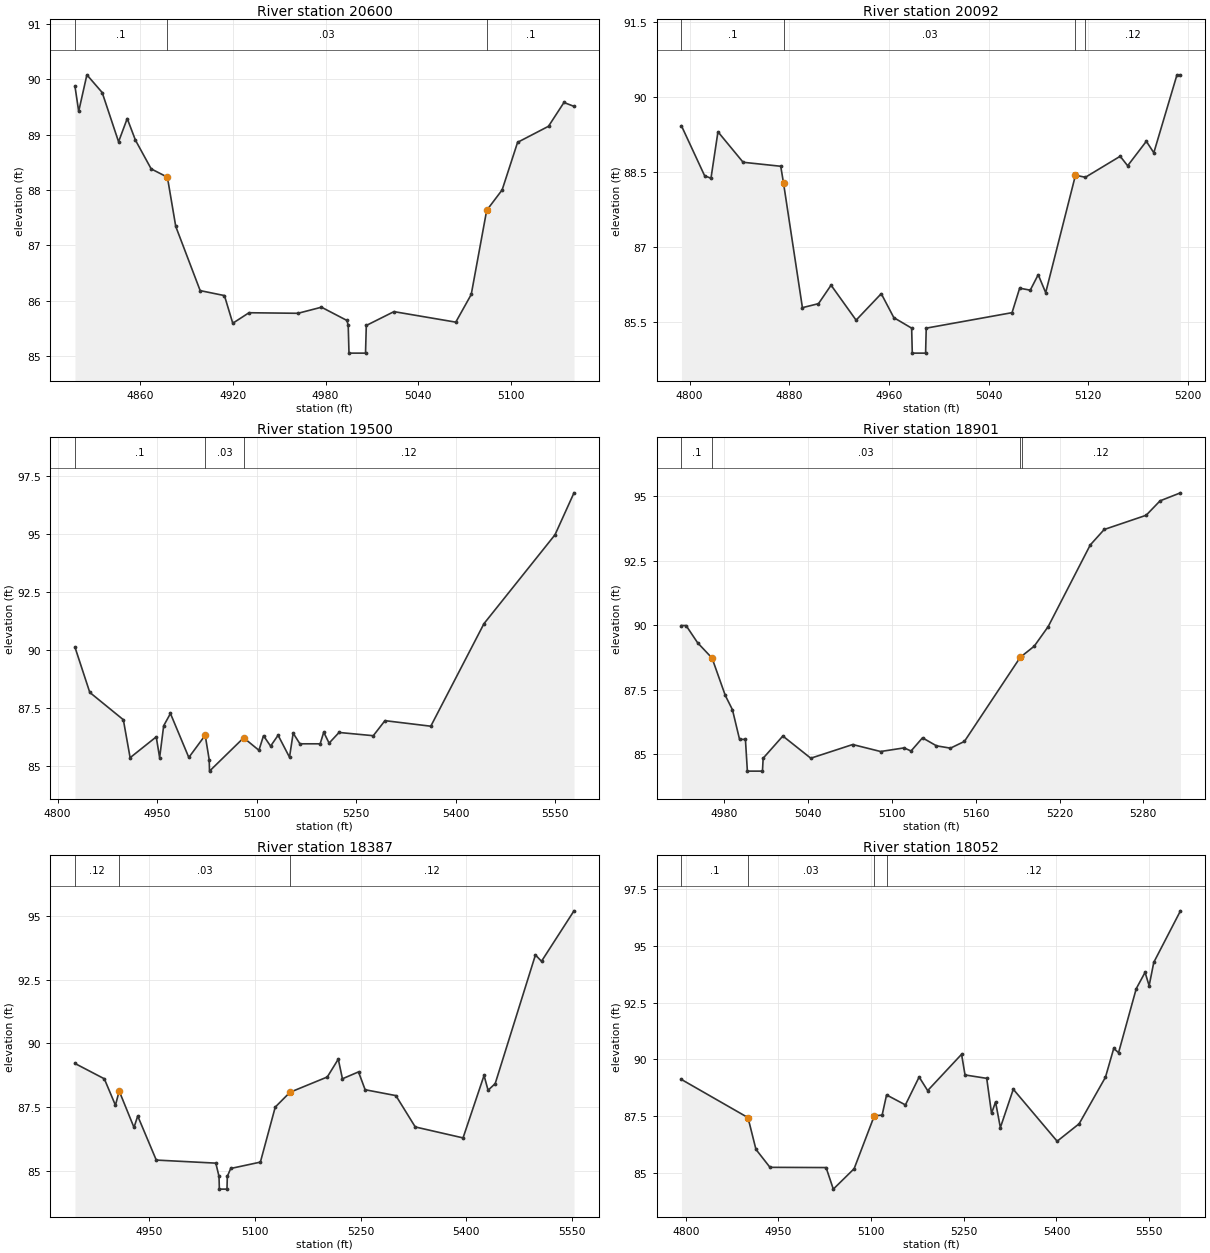
Type RM Length L Ch R = 1 ,20600   ,508,508,508
BEGIN DESCRIPTION:
WOODSONS GULLY 39.0
END DESCRIPTION:
XS GIS Cut Line= 3
      3875243.82     10038374.38      3875184.77     10038548.74
      3875185.46     10038687.56
#Sta/Elev= 30
  4817.9   89.87  4820.3   89.42  4825.6   90.08  4835.5   89.76  4846.1   88.87
  4851.7   89.29    4857    88.9  4867.2   88.38  4877.7   88.23  4883.1   87.34
  4898.9   86.18  4914.6   86.09    4920   85.59  4930.5   85.78  4962.2   85.77
  4977.4   85.88  4993.9   85.64  4994.7   85.55  4995.2   85.05  5005.9   85.05
  5006.4   85.55  5024.3    85.8  5064.3   85.61  5074.3   86.11  5084.3   87.63
  5094.3      88  5104.3   88.86  5124.3   89.15  5134.3   89.58  5140.8   89.51
#Mann= 3 , 0 , 0
  4817.9      .1       0  4877.7     .03       0  5084.3      .1       0
Bank Sta=4877.7,5084.3
XS Rating Curve= 0 ,0
Exp/Cntr=0.3,0.1

Type RM Length L Ch R = 1 ,20092   ,592,592,592
BEGIN DESCRIPTION:
WOODSONS GULLY 38.0
END DESCRIPTION:
XS GIS Cut Line= 3
      3874745.89     10038382.05      3874716.02     10038607.77
      3874618.83     10038750.78
#Sta/Elev= 30
  4793.4   89.42    4812   88.42  4817.1   88.37  4822.7    89.3  4842.9   88.69
  4873.1   88.61 4875.32  88.276  4890.5   85.78  4903.4   85.86  4913.5   86.23
  4933.6   85.53  4953.8   86.06  4963.9   85.58  4978.2   85.37  4978.7   84.87
  4989.4   84.87  4989.9   85.37  5058.8   85.68  5064.9   86.17  5073.4   86.13
  5079.8   86.44  5085.8   86.08  5109.7   88.43  5117.7   88.39  5145.6   88.81
  5151.6   88.62  5166.6   89.11  5172.6   88.88  5191.2   90.44    5194   90.44
#Mann= 4 ,-1 , 0
  4793.4      .1       0 4875.32     .03       0  5109.7      .1       0
  5117.7     .12       0
Bank Sta=4875.32,5109.7
XS Rating Curve= 0 ,0
Exp/Cntr=0.3,0.1

Type RM Length L Ch R = 1 ,19500   ,599,599,599
BEGIN DESCRIPTION:
WOODSONS GULLY 37.0
END DESCRIPTION:
XS GIS Cut Line= 3
      3874729.82     10038286.67      3874558.24     10038258.36
      3874031.81     10038018.72
#Sta/Elev= 30
  4826.1   90.11  4848.4   88.16    4899   86.98  4909.2   85.34  4948.6   86.24
  4953.7   85.34  4959.8   86.72    4970   87.25  4997.7   85.35  5022.4   86.31
  5028.4   85.26  5028.9   84.76  5080.4    86.2  5103.4   85.66  5110.3   86.29
    5121   85.84  5132.3   86.31  5149.5   85.36    5155    86.4  5165.2   85.94
  5195.7   85.94  5201.1   86.44  5209.2   85.97  5224.2   86.43  5275.8   86.29
  5293.4   86.94  5362.5    86.7  5442.7   91.13  5549.8   94.97  5578.4   96.78
#Mann= 3 , 0 , 0
  4826.1      .1       0  5022.4     .03       0  5080.4     .12       0
Bank Sta=5022.4,5080.4
XS Rating Curve= 0 ,0
Exp/Cntr=0.3,0.1

Type RM Length L Ch R = 1 ,18901   ,514,514,514
BEGIN DESCRIPTION:
WOODSONS GULLY 36.0
END DESCRIPTION:
XS GIS Cut Line= 3
      3874589.15     10037767.62      3874544.62     10037778.48
      3874233.22     10037771.97
#Sta/Elev= 30
  4949.3   89.99  4952.6   89.99  4960.9   89.32  4971.2   88.73  4980.7   87.28
  4985.8   86.73  4990.9   85.58  4995.1   85.58  4996.5   84.35  5007.3   84.35
  5007.8   84.85  5021.9   85.71  5041.9   84.85  5071.9   85.38  5091.9   85.11
  5108.7   85.25  5113.7   85.13  5121.9   85.64  5131.9   85.33  5141.9   85.24
  5151.9    85.5  5191.9   88.76  5193.3   88.82  5201.9   89.19  5211.9   89.95
    5242   93.11    5252   93.71    5282   94.26    5292   94.82  5306.6   95.13
#Mann= 4 ,-1 , 0
  4949.3      .1       0  4971.2     .03       0  5191.9      .1       0
  5193.3     .12       0
Bank Sta=4971.2,5191.9
XS Rating Curve= 0 ,0
Exp/Cntr=0.3,0.1

Type RM Length L Ch R = 1 ,18387   ,335,335,335
BEGIN DESCRIPTION:
WOODSONS GULLY 35.0
END DESCRIPTION:
XS GIS Cut Line= 3
      3874847.36      10037494.2      3874492.97     10037376.01
      3874199.87     10037536.84
#Sta/Elev= 30
  4844.7   89.21  4886.3   88.61  4902.1   87.57  4907.4   88.13  4928.4    86.7
  4933.7   87.15    4960   85.42  5044.5    85.3    5049   84.78  5049.5   84.28
  5060.3   84.28  5060.8   84.78  5065.6   85.09  5107.7   85.34  5128.8    87.5
  5149.7   88.08  5202.6   88.68  5218.2   89.38  5224.1   88.61  5246.9   88.88
  5256.3   88.18  5299.9   87.95  5327.4   86.72  5395.2   86.29    5425   88.74
  5430.7   88.16  5440.8   88.42  5497.9   93.47  5506.5   93.22  5552.6    95.2
#Mann= 3 , 0 , 0
  4844.7     .12       0  4907.4     .03       0  5149.7     .12       0
Bank Sta=4907.4,5149.7
XS Rating Curve= 0 ,0
Exp/Cntr=0.3,0.1

Type RM Length L Ch R = 1 ,18052   ,552,552,552
BEGIN DESCRIPTION:
WOODSONS GULLY 34.0
END DESCRIPTION:
XS GIS Cut Line= 3
      3874845.08     10037095.78      3874440.18     10037288.86
      3874164.76     10037519.31
#Sta/Elev= 30
    4793   89.11  4900.7   87.43  4913.6   86.03  4936.3   85.24  5027.1   85.23
  5038.8   84.28  5072.5   85.18 5105.13  87.509  5117.8   87.54    5125   88.43
  5155.5   87.99  5177.7   89.22  5191.5   88.62  5246.4   90.22    5252   89.31
  5287.1   89.16  5294.9   87.62  5301.4   88.12  5309.2   86.99  5330.1   88.68
  5401.1   86.39  5436.7   87.16  5479.3   89.21  5492.7   90.48  5500.5   90.29
  5529.1   93.11  5543.4   93.83    5550   93.24  5557.5   94.27  5600.7   96.54
#Mann= 4 ,-1 , 0
    4793      .1       0  4900.7     .03       0 5105.13      .1       0
    5125     .12       0
Bank Sta=4900.7,5105.13
XS Rating Curve= 0 ,0
Exp/Cntr=0.3,0.1

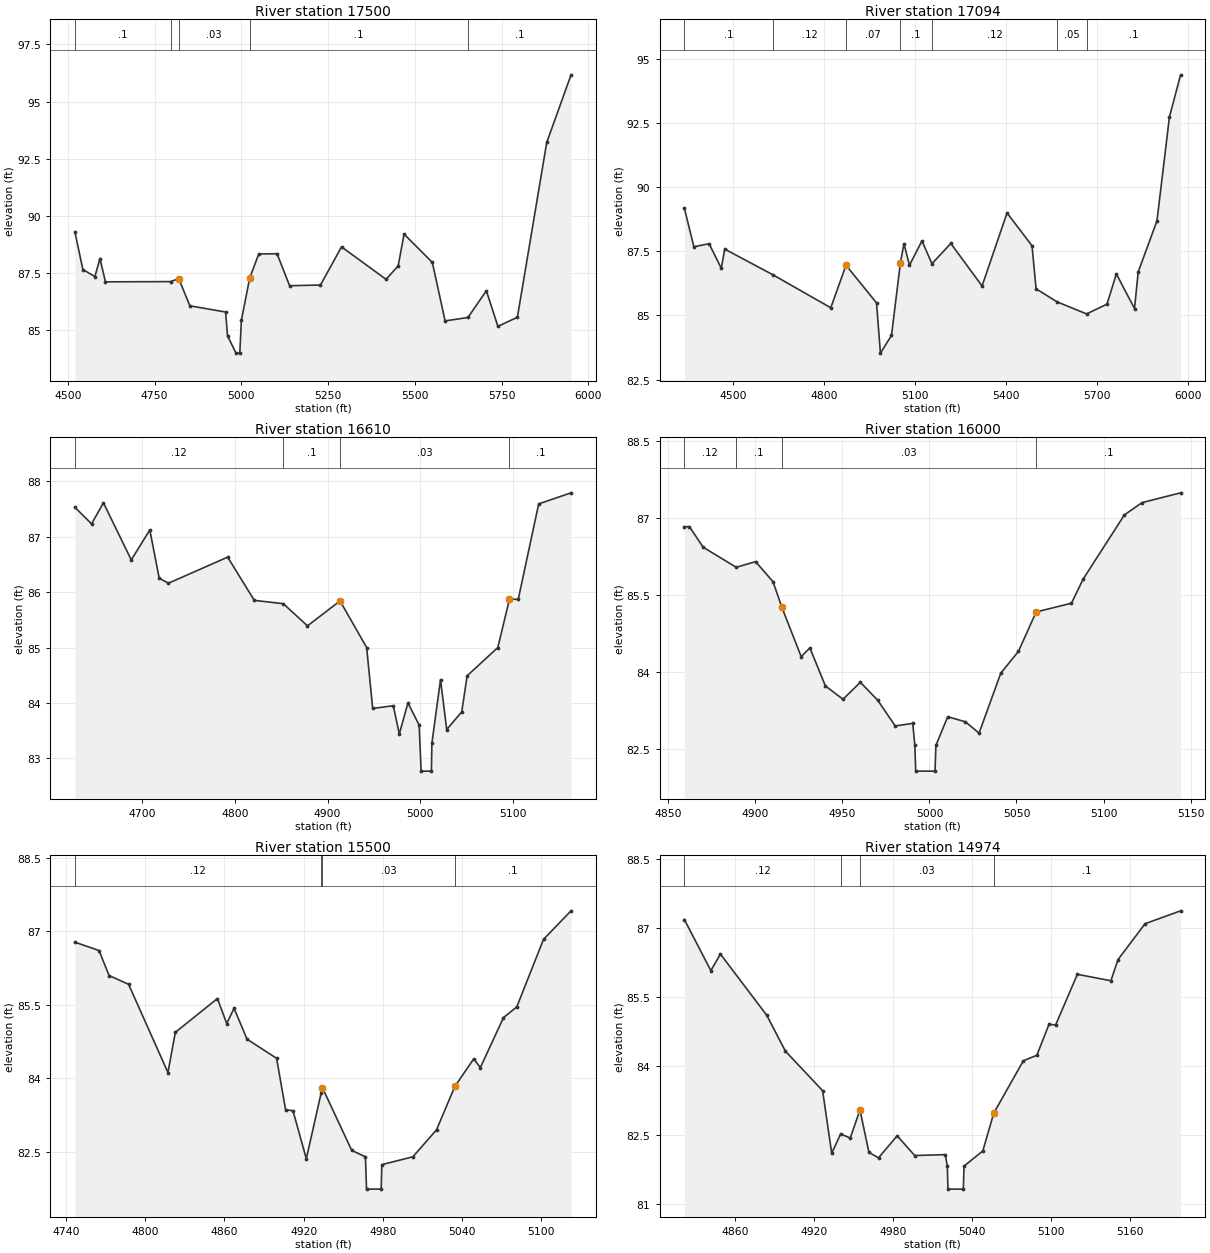
Type RM Length L Ch R = 1 ,17500   ,406,406,406
BEGIN DESCRIPTION:
WOODSONS GULLY 33.0
END DESCRIPTION:
XS GIS Cut Line= 3
      3875086.72     10037251.57      3874852.78     10036832.32
       3873998.4     10036416.04
#Sta/Elev= 30
  4519.9    89.3    4543   87.65  4577.7   87.34  4592.2   88.13  4608.1   87.11
  4795.7   87.12  4819.5   87.25  4851.5   86.06  4954.4   85.79  4960.1   84.75
  4984.4   83.99  4995.5   83.99  4999.9   85.42 5023.73  87.259    5050   88.33
  5102.8   88.34    5139   86.94    5228   86.97  5288.7   88.64  5417.1   87.22
    5452   87.81    5469    89.2  5550.5   87.96  5587.3    85.4  5653.1   85.55
  5706.3   86.72  5739.5   85.16  5795.7   85.56  5880.3   93.21  5950.4   96.17
#Mann= 5 ,-1 , 0
  4519.9      .1       0  4795.7     .12       0  4819.5     .03       0
 5023.73      .1       0  5653.1      .1       0
Bank Sta=4819.5,5023.73
XS Rating Curve= 0 ,0
Exp/Cntr=0.3,0.1

Type RM Length L Ch R = 1 ,17094   ,484,484,484
BEGIN DESCRIPTION:
WOODSONS GULLY 32.0
END DESCRIPTION:
XS GIS Cut Line= 3
      3875114.26      10037212.3       3875058.7     10036583.78
      3874082.13     10036340.02
#Sta/Elev= 30
  4338.2   89.18  4369.5   87.68  4419.7    87.8  4459.9   86.84  4471.3   87.59
  4629.8   86.59  4821.3    85.3  4871.5   86.96  4972.2   85.49  4985.1   83.53
  5021.6   84.22    5051  87.046  5062.8    87.8  5080.9   86.96  5122.2   87.91
    5155   87.02  5217.4   87.81  5320.5   86.15  5402.9      89  5485.4   87.72
  5498.7   86.04  5568.2   85.53  5665.4   85.06  5732.7   85.44  5763.7   86.62
  5823.6   85.27  5835.8    86.7  5897.7   88.69  5938.9   92.75  5975.7   94.39
#Mann= 7 ,-1 , 0
  4338.2      .1       0  4629.8     .12       0  4871.5     .07       0
    5051      .1       0    5155     .12       0  5568.2     .05       0
  5665.4      .1       0
Bank Sta=4871.5,5051
XS Rating Curve= 0 ,0
Exp/Cntr=0.3,0.1

Type RM Length L Ch R = 1 ,16610   ,610,610,610
BEGIN DESCRIPTION:
WOODSONS GULLY 31.0
END DESCRIPTION:
XS GIS Cut Line= 4
       3875263.9     10036931.81       3875256.3     10036785.28
      3875417.32     10036651.94      3875492.34     10036489.41
#Sta/Elev= 30
  4627.6   87.53  4645.6   87.23  4658.4   87.61  4688.4   86.58  4708.4   87.12
  4718.5   86.25  4728.5   86.16  4792.3   86.63    4821   85.85  4852.3   85.79
  4878.3   85.39  4913.4   85.84  4942.1      85  4948.6    83.9  4970.8   83.95
  4977.3   83.44  4986.6      84  4998.7    83.6  5000.8   82.77  5011.9   82.77
  5012.4   83.27  5021.7   84.42  5028.4   83.52  5044.6   83.84  5050.4   84.49
  5083.5      85    5096   85.87  5105.5   85.87  5127.5   87.59  5162.4   87.79
#Mann= 4 ,-1 , 0
  4627.6     .12       0  4852.3      .1       0  4913.4     .03       0
    5096      .1       0
Bank Sta=4913.4,5096
XS Rating Curve= 0 ,0
Exp/Cntr=0.3,0.1

Type RM Length L Ch R = 1 ,16000   ,500,500,500
BEGIN DESCRIPTION:
WOODSONS GULLY 30.0
END DESCRIPTION:
XS GIS Cut Line= 3
      3875838.66     10036501.08      3875698.24     10036511.39
      3875556.04     10036486.84
#Sta/Elev= 30
  4859.2   86.83  4862.1   86.83    4870   86.43    4889   86.04  4900.1   86.15
  4910.1   85.76 4915.23  85.257  4926.3    84.3  4931.3   84.47  4940.2   83.73
  4950.3   83.47  4960.3    83.8  4970.3   83.45  4980.3   82.95  4990.4      83
  4991.6   82.57  4992.1   82.07  5003.2   82.07  5003.7   82.57  5010.5   83.13
  5020.7   83.03  5028.5   82.81    5041   83.98  5051.1    84.4  5061.3   85.17
  5081.6   85.34  5088.3   85.81    5112   87.06  5122.2    87.3  5144.3   87.49
#Mann= 4 ,-1 , 0
  4859.2     .12       0    4889      .1       0 4915.23     .03       0
  5061.3      .1       0
Bank Sta=4915.23,5061.3
XS Rating Curve= 0 ,0
Exp/Cntr=0.3,0.1

Type RM Length L Ch R = 1 ,15500   ,526,526,526
BEGIN DESCRIPTION:
WOODSONS GULLY 29.0
END DESCRIPTION:
XS GIS Cut Line= 3
       3875954.2      10036218.7      3875728.24     10036104.24
      3875607.28     10036084.84
#Sta/Elev= 30
  4746.7   86.78    4765   86.61  4772.6    86.1  4787.4   85.92  4817.2   84.12
  4822.8   84.94  4854.7   85.63  4861.7   85.12  4867.3   85.43  4877.1    84.8
  4899.5   84.41  4906.3   83.36  4911.9   83.34    4922   82.36  4933.3   83.71
  4934.2   83.81  4956.4   82.53  4966.8    82.4  4967.6   81.74  4978.7   81.74
  4979.2   82.24  5002.7    82.4  5020.6   82.95 5034.51  83.836  5048.8    84.4
  5053.8   84.22  5071.3   85.24  5081.4   85.46  5101.7   86.84  5122.5   87.42
#Mann= 4 ,-1 , 0
  4746.7     .12       0  4933.3      .1       0  4934.2     .03       0
 5034.51      .1       0
Bank Sta=4934.2,5034.51
XS Rating Curve= 0 ,0
Exp/Cntr=0.3,0.1

Type RM Length L Ch R = 1 ,14974   ,474,474,474
BEGIN DESCRIPTION:
WOODSONS GULLY 28.0
END DESCRIPTION:
XS GIS Cut Line= 3
      3876007.87     10035829.51      3875876.65     10035707.31
      3875830.42     10035514.79
#Sta/Elev= 30
  4821.5   87.18  4841.6   86.07  4848.9   86.43  4884.1    85.1  4898.3   84.32
  4926.6   83.46  4933.5    82.1  4940.3   82.52  4947.6   82.43    4955   83.04
  4961.8   82.12  4969.1      82  4983.3   82.48  4996.6   82.05  5019.9   82.07
  5021.4   81.82  5021.9   81.32  5033.6   81.32  5034.1   81.82  5048.4   82.15
  5056.7   82.97  5079.2   84.11  5089.5   84.23  5098.7    84.9  5103.8   84.89
  5120.3   85.99  5145.8   85.85  5151.2   86.31  5171.8   87.09  5198.8   87.37
#Mann= 4 ,-1 , 0
  4821.5     .12       0  4940.3      .1       0    4955     .03       0
  5056.7      .1       0
Bank Sta=4955,5056.7
XS Rating Curve= 0 ,0
Exp/Cntr=0.3,0.1

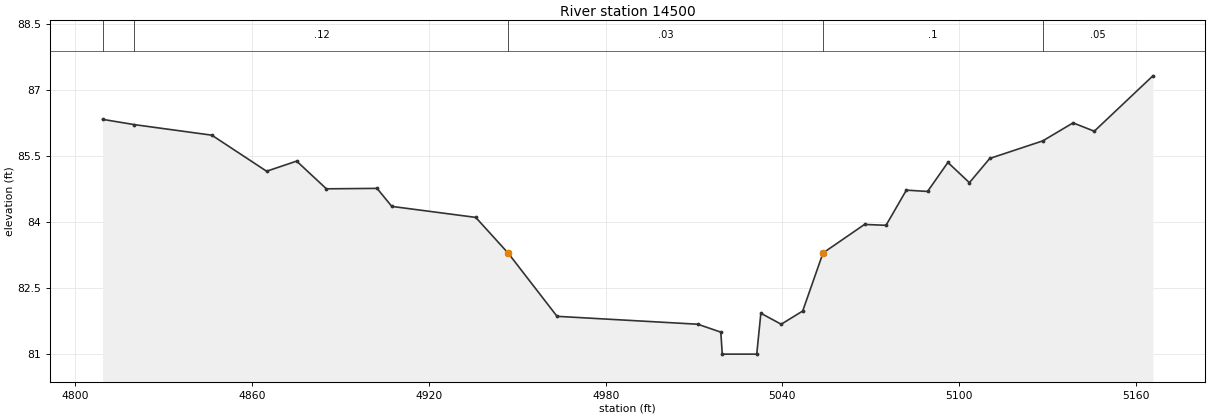
Type RM Length L Ch R = 1 ,14500   ,470,470,470
BEGIN DESCRIPTION:
WOODSONS GULLY 27.0
END DESCRIPTION:
XS GIS Cut Line= 3
      3876268.32     10035676.07      3876237.29     10035487.81
      3876122.35     10035368.31
#Sta/Elev= 30
  4809.2   86.33    4820   86.21  4846.3   85.97  4864.9   85.15  4875.1   85.38
  4885.2   84.75  4902.4   84.76  4907.4   84.35  4935.9    84.1    4947   83.28
  4963.5   81.85  5011.3   81.67  5019.1   81.49  5019.6   80.99  5031.3   80.99
  5032.7   81.92  5039.6   81.67  5046.9   81.97  5053.8   83.29  5067.9   83.94
  5075.2   83.92  5082.1   84.72  5089.3   84.69  5096.2   85.35  5103.5   84.89
  5110.4   85.44  5128.4   85.84  5138.7   86.25  5145.9   86.06  5165.8   87.32
#Mann= 5 ,-1 , 0
  4809.2      .1       0    4820     .12       0    4947     .03       0
  5053.8      .1       0  5128.4     .05       0
Bank Sta=4947,5053.8
XS Rating Curve= 0 ,0
Exp/Cntr=0.3,0.1