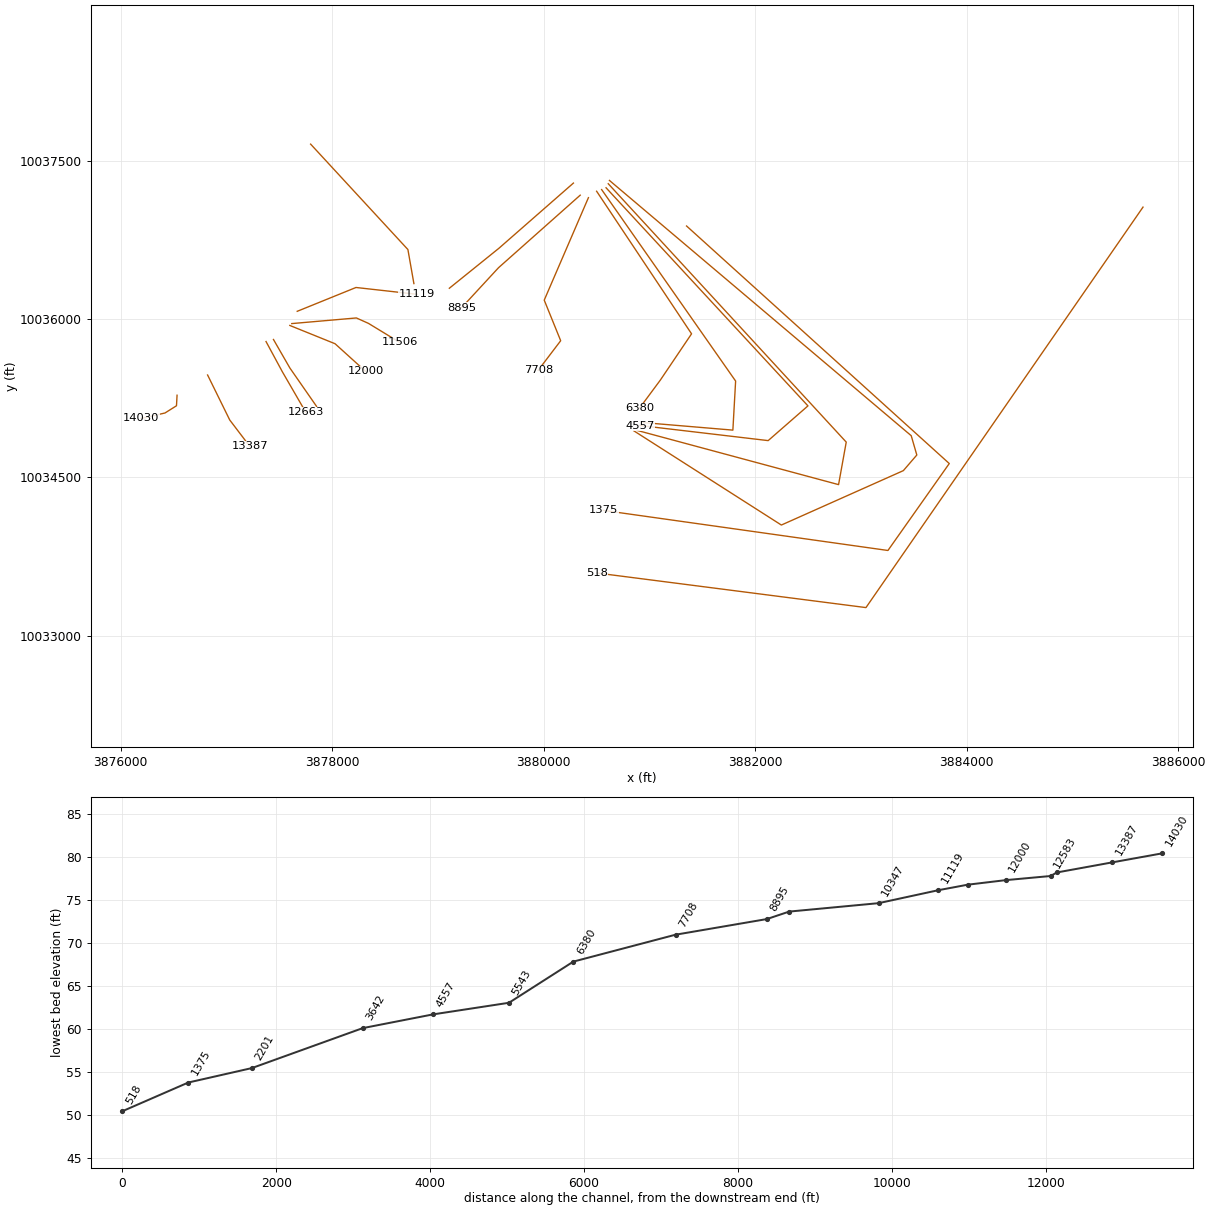
HEC-RAS study WOODSONS GULLY.prj: WOODSONS GULLY Base Level Engineering

--- WOODSONS GULLY.g10 (geometry) --- (continued)

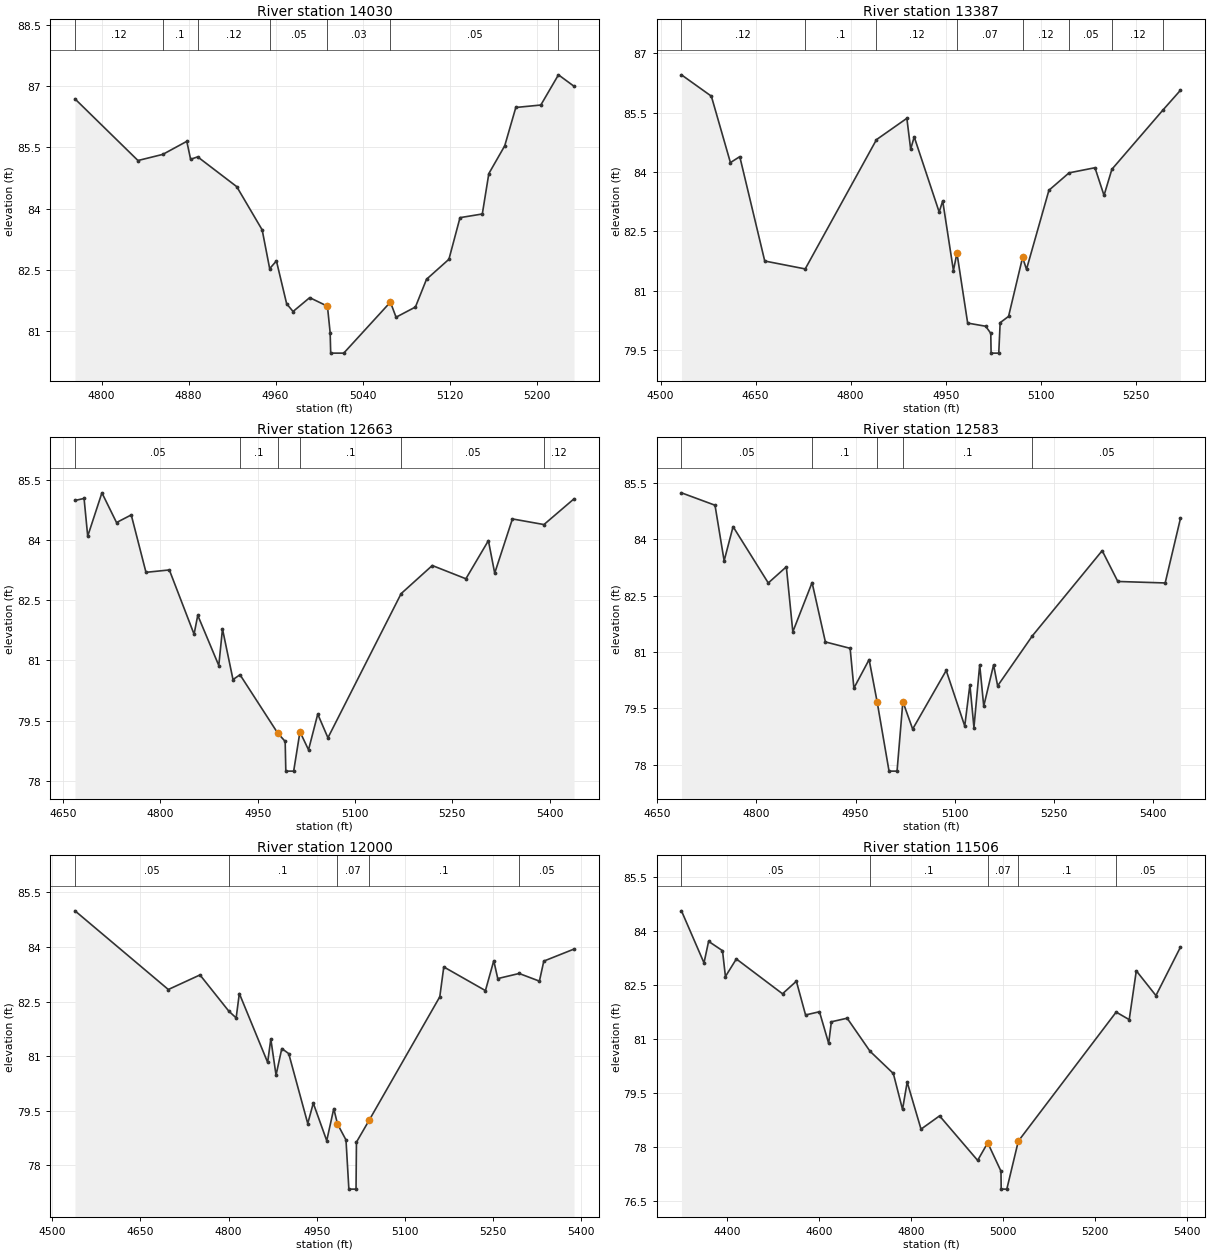
Type RM Length L Ch R = 1 ,14030   ,643,643,643
BEGIN DESCRIPTION:
WOODSONS GULLY 26.0
END DESCRIPTION:
XS GIS Cut Line= 4
      3876534.29     10035278.88      3876528.86       10035179.
      3876420.35     10035110.64      3876195.78     10035058.57
#Sta/Elev= 30
  4775.6   86.69  4833.5   85.18  4856.3   85.33  4878.4   85.65  4881.9   85.21
  4888.4   85.27  4924.3   84.54  4947.7   83.48  4954.6   82.53  4960.8   82.72
  4970.2   81.67  4976.1   81.48  4991.4   81.82  5007.7   81.61  5010.2   80.96
  5010.7   80.46  5022.7   80.46  5065.6   81.71  5070.8   81.34  5088.6   81.59
  5098.8   82.27  5119.4   82.76  5129.6   83.78  5150.1   83.87  5156.1   84.86
  5170.7   85.54  5180.9   86.48  5203.9   86.54  5220.1   87.28  5234.4      87
#Mann= 7 ,-1 , 0
  4775.6     .12       0  4856.3      .1       0  4888.4     .12       0
  4954.6     .05       0  5007.7     .03       0  5065.6     .05       0
  5220.1     .12       0
Bank Sta=5007.7,5065.6
XS Rating Curve= 0 ,0
Exp/Cntr=0.3,0.1

Type RM Length L Ch R = 1 ,13387   ,724,724,724
BEGIN DESCRIPTION:
WOODSONS GULLY 25.0
END DESCRIPTION:
XS GIS Cut Line= 3
      3876823.09     10035470.49      3877032.33     10035044.37
      3877221.67     10034794.91
#Sta/Elev= 30
  4532.8   86.46    4580   85.92  4610.1   84.24  4624.9   84.39  4664.3   81.75
  4728.2   81.55  4840.7   84.82  4888.7   85.36  4894.7   84.58  4900.3   84.89
  4939.7   82.99  4945.3   83.27  4962.2   81.51  4967.8   81.95  4984.7   80.18
  5013.2    80.1  5021.2   79.92  5021.7   79.42  5033.8   79.42    5036   80.19
  5049.3   80.35  5071.4   81.84  5077.6   81.54    5113   83.54  5144.8   83.98
  5185.7   84.11    5200   83.41  5212.4   84.07  5293.6   85.58  5320.7   86.07
#Mann= 8 ,-1 , 0
  4532.8     .12       0  4728.2      .1       0  4840.7     .12       0
  4967.8     .07       0  5071.4     .12       0  5144.8     .05       0
  5212.4     .12       0  5293.6     .05       0
Bank Sta=4967.8,5071.4
XS Rating Curve= 0 ,0
Exp/Cntr=0.3,0.1

Type RM Length L Ch R = 1 ,12663   ,80,80,80
BEGIN DESCRIPTION:
WOODSONS GULLY 24.0
END DESCRIPTION:
XS GIS Cut Line= 3
      3877375.69     10035787.37      3877529.35      10035502.2
      3877751.98     10035116.82
#Sta/Elev= 30
  4668.5   84.98  4682.5   85.03  4688.1   84.09    4710   85.17  4732.5   84.43
  4755.2   84.62  4777.9   83.19  4813.9   83.25    4852   81.65  4857.7   82.12
  4890.1   80.87  4895.8   81.78    4912   80.52  4922.8   80.64 4980.96  79.186
  4992.4   78.98  4993.4   78.24  5005.5   78.24  5015.2   79.22  5028.4   78.77
  5042.6   79.66  5058.3   79.07  5171.1   82.66  5219.1   83.36  5270.9   83.03
  5305.6   83.98  5315.3   83.17  5342.6   84.52  5391.2   84.38  5437.5   85.02
#Mann= 6 ,-1 , 0
  4668.5     .05       0  4922.8      .1       0 4980.96     .07       0
  5015.2      .1       0  5171.1     .05       0  5391.2     .12       0
Bank Sta=4980.96,5015.2
XS Rating Curve= 0 ,0
Exp/Cntr=0.3,0.1

Type RM Length L Ch R = 1 ,12583   ,583,583,583
BEGIN DESCRIPTION:
WOODSONS GULLY 23.0
END DESCRIPTION:
XS GIS Cut Line= 3
       3877445.9     10035807.02       3877601.1     10035536.71
       3877853.3     10035173.23
#Sta/Elev= 30
  4686.8   85.24  4737.5   84.91  4751.3   83.43  4764.8   84.34    4818   82.84
  4845.3   83.27  4855.1   81.54  4884.2   82.85  4904.3   81.27  4941.7    81.1
  4947.4   80.04  4970.4    80.8 4982.58  79.668  5000.5   77.83  5012.6   77.83
  5021.4   79.68  5036.2   78.95  5086.9   80.51  5114.9   79.03  5122.7   80.13
  5128.8   78.99  5137.5   80.66  5143.6   79.56  5158.5   80.66  5164.6    80.1
    5217   81.43  5322.6    83.7  5346.2   82.88  5417.8   82.84  5440.9   84.56
#Mann= 5 ,-1 , 0
  4686.8     .05       0  4884.2      .1       0 4982.58     .07       0
  5021.4      .1       0    5217     .05       0
Bank Sta=4982.58,5021.4
XS Rating Curve= 0 ,0
Exp/Cntr=0.3,0.1

Type RM Length L Ch R = 1 ,12000   ,494,494,494
BEGIN DESCRIPTION:
WOODSONS GULLY 22.0
END DESCRIPTION:
XS GIS Cut Line= 3
      3877600.59     10035939.92      3878028.24      10035766.7
      3878315.86     10035505.98
#Sta/Elev= 30
  4538.6   84.99  4697.5   82.83  4751.4   83.23  4800.3   82.24    4813   82.05
  4818.4   82.72  4866.6   80.83    4872   81.47  4880.9   80.48  4890.7   81.21
  4902.5   81.07  4934.9   79.15  4944.3   79.71  4967.2   78.68  4979.2   79.56
 4985.52  79.139    5000    78.7  5004.9   77.35  5017.1   77.35  5017.8   78.64
  5039.4   79.24  5159.7   82.63  5166.5   83.45  5237.4    82.8  5251.6   83.62
  5258.4   83.13  5294.8   83.27  5329.3   83.06  5336.8   83.61  5388.2   83.94
#Mann= 5 ,-1 , 0
  4538.6     .05       0  4800.3      .1       0 4985.52     .07       0
  5039.4      .1       0  5294.8     .05       0
Bank Sta=4985.52,5039.4
XS Rating Curve= 0 ,0
Exp/Cntr=0.3,0.1

Type RM Length L Ch R = 1 ,11506   ,387,387,387
BEGIN DESCRIPTION:
WOODSONS GULLY 21.0
END DESCRIPTION:
XS GIS Cut Line= 4
      3877619.03     10035957.62      3878229.68     10036011.01
      3878343.93     10035959.67      3878639.83     10035779.24
#Sta/Elev= 30
  4300.9   84.57  4349.9   83.12  4359.9   83.72  4390.1   83.46  4396.5   82.74
  4420.2   83.23  4520.6   82.26  4550.7   82.61  4570.7   81.67  4600.9   81.76
  4620.9   80.88  4626.8   81.48  4661.1   81.58  4710.8   80.66  4761.5   80.04
  4781.5   79.04  4791.6    79.8  4821.7   78.49    4862   78.86  4944.8   77.62
  4966.7   78.11  4995.5   77.32    4996   76.82  5008.2   76.82 5033.23  78.157
  5245.9   81.75  5274.3   81.54  5289.7    82.9  5332.4   82.21  5385.7   83.56
#Mann= 5 ,-1 , 0
  4300.9     .05       0  4710.8      .1       0  4966.7     .07       0
 5033.23      .1       0  5245.9     .05       0
Bank Sta=4966.7,5033.23
XS Rating Curve= 0 ,0
Exp/Cntr=0.3,0.1

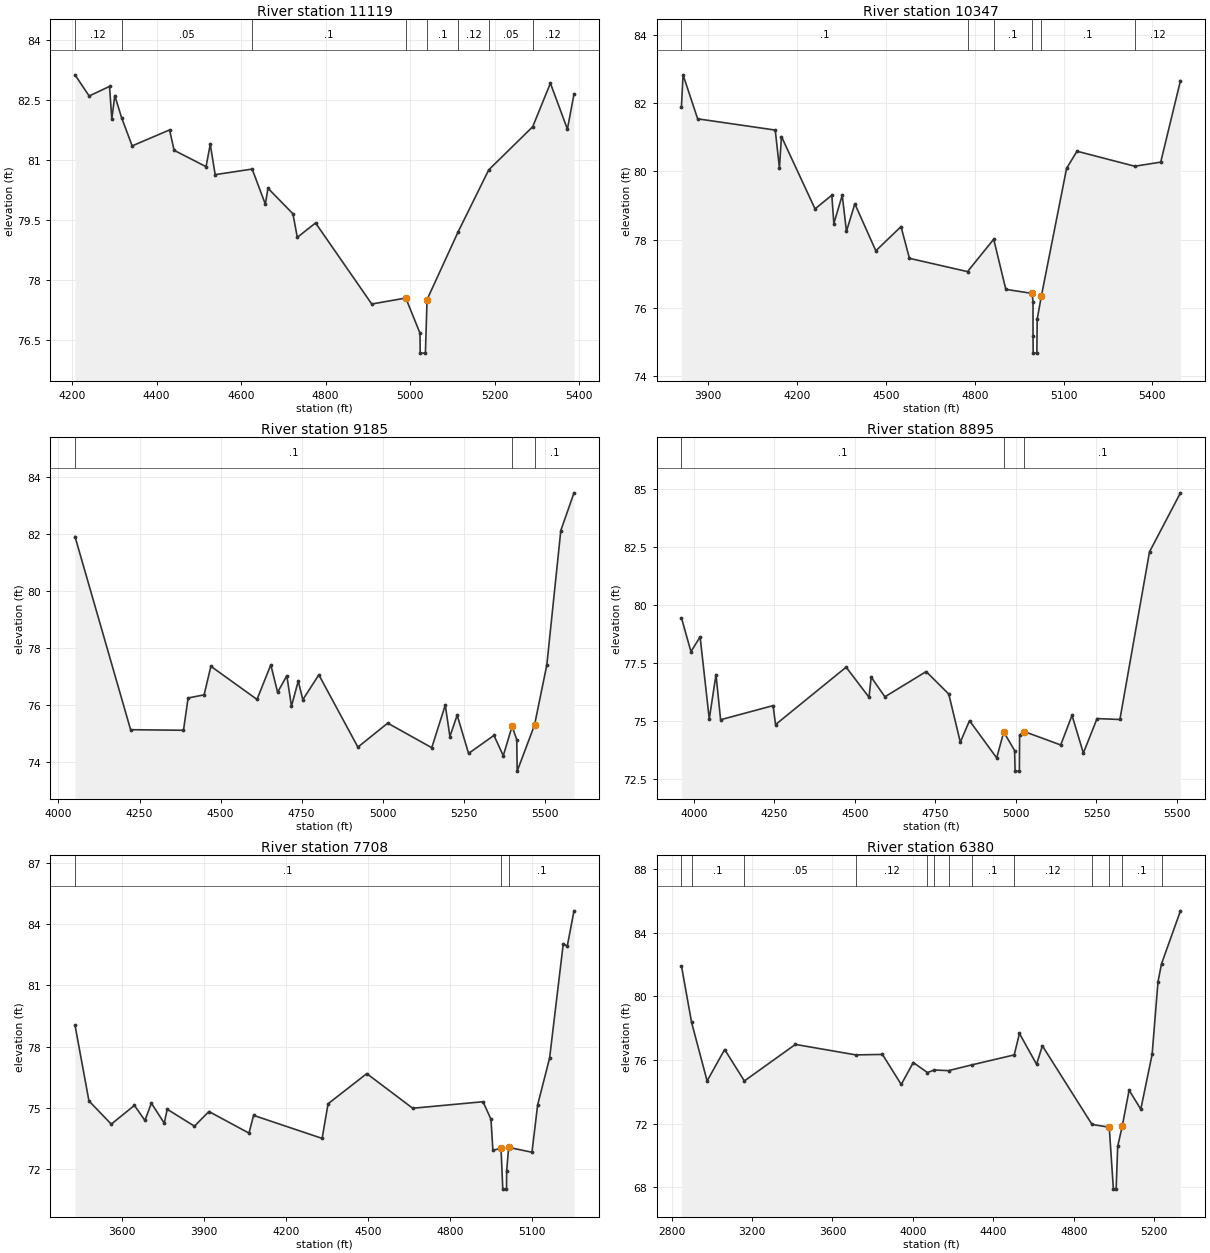
Type RM Length L Ch R = 1 ,11119   ,772,772,772
BEGIN DESCRIPTION:
WOODSONS GULLY 20.0
END DESCRIPTION:
XS GIS Cut Line= 3
      3877670.63     10036073.93      3878226.21     10036299.63
      3878803.33     10036235.03
#Sta/Elev= 30
  4207.1   83.14  4240.6   82.61  4288.8   82.85  4294.2   82.03  4301.2   82.62
  4317.6   82.06  4342.3   81.36  4430.8   81.76  4441.6   81.25  4517.1   80.84
  4527.1    81.4  4538.7   80.64  4626.2   80.78  4657.4    79.9  4663.6    80.3
  4722.6   79.66    4733   79.07  4776.2   79.43  4909.1    77.4  4989.6   77.55
  5023.2   76.67  5023.7   76.17    5036   76.17  5039.9   77.51  5113.5   79.21
  5185.8   80.76  5289.8   81.84  5331.7   82.93  5371.9   81.78  5387.5   82.66
#Mann= 8 ,-1 , 0
  4207.1     .12       0  4317.6     .05       0  4626.2      .1       0
  4989.6     .07       0  5039.9      .1       0  5113.5     .12       0
  5185.8     .05       0  5289.8     .12       0
Bank Sta=4989.6,5039.9
XS Rating Curve= 0 ,0
Exp/Cntr=0.3,0.1

Type RM Length L Ch R = 1 ,10347   ,1162,1162,1162
BEGIN DESCRIPTION:
WOODSONS GULLY 19.0
END DESCRIPTION:
XS GIS Cut Line= 3
      3877797.25     10037657.93      3878717.07     10036659.17
      3878773.74      10036336.7
#Sta/Elev= 30
  3809.6    81.9    3815   82.83  3864.3   81.54  4126.3   81.21  4140.5    80.1
  4147.3   81.02  4260.7    78.9  4317.4    79.3  4324.2   78.47  4352.6    79.3
  4366.8   78.24  4395.1   79.05    4466   77.67  4551.1   78.38  4579.5   77.45
  4775.7   77.06  4864.1   78.01    4905   76.54 4994.15  76.421  4996.8   76.17
  4996.9   75.17  4997.4   74.67  5009.8   74.67    5011   75.67  5025.2   76.35
  5110.3   80.09  5145.4   80.59  5340.4   80.15  5428.1   80.27  5494.8   82.66
#Mann= 6 ,-1 , 0
  3809.6      .1       0  4775.7     .12       0  4864.1      .1       0
 4994.15     .07       0  5025.2      .1       0  5340.4     .12       0
Bank Sta=4994.15,5025.2
XS Rating Curve= 0 ,0
Exp/Cntr=0.3,0.1

Type RM Length L Ch R = 1 ,9185    ,290,290,290
BEGIN DESCRIPTION:
WOODSONS GULLY 17.0
END DESCRIPTION:
XS GIS Cut Line= 3
      3880282.16     10037288.93      3879577.31     10036670.89
       3879108.8     10036292.44
#Sta/Elev= 30
  4050.9    81.9  4222.5   75.14  4385.7   75.12  4399.9   76.25  4449.3   76.36
  4470.2   77.36  4612.5    76.2  4655.1   77.41  4676.1   76.45  4704.6   77.03
  4718.8   75.96  4739.7   76.84  4753.9   76.19  4803.3   77.06  4923.8   74.53
  5015.8   75.37  5151.7   74.51  5193.4      76  5207.7    74.9  5230.1   75.65
  5265.3   74.31  5343.6   74.94  5372.4   74.23  5399.6   75.26    5414   74.79
  5415.3   73.69 5468.75  75.301  5506.8   77.41  5549.9   82.11  5590.6   83.43
#Mann= 3 , 0 , 0
  4050.9      .1       0  5399.6     .03       0 5468.75      .1       0
Bank Sta=5399.6,5468.75
XS Rating Curve= 0 ,0
Exp/Cntr=0.3,0.1

Type RM Length L Ch R = 1 ,8895    ,1187,1187,1187
BEGIN DESCRIPTION:
WOODSONS GULLY 15.0
END DESCRIPTION:
XS GIS Cut Line= 3
      3880346.38     10037174.34      3879573.84     10036486.86
       3879224.9     10036108.41
#Sta/Elev= 30
  3961.9   79.44  3991.4   77.98  4019.8   78.62  4048.2   75.07  4069.1   76.99
  4083.4   75.04  4246.4   75.65  4253.9   74.83    4473   77.31  4544.1   76.01
  4550.8   76.88  4593.4   76.03  4721.4   77.12  4791.6   76.15  4827.5   74.07
    4856      75  4940.4   73.39  4962.2   74.51    4996   73.71  4997.5   72.82
  5010.8   72.82  5011.5   74.37  5025.7   74.53  5139.1   73.95  5174.2   75.23
  5209.4    73.6  5251.9   75.09  5322.8   75.05  5414.7   82.29  5510.8   84.84
#Mann= 3 , 0 , 0
  3961.9      .1       0  4962.2     .03       0  5025.7      .1       0
Bank Sta=4962.2,5025.7
XS Rating Curve= 0 ,0
Exp/Cntr=0.3,0.1

Type RM Length L Ch R = 1 ,7708    ,1328,1328,1328
BEGIN DESCRIPTION:
WOODSONS GULLY 13.0
END DESCRIPTION:
XS GIS Cut Line= 4
      3880423.98     10037150.62      3880006.13      10036179.8
      3880161.73     10035795.25      3879948.97     10035515.03
#Sta/Elev= 30
  3429.9   79.05  3480.9   75.33  3562.4   74.19  3647.1   75.11  3685.5   74.37
    3709   75.22    3756   74.24    3767   74.92  3866.5   74.09  3919.3   74.81
  4065.7   73.75  4082.6   74.62    4333   73.49  4354.8   75.19  4496.2   76.67
  4664.1   74.97    4921   75.29  4950.1   74.43  4957.1   72.91 4986.81  73.002
  4993.3      71  5006.8      71  5007.4   71.87  5014.6   73.05  5099.9   72.81
  5120.7   75.14  5164.3   77.43  5214.3   83.05  5228.8   82.92  5253.5   84.66
#Mann= 3 , 0 , 0
  3429.9      .1       0 4986.81     .07       0  5014.6      .1       0
Bank Sta=4986.81,5014.6
XS Rating Curve= 0 ,0
Exp/Cntr=0.3,0.1

Type RM Length L Ch R = 1 ,6380    ,837,837,837
BEGIN DESCRIPTION:
WOODSONS GULLY 11.0
END DESCRIPTION:
XS GIS Cut Line= 4
      3880501.56     10037211.41      3881399.14      10035860.7
      3881103.51     10035421.59      3880906.78     10035155.77
#Sta/Elev= 30
  2848.9   81.92  2899.4   78.36  2976.5   74.68  3063.7   76.66  3161.8   74.68
  3415.5   76.98  3716.4   76.32  3848.4   76.35  3941.9   74.46  4001.8   75.84
  4072.4   75.21  4106.6   75.37  4177.2   75.33  4292.4   75.69  4503.8   76.32
    4530   77.67  4614.9   75.73    4644   76.89  4890.8   71.94  4976.5   71.77
  4997.1   67.87  5010.8   67.87  5018.6   70.57 5040.97  71.826  5075.3    74.1
  5133.4    72.9  5189.7   76.35    5219   80.93  5236.4   82.05  5330.7   85.39
#Mann= 13 ,-1 , 0
  2848.9     .05       0  2899.4      .1       0  3161.8     .05       0
  3716.4     .12       0  4072.4     .05       0  4106.6     .12       0
  4177.2     .05       0  4292.4      .1       0  4503.8     .12       0
  4890.8      .1       0  4976.5     .07       0 5040.97      .1       0
  5236.4     .05       0
Bank Sta=4976.5,5040.97
XS Rating Curve= 0 ,0
Exp/Cntr=0.3,0.1

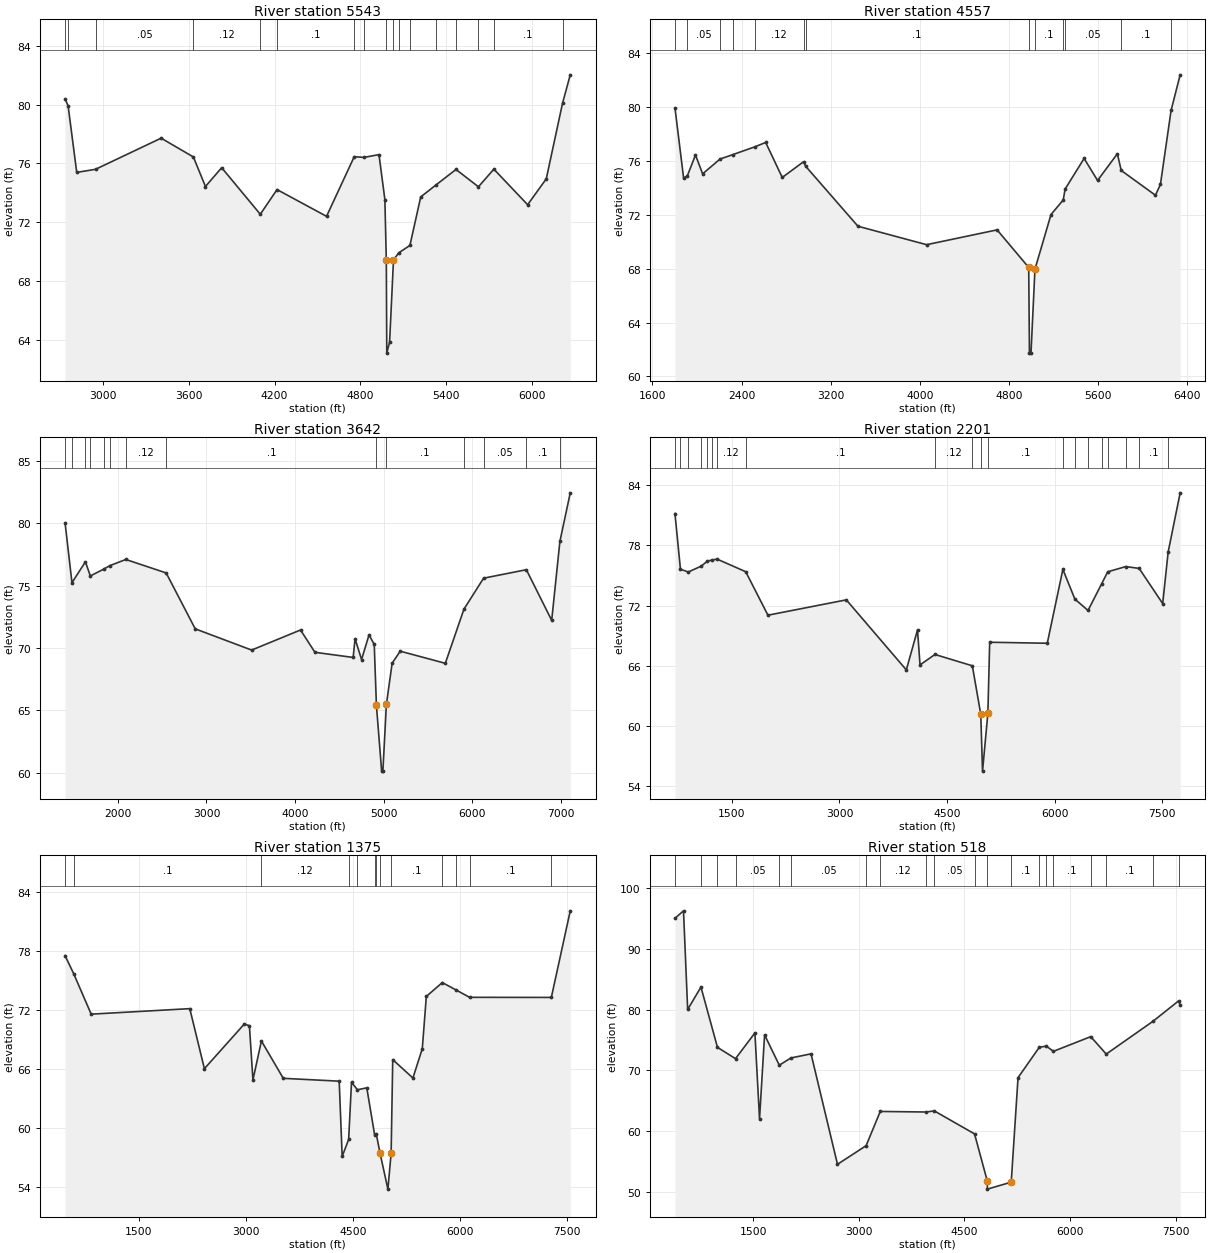
Type RM Length L Ch R = 1 ,5543    ,986,986,986
BEGIN DESCRIPTION:
WOODSONS GULLY 9.0
END DESCRIPTION:
XS GIS Cut Line= 4
      3880548.96     10037227.08      3881815.81     10035413.11
      3881789.77     10034948.27      3880941.19     10035019.74
#Sta/Elev= 30
  2735.8   80.38  2757.2   79.91  2817.4   75.38  2948.7   75.59  3407.1   77.71
  3632.4   76.43  3716.7   74.42  3830.1    75.7    4100   72.53  4216.9   74.21
  4562.8   72.39  4756.3   76.45  4824.2    76.4  4929.1   76.59  4970.4   73.53
  4980.4   69.39  4983.6   63.08  5003.3   63.83  5030.5   69.42  5066.5    69.9
  5145.3   70.41  5220.8   73.71  5329.4   74.54  5467.2   75.58    5624    74.4
  5731.7    75.6  5967.8   73.18  6097.9   74.94  6211.7   80.09  6265.5   82.02
#Mann= 17 ,-1 , 0
  2735.8     .05       0  2757.2      .1       0  2948.7     .05       0
  3632.4     .12       0    4100     .05       0  4216.9      .1       0
  4756.3     .12       0  4824.2      .1       0  4980.4     .07       0
  5030.5      .1       0  5066.5     .12       0  5145.3      .1       0
  5329.4     .12       0  5467.2     .05       0    5624     .12       0
  5731.7      .1       0  6211.7     .05       0
Bank Sta=4980.4,5030.5
XS Rating Curve= 0 ,0
Exp/Cntr=0.3,0.1

Type RM Length L Ch R = 1 ,4557    ,915,915,915
BEGIN DESCRIPTION:
WOODSONS GULLY 7.0
END DESCRIPTION:
XS GIS Cut Line= 4
      3880590.69     10037244.37      3882499.66     10035177.94
      3882123.53     10034848.88      3880911.95     10034991.99
#Sta/Elev= 30
  1802.3   79.94  1880.4    74.7  1914.3   74.91  1986.5   76.44  2050.5   75.04
  2207.3   76.14  2319.4   76.46  2520.6   77.05  2616.4   77.37    2765   74.77
  2956.4   75.94  2975.3    75.6  3444.3   71.15  4060.1   69.78  4692.7   70.88
  4976.5   68.09    4983   61.73  4996.9   61.73  5032.5   67.96  5176.5   72.02
  5286.2    73.1  5303.1   73.91  5473.4   76.18  5594.3   74.55  5771.9   76.53
  5806.5   75.29  6113.6   73.45  6158.2   74.25    6254   79.75  6335.3   82.39
#Mann= 13 ,-1 , 0
  1802.3      .1       0  1914.3     .05       0  2207.3     .12       0
  2319.4     .05       0  2520.6     .12       0  2956.4     .05       0
  2975.3      .1       0  4976.5     .07       0  5032.5      .1       0
  5286.2     .12       0  5303.1     .05       0  5806.5      .1       0
    6254     .05       0
Bank Sta=4976.5,5032.5
XS Rating Curve= 0 ,0
Exp/Cntr=0.3,0.1

Type RM Length L Ch R = 1 ,3642    ,1441,1441,1441
BEGIN DESCRIPTION:
WOODSONS GULLY 5.0
END DESCRIPTION:
XS GIS Cut Line= 4
      3880611.48     10037282.61      3882861.75     10034834.72
      3882789.21     10034431.87      3880885.48     10034945.27
#Sta/Elev= 30
  1402.8   80.03  1480.9   75.23  1632.9    76.9  1688.3   75.77  1840.4   76.32
  1907.2   76.59  2088.9   77.09  2544.9   76.01  2873.2   71.53  3510.3   69.83
  4062.5   71.44  4225.2   69.65  4656.8   69.24  4678.4   70.74  4751.9   69.07
  4836.3   71.05    4895   70.28 4919.64  65.399  4978.6   60.13  4992.6   60.13
  5032.1  65.469  5097.3   68.78  5188.4   69.74  5697.9   68.77  5908.3   73.11
  6130.1   75.59    6613   76.27  6899.3   72.21  6991.8   78.53  7108.9   82.43
#Mann= 14 ,-1 , 0
  1402.8      .1       0  1480.9     .05       0  1632.9     .12       0
  1688.3     .05       0  1840.4     .12       0  1907.2     .05       0
  2088.9     .12       0  2544.9      .1       0 4919.64     .07       0
  5032.1      .1       0  5908.3     .12       0  6130.1     .05       0
    6613      .1       0  6991.8     .05       0
Bank Sta=4919.64,5032.1
XS Rating Curve= 0 ,0
Exp/Cntr=0.3,0.1

Type RM Length L Ch R = 1 ,2201    ,826,826,826
BEGIN DESCRIPTION:
WOODSONS GULLY 4.0
END DESCRIPTION:
XS GIS Cut Line= 6
      3880622.64     10037313.99      3883476.16     10034895.46
      3883529.09      10034712.4      3883401.74     10034564.41
      3882248.32       10034049.      3880852.77     10034941.97
#Sta/Elev= 30
   705.5   81.18   782.1   75.63     891   75.35  1073.4   75.94  1158.1   76.44
    1219   76.53  1291.7   76.64  1692.4   75.38  2002.5   71.04  3095.5   72.57
  3932.6   65.58  4088.6   69.57  4123.7   66.08  4331.8   67.12  4853.5   65.99
 4970.84  61.157  4995.6   55.48  5070.1  61.257  5095.5   68.34  5898.6   68.24
  6116.3   75.61  6283.2   72.65    6467   71.51  6658.1   74.19    6742   75.37
    6993   75.89  7180.1   75.71  7508.5    72.2  7584.8   77.35    7752   83.25
#Mann= 20 ,-1 , 0
   705.5      .1       0   782.1     .05       0     891     .12       0
  1073.4     .05       0  1158.1     .12       0    1219     .05       0
  1291.7     .12       0  1692.4      .1       0  4331.8     .12       0
  4853.5      .1       0 4970.84     .07       0  5070.1      .1       0
  6116.3     .05       0  6283.2      .1       0    6467     .12       0
  6658.1     .05       0    6742     .12       0    6993     .05       0
  7180.1      .1       0  7584.8     .05       0
Bank Sta=4970.84,5070.1
XS Rating Curve= 0 ,0
Exp/Cntr=0.3,0.1

Type RM Length L Ch R = 1 ,1375    ,857,857,857
BEGIN DESCRIPTION:
WOODSONS GULLY 2.0
END DESCRIPTION:
XS GIS Cut Line= 4
      3881351.86     10036882.31      3883835.98     10034631.63
      3883256.06     10033807.97      3880565.85     10034187.74
#Sta/Elev= 30
   471.1   77.53   591.5    75.7   837.3   71.58  2218.1   72.14  2422.8   66.04
  2982.4   70.58  3053.4    70.4  3102.7    64.9  3221.6   68.85  3527.8   65.06
    4311   64.77  4352.8   57.12  4443.5   58.85  4483.4   64.65  4567.1    63.9
  4697.7   64.09  4807.7    59.3    4830   59.43  4883.8  57.423  4993.3    53.8
 5038.48  57.442    5061   66.96  5343.8   65.09    5475   68.07  5531.5   73.38
  5755.2   74.79  5947.3   74.04  6137.2   73.29  7282.6   73.28  7547.4   82.08
#Mann= 13 ,-1 , 0
   471.1     .12       0   591.5      .1       0  3221.6     .12       0
  4443.5      .1       0  4567.1     .12       0  4807.7     .05       0
    4830      .1       0  4883.8     .07       0 5038.48      .1       0
  5755.2     .12       0  5947.3     .05       0  6137.2      .1       0
  7282.6     .05       0
Bank Sta=4883.8,5038.48
XS Rating Curve= 0 ,0
Exp/Cntr=0.3,0.1

Type RM Length L Ch R = 1 ,518     ,0,0,0
BEGIN DESCRIPTION:
WOODSONS GULLY 1.0
END DESCRIPTION:
XS GIS Cut Line= 3
      3885667.86     10037061.08      3883048.24     10033266.86
      3880504.05     10033594.55
#Sta/Elev= 30
   389.3   95.02   510.8   96.25   569.8   80.02   758.7    83.7   993.3   73.78
  1249.7   71.93    1525   76.16  1590.6   62.02  1662.3   75.84  1871.4   70.85
  2035.5   72.04  2322.1   72.72  2697.9   54.54  3104.7   57.61  3305.4   63.24
  3955.2   63.15    4073   63.33  4644.5   59.55 4825.96  51.783  4827.1   50.46
 5165.75  51.608  5262.5    68.8  5564.6    73.8  5664.5   73.99  5764.5   73.13
  6295.2   75.55  6515.2   72.68  7177.6   78.06  7542.8   81.43  7565.2   80.81
#Mann= 20 ,-1 , 0
   389.3     .05       0   758.7     .12       0   993.3      .1       0
  1249.7     .05       0  1871.4      .1       0  2035.5     .05       0
  3104.7      .1       0  3305.4     .12       0  3955.2     .12       0
    4073     .05       0  4644.5      .1       0 4825.96     .07       0
 5165.75      .1       0  5564.6     .05       0  5664.5     .12       0
  5764.5      .1       0  6295.2     .12       0  6515.2      .1       0
  7177.6     .05       0  7542.8     .05       0
Bank Sta=4825.96,5165.75
XS Rating Curve= 0 ,0
Exp/Cntr=0.3,0.1