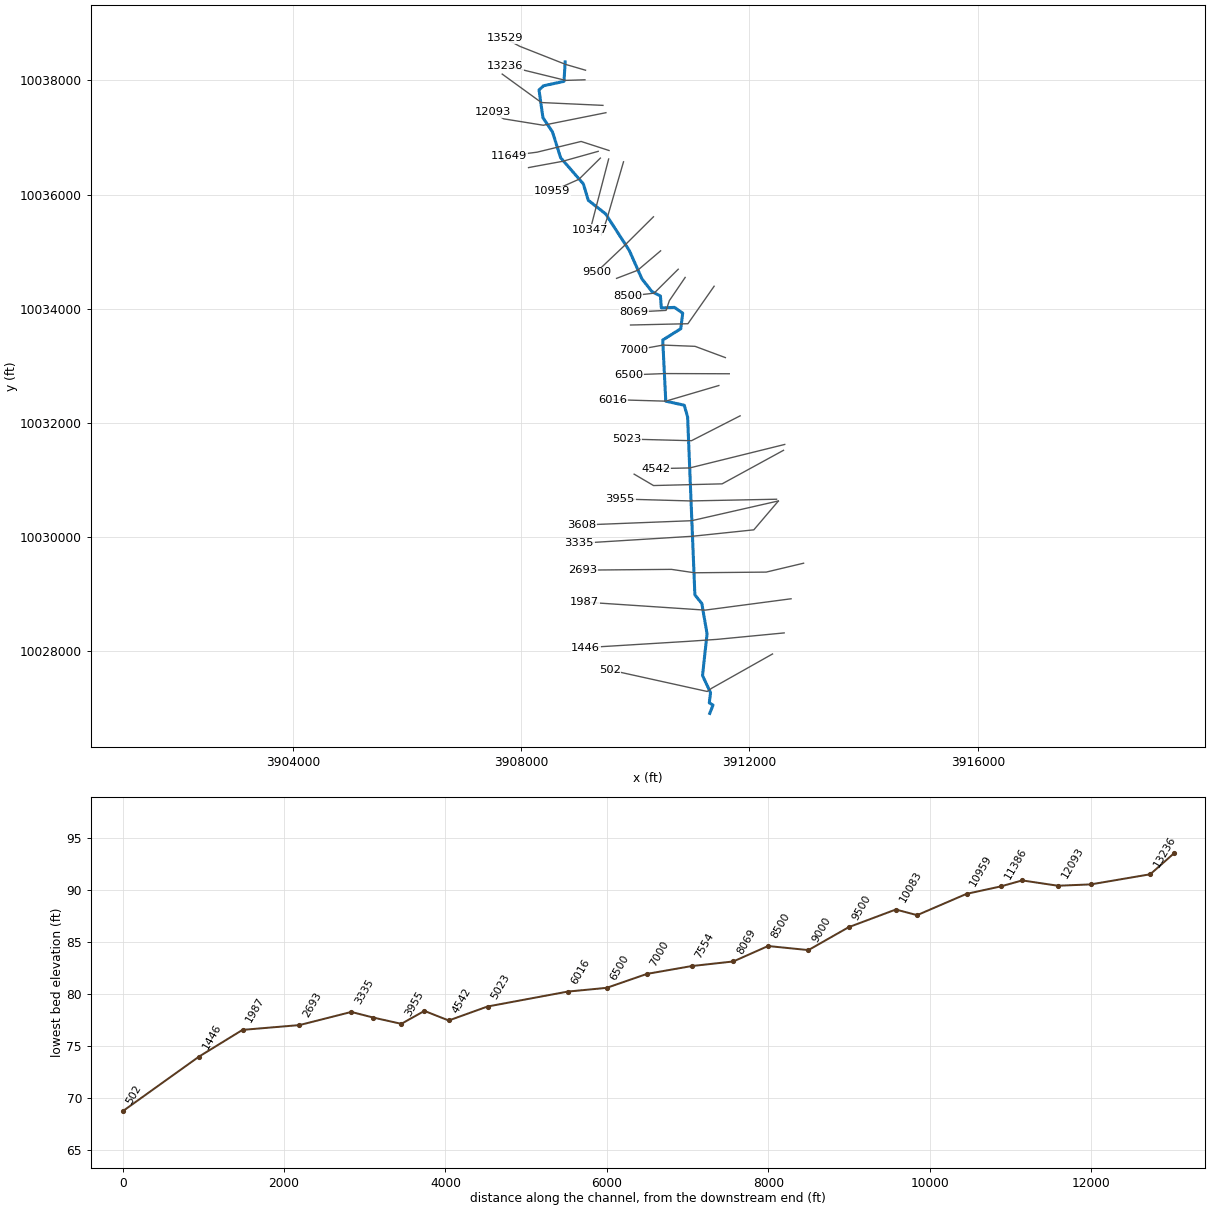
--- BENS BRANCH TRIBUTARY NO 1.prj (project) ---

Proj Title=BENS BRANCH TRIBUTARY NO 1 Base Level Engineering
Current Plan=p01
Default Exp/Contr=0.3,0.1
English Units
Geom File=g01
Flow File=f01
Flow File=f02
Plan File=p01
Y Axis Title=Elevation
X Axis Title(PF)=Main Channel Distance
X Axis Title(XS)=Station
BEGIN DESCRIPTION:
BENS BRANCH TRIBUTARY NO 1
END DESCRIPTION:
DSS Export Rating Curves= 0
DSS Export Rating Curve Sorted= 0
DSS Export Volume Flow Curves= 0
DXF OffsetX= 0
DXF OffsetY= 0
DXF ScaleX= 1
DXF ScaleY= 10

--- BENS BRANCH TRIBUTARY NO 1.p01 (plan) ---

Plan Title=Multiple Run
Program Version=4.10
Short Identifier=Multiple
Geom File=g01
Flow File=f01
Subcritical Flow
K Sum by GR= 0
Std Step Tol= 0.01
Critical Tol= 0.01
Num of Std Step Trials= 20
Max Error Tol= 0.3
Flow Tol Ratio= 0.001
Split Flow NTrial= 30
Split Flow Tol= 0.02
Split Flow Ratio= 0.02
Log Output Level= 0
Friction Slope Method= 1
Unsteady Friction Slope Method= 2
Unsteady Bridges Friction Slope Method= 1
Parabolic Critical Depth
Global Vel Dist= 1 , 1 , 1
Global Log Level= 0
CheckData=True
Encroach Param=-1 ,0,0, 0
BEGIN DESCRIPTION:
Multiple Run
END DESCRIPTION:
Computation Interval=1HOUR
Output Interval=1HOUR
Run HTab= 0
Run UNet= 0
Run PostProcess= 0
Run WQNet= 0
UNET Theta= 1
UNET Theta Warmup= 1
UNET ZTol= 0.02
UNET ZSATol= 0.05
UNET MxIter= 20
UNET MaxInSteps= 0
UNET DtIC= 0
UNET DtMin= 0
UNET MaxCRTS= 20
UNET WFStab= 2
UNET SFStab= 1
UNET WFX= 1
UNET SFX= 1
UNET DSS MLevel= 4
UNET DZMax Abort= 100
UNET Convert EG Bridges= 0
UNET Use Existing IB Tables=-1
UNET Froude Reduction=False
UNET Froude Limit= 1
UNET Froude Power= 10
UNET Time Slicing=0,0, 5
UNET Junction Losses=0
Instantaneous Interval=1HOUR
Write IC File= 0
Write IC File at Sim End=0
Echo Input=False
Echo Parameters=False
Echo Output=False
Write Detailed= 0
WQ AD Non Conservative
WQ ULTIMATE=-1
WQ Max Comp Step=1HOUR
WQ Output Interval=15MIN
WQ Output Selected Increments= 0
WQ Output face flow=0
WQ Output face velocity=0
WQ Output face area=0
WQ Output face dispersion=0
WQ Output cell volume=0
WQ Output cell surface area=0
WQ Output cell continuity=0
WQ Output cumulative cell continuity=0
WQ Output face conc=0
WQ Output face dconc_dx=0
WQ Output face courant=0
WQ Output face peclet=0
WQ Output face adv mass=0
WQ Output face disp mass=0
WQ Output cell mass=0
WQ Output cell source sink temp=0
WQ Output cell source sink nsm=0
WQ Output MaxMinRange=-1
WQ Daily Max Min Mean=-1
WQ Daily Range=0
WQ Daily Time=0
WQ Create Restart=0
WQ Fixed Restart=0
WQ System Summary=0
WQ Use Fixed Temperature=0
Sorting and Armoring Iterations= 10
XS Update Threshold= 0.02
Hydraulics Update Threshold= 0.02
Energy Slope Method= 1
Volume Change Method= 0
XS Weighting Method= 0
Number of US Weighted Cross Sections= 1
Number of DS Weighted Cross Sections= 1
Upstream XS Weight=0.25
Main XS Weight=0.5
Downstream XS Weight=0.25
Number of DS XS's Weighted with US Boundary= 1
Upstream Boundary Weight= 1
Weight of XSs Associated with US Boundary= 0
Number of US XS's Weighted with DS Boundary= 1
Downstream Boundary Weight= 0.5
Weight of XSs Associated with DS Boundary= 0.5
Sediment Output Level= 4
Mass or Volume Output= 0
Output Increment Type= 1
Profile and TS Output Increment= 10
XS Output Flag= 0
XS Output Increment= 10
Disregard all LS=0
Disregard all Conn=0
Disregard all Breaches=0
Disregard all Pumps=0

--- BENS BRANCH TRIBUTARY NO 1.f01 (steady flow) ---

Flow Title=Multiple
Program Version=4.10
Number of Profiles= 7
Profile Names=10-year,25-year,50-year,1pct_min,100-year,1pct_plu,500-year
River Rch & RM=BENS BRANCH TRIB,Reach-1         ,13529
     406     510     654     276     833    2516    1394
Boundary for River Rch & Prof#=BENS BRANCH TRIB,Reach-1         , 1
Up Type= 0
Dn Type= 3
Dn Slope=0.005
Boundary for River Rch & Prof#=BENS BRANCH TRIB,Reach-1         , 2
Up Type= 0
Dn Type= 3
Dn Slope=0.005
Boundary for River Rch & Prof#=BENS BRANCH TRIB,Reach-1         , 3
Up Type= 0
Dn Type= 3
Dn Slope=0.005
Boundary for River Rch & Prof#=BENS BRANCH TRIB,Reach-1         , 4
Up Type= 0
Dn Type= 3
Dn Slope=0.005
Boundary for River Rch & Prof#=BENS BRANCH TRIB,Reach-1         , 5
Up Type= 0
Dn Type= 3
Dn Slope=0.005
Boundary for River Rch & Prof#=BENS BRANCH TRIB,Reach-1         , 6
Up Type= 0
Dn Type= 3
Dn Slope=0.005
Boundary for River Rch & Prof#=BENS BRANCH TRIB,Reach-1         , 7
Up Type= 0
Dn Type= 3
Dn Slope=0.005
DSS Import GetInterval= 0
DSS Import GetPeak= 0
DSS Import FillOption= 0

--- BENS BRANCH TRIBUTARY NO 1.f02 (steady flow) ---

Flow Title=Orig_BLE_Flows
Program Version=4.10
Number of Profiles= 7
Profile Names=10-year,25-year,50-year,1pct_min,100-year,1pct_plu,500-year
River Rch & RM=BENS BRANCH TRIB,Reach-1         ,13529
     467     584     672     253     765    2310     988
Boundary for River Rch & Prof#=BENS BRANCH TRIB,Reach-1         , 1
Up Type= 0
Dn Type= 3
Dn Slope=0.005
Boundary for River Rch & Prof#=BENS BRANCH TRIB,Reach-1         , 2
Up Type= 0
Dn Type= 3
Dn Slope=0.005
Boundary for River Rch & Prof#=BENS BRANCH TRIB,Reach-1         , 3
Up Type= 0
Dn Type= 3
Dn Slope=0.005
Boundary for River Rch & Prof#=BENS BRANCH TRIB,Reach-1         , 4
Up Type= 0
Dn Type= 3
Dn Slope=0.005
Boundary for River Rch & Prof#=BENS BRANCH TRIB,Reach-1         , 5
Up Type= 0
Dn Type= 3
Dn Slope=0.005
Boundary for River Rch & Prof#=BENS BRANCH TRIB,Reach-1         , 6
Up Type= 0
Dn Type= 3
Dn Slope=0.005
Boundary for River Rch & Prof#=BENS BRANCH TRIB,Reach-1         , 7
Up Type= 0
Dn Type= 3
Dn Slope=0.005
DSS Import GetInterval= 0
DSS Import GetPeak= 0
DSS Import FillOption= 0

--- BENS BRANCH TRIBUTARY NO 1.g01 (geometry) ---

Geom Title=Existing Conditions
Program Version=4.10

River Reach=BENS BRANCH TRIB,Reach-1
Reach XY= 30
      3908771.28     10038325.21      3908750.22     10037983.25
      3908393.28     10037906.86      3908313.41     10037832.56
      3908381.47     10037347.84      3908548.83     10037097.84
      3908691.19     10036646.45       3909089.8     10036186.72
      3909175.91     10035900.61      3909481.47     10035660.34
      3909894.66     10035020.06      3910116.19     10034522.14
      3910291.89     10034299.92       3910440.5     10034222.14
      3910455.08      10034015.2      3910688.41     10034023.53
      3910830.08     10033922.14      3910796.75     10033650.61
      3910480.34     10033451.39      3910533.73     10032380.91
      3910858.03     10032309.38      3910916.37     10032101.05
      3911043.73     10028985.47       3911165.6     10028835.99
      3911256.75      10028303.7      3911177.58     10027574.01
      3911317.68     10027274.53      3911296.33     10027093.81
      3911361.95     10027056.83       3911304.1     10026910.98

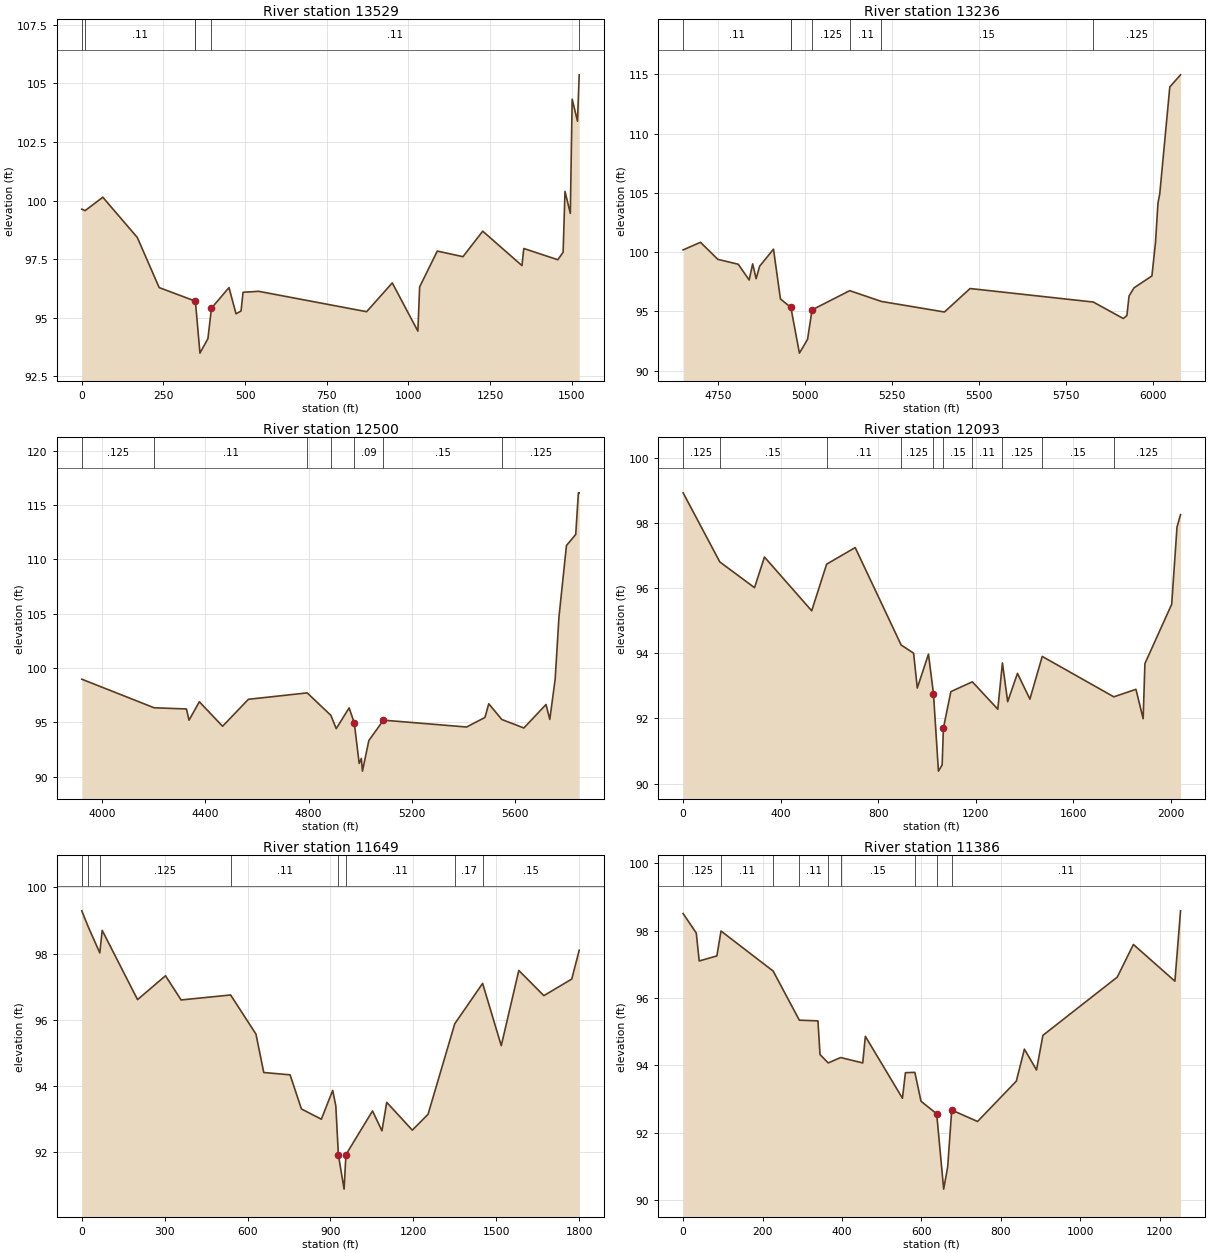
Type RM Length L Ch R = 1 ,13529   ,293,293,293
BEGIN DESCRIPTION:
BENS BRANCH TRIBUTARY NO. 1 27.0
END DESCRIPTION:
XS GIS Cut Line= 4
      3909127.84     10038178.97      3908778.45     10038280.97
      3907975.49     10038597.81      3907713.56     10038737.49
#Sta/Elev= 30
       0   99.63    10.4   99.57    64.4  100.14     170   98.42   236.9   96.28
   347.7    95.7   361.7   93.48   386.1    94.1   396.9    95.4   450.6   96.28
   472.1   95.16   487.5   95.28   493.6   96.08   541.7   96.12   871.8   95.25
   950.3   96.48  1028.7   94.42  1034.1   96.31  1088.2   97.84  1166.7    97.6
  1227.2   98.69  1347.3   97.22  1352.9   97.95    1457   97.47  1473.3   97.79
    1479  100.39  1495.3   99.45    1501  104.33  1517.3  103.39  1522.5  105.37
#Mann= 6 ,-1 , 0
       0    .125       0    10.4     .11       0   347.7    .125       0
   347.7     .09       0   396.9     .11       0  1522.5     .15       0
Bank Sta=347.7,396.9
XS Rating Curve= 0 ,0
Exp/Cntr=0.3,0.1

Type RM Length L Ch R = 1 ,13236   ,736,736,736
BEGIN DESCRIPTION:
BENS BRANCH TRIBUTARY NO. 1 26.0
END DESCRIPTION:
XS GIS Cut Line= 3
      3909117.84     10038011.07       3908780.3     10038000.65
      3907717.85     10038261.07
#Sta/Elev= 30
  4648.3  100.19  4698.3  100.83  4748.3   99.39  4806.9   98.98  4838.4   97.65
  4848.4   99.01  4858.4   97.76  4868.4   98.81  4908.4  100.25  4928.4   96.05
  4957.6   95.35  4958.4   95.33    4983   91.48  5006.4   92.64  5019.4   95.13
  5127.8   96.75    5219   95.84  5400.4   94.95  5474.2   96.93  5828.8   95.79
  5915.2    94.4  5925.5   94.65  5931.7    96.3  5946.1   96.99  5997.5   97.99
  6007.8   100.8  6014.9  104.14  6020.1  104.92    6049  113.94  6079.9  114.96
#Mann= 7 ,-1 , 0
  4648.3     .11       0  4957.6    .125       0  4958.4     .09       0
  5019.4    .125       0  5127.8     .11       0    5219     .15       0
  5828.8    .125       0
Bank Sta=4958.4,5019.4
XS Rating Curve= 0 ,0
Exp/Cntr=0.3,0.1

Type RM Length L Ch R = 1 ,12500   ,407,407,407
BEGIN DESCRIPTION:
BENS BRANCH TRIBUTARY NO. 1 25.0
END DESCRIPTION:
XS GIS Cut Line= 3
      3909433.08     10037563.15      3908354.91     10037612.51
      3907667.84     10038111.08
#Sta/Elev= 30
  3920.7   98.97  4201.1   96.34  4326.4   96.23  4336.4    95.2  4376.4   96.89
  4466.5   94.64  4566.6   97.12  4794.5   97.71  4886.4   95.64    4907   94.42
    4957   96.33    4977   94.95    4996   91.22  5004.3   91.68  5008.7   90.51
  5033.4   93.32  5090.1    95.2  5412.5   94.57  5483.6   95.45  5498.3   96.71
    5549   95.26  5634.4   94.48  5720.2   96.64  5734.9   95.27  5755.7   98.96
  5770.4  104.68  5799.5  111.27  5835.4  112.29  5845.8  116.12  5848.9  116.12
#Mann= 7 ,-1 , 0
  3920.7    .125       0  4201.1     .11       0  4794.5    .125       0
  4886.4     .11       0    4977     .09       0  5090.1     .15       0
    5549    .125       0
Bank Sta=4977,5090.1
XS Rating Curve= 0 ,0
Exp/Cntr=0.3,0.1

Type RM Length L Ch R = 1 ,12093   ,444,444,444
BEGIN DESCRIPTION:
Mapping XS c5c0aa29
END DESCRIPTION:
XS GIS Cut Line= 4
      3909485.16     10037434.68      3908387.54     10037214.96
      3907694.42     10037327.13      3907506.87     10037441.42
#Sta/Elev= 30
       0   98.92   150.5    96.8     293   96.01   333.8   96.95   527.6    95.3
   588.8   96.73   706.1   97.24   894.7   94.25   945.7      94   960.9   92.93
  1006.8   93.97  1027.3   92.76  1047.7   90.38  1062.9   90.57  1068.1    91.7
  1098.7   92.82  1186.9   93.12  1291.3   92.28  1310.3    93.7  1331.8   92.51
    1372   93.38    1423   92.59  1473.6    93.9  1767.4   92.66  1858.2   92.89
  1887.8   91.99    1895   93.68  2004.9    95.5  2026.7   97.87  2041.2   98.25
#Mann= 10 ,-1 , 0
       0    .125       0   150.5     .15       0   588.8     .11       0
   894.7    .125       0  1027.3     .09       0  1068.1     .15       0
  1186.9     .11       0  1310.3    .125       0  1473.6     .15       0
  1767.4    .125       0
Bank Sta=1027.3,1068.1
XS Rating Curve= 0 ,0
Exp/Cntr=0.3,0.1

Type RM Length L Ch R = 1 ,11649   ,263,263,263
BEGIN DESCRIPTION:
Mapping XS 9d16bacc
END DESCRIPTION:
XS GIS Cut Line= 4
      3909539.89     10036772.25      3909050.53     10036930.81
      3908278.19     10036742.95      3907789.19     10036680.19
#Sta/Elev= 30
       0   99.29    23.2   98.81    65.2   98.02    73.9    98.7   201.8   96.61
     303   97.33   359.5    96.6   538.7   96.75   630.4   95.57   658.7   94.41
   753.9   94.34     795   93.31   867.1      93   908.2   93.87   919.5    93.4
   928.8   91.92   949.4   90.89   956.1   91.93  1052.3   93.25  1086.4   92.65
  1103.8   93.51  1196.4   92.67  1253.4   93.15  1349.9   95.88  1450.8    97.1
  1518.3   95.22  1581.8   97.49  1672.5   96.73  1773.4   97.23  1800.4    98.1
#Mann= 8 ,-1 , 0
       0    .125       0    23.2     .11       0    65.2    .125       0
   538.7     .11       0   928.8     .06       0   956.1     .11       0
  1349.9     .17       0  1450.8     .15       0
Bank Sta=928.8,956.1
XS Rating Curve= 0 ,0
Exp/Cntr=0.3,0.1

Type RM Length L Ch R = 1 ,11386   ,427,427,427
BEGIN DESCRIPTION:
Mapping XS 9746b04a
END DESCRIPTION:
XS GIS Cut Line= 4
      3909349.74      10036757.6      3908723.48     10036582.29
      3908223.05     10036490.61      3908129.58     10036472.61
#Sta/Elev= 30
       0   98.51    33.1   97.93    40.5    97.1      85   97.25    95.4   97.99
   226.7    96.8   292.7   95.34   339.5   95.32   344.7   94.32   365.4   94.07
   396.6   94.23   452.3   94.07   458.9   94.86   552.3   93.02   559.8   93.78
   583.5   93.79   599.1   92.93   638.5   92.56   656.1   90.32   666.2   90.98
   676.4   92.67   741.4   92.33   839.1   93.53   859.4   94.48   889.9   93.86
     906   94.89  1093.2   96.62  1133.9   97.59  1238.4    96.5  1252.6   98.59
#Mann= 9 ,-1 , 0
       0    .125       0    95.4     .11       0   226.7    .125       0
   292.7     .11       0   365.4    .125       0   396.6     .15       0
   583.5     .11       0   638.5     .06       0   676.4     .11       0
Bank Sta=638.5,676.4
XS Rating Curve= 0 ,0
Exp/Cntr=0.3,0.1

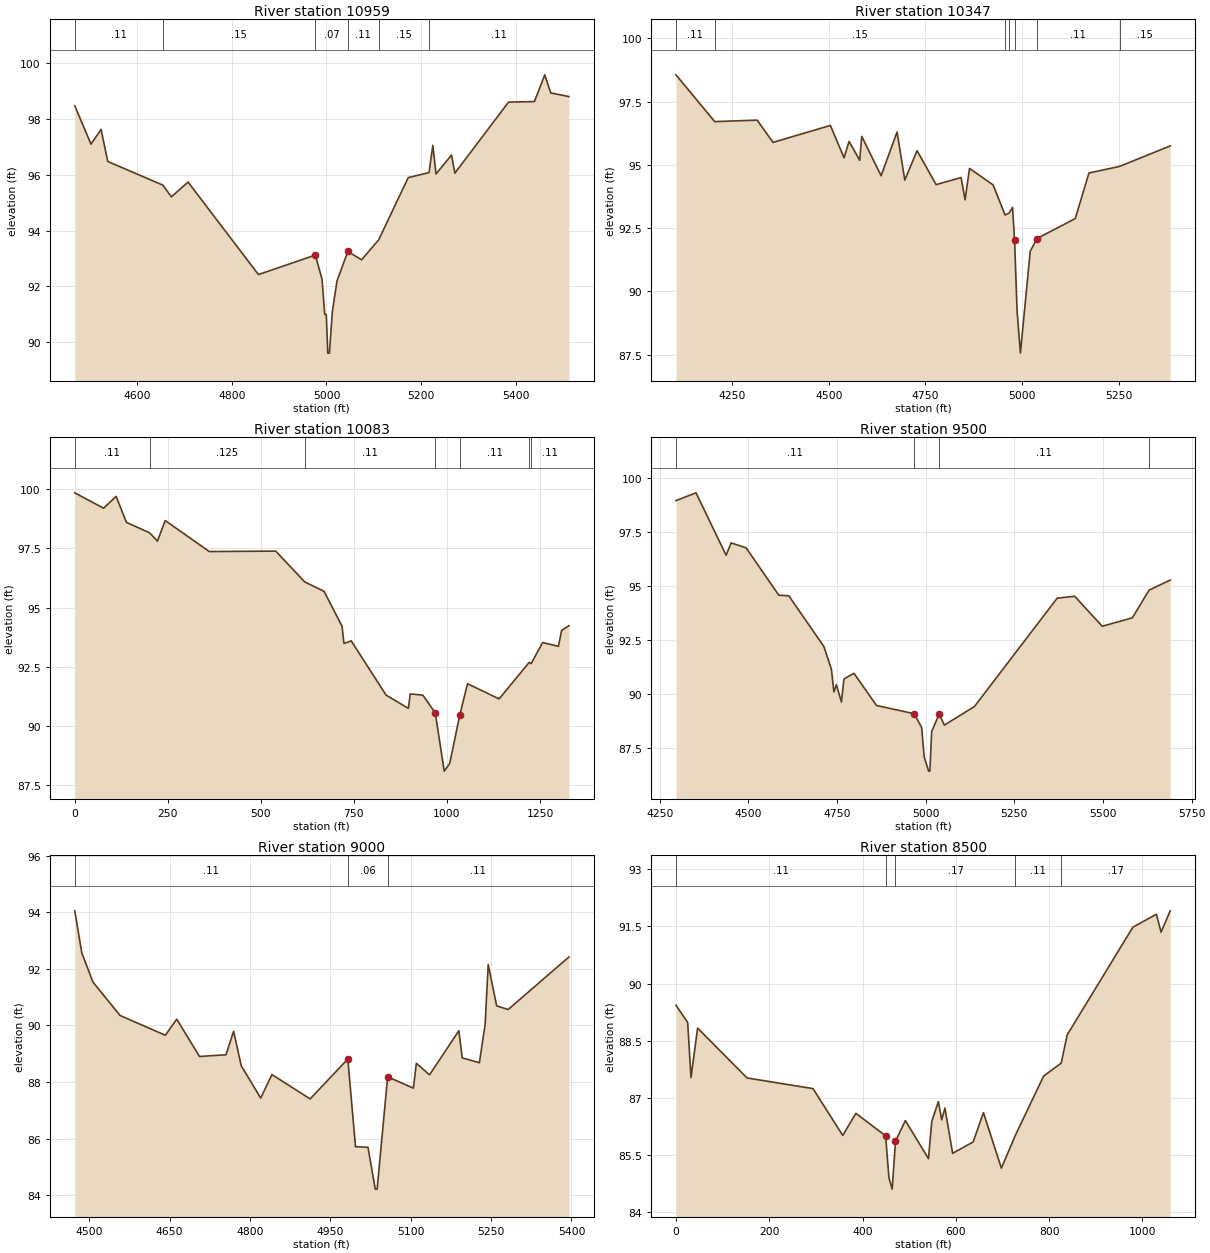
Type RM Length L Ch R = 1 ,10959   ,612,612,612
BEGIN DESCRIPTION:
Mapping XS 7fd9127d
END DESCRIPTION:
XS GIS Cut Line= 3
      3909387.93     10036639.53      3909011.67     10036268.05
      3908541.17     10036058.75
#Sta/Elev= 30
  4468.5   98.48  4502.8    97.1  4524.1   97.63  4538.2   96.48  4654.6   95.63
  4672.5   95.21  4707.8   95.74  4856.4   92.42  4976.6   93.12  4990.7   92.25
  4996.4   90.99  4999.7   90.99  5002.8    89.6  5006.3    89.6  5012.4   91.08
  5022.3   92.19  5045.2   93.25  5074.2   92.95  5110.4   93.67  5172.7    95.9
  5216.6   96.08  5224.7   97.06  5231.3   96.03  5264.1   96.71  5271.2   96.06
  5384.5   98.61  5439.2   98.63  5461.1   99.59  5473.6   98.94  5512.2   98.81
#Mann= 6 ,-1 , 0
  4468.5     .11       0  4654.6     .15       0  4976.6     .07       0
  5045.2     .11       0  5110.4     .15       0  5216.6     .11       0
Bank Sta=4976.6,5045.2
XS Rating Curve= 0 ,0
Exp/Cntr=0.3,0.1

Type RM Length L Ch R = 1 ,10347   ,264,264,264
BEGIN DESCRIPTION:
Mapping XS b5cad84e
END DESCRIPTION:
XS GIS Cut Line= 2
      3909532.89     10036623.88      3909211.18     10035388.28
#Sta/Elev= 30
  4105.4   98.56  4205.6   96.71    4315   96.77  4356.3   95.89  4504.3   96.56
  4539.6   95.28  4552.6   95.93  4580.1   95.18  4585.3   96.13  4635.3   94.57
  4676.6    96.3  4696.5    94.4  4728.3   95.56  4777.5   94.22    4842    94.5
  4852.3   93.62  4863.7   94.86  4924.6   94.21  4955.6   93.02  4966.2    93.1
  4974.9   93.32  4980.1   92.03  4986.6   89.24  4995.2   87.56  5020.6   91.59
  5038.3   92.09    5137   92.88  5172.3   94.68  5251.5   94.94  5382.2   95.75
#Mann= 7 ,-1 , 0
  4105.4     .11       0  4205.6     .15       0  4955.6    .125       0
  4966.2     .11       0  4980.1     .07       0  5038.3     .11       0
  5251.5     .15       0
Bank Sta=4980.1,5038.3
XS Rating Curve= 0 ,0
Exp/Cntr=0.3,0.1

Type RM Length L Ch R = 1 ,10083   ,583,583,583
BEGIN DESCRIPTION:
BENS BRANCH TRIBUTARY NO. 1 20.0
END DESCRIPTION:
XS GIS Cut Line= 3
      3909793.32     10036574.44      3909501.65     10035569.23
       3909406.7     10035302.48
#Sta/Elev= 30
       0   99.85    77.5    99.2   111.1    99.7   138.9    98.6   201.3   98.16
   222.2   97.81     243   98.68   361.6   97.37   539.9   97.39   617.8   96.09
   669.9   95.69   718.1   94.22   723.3   93.49   742.8    93.6   836.5   91.31
   896.3   90.75   901.5   91.36   935.1   91.31   968.6   90.56   992.7    88.1
  1007.4   88.42  1034.3   90.46  1055.3   91.79  1140.2   91.15  1220.9   92.69
  1226.2   92.64  1257.1   93.53  1299.5   93.37  1308.1   94.04  1327.9   94.24
#Mann= 7 ,-1 , 0
       0     .11       0   201.3    .125       0   617.8     .11       0
   968.6     .07       0  1034.3     .11       0  1220.9    .125       0
  1226.2     .11       0
Bank Sta=968.6,1034.3
XS Rating Curve= 0 ,0
Exp/Cntr=0.3,0.1

Type RM Length L Ch R = 1 ,9500    ,500,500,500
BEGIN DESCRIPTION:
BENS BRANCH TRIBUTARY NO. 1 19.0
END DESCRIPTION:
XS GIS Cut Line= 3
      3910317.82     10035611.04      3909818.06     10035114.77
      3909317.65     10034640.43
#Sta/Elev= 30
  4295.7   98.94  4352.2    99.3  4437.1   96.41  4451.2   96.98  4493.6   96.75
  4585.6   94.56  4613.9   94.53  4712.9   92.18    4734   91.13  4741.1   90.08
  4748.2   90.41  4762.3   89.61  4769.4   90.68  4797.7   90.94  4861.3   89.45
  4967.4   89.07  4988.6   88.43  4995.7   87.07  5008.2   86.41  5011.7   86.41
  5016.8   88.24  5038.2   89.06  5052.4   88.54  5137.3    89.4  5370.7   94.42
  5420.1   94.51  5497.8   93.12  5582.7   93.51  5629.8   94.79  5689.5   95.26
#Mann= 4 ,-1 , 0
  4295.7     .11       0  4967.4     .06       0  5038.2     .11       0
  5629.8    .125       0
Bank Sta=4967.4,5038.2
XS Rating Curve= 0 ,0
Exp/Cntr=0.3,0.1

Type RM Length L Ch R = 1 ,9000    ,500,500,500
BEGIN DESCRIPTION:
BENS BRANCH TRIBUTARY NO. 1 18.0
END DESCRIPTION:
XS GIS Cut Line= 3
      3910443.07     10035014.42      3910041.01     10034673.56
      3909671.73     10034532.26
#Sta/Elev= 30
  4472.9   94.05  4486.1   92.56  4506.9   91.53  4557.5   90.35    4642   89.65
  4663.3   90.22  4705.7    88.9  4755.2   88.96  4769.4   89.79  4783.7   88.57
    4820   87.43  4840.9   88.26  4912.3    87.4  4982.6   88.81  4996.9   85.71
  5020.2   85.69  5033.8   84.21  5037.3   84.21  5056.9   88.18    5105   87.78
  5110.5   88.66  5135.1   88.25  5189.8   89.81  5196.1   88.85  5228.2   88.68
  5238.9   90.04  5244.6   92.15  5260.4   90.69  5281.8   90.56  5395.4   92.42
#Mann= 3 , 0 , 0
  4472.9     .11       0  4982.6     .06       0  5056.9     .11       0
Bank Sta=4982.6,5056.9
XS Rating Curve= 0 ,0
Exp/Cntr=0.3,0.1

Type RM Length L Ch R = 1 ,8500    ,431,431,431
BEGIN DESCRIPTION:
BENS BRANCH TRIBUTARY NO. 1 17.0
END DESCRIPTION:
XS GIS Cut Line= 4
      3910751.97     10034692.45      3910711.45     10034652.67
      3910329.54     10034273.08      3909868.44      10034219.3
#Sta/Elev= 30
       0   89.43    25.1   88.98    32.2   87.53    46.4   88.83   152.4   87.52
   293.8   87.24   357.5   86.01   385.7   86.59   449.4      86   456.5    84.9
   463.5    84.6   470.6   85.86   491.8    86.4   541.3    85.4   548.4   86.38
   562.5    86.9   569.6   86.42   576.6   86.73   593.1   85.54   637.2   85.84
   659.1   86.61   697.6   85.15   727.8   86.02   788.2   87.57   825.9   87.91
   838.6   88.65   979.5   91.48  1029.9   91.82  1039.9   91.35  1059.5   91.91
#Mann= 5 ,-1 , 0
       0     .11       0   449.4     .09       0   470.6     .17       0
   727.8     .11       0   825.9     .17       0
Bank Sta=449.4,470.6
XS Rating Curve= 0 ,0
Exp/Cntr=0.3,0.1

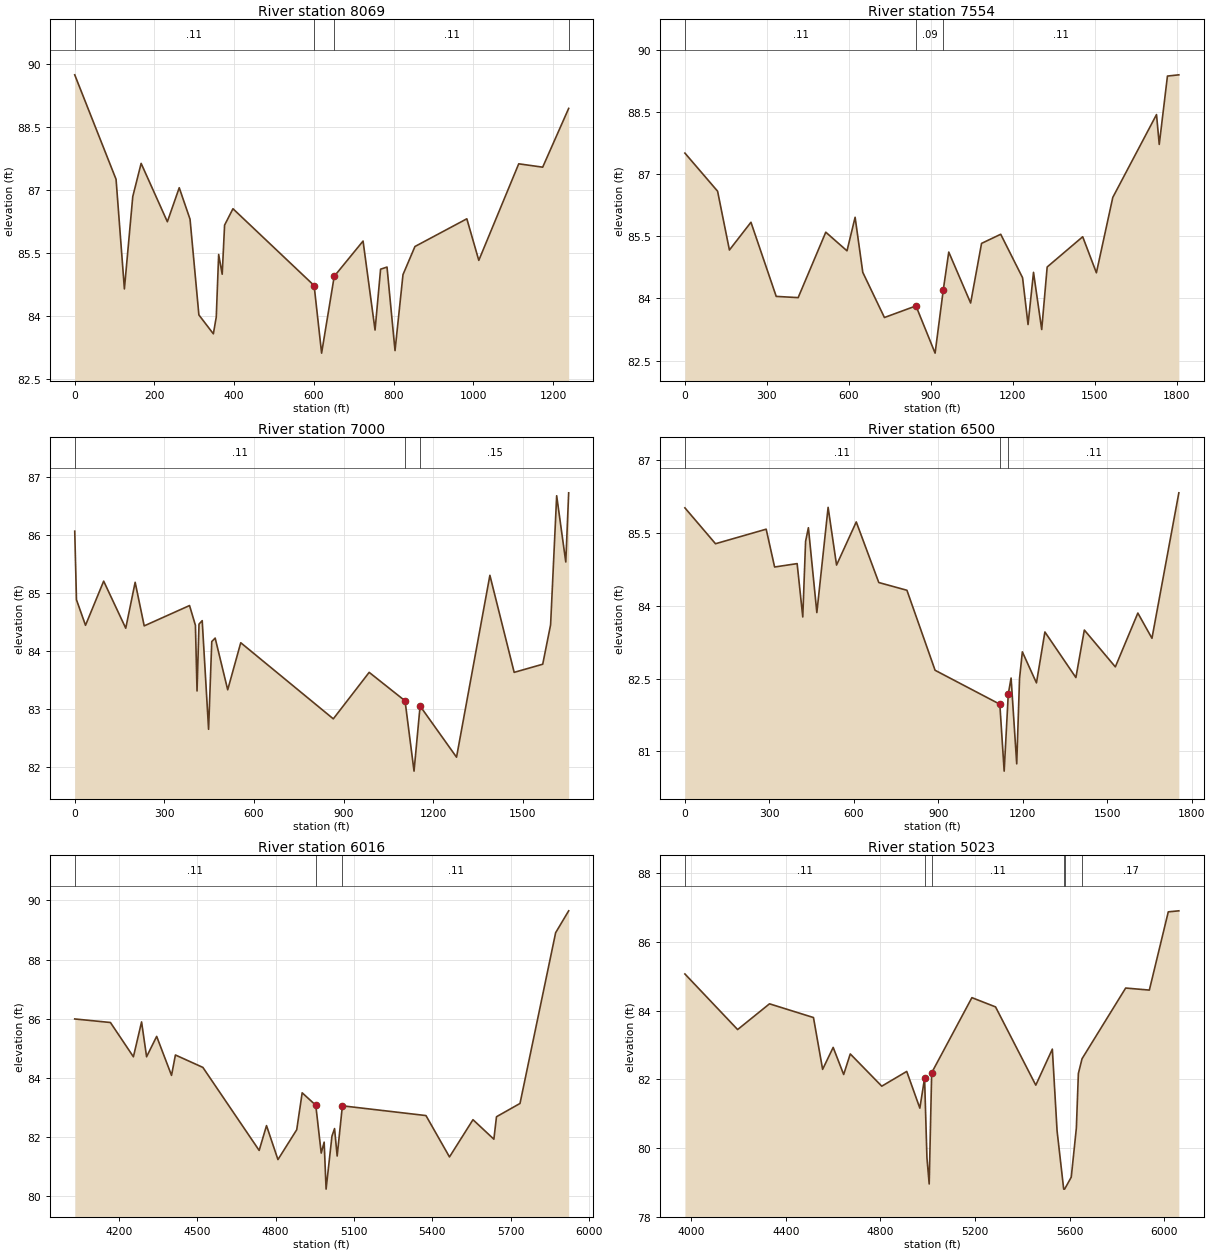
Type RM Length L Ch R = 1 ,8069    ,515,515,515
BEGIN DESCRIPTION:
BENS BRANCH TRIBUTARY NO. 1 16.0
END DESCRIPTION:
XS GIS Cut Line= 4
      3910873.43      10034548.5      3910596.83     10034142.43
      3910539.02     10033971.03      3909972.61     10033941.09
#Sta/Elev= 30
       0   89.75   103.7   87.26   124.6   84.65   145.6   86.85   166.6   87.64
   232.4   86.25   262.2   87.06   289.3   86.31   311.5   84.03   347.8   83.58
   355.1   83.98   361.1   85.47     370      85     376   86.17     397   86.56
   600.6   84.73   619.4   83.12   651.1   84.95   723.4   85.79   753.5   83.67
   767.4   85.12   783.5   85.17   803.6   83.18   823.6   84.99   853.6   85.66
   983.8   86.32  1013.8   85.33    1114   87.63  1174.1   87.55  1239.3   88.95
#Mann= 4 ,-1 , 0
       0     .11       0   600.6     .07       0   651.1     .11       0
  1239.3     .11       0
Bank Sta=600.6,651.1
XS Rating Curve= 0 ,0
Exp/Cntr=0.3,0.1

Type RM Length L Ch R = 1 ,7554    ,554,554,554
BEGIN DESCRIPTION:
BENS BRANCH TRIBUTARY NO. 1 15.0
END DESCRIPTION:
XS GIS Cut Line= 3
      3911381.03     10034394.56      3910921.79     10033737.63
      3909916.19     10033714.96
#Sta/Elev= 30
       0   87.51   119.6   86.59   162.9   85.17   241.7   85.84   334.1   84.05
   414.4   84.02   515.5    85.6   593.1   85.15   622.8   85.96   650.9   84.63
   730.1   83.54   845.5   83.82   915.5   82.68   945.5   84.21   965.5   85.12
  1045.5   83.89  1085.5   85.33  1155.6   85.55  1235.6    84.5  1255.6   83.37
  1275.6   84.63  1305.6   83.25  1325.6   84.76  1455.6   85.49  1505.7   84.62
  1565.7   86.44  1725.7   88.44  1735.7   87.72  1765.7   89.37  1807.4    89.4
#Mann= 3 , 0 , 0
       0     .11       0   845.5     .09       0   945.5     .11       0
Bank Sta=845.5,945.5
XS Rating Curve= 0 ,0
Exp/Cntr=0.3,0.1

Type RM Length L Ch R = 1 ,7000    ,500,500,500
BEGIN DESCRIPTION:
BENS BRANCH TRIBUTARY NO. 1 14.0
END DESCRIPTION:
XS GIS Cut Line= 4
      3911577.94     10033143.93      3911046.86     10033341.27
      3910485.17     10033363.54      3909968.27     10033270.51
#Sta/Elev= 30
       0   86.06     5.8   84.88    36.1   84.44    96.9    85.2   170.8   84.39
   202.3   85.18   232.6   84.43   384.4   84.78   404.1   84.44   409.5   83.31
   416.1   84.46   426.8   84.52   448.2   82.65   458.8   84.16   470.2   84.22
   512.2   83.33   555.9   84.14   865.8   82.83   985.9   83.63    1106   83.14
  1136.1   81.93  1156.4   83.05  1278.4   82.17  1390.1    85.3  1471.4   83.63
    1567   83.77  1593.4   84.45  1613.7   86.67  1644.2   85.53  1653.9   86.72
#Mann= 3 , 0 , 0
       0     .11       0    1106     .07       0  1156.4     .15       0
Bank Sta=1106,1156.4
XS Rating Curve= 0 ,0
Exp/Cntr=0.3,0.1

Type RM Length L Ch R = 1 ,6500    ,484,484,484
BEGIN DESCRIPTION:
BENS BRANCH TRIBUTARY NO. 1 13.5
END DESCRIPTION:
XS GIS Cut Line= 3
      3911646.52     10032860.95      3910511.97     10032864.26
      3909891.88     10032839.96
#Sta/Elev= 30
       0   86.02   108.7   85.28   288.7   85.58   318.7    84.8   398.7   84.87
   418.7   83.77   428.7   85.33   438.7   85.61   468.7   83.86   508.7   86.03
   538.7   84.84   608.7   85.73   688.7   84.48   788.7   84.32   888.7   82.67
  1118.7   81.97  1134.1   80.59  1148.7   82.18  1158.7   82.51  1178.7   80.74
  1188.7    82.5  1198.7   83.05  1248.8   82.41  1278.8   83.46  1388.9   82.52
  1418.9    83.5    1529   82.74    1609   83.85  1659.1   83.33  1754.6   86.33
#Mann= 3 , 0 , 0
       0     .11       0  1118.7     .07       0  1148.7     .11       0
Bank Sta=1118.7,1148.7
XS Rating Curve= 0 ,0
Exp/Cntr=0.3,0.1

Type RM Length L Ch R = 1 ,6016    ,993,993,993
BEGIN DESCRIPTION:
BENS BRANCH TRIBUTARY NO. 1 13.0
END DESCRIPTION:
XS GIS Cut Line= 3
      3911463.39      10032654.9      3910533.73     10032380.91
      3909611.51     10032407.47
#Sta/Elev= 30
  4030.8   85.99  4167.5   85.87  4255.5   84.71  4286.8   85.89    4306   84.71
  4344.6    85.4  4401.5   84.08  4416.4   84.77  4521.6   84.35  4737.2   81.54
  4765.3   82.38  4809.1   81.23    4881   82.24  4901.9   83.49    4954   83.07
  4974.8   81.45  4986.1   81.82  4993.5   80.23  5015.9   82.02  5025.9   82.28
  5035.9   81.35  5055.9   83.05    5376   82.72  5466.1   81.32  5556.1   82.58
  5636.1   81.92  5646.1   82.68  5736.2   83.13  5872.7   88.91  5922.6   89.65
#Mann= 3 , 0 , 0
  4030.8     .11       0    4954     .06       0  5055.9     .11       0
Bank Sta=4954,5055.9
XS Rating Curve= 0 ,0
Exp/Cntr=0.3,0.1

Type RM Length L Ch R = 1 ,5023    ,481,481,481
BEGIN DESCRIPTION:
BENS BRANCH TRIBUTARY NO. 1 12.0
END DESCRIPTION:
XS GIS Cut Line= 3
      3911836.34     10032123.82       3910983.9     10031688.05
      3909853.15     10031717.41
#Sta/Elev= 30
  3973.2   85.07  4196.1   83.45  4330.9    84.2  4516.8    83.8  4555.5   82.29
  4600.1   82.93  4644.5   82.14  4672.4   82.74  4805.6    81.8  4911.1   82.23
  4966.6   81.16  4986.6   82.03  4996.6   79.71  5006.1   78.95  5016.6   82.19
  5186.7   84.38  5286.7   84.11  5456.8   81.83  5526.8   82.88  5546.8    80.5
  5574.8    78.8  5578.8    78.8  5606.8   79.15  5628.4   80.58  5636.9   82.17
  5652.4    82.6  5836.9   84.66    5937    84.6    6017   86.88  6061.7   86.91
#Mann= 6 ,-1 , 0
  3973.2     .11       0  4986.6     .06       0  5016.6     .11       0
  5574.8     .08       0  5578.8     .11       0  5652.4     .17       0
Bank Sta=4986.6,5016.6
XS Rating Curve= 0 ,0
Exp/Cntr=0.3,0.1

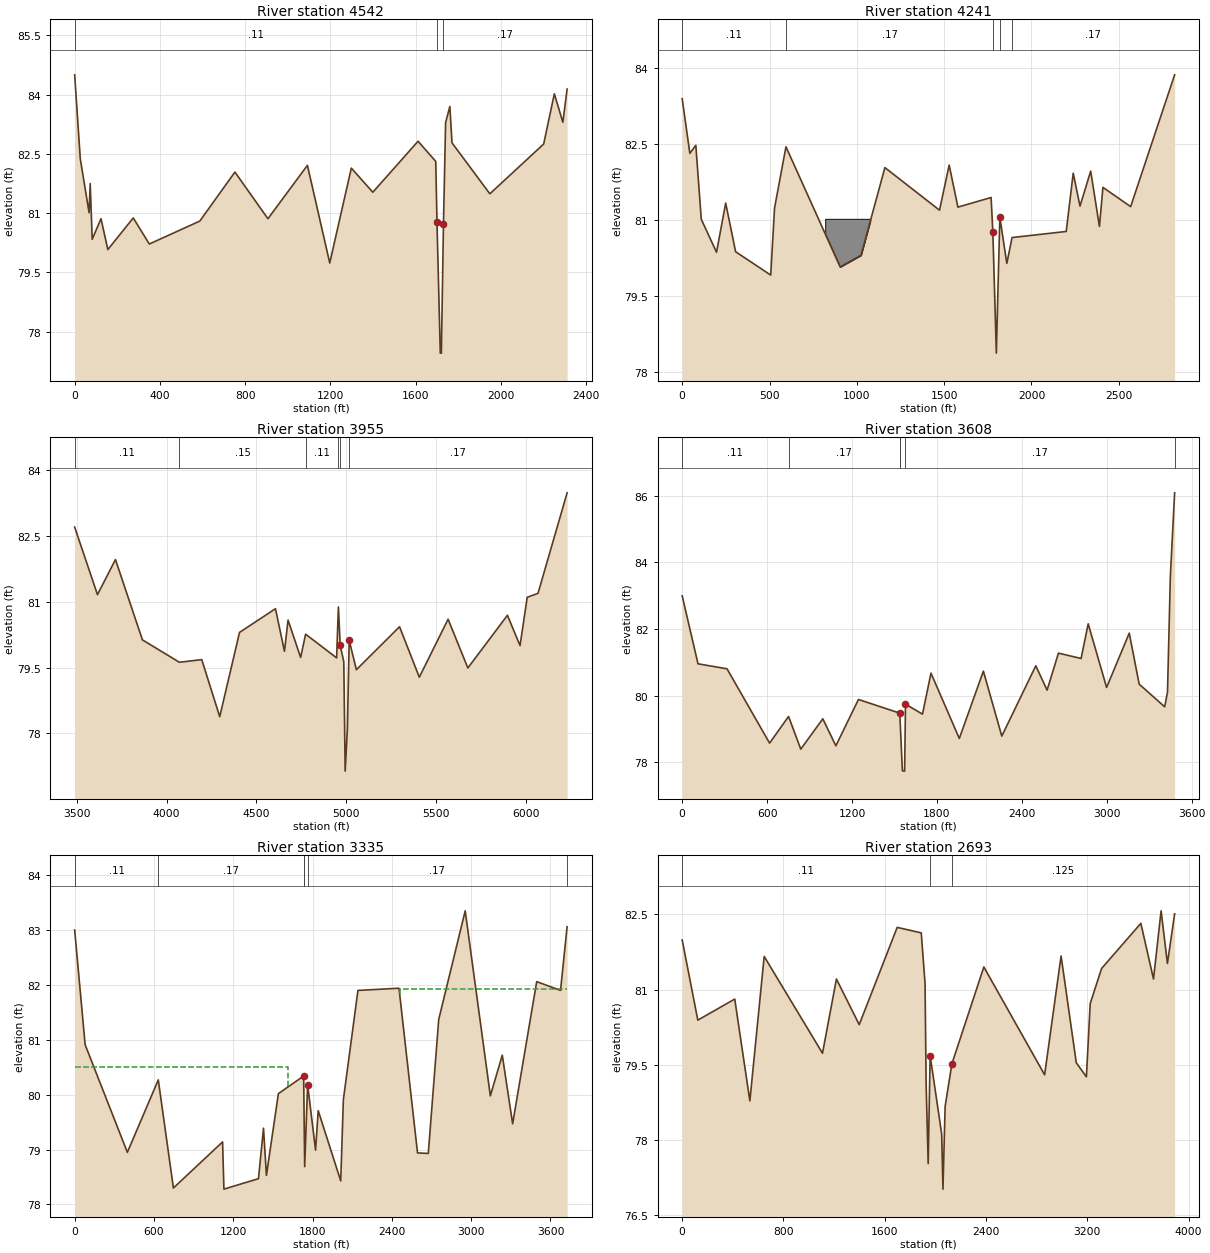
Type RM Length L Ch R = 1 ,4542    ,301,301,301
BEGIN DESCRIPTION:
BENS BRANCH TRIBUTARY NO. 1 11.0
END DESCRIPTION:
XS GIS Cut Line= 3
       3912617.7     10031622.56      3910952.65     10031210.77
      3910357.95     10031198.88
#Sta/Elev= 30
       0    84.5    26.3   82.38    67.7   81.01    72.9   81.75    82.3   80.34
   123.5   80.86   155.7   80.08   274.9   80.88   350.1   80.22     587    80.8
   751.8   82.04   906.6   80.86  1091.8   82.21  1196.6   79.74  1297.8   82.14
  1398.6   81.53  1610.9   82.82  1693.8   82.31  1699.6   80.77  1715.1   77.46
  1720.1   77.46    1730   80.72    1740   83.29    1760    83.7    1770   82.78
  1947.6   81.49  2200.1   82.75  2250.1   84.02  2290.1    83.3    2310   84.14
#Mann= 3 , 0 , 0
       0     .11       0  1699.6     .06       0    1730     .17       0
Bank Sta=1699.6,1730
XS Rating Curve= 0 ,0
Exp/Cntr=0.3,0.1

Type RM Length L Ch R = 1 ,4241    ,286,286,286
BEGIN DESCRIPTION:
Mapping XS 2c7e8904
END DESCRIPTION:
XS GIS Cut Line= 4
      3912596.43     10031519.82      3911520.72     10030932.19
      3910319.15     10030902.46      3909979.72     10031101.94
#Sta/Elev= 30
       0    83.4    43.9   82.32    78.1   82.48   109.4   81.02   196.7   80.37
   249.1   81.34     306   80.38   506.9   79.92   528.8   81.24   594.2   82.45
   904.5   80.08  1023.9   80.31  1160.7   82.04  1473.4    81.2  1528.7   82.09
  1578.7   81.26  1768.8   81.45  1778.8   80.76  1798.8   78.38  1818.8   81.06
  1858.8   80.15  1888.8   80.66  2198.9   80.78  2238.9   81.93  2277.8   81.28
    2339   81.97    2389   80.88    2409   81.65  2567.8   81.27  2819.6   83.87
#Mann= 5 ,-1 , 0
       0     .11       0   594.2     .17       0  1778.8     .06       0
  1818.8     .11       0  1888.8     .17       0
#XS Ineff= 2 , 0
          595.18   82.42
Permanent Ineff=
       F       F
#Block Obstruct= 1 ,-1
  818.81 1076.83   81.03
Bank Sta=1778.8,1818.8
XS Rating Curve= 0 ,0
Exp/Cntr=0.3,0.1

Type RM Length L Ch R = 1 ,3955    ,347,347,347
BEGIN DESCRIPTION:
BENS BRANCH TRIBUTARY NO. 1 9.0
END DESCRIPTION:
XS GIS Cut Line= 3
      3912474.74     10030662.72      3910964.04     10030632.87
      3909736.01     10030667.06
#Sta/Elev= 30
    3489    82.7  3615.9   81.16  3715.9   81.96    3866   80.13  4071.6   79.62
    4196   79.68    4296   78.38  4406.1    80.3  4606.1   80.84  4656.1   79.87
  4676.1   80.58  4746.1   79.73  4773.8   80.26  4946.2   79.72  4956.2   80.88
  4966.2   80.01  4986.2   79.63  4993.8   77.14  5006.2   78.11  5016.2   80.12
  5056.2   79.45  5296.3   80.43  5406.3   79.28  5566.4    80.6  5676.4   79.49
  5896.5   80.69  5966.6      80  6006.6    81.1  6066.6   81.19  6228.5   83.48
#Mann= 6 ,-1 , 0
    3489     .11       0  4071.6     .15       0  4773.8     .11       0
  4956.2     .12       0  4966.2     .09       0  5016.2     .17       0
Bank Sta=4966.2,5016.2
XS Rating Curve= 0 ,0
Exp/Cntr=0.3,0.1

Type RM Length L Ch R = 1 ,3608    ,273,273,273
BEGIN DESCRIPTION:
BENS BRANCH TRIBUTARY NO. 1 8.0
END DESCRIPTION:
XS GIS Cut Line= 3
      3912506.88     10030632.79      3910986.43     10030286.51
      3909067.51     10030211.21
#Sta/Elev= 30
       0      83   111.8   80.96   316.9   80.81   617.6   78.58   751.8   79.38
   837.9    78.4   993.8   79.31  1086.1    78.5  1245.6   79.89  1537.4   79.48
  1556.1   77.75  1571.8   77.74    1578   79.75  1698.1   79.45  1758.1   80.68
  1958.3   78.72  2128.4   80.74  2258.5   78.79  2498.7    80.9  2578.7   80.17
  2658.8   81.28  2818.9   81.12    2869   82.16  2999.1   80.25  3159.2   81.88
  3229.2   80.35  3409.4   79.67  3429.4   80.11  3449.4   83.57  3479.8   86.09
#Mann= 6 ,-1 , 0
       0     .11       0   751.8     .17       0  1537.4     .17       0
  1537.4     .09       0    1578     .17       0  3479.8     .17       0
Bank Sta=1537.4,1578
XS Rating Curve= 0 ,0
Exp/Cntr=0.3,0.1

Type RM Length L Ch R = 1 ,3335    ,642,642,642
BEGIN DESCRIPTION:
BENS BRANCH TRIBUTARY NO. 1 7.0
END DESCRIPTION:
XS GIS Cut Line= 4
      3912503.24     10030627.61      3912076.27     10030126.52
      3910997.18     10030013.66      3909018.18     10029890.72
#Sta/Elev= 30
       0      83    79.3   80.91   398.8   78.95   632.7   80.27   747.2    78.3
  1119.2   79.14  1129.3   78.28  1390.7   78.47  1428.8   79.39    1451   78.53
  1541.5   80.02  1732.6   80.34  1740.4   78.69  1762.7   80.18  1822.8   78.99
  1842.8   79.71  2013.1   78.43  2033.2   79.91  2143.4    81.9    2454   81.94
  2594.3   78.94  2675.7   78.93  2754.6   81.37    2955   83.35  3145.3   79.98
  3235.5   80.72  3313.9   79.47    3496   82.06  3676.3    81.9  3726.1   83.06
#Mann= 6 ,-1 , 0
       0     .11       0   632.7     .17       0  1732.6     .12       0
  1732.6     .09       0  1762.7     .17       0  3726.1     .17       0
#XS Ineff= 2 , 0
         1616.97    80.5 2458.72           81.92
Permanent Ineff=
       F       F
Bank Sta=1732.6,1762.7
XS Rating Curve= 0 ,0
Exp/Cntr=0.3,0.1

Type RM Length L Ch R = 1 ,2693    ,706,706,706
BEGIN DESCRIPTION:
BENS BRANCH TRIBUTARY NO. 1 6.0
END DESCRIPTION:
XS GIS Cut Line= 5
      3912947.96     10029541.89      3912292.85     10029386.07
       3911035.9     10029374.28      3910633.33     10029433.94
      3909079.11     10029420.75
#Sta/Elev= 30
       0   81.99   123.5   80.39   415.2   80.81   534.6   78.78   647.7   81.66
  1108.4   79.73  1218.4   81.21  1398.4    80.3  1698.4   82.24  1888.4   82.13
  1918.4   81.12  1926.9   79.11  1943.1   77.53  1958.7   79.68  2049.7   78.12
  2059.8   77.02    2077   78.67  2130.6   79.52  2382.8   81.45  2862.9    79.3
  2992.9   81.67  3112.9   79.54  3192.9   79.26  3222.9   80.72  3312.9   81.42
  3622.9   82.32  3722.9   81.21  3782.9   82.57  3832.9   81.52  3889.8   82.51
#Mann= 3 , 0 , 0
       0     .11       0  1958.7     .07       0  2130.6    .125       0
Bank Sta=1958.7,2130.6
XS Rating Curve= 0 ,0
Exp/Cntr=0.3,0.1

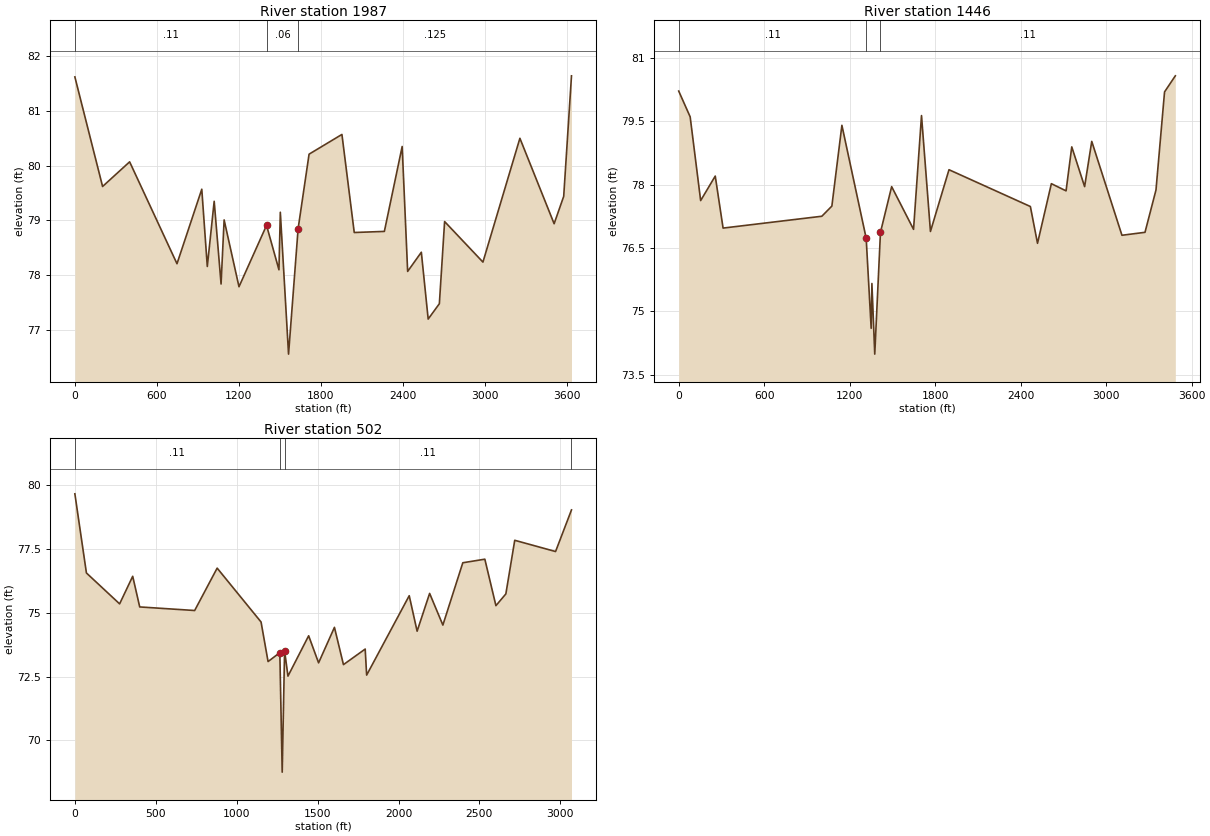
Type RM Length L Ch R = 1 ,1987    ,541,541,541
BEGIN DESCRIPTION:
BENS BRANCH TRIBUTARY NO. 1 4.0
END DESCRIPTION:
XS GIS Cut Line= 4
      3912728.98     10028918.71      3911224.16     10028720.05
      3911056.62     10028731.06      3909109.18     10028860.63
#Sta/Elev= 30
       0   81.62   202.9   79.62   400.9   80.07   747.6   78.21   929.1   79.57
   969.5   78.16  1019.9   79.35  1070.3   77.84  1092.7   79.01  1201.5   77.79
  1403.2   78.91    1494    78.1  1504.1   79.15  1564.3   76.56  1634.4   78.85
  1714.6   80.21  1955.1   80.57  2045.3   78.78  2265.8    78.8  2396.1   80.35
  2436.2   78.07  2536.4   78.42  2586.5    77.2  2668.4   77.48  2706.8   78.98
  2987.4   78.24    3258    80.5  3508.6   78.94  3578.7   79.44  3635.7   81.64
#Mann= 3 , 0 , 0
       0     .11       0  1403.2     .06       0  1634.4    .125       0
Bank Sta=1403.2,1634.4
XS Rating Curve= 0 ,0
Exp/Cntr=0.3,0.1

Type RM Length L Ch R = 1 ,1446    ,944,944,944
BEGIN DESCRIPTION:
BENS BRANCH TRIBUTARY NO. 1 3.0
END DESCRIPTION:
XS GIS Cut Line= 4
      3912607.86     10028320.64      3911433.24     10028207.69
      3910908.14      10028171.9      3909131.87     10028062.87
#Sta/Elev= 30
       0   80.21    80.4    79.6     154   77.62   256.4    78.2   311.4   76.97
  1004.6   77.25  1074.9   77.49  1145.3    79.4  1315.7   76.73  1350.8    74.6
  1355.9   75.66  1375.9   73.99    1416   76.87  1494.5   77.95  1648.2   76.94
    1704   79.63  1766.8   76.89    1897   78.35  2468.1   77.48  2518.2   76.61
  2615.5   78.02  2718.6   77.85  2758.6   78.89  2848.8   77.95  2898.9   79.02
  3110.8    76.8  3272.6   76.87  3349.7   77.87  3409.8   80.19  3485.5   80.57
#Mann= 3 , 0 , 0
       0     .11       0  1315.7     .06       0    1416     .11       0
Bank Sta=1315.7,1416
XS Rating Curve= 0 ,0
Exp/Cntr=0.3,0.1

Type RM Length L Ch R = 1 ,502     ,0,0,0
BEGIN DESCRIPTION:
BENS BRANCH TRIBUTARY NO. 1 1.0
END DESCRIPTION:
XS GIS Cut Line= 4
      3912403.82     10027951.78      3911336.48     10027350.18
      3911259.42     10027294.66      3909550.74     10027672.29
#Sta/Elev= 30
       0   79.66    71.4   76.56   276.5   75.35   357.4   76.43   400.7   75.23
   740.3   75.09   879.3   76.75  1150.6   74.64  1193.9   73.09  1266.6   73.44
  1281.3   68.76    1296   73.51  1316.9   72.52  1444.7    74.1  1506.1   73.04
  1604.1   74.43  1659.8   72.97  1794.1   73.58  1803.1   72.56  2066.2   75.67
    2115   74.28  2192.3   75.76  2274.2   74.52  2397.4   76.96  2533.5    77.1
    2602   75.28  2663.4   75.74  2718.3   77.84  2970.6    77.4    3069   79.03
#Mann= 4 ,-1 , 0
       0     .11       0  1266.6     .06       0    1296     .11       0
    3069     .17       0
Bank Sta=1266.6,1296
XS Rating Curve= 0 ,0
Exp/Cntr=0.3,0.1

Chan Stop Cuts=-1
Use User Specified Reach Order=0
Composite Channel Slope=5