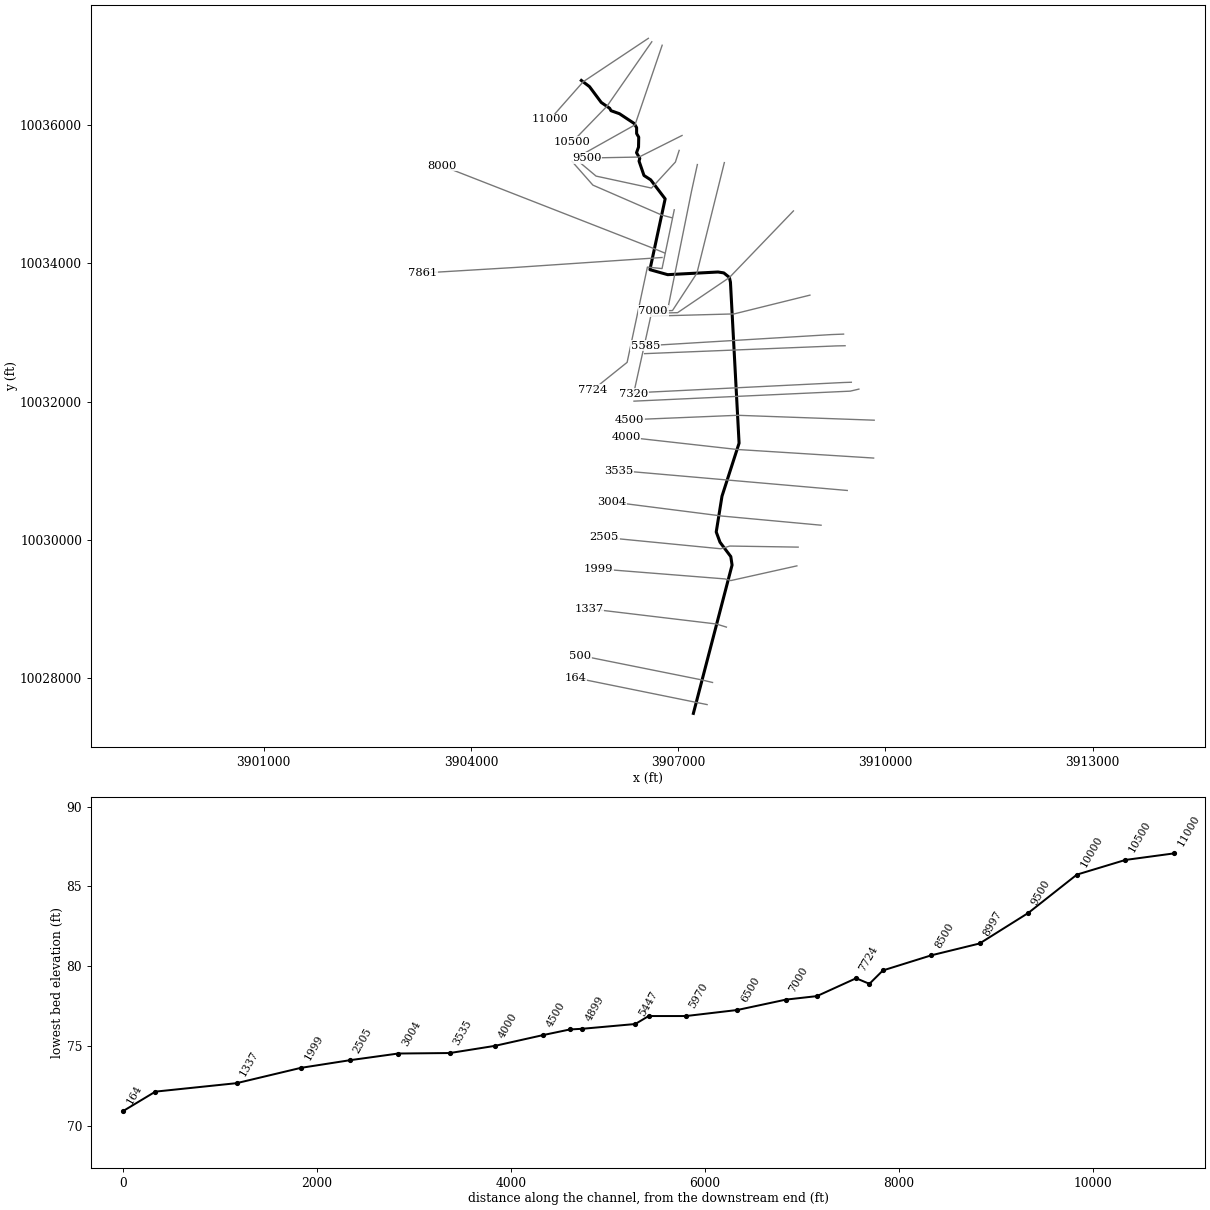
--- BENS BRANCH TRIBUTARY NO 2.prj (project) ---

Proj Title=BENS BRANCH TRIBUTARY NO 2 Base Level Engineering
Current Plan=p01
Default Exp/Contr=0.3,0.1
English Units
Geom File=g01
Flow File=f01
Plan File=p01
Y Axis Title=Elevation
X Axis Title(PF)=Main Channel Distance
X Axis Title(XS)=Station
BEGIN DESCRIPTION:
BENS BRANCH TRIBUTARY NO 2
END DESCRIPTION:
DSS Export Rating Curves= 0
DSS Export Rating Curve Sorted= 0
DSS Export Volume Flow Curves= 0
DXF OffsetX= 0
DXF OffsetY= 0
DXF ScaleX= 1
DXF ScaleY= 10

--- BENS BRANCH TRIBUTARY NO 2.p01 (plan) ---

Plan Title=Multiple Run
Short Identifier=Multiple
Geom File=g01
Flow File=f01
Subcritical Flow
K Sum by GR= 0
Std Step Tol= 0.01
Critical Tol= 0.01
Num of Std Step Trials= 20
Max Error Tol= 0.3
Flow Tol Ratio= 0.001
Split Flow NTrial= 30
Split Flow Tol= 0.02
Split Flow Ratio= 0.02
Log Output Level= 0
Friction Slope Method= 1
Unsteady Friction Slope Method= 2
Unsteady Bridges Friction Slope Method= 1
Parabolic Critical Depth
Global Vel Dist=  1 , 1 , 1
Global Log Level= 0
CheckData=True
Encroach Param= -1, 0, 0, 0
BEGIN DESCRIPTION:
Multiple Run
END DESCRIPTION:

--- BENS BRANCH TRIBUTARY NO 2.f01 (steady flow) ---

Flow Title=Multiple
Program Version=4.10
Number of Profiles= 7
Profile Names=10-year,25-year,50-year,1pct_min,100-year,1pct_plu,500-year
River Rch & RM=BENS BRANCH TRIB,Reach-1         ,11000
     653     837    1088     464    1400    4228    2394
River Rch & RM=BENS BRANCH TRIB,Reach-1         ,7320
     867    1131    1489     642    1940    5859    3397
Boundary for River Rch & Prof#=BENS BRANCH TRIB,Reach-1         , 1
Up Type= 0
Dn Type= 3
Dn Slope=0.005
Boundary for River Rch & Prof#=BENS BRANCH TRIB,Reach-1         , 2
Up Type= 0
Dn Type= 3
Dn Slope=0.005
Boundary for River Rch & Prof#=BENS BRANCH TRIB,Reach-1         , 3
Up Type= 0
Dn Type= 3
Dn Slope=0.005
Boundary for River Rch & Prof#=BENS BRANCH TRIB,Reach-1         , 4
Up Type= 0
Dn Type= 3
Dn Slope=0.005
Boundary for River Rch & Prof#=BENS BRANCH TRIB,Reach-1         , 5
Up Type= 0
Dn Type= 3
Dn Slope=0.005
Boundary for River Rch & Prof#=BENS BRANCH TRIB,Reach-1         , 6
Up Type= 0
Dn Type= 3
Dn Slope=0.005
Boundary for River Rch & Prof#=BENS BRANCH TRIB,Reach-1         , 7
Up Type= 0
Dn Type= 3
Dn Slope=0.005
DSS Import GetInterval= 0
DSS Import GetPeak= 0
DSS Import FillOption= 0

--- BENS BRANCH TRIBUTARY NO 2.g01 (geometry) ---

Geom Title=Existing Conditions
Program Version=4.10

River Reach=BENS BRANCH TRIB,Reach-1
Reach XY= 30
       3905598.1     10036651.09      3905715.99     10036561.59
        3905886.     10036332.75      3906008.03     10036247.76
      3906027.67     10036212.89      3906149.71     10036169.29
      3906363.28     10036027.65      3906398.13     10035966.63
      3906398.15     10035881.61      3906428.67     10035829.36
      3906425.75     10035685.74      3906396.88     10035604.58
       3906443.9     10035522.33      3906433.24     10035482.78
      3906504.77     10035274.45      3906602.02      10035211.4
      3906811.17      10034935.9      3906590.73     10033910.15
      3906847.94      10033837.9      3907576.51     10033876.41
      3907659.85     10033863.39      3907740.57     10033798.28
       3907756.2     10033727.97       3907881.2     10031397.24
       3907633.8     10030629.01      3907550.47     10030110.78
      3907605.16     10029962.35      3907761.41     10029754.01
      3907779.64     10029631.62      3907219.74     10027483.18

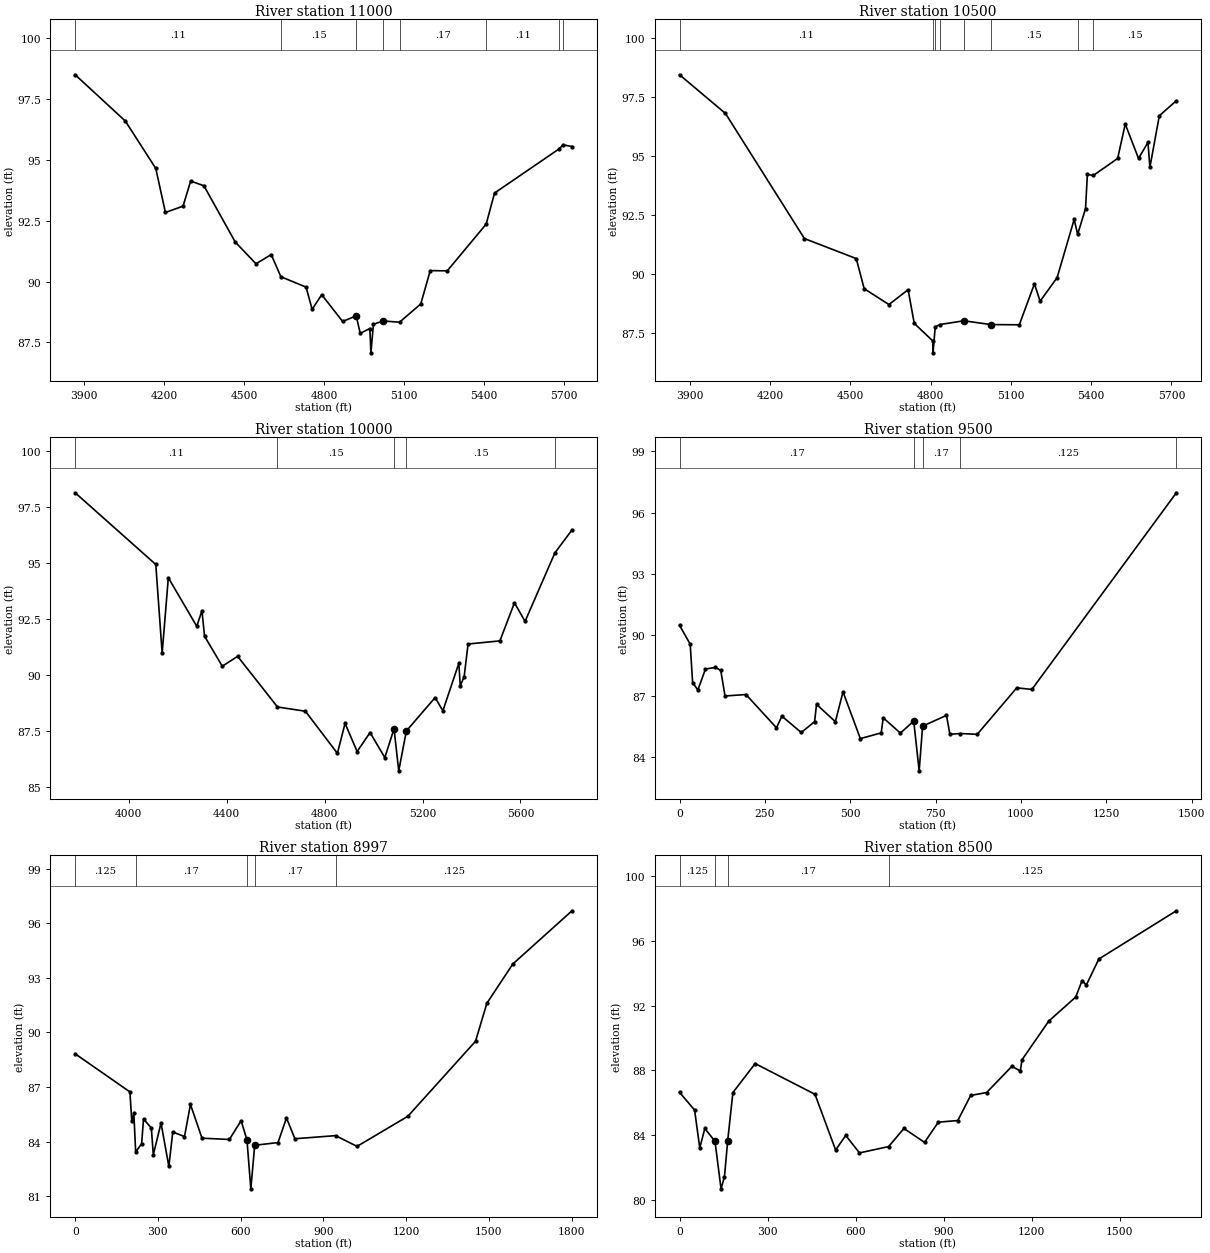
Type RM Length L Ch R = 1 ,11000   ,500,500,500
BEGIN DESCRIPTION:
BENS BRANCH TRIBUTARY NO. 2 22.0
END DESCRIPTION:
XS GIS Cut Line= 3
      3906567.89      10037261.1      3905625.78     10036633.16
      3905142.88     10036086.11
#Sta/Elev= 30
  3867.8    98.5  4055.6    96.6  4169.8   94.65  4205.9   92.84    4272    93.1
  4300.5   94.13  4350.1   93.94  4467.3   91.63  4545.4   90.73  4602.5   91.11
  4638.6    90.2  4733.1   89.77  4755.8   88.86  4791.8   89.46  4869.9   88.36
    4921   88.59    4936   87.87  4972.1   88.07  4976.1   87.07  4985.5   88.24
  5021.2   88.38  5083.5   88.33  5162.9   89.08  5198.5   90.45  5262.1   90.44
    5408   92.36  5439.5   93.64  5680.9   95.45  5696.5   95.62  5729.7   95.55
#Mann= 8 ,-1 , 0
  3867.8     .11       0  4638.6     .15       0    4921     .09       0
  5021.2     .15       0  5083.5     .17       0    5408     .11       0
  5680.9     .15       0  5696.5     .17       0
Bank Sta=4921,5021.2
XS Rating Curve= 0 ,0
Exp/Cntr=0.3,0.1

Type RM Length L Ch R = 1 ,10500   ,500,500,500
BEGIN DESCRIPTION:
BENS BRANCH TRIBUTARY NO. 2 21.0
END DESCRIPTION:
XS GIS Cut Line= 3
      3906617.85     10037211.07       3905968.1     10036276.67
      3905467.85     10035761.07
#Sta/Elev= 30
  3861.9   98.46  4033.4   96.82  4328.5   91.51  4522.2   90.66  4551.9   89.38
  4644.4   88.71    4716   89.34  4738.9   87.91  4808.8   87.16  4809.1   86.66
  4817.3   87.76  4833.7   87.86  4924.6   88.02  5025.3   87.86  5131.5   87.85
  5188.1   89.59  5209.2   88.85  5272.8   89.85  5336.5   92.32  5349.6   91.69
    5379   92.78  5385.9   94.23  5408.6   94.19  5499.1   94.91  5527.4   96.37
    5577   94.91  5612.3   95.59  5619.5   94.53  5654.7   96.72  5718.4   97.36
#Mann= 8 ,-1 , 0
  3861.9     .11       0  4808.8     .12       0  4817.3     .11       0
  4833.7     .15       0  4924.6     .07       0  5025.3     .15       0
  5349.6     .17       0  5408.6     .15       0
Bank Sta=4924.6,5025.3
XS Rating Curve= 0 ,0
Exp/Cntr=0.3,0.1

Type RM Length L Ch R = 1 ,10000   ,500,500,500
BEGIN DESCRIPTION:
BENS BRANCH TRIBUTARY NO. 2 20.0
END DESCRIPTION:
XS GIS Cut Line= 3
      3906767.86     10037161.09      3906374.77     10036007.53
      3905667.85     10035611.07
#Sta/Elev= 30
  3781.3   98.15  4110.5   94.95  4136.5   90.99  4161.7   94.36  4277.9   92.19
    4299   92.89  4309.6   91.75  4382.1   90.41  4444.8   90.85  4607.6   88.59
  4721.6    88.4  4852.3   86.52  4883.6   87.86  4932.9    86.6  4985.7   87.45
    5046   86.33  5083.6   87.62  5102.8   85.74    5134   87.52  5251.4   89.01
  5283.1   88.42  5348.3   90.54  5354.1   89.53    5370   89.94    5386    91.4
  5516.1   91.54  5575.4   93.24  5618.8   92.41  5740.7   95.47  5810.5   96.49
#Mann= 5 ,-1 , 0
  3781.3     .11       0  4607.6     .15       0  5083.6     .09       0
    5134     .15       0  5740.7     .11       0
Bank Sta=5083.6,5134
XS Rating Curve= 0 ,0
Exp/Cntr=0.3,0.1

Type RM Length L Ch R = 1 ,9500    ,503,503,503
BEGIN DESCRIPTION:
BENS BRANCH TRIBUTARY NO. 2 19.0
END DESCRIPTION:
XS GIS Cut Line= 3
      3907055.71     10035853.93      3906433.67      10035541.6
      3905674.66     10035527.25
#Sta/Elev= 30
       0   90.47    31.2   89.55    38.3   87.67    53.6    87.3    75.9   88.33
   105.3   88.41   120.7   88.26   133.2   87.01   194.6   87.08   283.9   85.45
   299.7   86.02   356.5   85.22   395.6   85.75   401.2    86.6   456.4   85.75
   478.8   87.21   529.6   84.92   590.7    85.2   596.6   85.94   646.9   85.19
   685.9   85.78   701.9   83.34   711.9   85.53   781.9   86.06   791.9   85.13
   821.9   85.17   871.9   85.13   987.8   87.41  1031.9   87.33  1455.2   96.97
#Mann= 5 ,-1 , 0
       0     .17       0   685.9     .06       0   711.9     .17       0
   821.9    .125       0  1455.2     .11       0
Bank Sta=685.9,711.9
XS Rating Curve= 0 ,0
Exp/Cntr=0.3,0.1

Type RM Length L Ch R = 1 ,8997    ,497,497,497
BEGIN DESCRIPTION:
BENS BRANCH TRIBUTARY NO. 2 18.0
END DESCRIPTION:
XS GIS Cut Line= 5
      3907013.91      10035637.8      3906959.35     10035468.99
      3906613.19     10035092.29      3905811.25     10035265.64
      3905587.86     10035453.47
#Sta/Elev= 30
       0   88.83   198.4   86.74   205.2   85.12   212.6   85.56   219.3   83.44
   240.9    83.9   247.7   85.25   276.1   84.76   283.2   83.29   311.2   85.03
   339.6   82.65   353.8   84.54   396.3   84.29   417.9   86.05   459.8    84.2
   559.1   84.13   601.6   85.16   622.8   84.11   636.8   81.42   650.9   83.81
   735.4   83.96   766.1   85.31   796.6   84.17   944.3   84.34  1021.9   83.75
    1206    85.4  1451.6   89.52  1492.5    91.6  1586.8   93.76  1801.3   96.68
#Mann= 5 ,-1 , 0
       0    .125       0   219.3     .17       0   622.8     .06       0
   650.9     .17       0   944.3    .125       0
Bank Sta=622.8,650.9
XS Rating Curve= 0 ,0
Exp/Cntr=0.3,0.1

Type RM Length L Ch R = 1 ,8500    ,500,500,500
BEGIN DESCRIPTION:
BENS BRANCH TRIBUTARY NO. 2 17.0
END DESCRIPTION:
XS GIS Cut Line= 4
      3906904.44     10034663.46      3906760.85     10034701.73
      3905765.25     10035134.99      3905461.99     10035479.51
#Sta/Elev= 30
       0   86.64    51.2   85.55    68.9   83.21    86.1   84.41   120.7   83.62
   141.4   80.68     153   81.42   163.9   83.63   181.8   86.63   257.6   88.42
   461.5   86.52   531.8   83.08   566.3   83.98     613    82.9   712.2   83.29
   764.5   84.41   834.8   83.55   881.7    84.8     948    84.9   991.8   86.45
  1046.2   86.63  1132.4   88.25  1161.3   87.96  1166.7   88.65  1257.8   91.04
  1349.8   92.53  1371.6   93.55  1385.9   93.27  1428.6   94.88  1692.7   97.86
#Mann= 4 ,-1 , 0
       0    .125       0   120.7     .09       0   163.9     .17       0
   712.2    .125       0
Bank Sta=120.7,163.9
XS Rating Curve= 0 ,0
Exp/Cntr=0.3,0.1

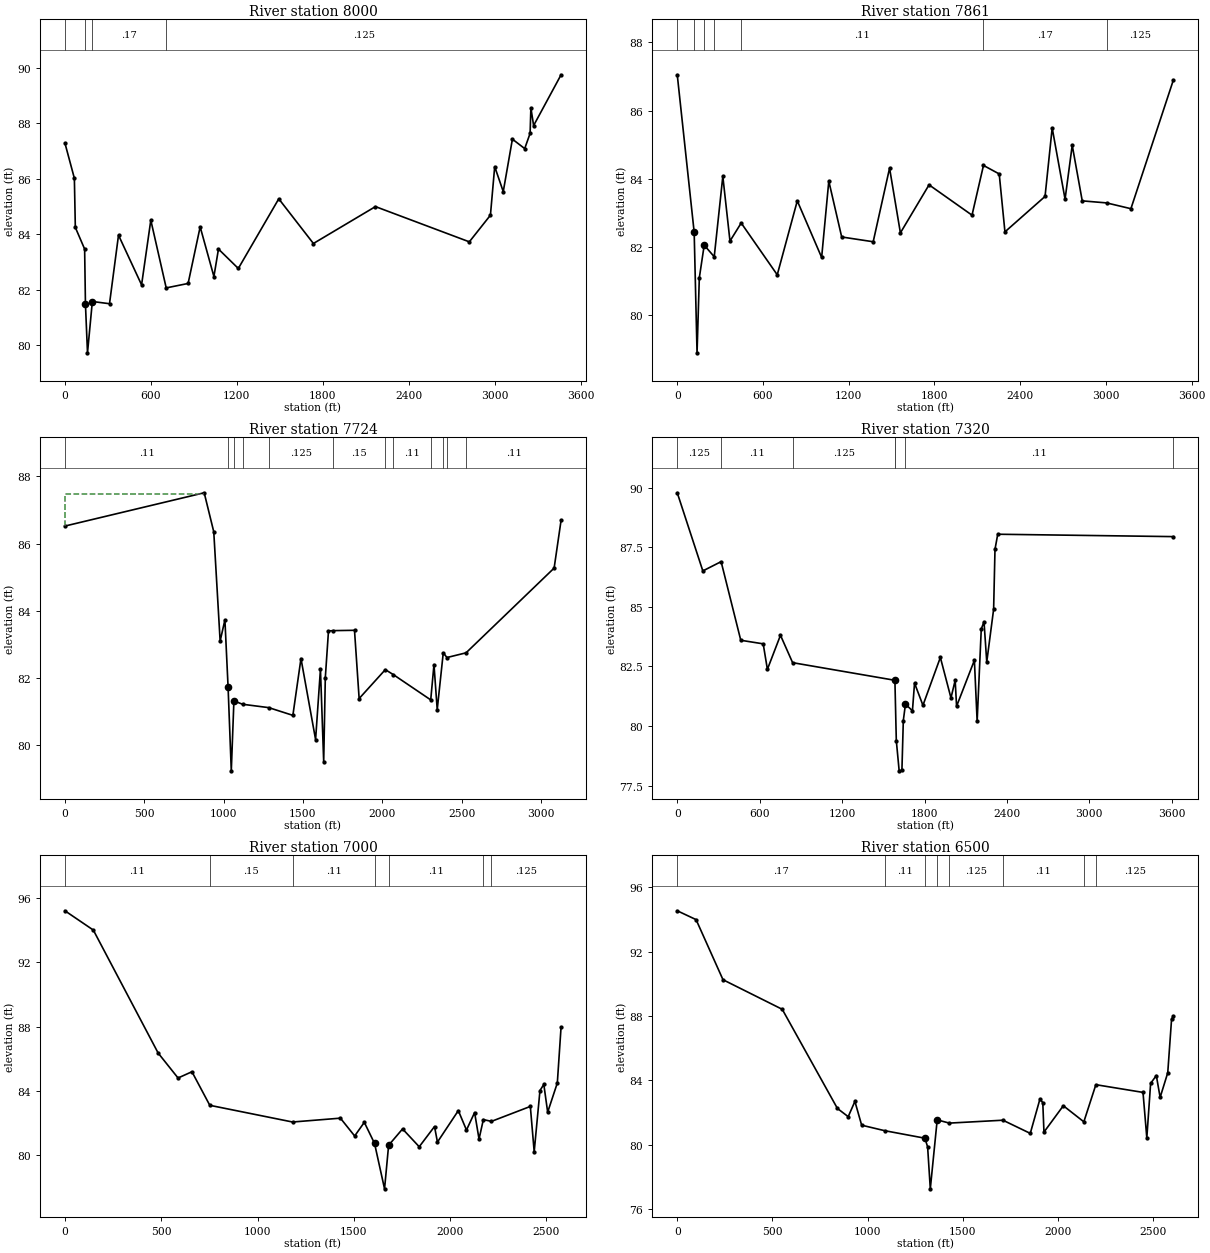
Type RM Length L Ch R = 1 ,8000    ,139,139,139
BEGIN DESCRIPTION:
BENS BRANCH TRIBUTARY NO. 2 16.0
END DESCRIPTION:
XS GIS Cut Line= 3
      3906805.11     10034151.52      3906655.79     10034212.89
      3903580.05     10035415.27
#Sta/Elev= 30
       0   87.29      66   86.02    72.7   84.25   137.6   83.47   143.3   81.48
   157.6   79.73   191.4   81.58   311.2    81.5     374   83.97     535   82.18
   599.4   84.51   706.8   82.07   859.7   82.23   943.8   84.27  1039.7   82.48
  1071.5   83.47    1210   82.77  1492.3   85.28    1734   83.67    2167      85
    2822   83.73  2969.3   84.69  2999.1   86.44  3058.8   85.54  3122.6   87.43
  3208.5   87.09  3246.2   87.64  3251.6   88.56  3270.7   87.92  3462.3   89.75
#Mann= 4 ,-1 , 0
       0    .125       0   143.3     .09       0   191.4     .17       0
   706.8    .125       0
Bank Sta=143.3,191.4
XS Rating Curve= 0 ,0
Exp/Cntr=0.3,0.1

Type RM Length L Ch R = 1 ,7861    ,137,137,137
BEGIN DESCRIPTION:
Mapping XS 18c2bfbe
END DESCRIPTION:
XS GIS Cut Line= 3
      3906766.01     10034086.58       3904636.2     10033942.12
      3903299.04      10033861.8
#Sta/Elev= 30
       0   87.05   118.4   82.43   138.5   78.89   154.4   81.09   188.6   82.05
   258.8   81.71   318.9   84.07     369   82.17   447.5    82.7   699.8   81.18
   840.1   83.35  1010.5   81.69  1060.6   83.93  1150.8   82.29  1371.3   82.15
  1485.9   84.31  1561.7   82.41  1762.2   83.82  2062.9   82.93  2143.1   84.39
  2253.3   84.14  2293.3   82.44    2574   83.48  2623.9   85.49  2714.1    83.4
  2764.2   84.98  2834.3   83.35  3004.6   83.29  3174.9   83.12  3472.4    86.9
#Mann= 7 ,-1 , 0
       0    .125       0   118.4     .09       0   188.6    .125       0
   258.8     .17       0   447.5     .11       0  2143.1     .17       0
  3004.6    .125       0
Bank Sta=118.4,188.6
XS Rating Curve= 0 ,0
Exp/Cntr=0.3,0.1

Type RM Length L Ch R = 1 ,7724    ,404,404,404
BEGIN DESCRIPTION:
Mapping XS 7b29c594
END DESCRIPTION:
XS GIS Cut Line= 5
       3906943.1     10034777.55       3906766.2     10033926.17
      3906554.21     10033947.69      3906260.76     10032567.74
      3905766.38      10032170.5
#Sta/Elev= 30
       0   86.52     878   87.51   938.3   86.35   978.5    83.1  1008.6   83.73
  1028.7   81.72  1048.8   79.24  1065.3   81.32  1120.1   81.22  1285.1   81.12
    1437   80.89  1488.1   82.58  1580.2   80.17  1610.8   82.26  1631.3   79.51
  1641.5   82.01  1661.5    83.4  1692.6   83.41  1825.5   83.42  1854.7   81.39
  2019.8   82.25  2070.9    82.1    2306   81.35  2326.5    82.4  2346.9   81.06
    2385   82.75  2408.3   82.61  2528.7   82.75  3083.9   85.27  3127.7   86.69
#Mann= 12 ,-1 , 0
       0     .11       0  1028.7     .09       0  1065.3     .11       0
  1120.1     .15       0  1285.1    .125       0  1692.6     .15       0
  2019.8    .125       0  2070.9     .11       0    2306     .15       0
    2385     .11       0  2408.3    .125       0  2528.7     .11       0
#XS Ineff= 2 , 0
          879.01   87.47
Permanent Ineff=
       F       F
Bank Sta=1028.7,1065.3
XS Rating Curve= 0 ,0
Exp/Cntr=0.3,0.1

Type RM Length L Ch R = 1 ,7320    ,320,320,320
BEGIN DESCRIPTION:
Mapping XS 688f740d
END DESCRIPTION:
XS GIS Cut Line= 5
      3907277.28     10035432.98      3907191.49     10035040.28
      3906852.66      10033357.8      3906629.37     10033356.25
      3906355.01     10032115.85
#Sta/Elev= 30
       0   89.79   186.2   86.51   319.3    86.9   462.4    83.6   625.6   83.45
   656.2   82.38   751.4   83.81   839.8   82.66  1584.4   81.92  1594.6   79.39
  1615.4   78.12  1635.4   78.14  1645.6   80.23  1661.2   80.92    1712   80.64
  1727.3    81.8  1788.5   80.87  1915.3   82.88  1992.5   81.18  2023.1   81.92
  2033.3   80.83    2163   82.76    2183    80.2    2213   84.07    2233   84.38
    2253   82.69    2303    84.9    2313   87.42    2333   88.05  3611.8   87.95
#Mann= 7 ,-1 , 0
       0    .125       0   319.3     .11       0   839.8    .125       0
  1584.4     .11       0  1584.4     .07       0  1661.2     .11       0
  3611.8    .125       0
Bank Sta=1584.4,1661.2
XS Rating Curve= 0 ,0
Exp/Cntr=0.3,0.1

Type RM Length L Ch R = 1 ,7000    ,500,500,500
BEGIN DESCRIPTION:
BENS BRANCH TRIBUTARY NO. 2 14.0
END DESCRIPTION:
XS GIS Cut Line= 4
      3907667.85     10035461.07      3907270.53     10033859.07
      3906917.08     10033317.95      3906638.33     10033312.03
#Sta/Elev= 30
       0   95.21   147.4   94.01   484.2   86.35   587.3    84.8   659.4   85.19
   752.1    83.1  1181.8   82.06  1430.1    82.3  1504.2   81.19  1554.2   82.04
  1607.3   80.73  1659.3    77.9  1680.4   80.61  1752.8   81.63  1839.3   80.52
  1918.7   81.78  1933.9   80.81  2042.3   82.77  2084.6   81.56  2126.8   82.65
  2149.8      81  2172.2   82.21  2214.3    82.1  2416.1   83.03  2436.1   80.21
  2466.1   84.02  2486.1    84.4  2506.1   82.67  2556.2   84.49  2575.7   87.98
#Mann= 7 ,-1 , 0
       0     .11       0   752.1     .15       0  1181.8     .11       0
  1607.3     .06       0  1680.4     .11       0  2172.2     .15       0
  2214.3    .125       0
Bank Sta=1607.3,1680.4
XS Rating Curve= 0 ,0
Exp/Cntr=0.3,0.1

Type RM Length L Ch R = 1 ,6500    ,530,530,530
BEGIN DESCRIPTION:
BENS BRANCH TRIBUTARY NO. 2 13.0
END DESCRIPTION:
XS GIS Cut Line= 4
      3908667.85     10034761.07      3907741.03     10033796.24
      3906991.24     10033287.59      3906628.08      10033277.6
#Sta/Elev= 30
       0   94.55    98.9      94   240.4   90.26   551.7   88.42   841.7   82.25
   898.3   81.74   933.5   82.69     969   81.21  1089.2   80.87  1301.4    80.4
  1315.6   79.86  1329.7   77.25  1365.9   81.54  1429.8   81.34  1711.3   81.52
    1855    80.7  1905.9   82.84  1920.8   82.61  1926.9   80.78  2028.7   82.42
  2136.5   81.42  2199.7   83.73  2447.4   83.25  2467.4   80.42  2487.4   83.81
  2517.4    84.3  2537.4   82.94  2577.4   84.47  2597.4   87.79  2607.2   88.01
#Mann= 8 ,-1 , 0
       0     .17       0  1089.2     .11       0  1301.4     .06       0
  1365.9     .11       0  1429.8    .125       0  1711.3     .11       0
  2136.5     .15       0  2199.7    .125       0
Bank Sta=1301.4,1365.9
XS Rating Curve= 0 ,0
Exp/Cntr=0.3,0.1

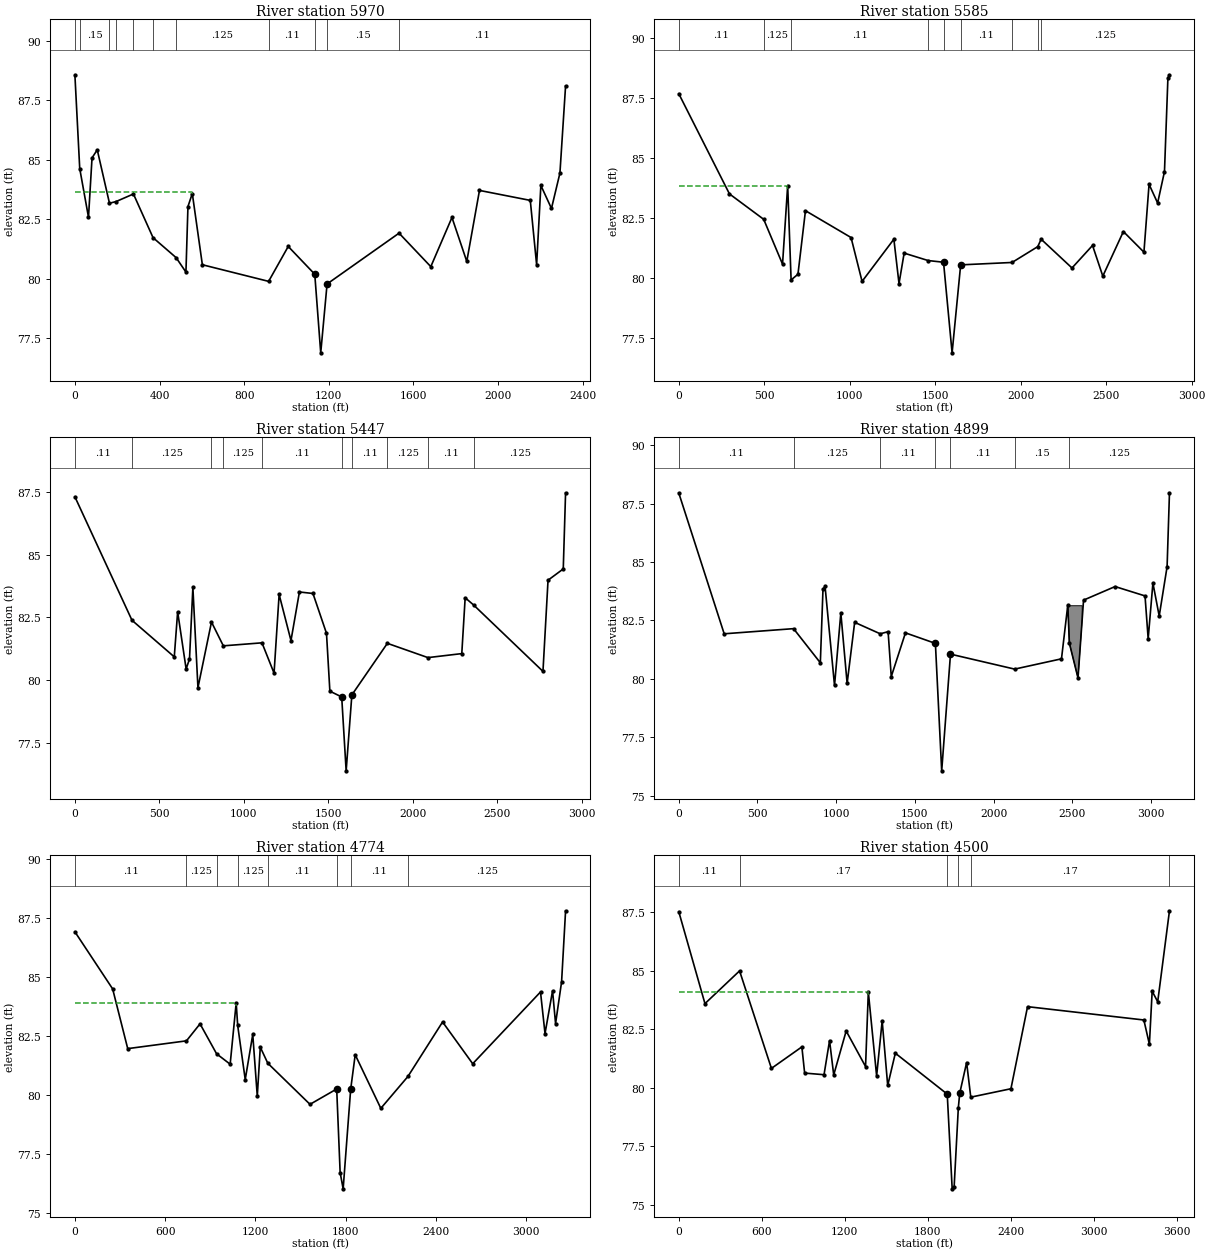
Type RM Length L Ch R = 1 ,5970    ,385,385,385
BEGIN DESCRIPTION:
Mapping XS 81d874c9
END DESCRIPTION:
XS GIS Cut Line= 3
      3908906.45     10033541.22      3907809.16      10033269.4
       3906619.4     10033237.64
#Sta/Elev= 30
       0   88.58    22.9   84.63    64.3   82.58      81   85.08   105.7   85.42
   163.4   83.17   194.3   83.24   276.7   83.56   369.4   81.72   478.3   80.88
   524.8   80.27   534.3   83.03   554.9   83.58   602.4   80.58   915.5   79.88
  1008.2   81.35  1133.6   80.18  1161.8   76.87  1191.8   79.77  1531.9   81.91
    1682    80.5    1782   82.57    1852   80.72    1912   83.71  2152.1   83.29
  2182.1   80.58  2202.1   83.92  2252.2   82.95  2292.2   84.44  2318.9   88.11
#Mann= 11 ,-1 , 0
       0     .11       0    22.9     .15       0   163.4    .125       0
   194.3     .15       0   276.7    .125       0   369.4     .11       0
   478.3    .125       0   915.5     .11       0  1133.6     .06       0
  1191.8     .15       0  1531.9     .11       0
#XS Ineff= 2 , 0
          554.29   83.64
Permanent Ineff=
       F       F
Bank Sta=1133.6,1191.8
XS Rating Curve= 0 ,0
Exp/Cntr=0.3,0.1

Type RM Length L Ch R = 1 ,5585    ,138,138,138
BEGIN DESCRIPTION:
Mapping XS b251691b
END DESCRIPTION:
XS GIS Cut Line= 3
      3909393.87     10032976.91      3909216.19     10032969.96
      3906528.74      10032807.6
#Sta/Elev= 30
       0   87.68   296.4    83.5   496.7   82.44   606.9   80.57     637   83.85
     657   79.91   697.1   80.15     741    82.8  1007.7   81.68  1072.1   79.85
  1258.1   81.61  1288.2   79.76  1318.2   81.03  1458.5   80.72  1548.6   80.65
  1598.7   76.87  1648.8   80.54  1949.4   80.64  2099.6    81.3  2119.7   81.61
    2300   80.41  2420.2   81.35  2480.3   80.07  2600.6   81.93  2720.8   81.07
  2750.8    83.9  2800.9   83.12    2841   84.43    2861   88.32  2870.2   88.47
#Mann= 9 ,-1 , 0
       0     .11       0   496.7    .125       0     657     .11       0
  1458.5    .125       0  1548.6     .09       0  1648.8     .11       0
  1949.4    .125       0  2099.6     .11       0  2119.7    .125       0
#XS Ineff= 2 , 0
          634.75   83.83
Permanent Ineff=
       F       F
Bank Sta=1548.6,1648.8
XS Rating Curve= 0 ,0
Exp/Cntr=0.3,0.1

Type RM Length L Ch R = 1 ,5447    ,548,548,548
BEGIN DESCRIPTION:
Mapping XS 3a864216
END DESCRIPTION:
XS GIS Cut Line= 3
      3909415.56     10032808.49       3909290.6     10032805.84
      3906514.12     10032693.74
#Sta/Elev= 30
       0   87.31   337.9   82.38   588.1   80.92   608.1   82.72   658.2   80.44
   678.2   80.83   698.2   83.69   728.2   79.69   808.3   82.31   878.4   81.36
  1107.1   81.48  1178.6   80.27  1208.6   83.41  1278.7   81.57  1328.7   83.51
  1408.8   83.45  1488.9   81.86  1508.9   79.55  1578.9   79.32  1605.2   76.37
    1639    79.4  1849.1   81.46  2089.3   80.89  2289.5   81.05  2309.5   83.28
  2359.6   82.99  2769.9   80.34  2799.9   83.98    2890   84.43  2903.7   87.47
#Mann= 10 ,-1 , 0
       0     .11       0   337.9    .125       0   808.3     .11       0
   878.4    .125       0  1107.1     .11       0  1578.9     .07       0
    1639     .11       0  1849.1    .125       0  2089.3     .11       0
  2359.6    .125       0
#XS Ineff= 2 , 0
          698.39   83.66
Permanent Ineff=
       F       F
Bank Sta=1578.9,1639
XS Rating Curve= 0 ,0
Exp/Cntr=0.3,0.1

Type RM Length L Ch R = 1 ,4899    ,125,125,125
BEGIN DESCRIPTION:
Mapping XS f0d0b173
END DESCRIPTION:
XS GIS Cut Line= 3
      3909506.03      10032279.5      3909388.82     10032275.64
      3906392.59     10032127.34
#Sta/Elev= 30
       0   87.95   288.4   81.93     729   82.15   899.2   80.69     916   83.83
   929.2   83.96   989.3   79.72  1029.4   82.82  1069.4   79.81  1117.2   82.42
  1279.7   81.93  1329.7   82.02  1349.7    80.1  1439.9   81.97  1630.1   81.52
  1670.1   76.07    1726   81.06  2133.5   80.42  2431.1   80.86  2471.1   83.16
  2481.1   81.53    2536   80.04  2571.2   83.37  2771.5   83.95  2961.7   83.55
  2981.7   81.72  3011.8    84.1  3051.8   82.69  3101.9    84.8    3117   87.96
#Mann= 7 ,-1 , 0
       0     .11       0     729    .125       0  1279.7     .11       0
  1630.1     .07       0    1726     .11       0  2133.5     .15       0
  2481.1    .125       0
#XS Ineff= 2 , 0
          927.18   83.93
Permanent Ineff=
       F       F
#Block Obstruct= 1 ,-1
 2468.46 2562.79   83.13
Bank Sta=1630.1,1726
XS Rating Curve= 0 ,0
Exp/Cntr=0.3,0.1

Type RM Length L Ch R = 1 ,4774    ,274,274,274
BEGIN DESCRIPTION:
Mapping XS b57057f6
END DESCRIPTION:
XS GIS Cut Line= 3
      3909615.23     10032180.11       3909490.9     10032150.67
      3906360.04     10032005.81
#Sta/Elev= 30
       0   86.92   250.9    84.5   351.1   81.97   741.5    82.3   831.6   83.02
   941.7   81.75  1031.8   81.31  1071.8   83.91  1081.8   82.95  1131.9   80.66
  1181.9   82.57    1212   79.96    1232   82.03    1282   81.35  1562.3   79.61
  1739.7   80.26  1762.6   76.72  1782.6   76.03  1832.6   80.25  1862.7   81.71
  2032.9   79.44    2213   80.79  2443.3    83.1  2643.5   81.33    3094   84.37
    3124   82.61  3174.1   84.42  3194.1   83.03  3234.1    84.8  3260.6   87.81
#Mann= 8 ,-1 , 0
       0     .11       0   741.5    .125       0   941.7     .11       0
  1081.8    .125       0    1282     .11       0  1739.7     .07       0
  1832.6     .11       0    2213    .125       0
#XS Ineff= 2 , 0
         1069.67    83.9
Permanent Ineff=
       F       F
Bank Sta=1739.7,1832.6
XS Rating Curve= 0 ,0
Exp/Cntr=0.3,0.1

Type RM Length L Ch R = 1 ,4500    ,500,500,500
BEGIN DESCRIPTION:
BENS BRANCH TRIBUTARY NO. 2 9.0
END DESCRIPTION:
XS GIS Cut Line= 3
      3909836.97     10031729.92      3907861.34     10031800.84
      3906292.85     10031736.07
#Sta/Elev= 30
       0   87.53   189.2    83.6   439.4      85   669.6   80.83   889.7   81.75
   909.7   80.63  1049.8   80.56  1089.8   82.02  1119.8   80.55  1209.9   82.43
    1350   80.91    1370    84.1    1430   80.51  1470.1   82.86  1510.1    80.1
  1565.2   81.48  1940.4   79.73  1976.1   75.68  1990.4   75.78  2020.4   79.13
  2030.4   79.76  2080.5   81.08  2110.5    79.6  2400.8   79.96  2520.9   83.47
  3361.6    82.9  3401.6   81.86  3421.6   84.13  3461.7   83.68  3546.7   87.57
#Mann= 6 ,-1 , 0
       0     .11       0   439.4     .17       0  1940.4     .06       0
  2020.4     .15       0  2110.5     .17       0  3546.7     .15       0
#XS Ineff= 2 , 0
         1369.27    84.1
Permanent Ineff=
       F       F
Bank Sta=1940.4,2030.4
XS Rating Curve= 0 ,0
Exp/Cntr=0.3,0.1

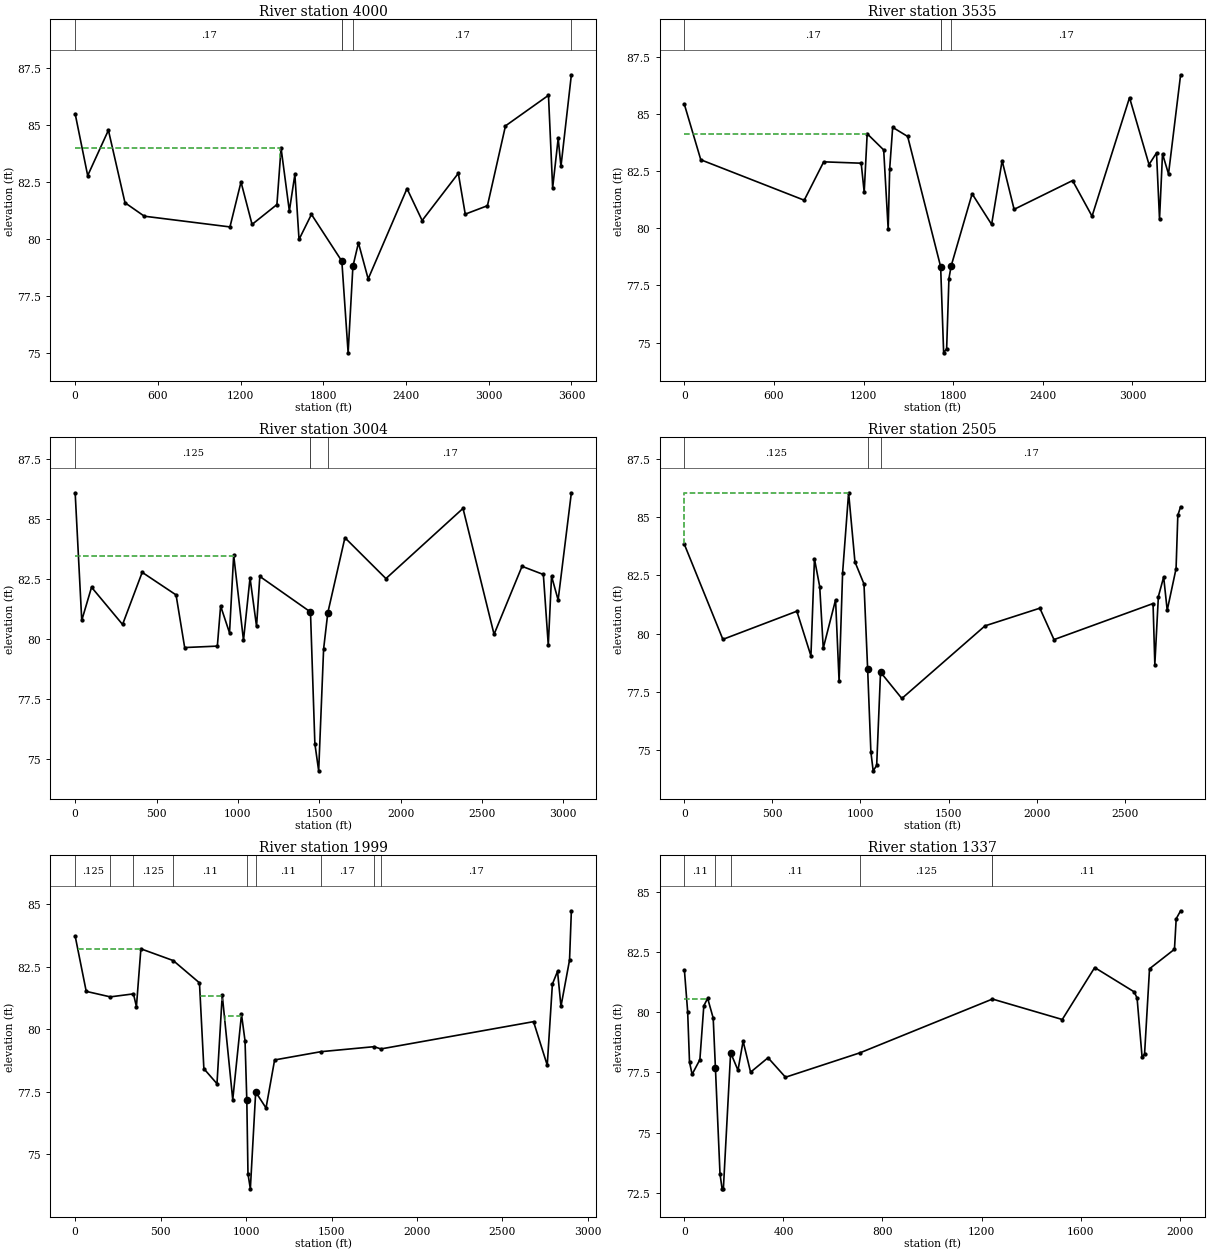
Type RM Length L Ch R = 1 ,4000    ,465,465,465
BEGIN DESCRIPTION:
BENS BRANCH TRIBUTARY NO. 2 8.0
END DESCRIPTION:
XS GIS Cut Line= 3
       3909828.6     10031181.44       3907851.8     10031305.95
      3906242.85     10031486.07
#Sta/Elev= 30
       0   85.48    90.9   82.77   241.2   84.76   361.5   81.58   501.7   80.99
    1123   80.52  1203.1   82.49  1283.3   80.63  1463.6    81.5  1493.7   83.98
  1553.8   81.22  1593.9   82.82    1624   79.97  1714.1   81.07  1934.6   79.02
  1980.2      75  2014.9   78.79  2055.1   79.82  2125.6   78.24  2407.3    82.2
  2517.1    80.8  2779.6   82.87  2829.9   81.08  2990.9   81.45  3121.7   84.95
  3433.7   86.29  3463.9   82.23  3504.1    84.4  3524.2   83.17  3599.7   87.19
#Mann= 5 ,-1 , 0
       0     .17       0  1934.6     .11       0  1934.6     .09       0
  2014.9     .17       0  3599.7    .125       0
#XS Ineff= 2 , 0
         1488.53   83.98
Permanent Ineff=
       F       F
Bank Sta=1934.6,2014.9
XS Rating Curve= 0 ,0
Exp/Cntr=0.3,0.1

Type RM Length L Ch R = 1 ,3535    ,531,531,531
BEGIN DESCRIPTION:
BENS BRANCH TRIBUTARY NO. 2 7.0
END DESCRIPTION:
XS GIS Cut Line= 2
      3909447.15     10030711.99      3906137.17     10031000.95
#Sta/Elev= 30
       0   85.42   109.7      83   802.3   81.23   932.8   82.91  1183.8   82.85
  1203.9   81.58  1223.9   84.14  1334.4   83.43  1364.5   79.96  1374.5    82.6
  1394.6   84.42    1495   84.02  1715.8   78.32  1735.9   74.55    1756   74.73
  1771.3    77.8  1786.1   78.35  1926.6   81.51  2057.1   80.17  2127.4   82.96
  2207.7   80.83  2599.1   82.09  2729.6   80.53  2980.6   85.72  3111.1   82.79
  3161.3    83.3  3181.4    80.4  3201.4   83.26  3241.6   82.38  3322.6   86.72
#Mann= 4 ,-1 , 0
       0     .17       0  1715.8     .11       0  1715.8     .09       0
  1786.1     .17       0
#XS Ineff= 2 , 0
         1223.92   84.14
Permanent Ineff=
       F       F
Bank Sta=1715.8,1786.1
XS Rating Curve= 0 ,0
Exp/Cntr=0.3,0.1

Type RM Length L Ch R = 1 ,3004    ,499,499,499
BEGIN DESCRIPTION:
BENS BRANCH TRIBUTARY NO. 2 6.0
END DESCRIPTION:
XS GIS Cut Line= 4
      3909068.15     10030208.81      3907642.29     10030340.54
      3907338.47      10030379.6      3906037.08     10030545.67
#Sta/Elev= 30
       0   86.09    40.5   80.78   100.7   82.16   291.4   80.61     412   82.78
   620.2   81.84   673.2   79.65     874   79.71   894.1   81.38   948.9   80.26
   974.4    83.5  1034.7   79.95  1074.9   82.55    1115   80.53  1135.1   82.61
  1446.5   81.13  1473.5   75.65  1496.9   74.52  1527.2   79.59  1553.1    81.1
  1658.2   84.22  1910.3   82.52  2384.1   85.44    2575    80.2    2747   83.03
    2878   82.69  2908.3   79.75  2928.4   82.62  2968.8   81.63  3050.2   86.09
#Mann= 4 ,-1 , 0
       0    .125       0  1446.5     .17       0  1446.5     .09       0
  1553.1     .17       0
#XS Ineff= 2 , 0
          973.34   83.47
Permanent Ineff=
       F       F
Bank Sta=1446.5,1553.1
XS Rating Curve= 0 ,0
Exp/Cntr=0.3,0.1

Type RM Length L Ch R = 1 ,2505    ,506,506,506
BEGIN DESCRIPTION:
BENS BRANCH TRIBUTARY NO. 2 5.0
END DESCRIPTION:
XS GIS Cut Line= 4
      3908736.34     10029891.36      3907747.02     10029906.98
      3907616.24     10029867.45      3905931.44     10030032.06
#Sta/Elev= 30
       0   83.83   218.5   79.75   638.6   80.96   718.6   79.04   738.6   83.21
   768.6   82.01   788.6   79.37   858.6   81.45   878.6   77.94   898.6   82.62
   932.6   86.05   968.6   83.08  1019.9   82.13  1040.8   78.46  1059.1   74.91
  1072.1    74.1    1092   74.33  1113.9   78.34    1235   77.21  1707.2   80.33
  2018.7   81.09  2099.1   79.74  2661.7   81.29  2671.8   78.67  2691.9   81.59
    2722   82.43  2742.1      81  2792.4   82.79  2802.4   85.08  2818.2   85.45
#Mann= 3 , 0 , 0
       0    .125       0  1040.8     .09       0  1113.9     .17       0
#XS Ineff= 2 , 0
          930.62   86.05
Permanent Ineff=
       F       F
Bank Sta=1040.8,1113.9
XS Rating Curve= 0 ,0
Exp/Cntr=0.3,0.1

Type RM Length L Ch R = 1 ,1999    ,662,662,662
BEGIN DESCRIPTION:
BENS BRANCH TRIBUTARY NO. 2 4.0
END DESCRIPTION:
XS GIS Cut Line= 4
      3908717.67     10029619.78      3907762.24     10029406.99
      3907677.03     10029430.76       3905845.5     10029576.33
#Sta/Elev= 30
       0   83.72    64.7   81.51   205.5   81.29     341   81.41   358.4    80.9
   384.5   83.21   573.9   82.74   727.2   81.85     753   78.42   829.7   77.82
   860.4   81.37   921.9   77.18   973.1   80.59   993.8   79.53  1004.2   77.15
    1011   74.22  1024.9   73.62  1056.1   77.49  1116.6   76.85  1166.8   78.77
  1437.6    79.1  1748.6    79.3  1788.7   79.21  2681.6    80.3  2761.8   78.56
  2791.9    81.8    2822   82.31  2842.1   80.91  2892.2   82.76  2902.9   84.73
#Mann= 9 ,-1 , 0
       0    .125       0   205.5     .11       0     341    .125       0
   573.9     .11       0  1004.2     .06       0  1056.1     .11       0
  1437.6     .17       0  1748.6     .15       0  1788.7     .17       0
#XS Ineff= 3 ,-1
   15.48   383.6    83.2  731.08  858.37   81.33  875.57  970.18   80.54
Permanent Ineff=
       F       F       F
Bank Sta=1004.2,1056.1
XS Rating Curve= 0 ,0
Exp/Cntr=0.3,0.1

Type RM Length L Ch R = 1 ,1337    ,837,837,837
BEGIN DESCRIPTION:
BENS BRANCH TRIBUTARY NO. 2 3.0
END DESCRIPTION:
XS GIS Cut Line= 3
      3907697.55     10028732.87      3907551.14     10028778.04
      3905713.26     10028997.97
#Sta/Elev= 30
       0   81.75    13.1   80.03    20.6   77.93    31.1   77.42    62.5   78.03
    78.4   80.27    93.9   80.58   116.3   79.76   125.3   77.68   143.8   73.28
   152.3   72.66   157.4   72.66   186.7   78.32   216.4   77.59   237.1    78.8
   267.3   77.51   337.8   78.11   408.3    77.3   710.5   78.32  1244.2   80.55
  1526.2    79.7  1657.2   81.86  1816.6   80.85  1828.4   80.59  1848.5   78.15
  1858.6   78.26  1878.7   81.81  1979.4   82.62  1986.4   83.89  2004.2   84.22
#Mann= 6 ,-1 , 0
       0     .11       0   125.3     .06       0   186.7     .11       0
   710.5    .125       0  1244.2    .125       0  1244.2     .11       0
#XS Ineff= 2 , 0
           93.18   80.57
Permanent Ineff=
       F       F
Bank Sta=125.3,186.7
XS Rating Curve= 0 ,0
Exp/Cntr=0.3,0.1

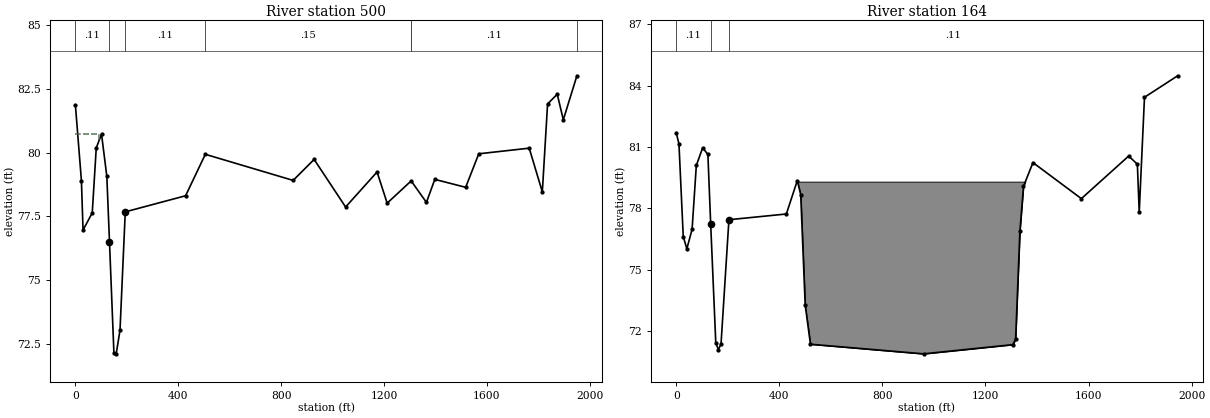
Type RM Length L Ch R = 1 ,500     ,336,336,336
BEGIN DESCRIPTION:
BENS BRANCH TRIBUTARY NO. 2 1.0
END DESCRIPTION:
XS GIS Cut Line= 3
       3907496.6     10027930.92      3907341.81     10027967.88
      3905586.05     10028320.74
#Sta/Elev= 30
       0   81.84    23.3    78.9    29.6   76.97    65.4   77.64      81   80.18
   101.5   80.72   122.1   79.07   132.4   76.52   149.6   72.18   158.6   72.13
   173.4   73.06   193.8   77.68   428.4   78.31   505.1   79.93   846.6   78.91
   928.2   79.73  1050.6   77.87    1173   79.24  1212.2   78.02  1305.6   78.89
  1364.9   78.05  1397.4   78.95  1517.5   78.64  1568.4   79.95  1764.6   80.17
  1815.6   78.46    1836    81.9  1873.6   82.28  1897.2   81.28    1950      83
#Mann= 7 ,-1 , 0
       0     .11       0   132.4     .06       0   193.8     .11       0
   505.1     .15       0  1305.6     .15       0  1305.6     .11       0
    1950    .125       0
#XS Ineff= 2 , 0
           91.74   80.73
Permanent Ineff=
       F       F
Bank Sta=132.4,193.8
XS Rating Curve= 0 ,0
Exp/Cntr=0.3,0.1

Type RM Length L Ch R = 1 ,164     ,0,0,0
BEGIN DESCRIPTION:
BENS BRANCH TRIBUTARY NO. 2 0.5
END DESCRIPTION:
XS GIS Cut Line= 2
      3907418.36     10027610.34      3905510.53     10027997.83
#Sta/Elev= 30
       0    81.7    10.7   81.16    27.4   76.63    41.3   76.03    61.7   76.98
    78.1    80.1   102.6   80.96     123   80.64   133.8   77.25   153.6   71.44
   163.8    71.1     174   71.39   204.6   77.45   427.4   77.73   469.9   79.36
   483.1   78.67   500.5   73.28   520.9   71.37   959.7    70.9  1306.7   71.35
  1316.9   71.62  1333.6    76.9  1347.5   79.08  1384.2   80.24    1572   78.48
  1755.6   80.56  1789.3   80.16  1796.5   77.82  1816.9   83.43  1945.6   84.48
#Mann= 3 , 0 , 0
       0     .11       0   133.8     .06       0   204.6     .11       0
#XS Ineff= 2 , 0
          103.47   80.93
Permanent Ineff=
       F       F
#Block Obstruct= 1 ,-1
  469.58 1357.59   79.31
Bank Sta=133.8,204.6
XS Rating Curve= 0 ,0
Exp/Cntr=0.3,0.1

Chan Stop Cuts=-1
Use User Specified Reach Order=0
Composite Channel Slope=5