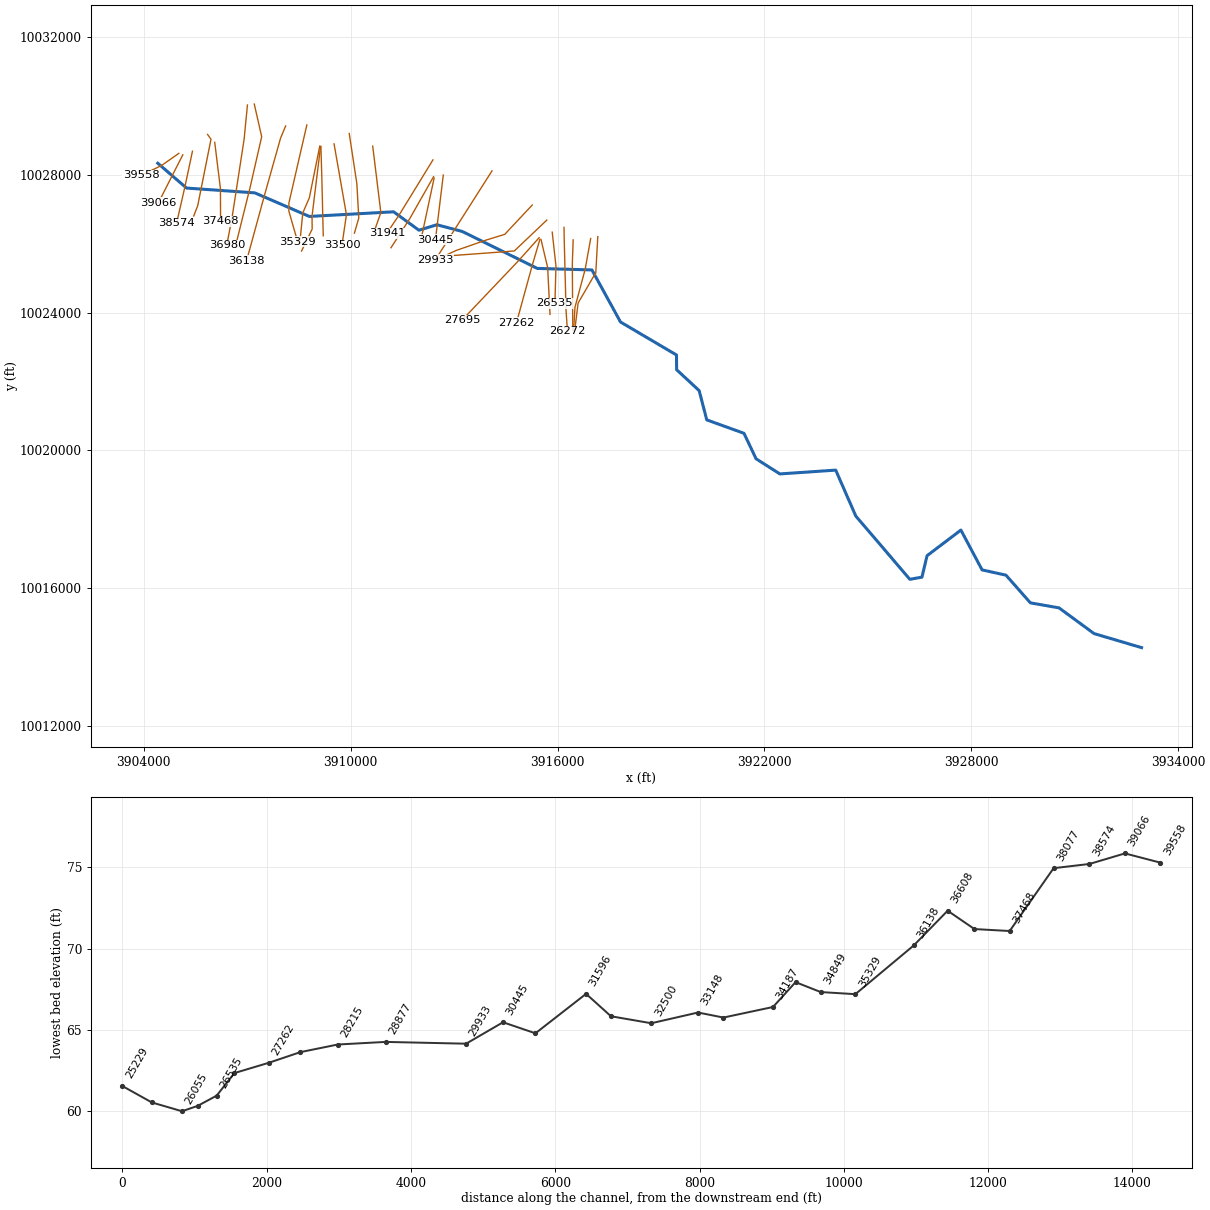
--- BENS BRANCH.prj (project) ---

Proj Title=BENS BRANCH Base Level Engineering
Current Plan=p01
Default Exp/Contr=0.3,0.1
English Units
Geom File=g01
Flow File=f01
Plan File=p01
Y Axis Title=Elevation
X Axis Title(PF)=Main Channel Distance
X Axis Title(XS)=Station
BEGIN DESCRIPTION:
BENS BRANCH
END DESCRIPTION:
DSS Export Rating Curves= 0
DSS Export Rating Curve Sorted= 0
DSS Export Volume Flow Curves= 0
DXF OffsetX= 0
DXF OffsetY= 0
DXF ScaleX= 1
DXF ScaleY= 10

--- BENS BRANCH.p01 (plan) ---

Plan Title=Multiple Run
Program Version=4.10
Short Identifier=Multiple
Geom File=g01
Flow File=f01
Subcritical Flow
K Sum by GR= 0
Std Step Tol= 0.01
Critical Tol= 0.01
Num of Std Step Trials= 20
Max Error Tol= 0.3
Flow Tol Ratio= 0.001
Split Flow NTrial= 30
Split Flow Tol= 0.02
Split Flow Ratio= 0.02
Log Output Level= 0
Friction Slope Method= 1
Unsteady Friction Slope Method= 2
Unsteady Bridges Friction Slope Method= 1
Parabolic Critical Depth
Global Vel Dist= 1 , 1 , 1
Global Log Level= 0
CheckData=True
Encroach Param=-1 ,0,0, 0
BEGIN DESCRIPTION:
Multiple Run
END DESCRIPTION:
Computation Interval=1HOUR
Output Interval=1HOUR
Run HTab= 0
Run UNet= 0
Run PostProcess= 0
Run WQNet= 0
UNET Theta= 1
UNET Theta Warmup= 1
UNET ZTol= 0.02
UNET ZSATol= 0.05
UNET MxIter= 20
UNET MaxInSteps= 0
UNET DtIC= 0
UNET DtMin= 0
UNET MaxCRTS= 20
UNET WFStab= 2
UNET SFStab= 1
UNET WFX= 1
UNET SFX= 1
UNET DSS MLevel= 4
UNET DZMax Abort= 100
UNET Convert EG Bridges= 0
UNET Use Existing IB Tables=-1
UNET Froude Reduction=False
UNET Froude Limit= 1
UNET Froude Power= 10
UNET Time Slicing=0,0, 5
UNET Junction Losses=0
Instantaneous Interval=1HOUR
Write IC File= 0
Write IC File at Sim End=0
Echo Input=False
Echo Parameters=False
Echo Output=False
Write Detailed= 0
WQ AD Non Conservative
WQ ULTIMATE=-1
WQ Max Comp Step=1HOUR
WQ Output Interval=15MIN
WQ Output Selected Increments= 0
WQ Output face flow=0
WQ Output face velocity=0
WQ Output face area=0
WQ Output face dispersion=0
WQ Output cell volume=0
WQ Output cell surface area=0
WQ Output cell continuity=0
WQ Output cumulative cell continuity=0
WQ Output face conc=0
WQ Output face dconc_dx=0
WQ Output face courant=0
WQ Output face peclet=0
WQ Output face adv mass=0
WQ Output face disp mass=0
WQ Output cell mass=0
WQ Output cell source sink temp=0
WQ Output cell source sink nsm=0
WQ Output MaxMinRange=-1
WQ Daily Max Min Mean=-1
WQ Daily Range=0
WQ Daily Time=0
WQ Create Restart=0
WQ Fixed Restart=0
WQ System Summary=0
WQ Use Fixed Temperature=0
Sorting and Armoring Iterations= 10
XS Update Threshold= 0.02
Hydraulics Update Threshold= 0.02
Energy Slope Method= 1
Volume Change Method= 0
XS Weighting Method= 0
Number of US Weighted Cross Sections= 1
Number of DS Weighted Cross Sections= 1
Upstream XS Weight=0.25
Main XS Weight=0.5
Downstream XS Weight=0.25
Number of DS XS's Weighted with US Boundary= 1
Upstream Boundary Weight= 1
Weight of XSs Associated with US Boundary= 0
Number of US XS's Weighted with DS Boundary= 1
Downstream Boundary Weight= 0.5
Weight of XSs Associated with DS Boundary= 0.5
Sediment Output Level= 4
Mass or Volume Output= 0
Output Increment Type= 1
Profile and TS Output Increment= 10
XS Output Flag= 0
XS Output Increment= 10
Disregard all LS=0
Disregard all Conn=0
Disregard all Breaches=0
Disregard all Pumps=0

--- BENS BRANCH.f01 (steady flow) ---

Flow Title=Multiple
Program Version=4.10
Number of Profiles= 7
Profile Names=10-year,25-year,50-year,1pct_min,100-year,1pct_plu,500-year
River Rch & RM=BENS BRANCH,Reach-1         ,39558
     121     139     169      67     203     613     305
River Rch & RM=BENS BRANCH,Reach-1         ,36138
    1252    1681    2257     992    2996    9048    5455
River Rch & RM=BENS BRANCH,Reach-1         ,31941
    1336    1784    2385    1043    3150    9513    5679
River Rch & RM=BENS BRANCH,Reach-1         ,28877
    1482    1994    2681    1178    3559   10748    6484
River Rch & RM=BENS BRANCH,Reach-1         ,28215
    1593    2142    2877    1264    3816   11524    6938
River Rch & RM=BENS BRANCH,Reach-1         ,19481
    1711    2314    3121    1376    4155   12548    7615
River Rch & RM=BENS BRANCH,Reach-1         ,13422
    2050    2793    3787    1678    5066   15299    9371
River Rch & RM=BENS BRANCH,Reach-1         ,12991
    2050    2793    3787    1678    5066   15299    9371
River Rch & RM=BENS BRANCH,Reach-1         ,9908
    2161    2941    3983    1762    5322   16072    9819
River Rch & RM=BENS BRANCH,Reach-1         ,5832
    2089    2823    3805    1675    5057   15272    9233
Boundary for River Rch & Prof#=BENS BRANCH,Reach-1         , 1
Up Type= 0
Dn Type= 3
Dn Slope=0.00012
Boundary for River Rch & Prof#=BENS BRANCH,Reach-1         , 2
Up Type= 0
Dn Type= 3
Dn Slope=0.00012
Boundary for River Rch & Prof#=BENS BRANCH,Reach-1         , 3
Up Type= 0
Dn Type= 3
Dn Slope=0.00012
Boundary for River Rch & Prof#=BENS BRANCH,Reach-1         , 4
Up Type= 0
Dn Type= 3
Dn Slope=0.00012
Boundary for River Rch & Prof#=BENS BRANCH,Reach-1         , 5
Up Type= 0
Dn Type= 3
Dn Slope=0.00012
Boundary for River Rch & Prof#=BENS BRANCH,Reach-1         , 6
Up Type= 0
Dn Type= 3
Dn Slope=0.00012
Boundary for River Rch & Prof#=BENS BRANCH,Reach-1         , 7
Up Type= 0
Dn Type= 3
Dn Slope=0.00012
DSS Import GetInterval= 0
DSS Import GetPeak= 0
DSS Import FillOption= 0

--- BENS BRANCH.g01 (geometry) ---

Geom Title=Existing Conditions
Program Version=4.10

River Reach=BENS BRANCH     ,Reach-1
Reach XY= 30
      3904406.44     10028342.58      3905241.12     10027622.37
      3907219.74     10027483.18      3908802.22     10026797.92
      3911245.65     10026932.38      3911981.75     10026397.45
      3912501.02     10026556.83        3913238.     10026360.99
        3915413.     10025287.56      3916998.15     10025243.77
      3917826.88      10023730.8      3919450.61      10022772.1
      3919454.08     10022345.02      3920108.23     10021736.84
      3920328.23     10020886.84      3921408.23     10020496.84
      3921758.23     10019756.84      3922448.23     10019316.84
      3924068.23     10019426.84        3924652.     10018091.55
      3926218.41     10016254.74      3926569.97     10016317.68
      3926717.54     10016940.51      3927699.31     10017684.86
      3928313.89     10016528.61       3929006.6     10016374.97
      3929714.93     10015570.28      3930545.66     10015424.45
      3931561.41     10014677.56      3932939.17     10014269.28

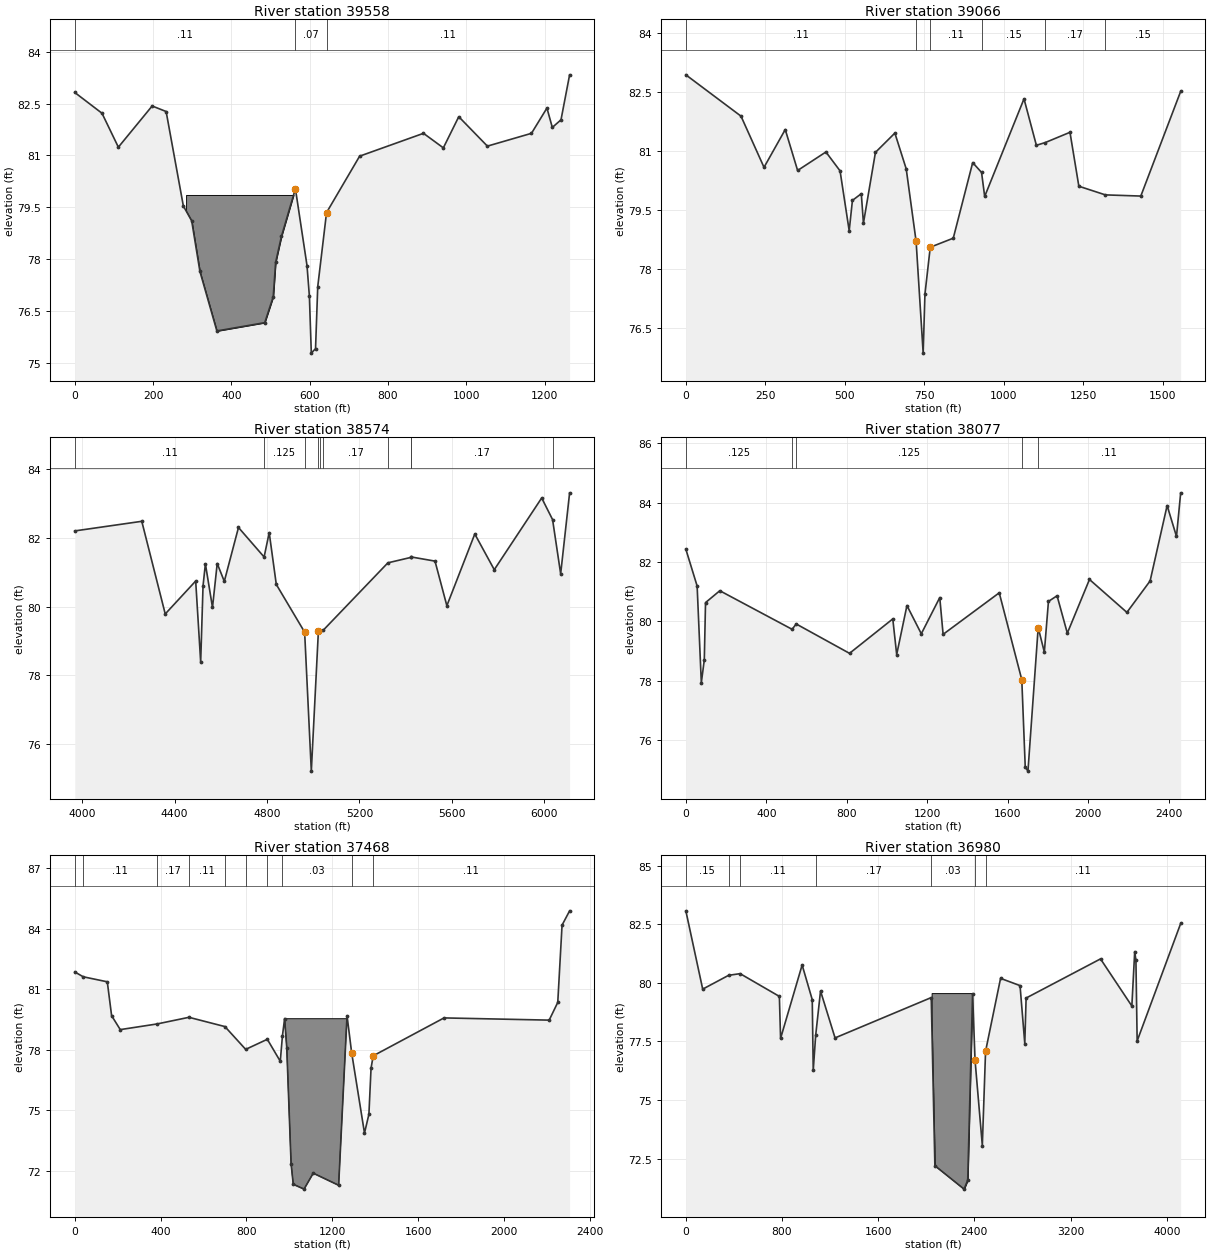
Type RM Length L Ch R = 1 ,39558   ,492,492,492
BEGIN DESCRIPTION:
Mapping XS 5f47dd87
END DESCRIPTION:
XS GIS Cut Line= 3
      3905014.68      10028629.6      3904518.31     10028280.45
      3903928.13     10027991.94
#Sta/Elev= 30
       0   82.82    69.5   82.22   111.3   81.24   197.6   82.43   233.3   82.27
   277.3   79.54   298.6   79.11   319.6   77.65   362.9   75.93   485.2   76.17
   506.9   76.92     513   77.91   527.8   78.66   563.5   80.04   593.1   77.82
   599.2   76.93   604.1   75.29   614.9   75.42   620.5   77.21     643   79.35
   727.5   80.98   890.6   81.64   941.3   81.22   980.7   82.12  1053.8   81.27
  1166.4   81.64  1205.9   82.37  1219.6   81.81  1241.8   82.03  1263.8   83.33
#Mann= 3 , 0 , 0
       0     .11       0   563.5     .07       0     643     .11       0
#Block Obstruct= 1 ,-1
  284.29  561.43   79.86
Bank Sta=563.5,643
XS Rating Curve= 0 ,0
Exp/Cntr=0.3,0.1

Type RM Length L Ch R = 1 ,39066   ,492,492,492
BEGIN DESCRIPTION:
Mapping XS 25d797a9
END DESCRIPTION:
XS GIS Cut Line= 3
      3905132.33     10028589.08      3904595.48     10027532.61
      3904427.75     10027201.16
#Sta/Elev= 30
       0   82.93   173.5   81.88   245.9   80.58   312.7   81.54   351.6    80.5
   440.6   80.97   485.1   80.49   513.8   78.97     524   79.74   551.9   79.91
   558.6   79.16   596.4   80.96   657.5   81.45   693.2   80.54   724.3    78.7
   746.5   75.86   752.1   77.36   768.8   78.55   841.2   78.78   902.3    80.7
   930.2   80.45     940   79.84  1063.7   82.32  1102.6   81.14  1130.7   81.21
  1208.3   81.47  1236.2    80.1  1319.7   79.88  1431.1   79.85  1556.5   82.51
#Mann= 6 ,-1 , 0
       0     .11       0   724.3     .06       0   768.8     .11       0
   930.2     .15       0  1130.7     .17       0  1319.7     .15       0
Bank Sta=724.3,768.8
XS Rating Curve= 0 ,0
Exp/Cntr=0.3,0.1

Type RM Length L Ch R = 1 ,38574   ,497,497,497
BEGIN DESCRIPTION:
Mapping XS 63d8d86b
END DESCRIPTION:
XS GIS Cut Line= 3
      3905411.95     10028693.87      3905198.42     10027684.61
      3904952.52     10026603.32
#Sta/Elev= 30
  3968.4   82.21  4258.2   82.49  4359.7   79.79  4491.4   80.75    4513   78.39
  4523.2   80.61  4533.4   81.25  4564.1   79.98  4584.5   81.26  4615.2   80.74
  4676.5   82.31  4787.4   81.45  4809.4   82.16  4840.1   80.65  4962.7   79.26
  4991.6   75.21  5022.1   79.28  5027.2   79.29  5042.3   79.31  5322.8   81.28
  5423.7   81.44  5424.6   81.45  5526.6   81.33  5577.9   80.03  5698.7   82.12
    5783   81.08  5988.1   83.17  6035.2   82.54  6070.2   80.96  6108.9   83.32
#Mann= 10 ,-1 , 0
  3968.4     .11       0  4787.4    .125       0  4962.7     .09       0
  5022.1     .12       0  5027.2    .125       0  5042.3     .17       0
  5322.8     .11       0  5423.7     .15       0  5424.6     .17       0
  6035.2     .11       0
Bank Sta=4962.7,5022.1
XS Rating Curve= 0 ,0
Exp/Cntr=0.3,0.1

Type RM Length L Ch R = 1 ,38077   ,609,609,609
BEGIN DESCRIPTION:
Mapping XS 05f19bf7
END DESCRIPTION:
XS GIS Cut Line= 4
      3905849.73     10029180.85      3905949.53     10029039.92
       3905564.9     10027111.43      3905449.13     10026811.67
#Sta/Elev= 30
       0   82.43    56.1   81.19      77   77.93    91.8    78.7    97.9   80.63
   168.9   81.03   528.4   79.73   548.8   79.91   813.9   78.92    1029   80.08
  1048.4   78.88  1099.4   80.53  1170.8   79.58  1262.6    80.8  1279.2   79.56
  1558.3   80.96  1670.5   78.03  1687.6   75.09  1701.1   74.95    1752   79.79
  1782.6   78.96    1803   80.67  1845.9   80.86  1896.9    79.6    2007   81.41
  2193.1    80.3  2308.5   81.36  2393.1    83.9  2439.7   82.86  2460.5   84.33
#Mann= 5 ,-1 , 0
       0    .125       0   528.4     .11       0   548.8    .125       0
  1670.5     .09       0    1752     .11       0
Bank Sta=1670.5,1752
XS Rating Curve= 0 ,0
Exp/Cntr=0.3,0.1

Type RM Length L Ch R = 1 ,37468   ,488,488,488
BEGIN DESCRIPTION:
Mapping XS a604b212
END DESCRIPTION:
XS GIS Cut Line= 3
      3906057.63     10028951.42       3906222.9     10027606.64
      3906227.34     10026655.56
#Sta/Elev= 30
       0   81.85    39.2   81.61   151.5   81.36   171.6   79.68   211.9   78.99
   383.2   79.27     532    79.6   699.6   79.14   796.3   78.01   897.1   78.51
   957.5   77.42   967.6   78.68   977.7   79.54   987.7    78.1  1007.9   72.34
    1018   71.32  1068.3   71.08  1111.1   71.87  1229.5   71.27  1268.6   79.68
    1290   77.85  1349.9   73.86  1370.5   74.79  1380.5   77.08  1390.5   77.69
  1720.5   79.57  2210.5   79.46  2250.5   80.34  2270.5   84.17  2305.7   84.88
#Mann= 10 ,-1 , 0
       0    .125       0    39.2     .11       0   383.2     .17       0
     532     .11       0   699.6    .125       0   796.3     .11       0
   897.1     .08       0   967.6     .03       0    1290     .06       0
  1390.5     .11       0
#Block Obstruct= 1 ,-1
  976.68 1266.84   79.53
Bank Sta=1290,1390.5
XS Rating Curve= 0 ,0
Exp/Cntr=0.3,0.1

Type RM Length L Ch R = 1 ,36980   ,372,372,372
BEGIN DESCRIPTION:
Mapping XS dd05bb01
END DESCRIPTION:
XS GIS Cut Line= 4
      3907006.38     10030035.38      3906909.76     10029037.29
        3906562.     10026777.42      3906406.94     10025964.99
#Sta/Elev= 30
       0   83.07   140.2   79.73     356   80.32   451.6   80.39   777.9   79.42
     788   77.63   967.3   80.76  1051.4   79.28  1059.6   76.26  1079.9   77.76
  1120.3   79.65  1241.1   77.65  2041.1   79.37  2071.4    72.2  2314.2    71.2
  2344.6   71.58  2385.1   79.54  2405.3   76.71    2466   73.06    2493   77.08
  2617.8   80.19  2779.7   79.88  2819.2   77.41  2830.2   79.35  3449.1   81.02
  3709.7   79.01  3733.5   81.33  3743.6   80.96  3753.8   77.52  4115.8   82.53
#Mann= 7 ,-1 , 0
       0     .15       0     356    .125       0   451.6     .11       0
  1079.9     .17       0  2041.1     .03       0  2405.3     .06       0
    2493     .11       0
#Block Obstruct= 1 ,-1
 2044.15 2382.45   79.56
Bank Sta=2405.3,2493
XS Rating Curve= 0 ,0
Exp/Cntr=0.3,0.1

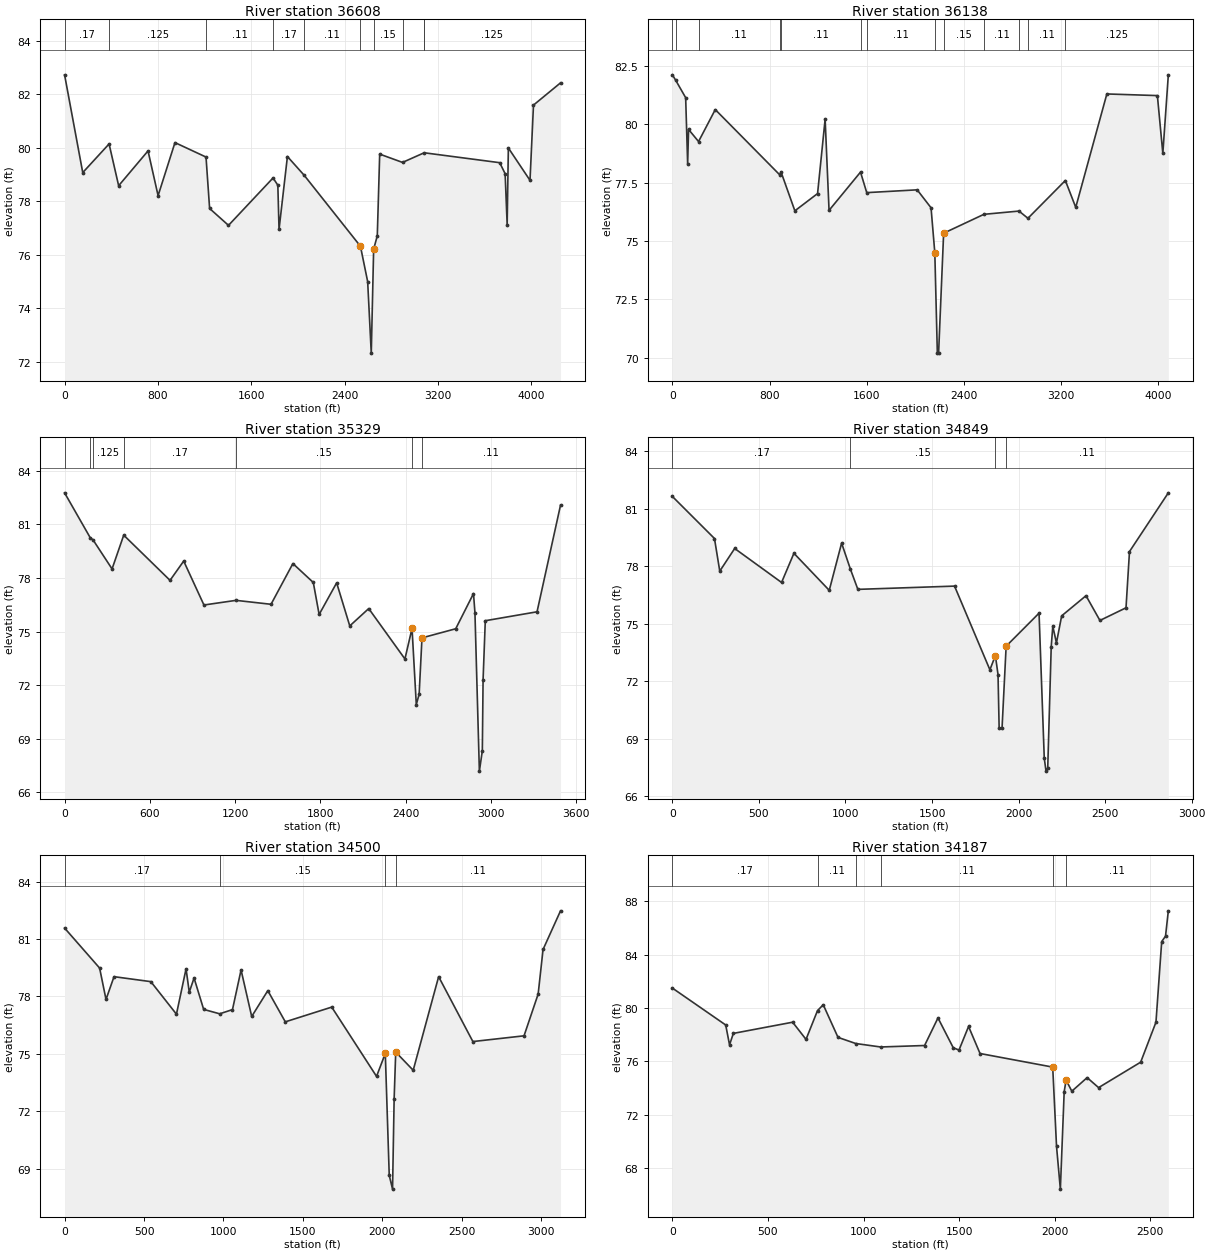
Type RM Length L Ch R = 1 ,36608   ,470,470,470
BEGIN DESCRIPTION:
Mapping XS df6ec9b7
END DESCRIPTION:
XS GIS Cut Line= 4
      3907204.51     10030062.83       3907419.7     10029114.65
      3907077.89     10027617.51      3906657.94     10025927.22
#Sta/Elev= 30
       0   82.72   155.6   79.07   381.2   80.14   463.2   78.58     715   79.88
   801.2   78.21   945.8   80.19  1211.9   79.65  1242.7   77.73  1404.5    77.1
  1786.3   78.87  1827.3    78.6  1837.6   76.95  1909.4   79.67    2053   78.97
  2535.2   76.32    2597      75  2627.9   72.33  2648.3   76.21  2679.5   76.71
  2700.1   79.76  2895.8   79.45  3081.3   79.81  3728.4   79.44  3774.9   79.03
  3792.3   77.13  3802.6   79.99  3988.1   78.78  4017.9   81.59  4249.6   82.42
#Mann= 10 ,-1 , 0
       0     .17       0   381.2    .125       0  1211.9     .11       0
  1786.3     .17       0    2053     .11       0  2535.2     .06       0
  2648.3     .15       0  2895.8     .11       0  3081.3     .15       0
  3081.3    .125       0
Bank Sta=2535.2,2648.3
XS Rating Curve= 0 ,0
Exp/Cntr=0.3,0.1

Type RM Length L Ch R = 1 ,36138   ,809,809,809
BEGIN DESCRIPTION:
Mapping XS aa7c9192
END DESCRIPTION:
XS GIS Cut Line= 4
      3908114.75     10029427.15      3907966.67     10029071.39
      3907503.68     10027424.01      3906979.96      10025504.6
#Sta/Elev= 30
       0   82.12    26.9   81.89   109.3   81.14   125.7    78.3   133.1   79.78
   215.5   79.26   353.2   80.63   884.7   77.83   894.7   77.96  1008.9   76.29
  1195.9   77.03  1258.2   80.22  1290.5   76.31  1549.7   77.95    1601   77.07
  2016.5   77.19  2130.7   76.42  2161.8   74.49  2182.5   70.21  2192.9   70.19
  2234.4   75.33    2566   76.14  2855.3   76.28  2928.8   75.97    3237   77.59
  3322.7   76.44    3579    81.3  3995.2   81.23  4040.1   78.75  4085.4   82.12
#Mann= 13 ,-1 , 0
       0     .11       0    26.9    .125       0   215.5     .11       0
   884.7     .17       0   894.7     .11       0  1549.7     .17       0
    1601     .11       0  2161.8     .09       0  2234.4     .15       0
    2566     .11       0  2855.3     .15       0  2928.8     .11       0
    3237    .125       0
Bank Sta=2161.8,2234.4
XS Rating Curve= 0 ,0
Exp/Cntr=0.3,0.1

Type RM Length L Ch R = 1 ,35329   ,480,480,480
BEGIN DESCRIPTION:
Mapping XS f7b2875c
END DESCRIPTION:
XS GIS Cut Line= 4
      3908729.33     10029456.66        3908209.     10027188.51
       3908207.9     10026951.45      3908463.71     10026060.83
#Sta/Elev= 30
       0   82.77   180.2   80.26   200.7   80.13     334   78.51   416.1    80.4
   741.9   77.87     838   78.95   980.4   76.49  1206.1   76.75  1452.4   76.53
  1606.3   78.81  1749.9   77.75  1790.9   75.96  1914.1   77.73  2006.4   75.32
  2139.8   76.29  2394.5   73.47  2444.5   75.18  2474.5   70.92  2494.5   71.49
  2514.5   74.65  2751.8   75.16  2876.9   77.13  2887.1   76.06  2918.3   67.19
  2939.1   68.33  2944.3   72.29  2959.9   75.61    3324   76.11  3489.2   82.08
#Mann= 7 ,-1 , 0
       0    .125       0   180.2     .11       0   200.7    .125       0
   416.1     .17       0  1206.1     .15       0  2444.5     .07       0
  2514.5     .11       0
Bank Sta=2444.5,2514.5
XS Rating Curve= 0 ,0
Exp/Cntr=0.3,0.1

Type RM Length L Ch R = 1 ,34849   ,349,349,349
BEGIN DESCRIPTION:
Mapping XS a86fbf82
END DESCRIPTION:
XS GIS Cut Line= 4
      3909103.74      10028839.4      3908801.55     10027338.49
       3908611.9     10026900.43      3908527.51     10026047.81
#Sta/Elev= 30
       0   81.63   243.1   79.44   273.7   77.74   359.8   78.92   630.7   77.15
   702.1   78.67   906.2   76.74   977.6    79.2  1028.6   77.84  1071.5   76.79
  1630.1   76.96  1834.3    72.6    1866   73.34  1881.3   72.35  1887.8   69.55
  1904.7   69.59  1928.2   73.83  2118.3   75.55  2148.4      68  2158.5   67.32
  2168.5   67.49  2188.6    73.8  2197.7   74.87  2218.8      74  2248.9   75.41
  2389.6   76.46    2470   75.17  2620.7   75.83  2640.8   78.76  2865.2   81.82
#Mann= 4 ,-1 , 0
       0     .17       0  1028.6     .15       0    1866     .09       0
  1928.2     .11       0
Bank Sta=1866,1928.2
XS Rating Curve= 0 ,0
Exp/Cntr=0.3,0.1

Type RM Length L Ch R = 1 ,34500   ,313,313,313
BEGIN DESCRIPTION:
BENS BRANCH 69.0
END DESCRIPTION:
XS GIS Cut Line= 4
      3909127.14     10028829.87      3908879.28     10026797.49
      3908883.89      10026431.4      3908575.62      10025792.5
#Sta/Elev= 30
       0   81.57   220.4   79.48   260.7   77.84   311.1   79.03   542.8   78.77
     704   77.07   764.4   79.44   784.6   78.22   814.8   78.96   875.2   77.32
     976   77.09  1056.6   77.31  1110.6   79.38  1177.5   76.95  1278.9    78.3
    1389   76.67  1681.2   77.44  1963.2   73.82  2018.3   75.02  2043.1   68.65
  2063.9   67.93  2073.9   72.64  2083.9   75.09  2193.9   74.14  2353.9   79.03
  2569.4   75.64  2891.4   75.94  2980.2   78.12  3011.1   80.45    3121   82.47
#Mann= 4 ,-1 , 0
       0     .17       0     976     .15       0  2018.3     .09       0
  2083.9     .11       0
Bank Sta=2018.3,2083.9
XS Rating Curve= 0 ,0
Exp/Cntr=0.3,0.1

Type RM Length L Ch R = 1 ,34187   ,687,687,687
BEGIN DESCRIPTION:
Mapping XS b0cddf55
END DESCRIPTION:
XS GIS Cut Line= 3
      3909137.18      10028829.8      3909162.49     10027975.86
      3909205.65     10026236.37
#Sta/Elev= 30
       0   81.49   278.9   78.72   298.9   77.23   318.9   78.09     629   78.93
     699   77.64   759.1    79.8   789.1   80.24   866.4   77.79   959.1   77.33
  1089.2   77.07  1319.2   77.18  1389.3   79.25  1469.3   77.01  1499.3   76.84
  1549.3   78.61  1609.3   76.58  1989.5   75.56  2009.5    69.6  2029.5    66.4
  2049.5   73.71  2059.5   74.58  2089.5   73.75  2169.5   74.77  2229.5   74.02
  2449.6   75.93  2529.6   78.93  2559.6   84.98  2579.6   85.39  2594.3   87.29
#Mann= 6 ,-1 , 0
       0     .17       0   759.1     .11       0   959.1     .15       0
  1089.2     .11       0  1989.5     .06       0  2059.5     .11       0
Bank Sta=1989.5,2059.5
XS Rating Curve= 0 ,0
Exp/Cntr=0.3,0.1

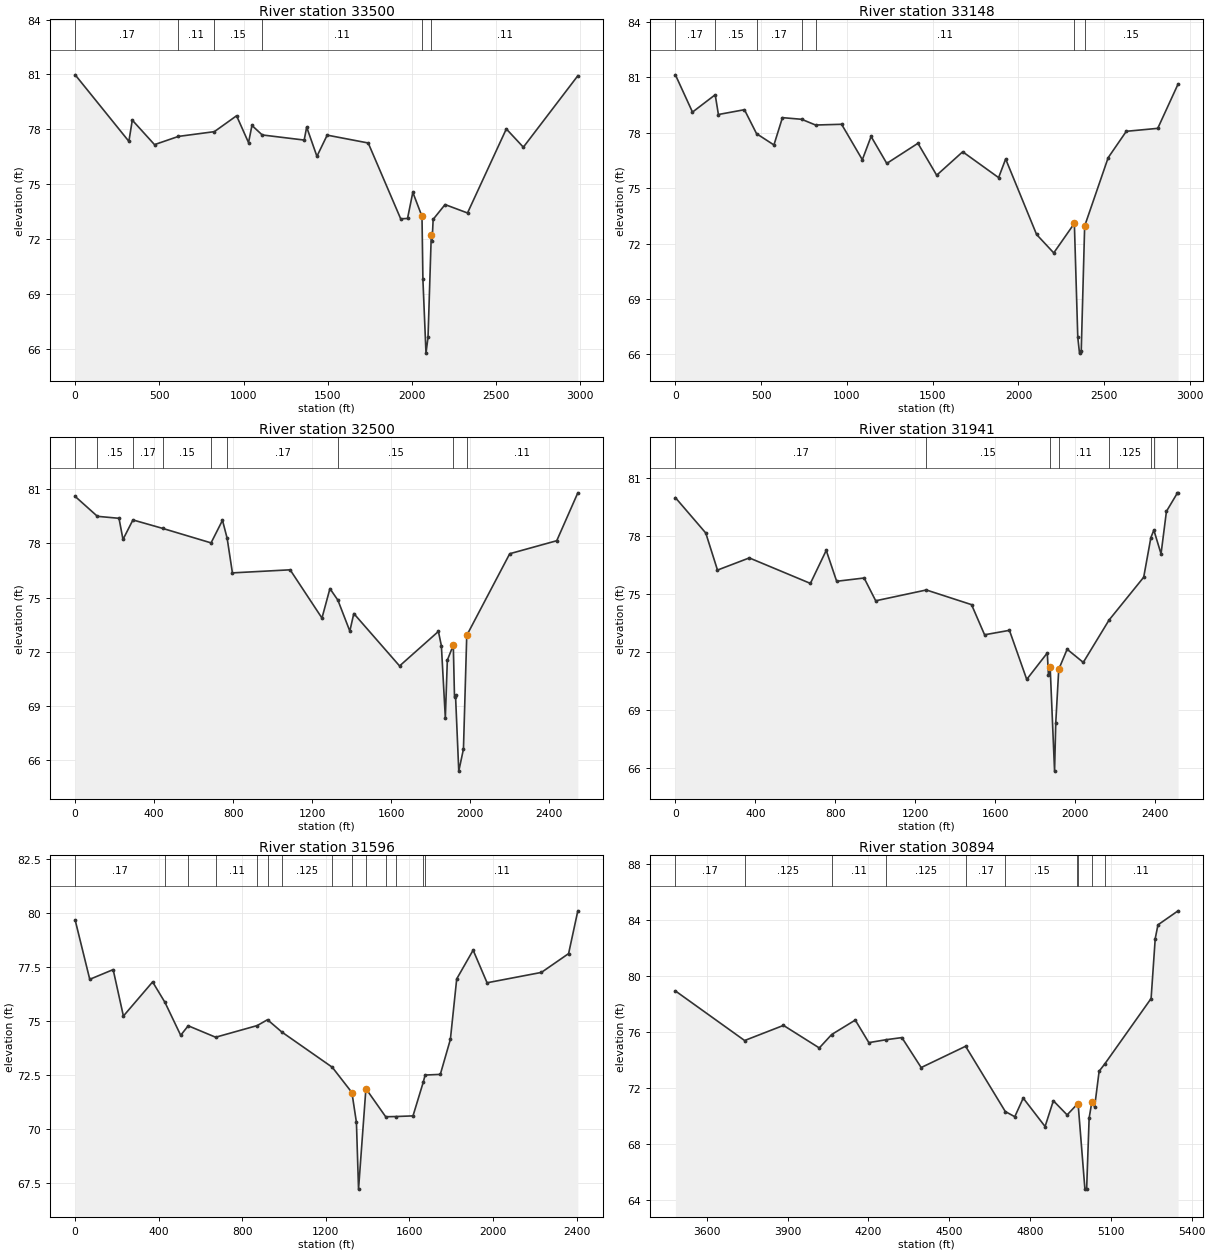
Type RM Length L Ch R = 1 ,33500   ,352,352,352
BEGIN DESCRIPTION:
BENS BRANCH 67.0
END DESCRIPTION:
XS GIS Cut Line= 3
      3909519.12      10028905.2      3909877.51     10026850.05
      3909747.89     10025960.95
#Sta/Elev= 30
       0   80.98   318.9   77.34   339.2    78.5   471.1   77.16   613.2   77.61
   826.4   77.87   958.4   78.74  1029.4   77.27  1049.7   78.21  1110.6   77.69
  1359.9   77.41  1374.6   78.12  1435.5   76.52  1496.4   77.68    1740   77.25
  1932.9    73.1  1973.5   73.12  2004.9   74.55  2059.4   73.23  2064.8   69.78
  2083.1   65.75  2095.2   66.62  2114.4   72.19  2119.5   71.89  2125.6   73.07
  2196.3   73.88  2329.6   73.42  2560.1   78.02  2661.2   77.02  2984.7   80.93
#Mann= 6 ,-1 , 0
       0     .17       0   613.2     .11       0   826.4     .15       0
  1110.6     .11       0  2059.4     .06       0  2114.4     .11       0
Bank Sta=2059.4,2114.4
XS Rating Curve= 0 ,0
Exp/Cntr=0.3,0.1

Type RM Length L Ch R = 1 ,33148   ,648,648,648
BEGIN DESCRIPTION:
Mapping XS e2225c18
END DESCRIPTION:
XS GIS Cut Line= 4
      3909958.56     10029208.96        3910180.      10027750.5
      3910235.47     10026749.23      3910108.74      10026313.3
#Sta/Elev= 30
       0   81.14    99.6   79.12     232   80.06   250.7   78.99   402.4   79.25
   473.2   77.95   574.4   77.34     624   78.82   736.2   78.73   817.1   78.42
   968.9   78.46  1089.8   76.54  1140.8    77.8  1232.3   76.34  1413.9   77.43
  1523.2    75.7  1674.9   76.97  1884.3   75.57  1925.3   76.58  2105.6   72.49
  2205.7   71.49  2325.9   73.09  2345.9   66.91  2355.9   66.06    2366   66.17
    2386   72.95    2523   76.65  2628.8   78.08  2812.1   78.24  2930.5   80.64
#Mann= 7 ,-1 , 0
       0     .17       0     232     .15       0   473.2     .17       0
   736.2     .15       0   817.1     .11       0  2325.9     .06       0
    2386     .15       0
Bank Sta=2325.9,2386
XS Rating Curve= 0 ,0
Exp/Cntr=0.3,0.1

Type RM Length L Ch R = 1 ,32500   ,559,559,559
BEGIN DESCRIPTION:
BENS BRANCH 65.0
END DESCRIPTION:
XS GIS Cut Line= 3
      3910639.64     10028841.34      3910875.63     10026911.19
      3910677.49     10026342.38
#Sta/Elev= 30
       0    80.6   112.5    79.5   221.9   79.39   242.1   78.22   292.4    79.3
   443.5   78.83     688   78.03   745.8   79.28   769.5   78.28   796.1   76.37
  1088.3   76.54  1249.5   73.87  1289.8    75.5  1330.1   74.86  1390.5   73.15
  1410.7   74.12  1642.4   71.22    1839   73.13    1854   72.34  1874.1   68.34
  1884.2   71.54  1914.4   72.37  1920.5    69.5  1925.6    69.6  1942.1    65.4
  1965.8   66.62  1982.5   72.91  2200.1   77.43  2438.2   78.15  2544.9    80.8
#Mann= 9 ,-1 , 0
       0     .17       0   112.5     .15       0   292.4     .17       0
   443.5     .15       0     688     .11       0   769.5     .17       0
  1330.1     .15       0  1914.4     .09       0  1982.5     .11       0
Bank Sta=1914.4,1982.5
XS Rating Curve= 0 ,0
Exp/Cntr=0.3,0.1

Type RM Length L Ch R = 1 ,31941   ,345,345,345
BEGIN DESCRIPTION:
BENS BRANCH 60.0
END DESCRIPTION:
XS GIS Cut Line= 3
      3912386.62     10028440.64      3911399.45      10026828.7
       3911047.9     10026311.17
#Sta/Elev= 30
       0   79.99   151.9   78.16   210.6   76.24   369.9   76.87   675.6   75.55
   754.9   77.26   807.1   75.66   944.5   75.83  1002.5   74.65  1255.9   75.21
  1482.2   74.45  1547.4   72.89  1671.8   73.12  1758.4   70.58  1861.3   71.95
  1867.2   70.79  1875.7    71.2  1897.7   65.83  1903.7   68.34  1918.6    71.1
  1960.6   72.14  2041.4   71.46  2170.2   73.65  2343.8   75.87  2379.7   77.92
  2394.6   78.31  2430.6   77.08  2457.6   79.28  2512.9   80.24  2515.8   80.24
#Mann= 8 ,-1 , 0
       0     .17       0  1255.9     .15       0  1875.7     .09       0
  1918.6     .11       0  2170.2    .125       0  2379.7     .15       0
  2394.6    .125       0  2512.9     .15       0
Bank Sta=1875.7,1918.6
XS Rating Curve= 0 ,0
Exp/Cntr=0.3,0.1

Type RM Length L Ch R = 1 ,31596   ,702,702,702
BEGIN DESCRIPTION:
Mapping XS 13b81871
END DESCRIPTION:
XS GIS Cut Line= 3
      3912403.82     10027951.78      3911709.37     10026725.97
      3911169.61     10025887.82
#Sta/Elev= 30
       0   79.66    69.8   76.92   181.8   77.37   230.8   75.22   370.7    76.8
   429.9   75.85     505   74.33     541   74.77   672.3   74.24   871.4   74.78
   920.5   75.05   989.2   74.48  1230.6   72.85  1324.5   71.68  1346.1    70.3
  1356.2   67.21  1391.5   71.86  1486.1   70.56  1535.6   70.57  1616.9    70.6
  1665.7   72.15  1674.9   72.49  1747.6   72.52  1795.8   74.14  1826.1   76.94
  1904.7   78.27  1971.4   76.76  2231.5   77.24  2361.6   78.11  2405.8   80.09
#Mann= 14 ,-1 , 0
       0     .17       0   429.9     .11       0     541    .125       0
   672.3     .11       0   871.4    .125       0   920.5     .11       0
   989.2    .125       0  1230.6     .15       0  1324.5     .09       0
  1391.5     .15       0  1486.1     .17       0  1535.6     .15       0
  1665.7     .17       0  1674.9     .11       0
Bank Sta=1324.5,1391.5
XS Rating Curve= 0 ,0
Exp/Cntr=0.3,0.1

Type RM Length L Ch R = 1 ,30894   ,449,449,449
BEGIN DESCRIPTION:
Mapping XS d462e57b
END DESCRIPTION:
XS GIS Cut Line= 2
      3912421.18     10027913.59        3912032.     10026088.11
#Sta/Elev= 30
  3483.1   78.93  3740.1   75.39  3884.4   76.47  4017.4   74.86  4063.4   75.82
    4151   76.85  4201.4   75.24  4266.3   75.45  4324.1    75.6  4395.7   73.46
  4560.7   74.98  4708.1   70.32  4743.3   69.95  4774.6   71.28  4855.8   69.25
  4886.5   71.09  4937.6   70.08  4976.1   70.86  4978.5   70.86  5003.7   64.78
  5010.1   64.78  5019.4   69.86  5029.6   71.01  5039.8   70.66  5056.5    73.2
  5077.5   73.72  5249.5   78.39  5264.8   82.67    5275   83.65  5349.6   84.65
#Mann= 10 ,-1 , 0
  3483.1     .17       0  3740.1    .125       0  4063.4     .11       0
  4266.3    .125       0  4560.7     .17       0  4708.1     .15       0
  4976.1     .17       0  4978.5     .09       0  5029.6     .17       0
  5077.5     .11       0
Bank Sta=4978.5,5029.6
XS Rating Curve= 0 ,0
Exp/Cntr=0.3,0.1

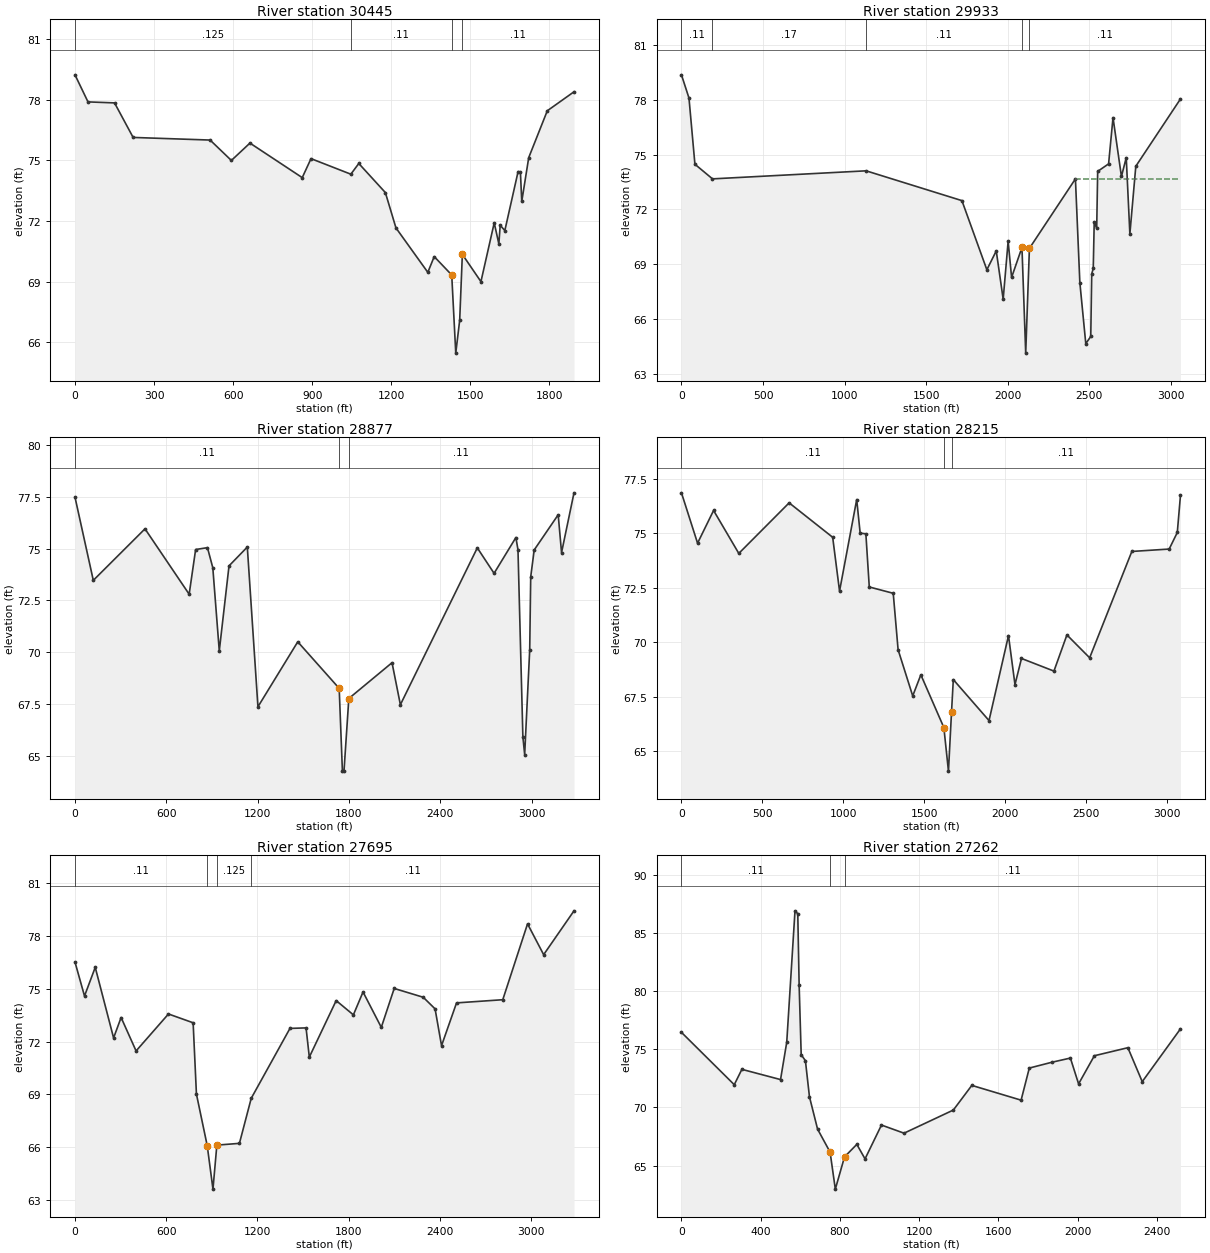
Type RM Length L Ch R = 1 ,30445   ,512,512,512
BEGIN DESCRIPTION:
BENS BRANCH 59.0
END DESCRIPTION:
XS GIS Cut Line= 2
      3912687.03     10028000.04       3912458.8     10026120.56
#Sta/Elev= 30
       0   79.24    49.3    77.9   150.1   77.85   220.6   76.14   512.7   76.01
   593.3      75   663.8   75.86   862.2   74.15   895.5   75.09  1046.6   74.32
  1076.8   74.85  1177.6   73.41  1217.8   71.66  1338.7   69.46  1362.9   70.24
  1429.4   69.33  1444.7   65.46  1459.6   67.09  1469.7   70.35  1540.2      69
  1590.6   71.91  1608.2   70.87  1613.3   71.79  1630.9   71.53  1681.2   74.45
    1690   74.42  1695.1   72.97  1721.5   75.14    1792   77.46  1893.3    78.4
#Mann= 4 ,-1 , 0
       0    .125       0  1046.6     .11       0  1429.4     .09       0
  1469.7     .11       0
Bank Sta=1429.4,1469.7
XS Rating Curve= 0 ,0
Exp/Cntr=0.3,0.1

Type RM Length L Ch R = 1 ,29933   ,1116,1116,1116
BEGIN DESCRIPTION:
BENS BRANCH 58.0
END DESCRIPTION:
XS GIS Cut Line= 2
      3914099.79     10028121.57       3912458.8      10025540.7
#Sta/Elev= 30
       0   79.36    46.1   78.09    82.5   74.47   190.2   73.67  1131.7   74.11
  1718.9   72.48  1871.8    68.7  1929.4   69.73  1971.8   67.09  2002.2   70.26
  2023.4   68.28  2086.9   69.92  2109.9   64.14  2132.6   69.87  2414.6   73.67
  2441.7      68  2478.1   64.66  2508.6   65.05  2514.6   68.48  2523.9   68.77
  2529.8   71.31    2545   70.96    2551   74.08  2617.9   74.49    2645   77.02
  2696.6    73.8  2726.1   74.83  2748.3   70.66  2784.7   74.36  3058.4   78.04
#Mann= 5 ,-1 , 0
       0     .11       0   190.2     .17       0  1131.7     .11       0
  2086.9     .09       0  2132.6     .11       0
#XS Ineff= 2 , 0
                         2414.32           73.67
Permanent Ineff=
       F       F
Bank Sta=2086.9,2132.6
XS Rating Curve= 0 ,0
Exp/Cntr=0.3,0.1

Type RM Length L Ch R = 1 ,28877   ,662,662,662
BEGIN DESCRIPTION:
BENS BRANCH 57.0
END DESCRIPTION:
XS GIS Cut Line= 6
      3915267.83     10027130.98      3914469.08     10026277.27
      3913939.92     10026114.45      3913847.15     10026083.21
      3913068.44     10025812.28      3912493.53     10025547.65
#Sta/Elev= 30
       0   77.49   120.3   73.47   459.8   75.96     750    72.8   792.5   74.96
   870.2   75.05   905.3   74.08   947.8   70.06  1011.8   74.17    1132   75.08
  1201.8   67.36  1463.4    70.5  1735.5   68.25  1756.6   64.26  1767.1   64.25
  1798.8   67.76  2082.6   69.49  2137.5   67.46  2642.8   75.04    2753   73.81
  2896.3   75.54    2910   74.95  2942.2   65.91    2954   65.05  2987.1   70.12
  2993.7   73.64  3016.6   74.94  3174.2   76.64  3196.2   74.81    3278    77.7
#Mann= 3 , 0 , 0
       0     .11       0  1735.5     .09       0  1798.8     .11       0
#XS Ineff= 2 , 0
                         2895.93           75.48
Permanent Ineff=
       F       F
Bank Sta=1735.5,1798.8
XS Rating Curve= 0 ,0
Exp/Cntr=0.3,0.1

Type RM Length L Ch R = 1 ,28215   ,520,520,520
BEGIN DESCRIPTION:
BENS BRANCH 55.0
END DESCRIPTION:
XS GIS Cut Line= 5
      3915688.43     10026691.28      3914747.98     10025796.28
       3914429.5     10025769.84      3914319.03     10025762.23
      3912968.28     10025662.36
#Sta/Elev= 30
       0   76.86    99.5   74.55   198.5   76.05   354.3   74.08   665.3    76.4
   934.3   74.82   976.7   72.35  1082.7   76.55  1104.1   75.01  1139.3   74.98
  1160.4   72.54  1308.4   72.25  1338.5   69.66  1428.8   67.54    1479   68.51
  1621.2   66.09  1649.6   64.09  1668.6   66.81  1679.6   68.29  1900.2   66.41
  2020.5   70.31  2060.6   68.06  2100.8   69.26  2301.3   68.68  2381.5   70.34
  2521.9   69.29  2782.6   74.17  3013.2   74.28  3063.4   75.04    3083   76.74
#Mann= 3 , 0 , 0
       0     .11       0  1621.2     .04       0  1668.6     .11       0
Bank Sta=1621.2,1668.6
XS Rating Curve= 0 ,0
Exp/Cntr=0.3,0.1

Type RM Length L Ch R = 1 ,27695   ,433,433,433
BEGIN DESCRIPTION:
BENS BRANCH 54.0
END DESCRIPTION:
XS GIS Cut Line= 3
      3915466.73     10026180.36      3914861.43      10025503.7
      3913226.16     10023780.29
#Sta/Elev= 30
       0   76.52    62.6   74.59   133.2   76.22     254   72.21   303.4   73.37
     402   71.47   615.1   73.57   777.4   73.07   799.1   69.02   870.1   66.09
   907.9   63.62   933.5   66.12    1082   66.22  1159.7   68.78  1414.5   72.75
  1520.5   72.78  1541.9   71.12  1718.7   74.33  1831.9   73.52  1895.4   74.82
  2015.6   72.81  2100.5   75.02  2291.5   74.52  2369.5   73.86    2412   71.77
  2510.7    74.2  2814.9   74.38  2977.9   78.69  3083.9   76.94  3283.6   79.43
#Mann= 4 ,-1 , 0
       0     .11       0   870.1     .04       0   933.5    .125       0
  1159.7     .11       0
Bank Sta=870.1,933.5
XS Rating Curve= 0 ,0
Exp/Cntr=0.3,0.1

Type RM Length L Ch R = 1 ,27262   ,481,481,481
BEGIN DESCRIPTION:
BENS BRANCH 53.0
END DESCRIPTION:
XS GIS Cut Line= 3
      3915488.42       10026131.      3915268.73     10025385.47
      3914808.28     10023703.95
#Sta/Elev= 30
       0   76.45   266.6   71.95   305.1   73.27   500.3   72.39   531.6    75.6
   573.3    86.9   587.3   86.65   594.2   80.51   604.6   74.53   625.9   74.01
   646.3   70.91   687.3   68.13   750.5   66.15   776.9   62.97   823.3   65.74
   885.5   66.82   926.9   65.57  1009.9   68.48  1123.9   67.78  1372.8   69.77
  1466.1   71.89  1714.9   70.62  1756.4   73.38  1870.4   73.88  1963.8   74.24
  2005.2   72.02  2084.9   74.44  2254.1   75.13  2326.6   72.21  2519.6   76.75
#Mann= 3 , 0 , 0
       0     .11       0   750.5     .04       0   823.3     .11       0
Bank Sta=750.5,823.3
XS Rating Curve= 0 ,0
Exp/Cntr=0.3,0.1

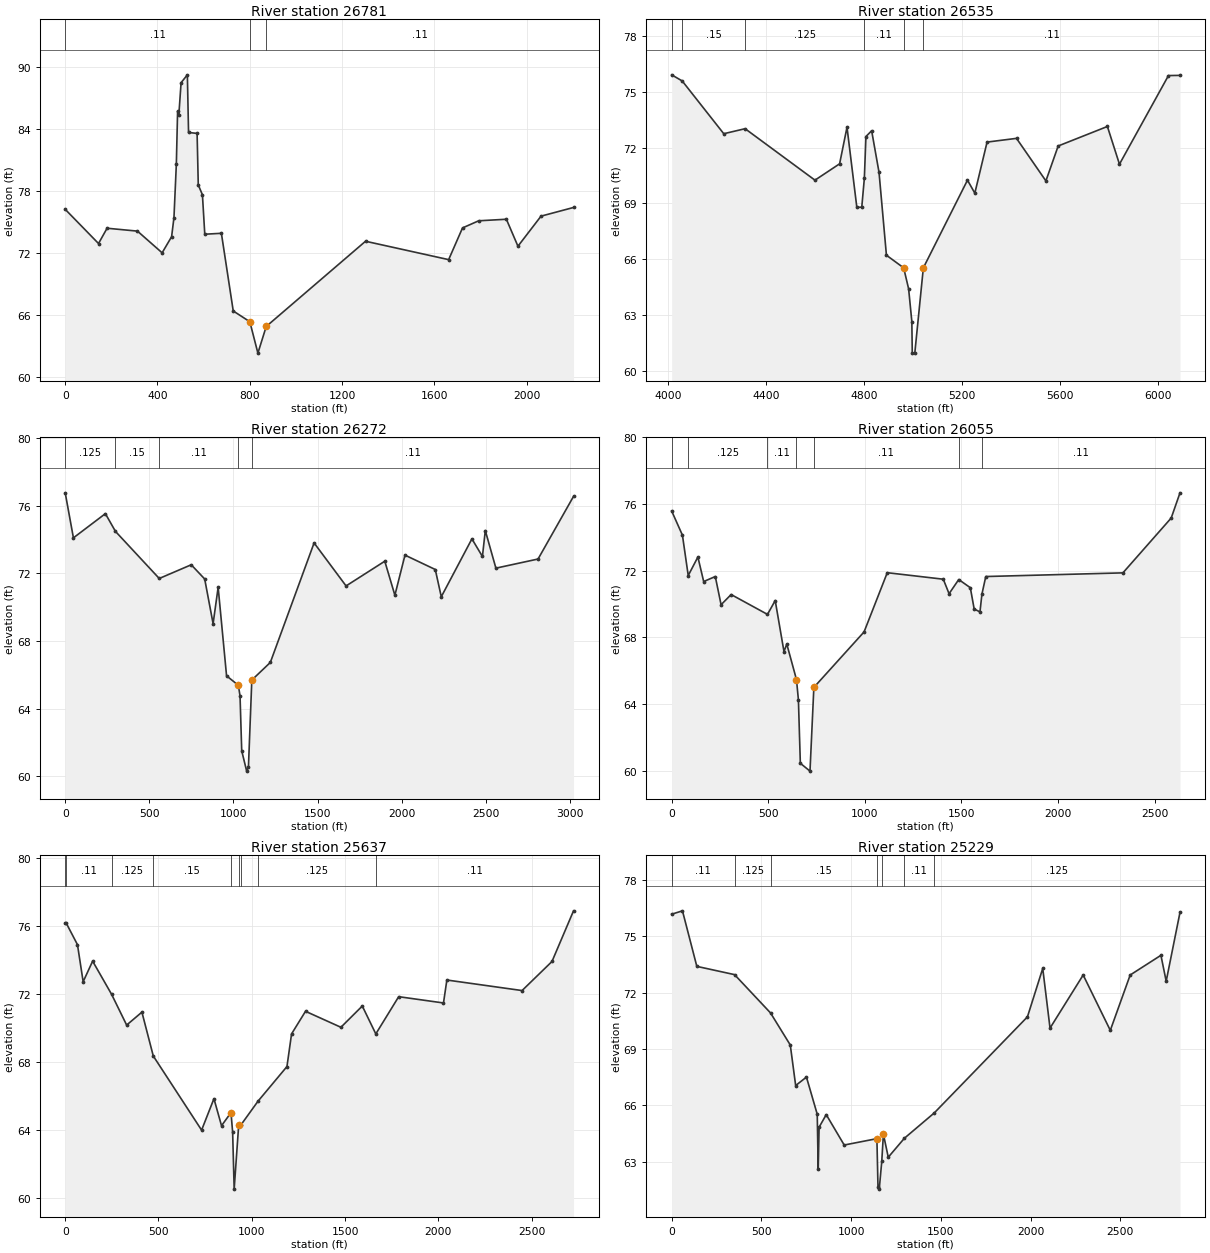
Type RM Length L Ch R = 1 ,26781   ,246,246,246
BEGIN DESCRIPTION:
BENS BRANCH 52.0
END DESCRIPTION:
XS GIS Cut Line= 3
      3915520.32     10026129.89      3915713.52     10025315.16
      3915781.72     10023950.43
#Sta/Elev= 30
       0   76.25   144.4   72.94   181.5   74.42   313.3   74.14   420.2   72.04
   461.3    73.6   471.5   75.45   481.8   80.61   487.3   85.76   492.5   85.34
   502.4   88.51   529.6   89.27   534.7   83.69   571.8    83.6   576.9   78.61
   594.9   77.66   605.1   73.84   677.1   73.93   728.5   66.41   800.4   65.37
   835.4   62.33   871.5   64.91    1302   73.16  1662.4   71.38  1722.5   74.45
  1792.6   75.14  1912.7   75.29  1962.8   72.68  2062.9   75.59  2203.8   76.43
#Mann= 3 , 0 , 0
       0     .11       0   800.4     .04       0   871.5     .11       0
Bank Sta=800.4,871.5
XS Rating Curve= 0 ,0
Exp/Cntr=0.3,0.1

Type RM Length L Ch R = 1 ,26535   ,263,263,263
BEGIN DESCRIPTION:
BENS BRANCH 51.0
END DESCRIPTION:
XS GIS Cut Line= 3
      3915846.23     10026342.38      3915954.73     10025352.82
      3915924.41     10024274.03
#Sta/Elev= 30
  4014.8   75.92  4057.8   75.59  4227.4   72.75  4314.5   73.02  4599.6   70.25
  4700.2   71.13  4730.4    73.1  4770.6   68.78  4790.7    68.8  4801.2   70.35
  4807.7    72.6    4831   72.91  4861.1   70.67  4891.3   66.21  4961.7   65.53
  4981.9    64.4    4995   62.64  4996.8   60.94  5007.1   60.94    5042   65.53
  5222.1   70.25  5252.1   69.55  5302.1    72.3  5422.2    72.5  5542.2   70.21
  5592.3   72.09  5793.2   73.14  5842.4   71.11  6042.4   75.88  6089.5   75.89
#Mann= 6 ,-1 , 0
  4014.8     .11       0  4057.8     .15       0  4314.5    .125       0
  4801.2     .11       0  4961.7     .04       0    5042     .11       0
Bank Sta=4961.7,5042
XS Rating Curve= 0 ,0
Exp/Cntr=0.3,0.1

Type RM Length L Ch R = 1 ,26272   ,217,217,217
BEGIN DESCRIPTION:
Mapping XS 927cc2fc
END DESCRIPTION:
XS GIS Cut Line= 4
      3916188.11     10026479.86      3916193.83     10026128.27
      3916247.64     10024060.68      3916287.29     10023460.76
#Sta/Elev= 30
       0   76.75    48.8   74.09   238.8   75.52   298.8   74.47   558.9   71.69
     749    72.5     829   71.66     879   69.02     909   71.17     959   65.94
  1029.1   65.38  1039.1   64.75  1049.1   61.51  1078.5   60.31  1089.1   60.57
  1109.1   65.69  1219.1   66.73  1479.2   73.79  1669.3   71.25  1899.4   72.71
  1959.4    70.7  2019.4   73.07  2199.5   72.22  2235.2   70.61  2417.2   74.03
  2479.7   72.99  2496.8   74.52  2559.8    72.3  2810.4   72.84  3021.2   76.54
#Mann= 5 ,-1 , 0
       0    .125       0   298.8     .15       0   558.9     .11       0
  1029.1     .04       0  1109.1     .11       0
Bank Sta=1029.1,1109.1
XS Rating Curve= 0 ,0
Exp/Cntr=0.3,0.1

Type RM Length L Ch R = 1 ,26055   ,418,418,418
BEGIN DESCRIPTION:
BENS BRANCH 50.0
END DESCRIPTION:
XS GIS Cut Line= 3
      3916453.87     10026116.71       3916428.8     10025423.24
      3916443.03     10023485.15
#Sta/Elev= 30
       0   75.58    55.7   74.13    85.7   71.71   135.7   72.82   165.7   71.35
   225.8   71.65   255.8   69.96   307.9   70.57     496   69.38     536   70.21
   581.4   67.15     596    67.6   646.1   65.47   656.1   64.26   666.1   60.45
   716.1   59.98   736.1      65   996.1   68.33  1116.1   71.88  1406.1   71.49
  1436.1   70.62  1486.1   71.47  1546.1   70.98  1566.1    69.7  1596.1   69.53
  1606.1   70.59  1626.1   71.65  2336.1   71.87  2586.1   75.16  2631.6   76.67
#Mann= 7 ,-1 , 0
       0     .11       0    85.7    .125       0     496     .11       0
   646.1     .07       0   736.1     .11       0  1486.1    .125       0
  1606.1     .11       0
Bank Sta=646.1,736.1
XS Rating Curve= 0 ,0
Exp/Cntr=0.3,0.1

Type RM Length L Ch R = 1 ,25637   ,408,408,408
BEGIN DESCRIPTION:
BENS BRANCH 49.0
END DESCRIPTION:
XS GIS Cut Line= 4
      3916961.68     10026155.77      3916801.73     10025262.57
      3916506.14     10024160.42       3916465.6     10023485.15
#Sta/Elev= 30
       0   76.18     4.9   76.18    65.7    74.9    96.2   72.72     147   73.93
   248.6   71.98   329.3   70.17   411.1   70.93   472.1   68.35     731   63.99
   797.2   65.84   837.8   64.25   888.6   65.02   897.4   63.87   905.6   60.52
   929.7   64.27   943.4   64.32  1033.2   65.69  1188.5   67.73  1213.2   69.65
    1288   70.98  1477.7   70.04  1592.3   71.29  1664.8   69.65  1787.4   71.84
  2027.5   71.47  2045.6   72.82  2448.6    72.2    2609   73.91  2724.5   76.89
#Mann= 9 ,-1 , 0
       0    .125       0     4.9     .11       0   248.6    .125       0
   472.1     .15       0   888.6     .09       0   929.7     .15       0
   943.4     .11       0  1033.2    .125       0  1664.8     .11       0
Bank Sta=888.6,929.7
XS Rating Curve= 0 ,0
Exp/Cntr=0.3,0.1

Type RM Length L Ch R = 1 ,25229   ,550,550,550
BEGIN DESCRIPTION:
BENS BRANCH 48.0
END DESCRIPTION:
XS GIS Cut Line= 5
      3917167.85     10026211.07      3917109.25     10025148.83
      3917026.49     10025022.33      3916597.83     10024282.85
       3916503.8     10023525.08
#Sta/Elev= 30
       0   76.18    60.1   76.36   140.2    73.4   350.5   72.96   550.8   70.92
     661   69.21     691   67.05   751.1    67.5   811.2   65.52   816.6   62.58
   821.6   64.83   861.3    65.5   961.5   63.88  1143.7   64.22  1149.7   61.67
  1156.8   61.53  1170.8   63.01  1179.9   64.46    1207   63.23  1296.8   64.24
  1463.3   65.59  1982.6   70.71  2067.9   73.29  2108.5   70.11  2293.2   72.94
  2444.4   69.99  2555.2   72.94  2726.5   73.99  2755.8   72.61  2832.8   76.28
#Mann= 7 ,-1 , 0
       0     .11       0   350.5    .125       0   550.8     .15       0
  1143.7     .09       0  1170.8     .15       0  1296.8     .11       0
  1463.3    .125       0
Bank Sta=1143.7,1179.9
XS Rating Curve= 0 ,0
Exp/Cntr=0.3,0.1