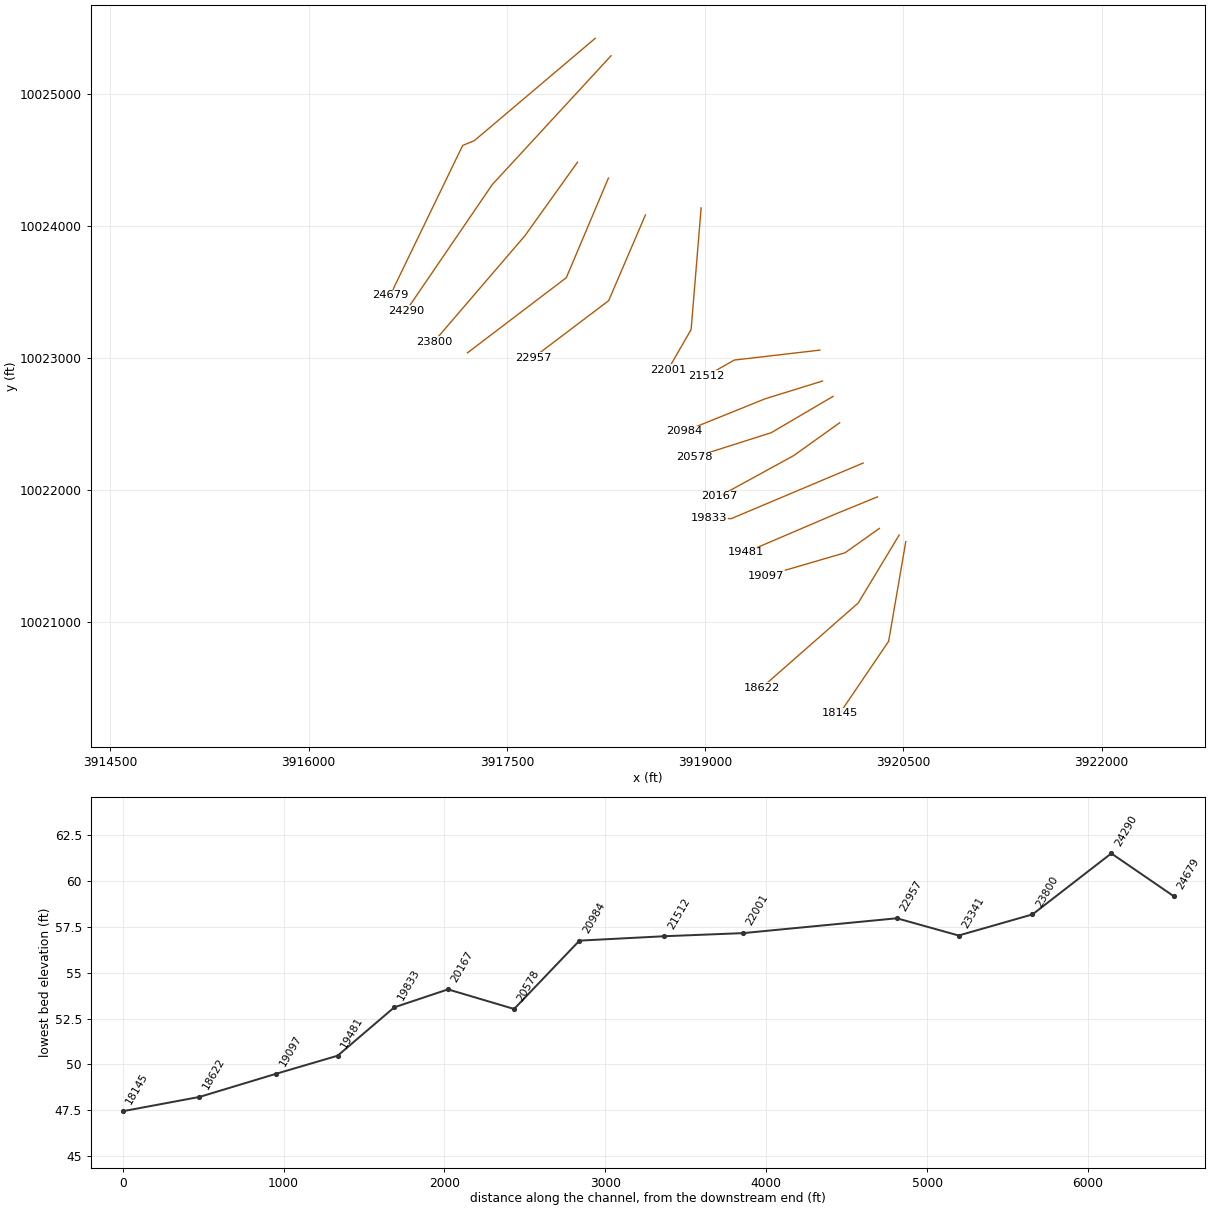
HEC-RAS study BENS BRANCH.prj: BENS BRANCH Base Level Engineering

--- BENS BRANCH.g01 (geometry) --- (continued)

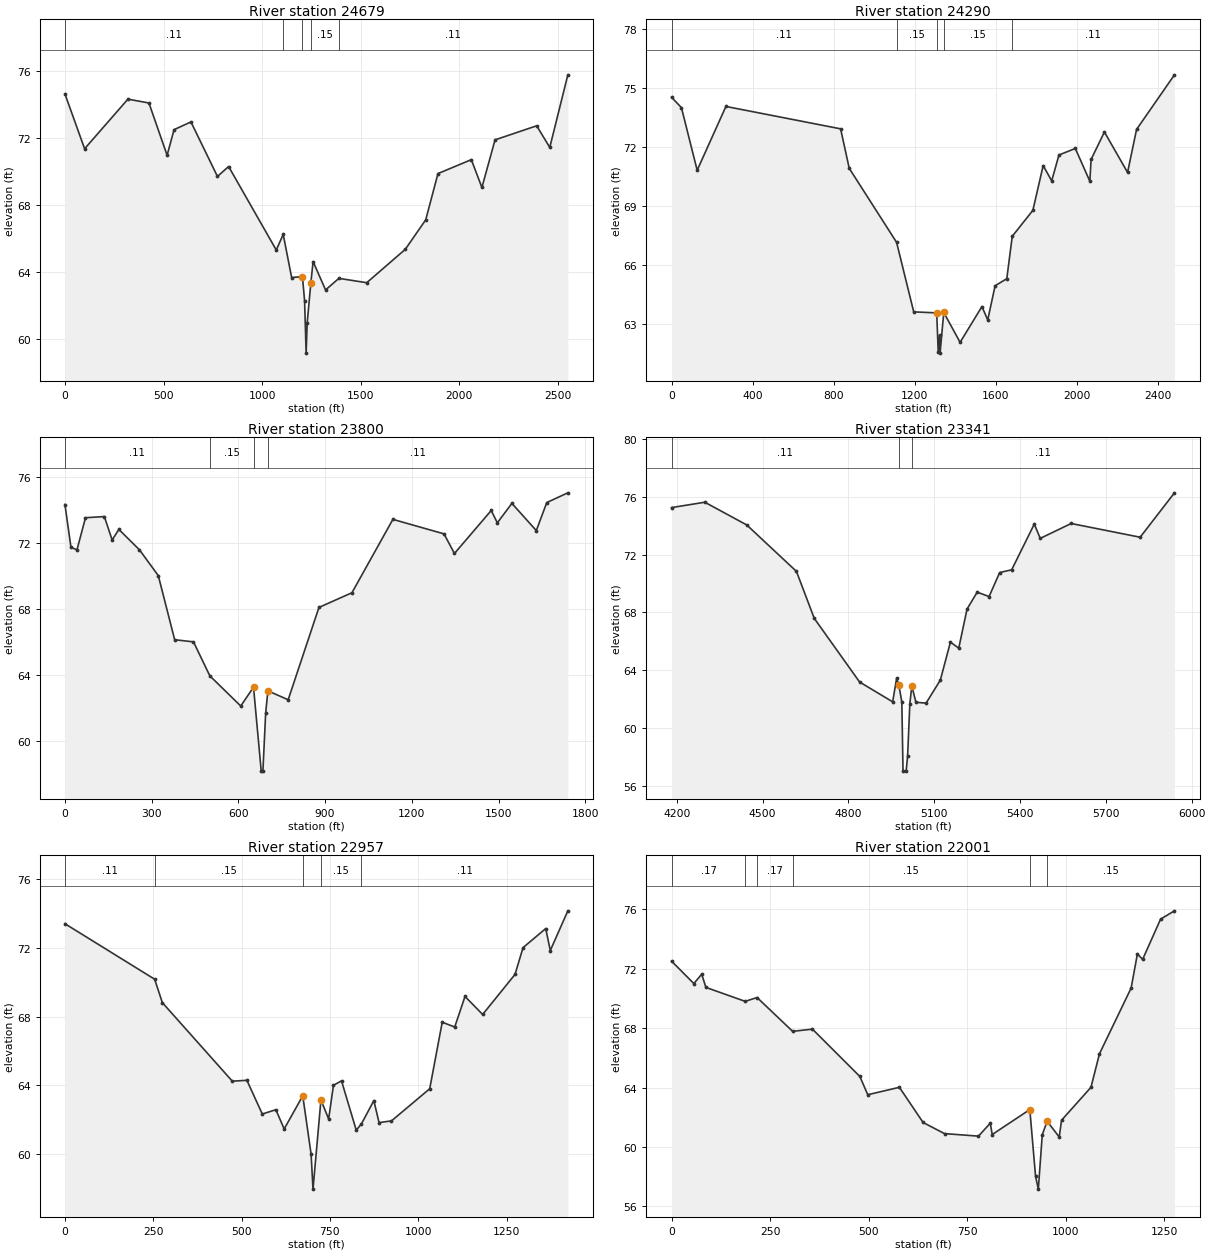
Type RM Length L Ch R = 1 ,24679   ,389,389,389
BEGIN DESCRIPTION:
BENS BRANCH 47.0
END DESCRIPTION:
XS GIS Cut Line= 5
      3918168.11     10025421.33      3917252.98     10024646.02
      3917165.67     10024610.63      3916649.18     10023542.93
      3916621.85     10023474.74
#Sta/Elev= 30
       0   74.63    99.8   71.36   319.5   74.32   426.1   74.09   518.3   70.97
   553.5    72.5   639.2   72.96   773.6   69.71   830.3    70.3    1072   65.32
  1107.2   66.25    1150   63.68  1204.9   63.73  1215.7   62.29  1223.5   59.17
  1228.9   60.98  1247.6   63.38  1258.9   64.63    1322   62.94  1389.7   63.63
  1530.8   63.37  1726.4   65.36  1830.1   67.12  1892.3   69.88  2061.5   70.71
  2115.2   69.05  2181.8   71.89  2392.9   72.73  2459.5   71.44  2551.1   75.77
#Mann= 5 ,-1 , 0
       0     .11       0  1107.2     .15       0  1204.9     .07       0
  1247.6     .15       0  1389.7     .11       0
Bank Sta=1204.9,1247.6
XS Rating Curve= 0 ,0
Exp/Cntr=0.3,0.1

Type RM Length L Ch R = 1 ,24290   ,490,490,490
BEGIN DESCRIPTION:
BENS BRANCH 46.0
END DESCRIPTION:
XS GIS Cut Line= 3
      3918288.17     10025289.51      3917389.36     10024314.23
      3916738.64     10023359.91
#Sta/Elev= 30
       0   74.54    48.8   74.01   126.5   70.82   268.3   74.07   834.2   72.93
   876.7   70.92  1110.4   67.15  1194.9   63.61  1308.3   63.56  1315.7   61.59
  1322.5   62.44    1325   61.51  1343.1   63.58  1423.7   62.06  1531.5   63.88
  1560.1    63.2  1596.4   64.94  1654.1    65.3  1681.1   67.46  1782.8   68.78
  1833.6   71.06  1875.6   70.28  1911.5    71.6  1992.2   71.93    2064   70.26
    2070   71.37  2135.8   72.77    2250   70.71  2294.4    72.9  2481.3   75.68
#Mann= 5 ,-1 , 0
       0     .11       0  1110.4     .15       0  1308.3     .09       0
  1343.1     .15       0  1681.1     .11       0
Bank Sta=1308.3,1343.1
XS Rating Curve= 0 ,0
Exp/Cntr=0.3,0.1

Type RM Length L Ch R = 1 ,23800   ,459,459,459
BEGIN DESCRIPTION:
BENS BRANCH 45.0
END DESCRIPTION:
XS GIS Cut Line= 3
      3918034.31     10024483.81      3917636.14     10023926.69
      3916949.36     10023125.77
#Sta/Elev= 30
       0   74.35    20.8   71.76    41.6    71.6    71.1   73.55   136.3   73.62
   163.3    72.2   186.6   72.84   257.9    71.6   322.9   70.04   379.6   66.15
   444.7   66.02   501.2   63.96   608.1   62.13   652.3   63.27     679   58.18
   684.8   58.18   694.3    61.7     702   63.05   772.2   62.51   878.7   68.11
   992.8      69  1134.4   73.45  1311.3   72.57  1347.3   71.38  1474.6   73.99
  1495.7   73.24    1546   74.42  1630.5   72.77  1666.7   74.47  1739.6   75.06
#Mann= 4 ,-1 , 0
       0     .11       0   501.2     .15       0   652.3     .09       0
     702     .11       0
Bank Sta=652.3,702
XS Rating Curve= 0 ,0
Exp/Cntr=0.3,0.1

Type RM Length L Ch R = 1 ,23341   ,384,384,384
BEGIN DESCRIPTION:
BENS BRANCH 44.0
END DESCRIPTION:
XS GIS Cut Line= 3
       3918268.1     10024363.23      3917949.62     10023609.44
      3917201.59     10023040.36
#Sta/Elev= 30
  4181.7   75.25    4298   75.62  4444.6   74.05  4618.3   70.84  4680.7   67.59
  4839.2   63.19  4954.8   61.82  4968.5   63.44  4976.5   62.98  4986.8    61.8
    4991   57.03  5001.9   57.03    5007   58.07  5014.8   61.67  5021.6   62.92
  5036.1   61.79  5071.5   61.73  5121.4   63.32  5156.7   65.95  5185.8   65.53
  5214.9   68.24  5250.3    69.4  5291.9    69.1  5328.9   70.76  5370.9   70.95
  5449.9   74.11  5470.7   73.12  5578.8   74.15    5820    73.2  5939.9   76.27
#Mann= 3 , 0 , 0
  4181.7     .11       0  4976.5     .06       0  5021.6     .11       0
Bank Sta=4976.5,5021.6
XS Rating Curve= 0 ,0
Exp/Cntr=0.3,0.1

Type RM Length L Ch R = 1 ,22957   ,956,956,956
BEGIN DESCRIPTION:
BENS BRANCH 43.0
END DESCRIPTION:
XS GIS Cut Line= 3
       3918548.2      10024084.5      3918270.03     10023435.46
      3917697.94     10023002.47
#Sta/Elev= 30
       0   73.41     254   70.18   275.7   68.82   473.8   64.25   515.1    64.3
   558.6   62.34   597.1   62.59   620.6   61.47   673.2    63.4   696.8   60.01
   702.2   57.97   724.7   63.16   746.5   62.05   760.1   64.01   782.9   64.27
   824.6    61.4   839.1   61.76   874.5   63.12   889.1   61.84   924.4   61.94
  1032.6   63.81    1068   67.68  1103.4    67.4  1132.5   69.18  1182.4   68.13
    1274   70.46  1296.8   72.02    1361   73.13  1373.9   71.85  1423.6   74.16
#Mann= 5 ,-1 , 0
       0     .11       0     254     .15       0   673.2     .09       0
   724.7     .15       0   839.1     .11       0
Bank Sta=673.2,724.7
XS Rating Curve= 0 ,0
Exp/Cntr=0.3,0.1

Type RM Length L Ch R = 1 ,22001   ,489,489,489
BEGIN DESCRIPTION:
BENS BRANCH 42.0
END DESCRIPTION:
XS GIS Cut Line= 3
      3918969.64     10024137.45      3918893.83     10023216.68
      3918717.85     10022911.07
#Sta/Elev= 30
       0   72.52    56.6   71.01    76.6   71.64    87.2   70.75     187   69.81
   217.1   70.07   307.4   67.79   357.6   67.94     478   64.75   498.1   63.52
   578.3   64.02   638.5   61.65   692.9    60.9     779   60.73     809    61.6
     814   60.84   909.4   62.52   923.9   58.04     931   57.16     941   60.83
   953.4   61.73   984.1   60.67   989.9    61.8  1064.6   64.02  1086.2   66.28
  1166.6   70.71  1182.4      73  1195.8   72.64  1241.3   75.35  1276.5   75.91
#Mann= 6 ,-1 , 0
       0     .17       0     187     .11       0   217.1     .17       0
   307.4     .15       0   909.4     .09       0   953.4     .15       0
Bank Sta=909.4,953.4
XS Rating Curve= 0 ,0
Exp/Cntr=0.3,0.1

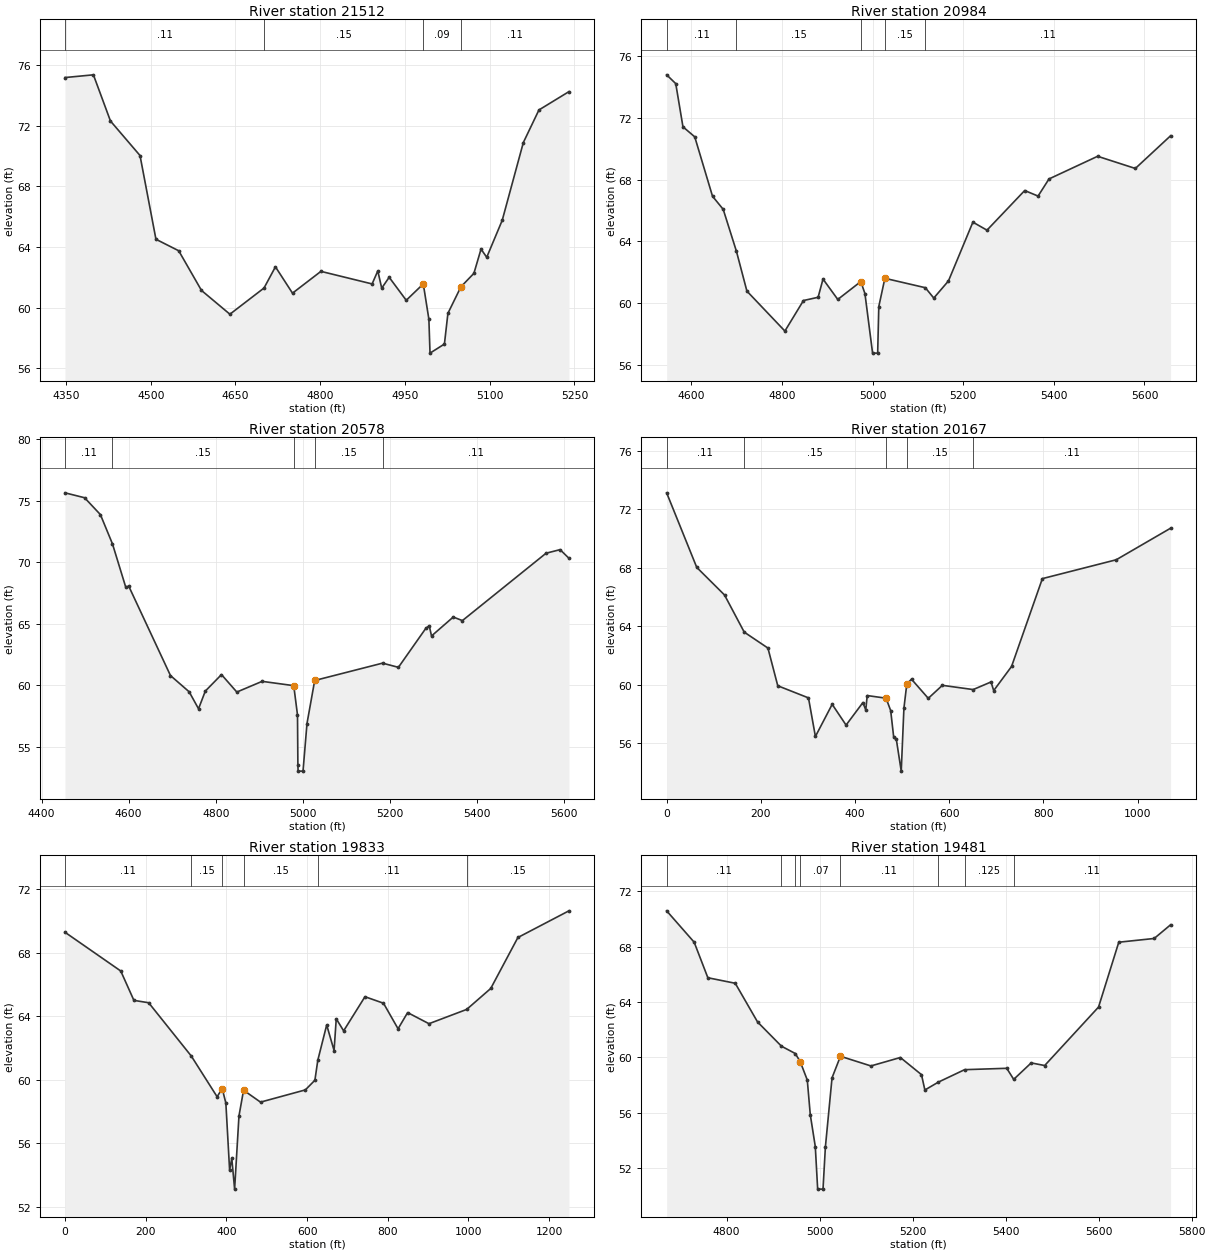
Type RM Length L Ch R = 1 ,21512   ,528,528,528
BEGIN DESCRIPTION:
BENS BRANCH 41.0
END DESCRIPTION:
XS GIS Cut Line= 3
      3919867.81     10023061.07      3919220.48     10022985.75
      3919011.76     10022866.68
#Sta/Elev= 30
  4348.3   75.19  4398.6   75.37  4428.8   72.32  4481.1   70.04  4509.3   64.51
  4549.6   63.75  4589.9   61.13  4640.2   59.56  4700.6   61.29  4720.8   62.69
    4751   60.95  4801.3   62.39  4891.9   61.56    4902   62.42  4908.9   61.28
  4922.1      62  4952.3   60.48  4982.5   61.56  4992.4   59.23  4994.4   56.99
  5019.9   57.59  5026.1   59.62  5049.1   61.37  5072.1   62.26  5084.7   63.86
  5094.8   63.32  5122.2   65.76  5159.6    70.9  5187.2   73.05  5240.3   74.26
#Mann= 4 ,-1 , 0
  4348.3     .11       0  4700.6     .15       0  4982.5     .09       0
  5049.1     .11       0
Bank Sta=4982.5,5049.1
XS Rating Curve= 0 ,0
Exp/Cntr=0.3,0.1

Type RM Length L Ch R = 1 ,20984   ,406,406,406
BEGIN DESCRIPTION:
BENS BRANCH 40.0
END DESCRIPTION:
XS GIS Cut Line= 3
      3919887.03     10022826.78        3919453.     10022692.23
      3918843.44     10022445.81
#Sta/Elev= 30
  4545.8   74.79  4565.9   74.22  4581.8   71.42  4607.8   70.77    4647   66.92
  4670.6   66.07  4699.8   63.35  4722.9   60.77  4806.7   58.18  4847.7   60.16
    4880   60.37  4890.8   61.55  4923.4   60.23  4974.2   61.39  4983.3   60.61
  5000.2   56.75  5011.4   56.75  5013.9   59.77  5027.3    61.6  5116.6   60.99
  5135.2   60.32  5167.6   61.43  5221.5   65.24  5252.6   64.72  5335.8   67.29
  5365.3   66.93  5389.4   68.04  5496.7   69.51  5579.9   68.72  5657.7   70.84
#Mann= 5 ,-1 , 0
  4545.8     .11       0  4699.8     .15       0  4974.2     .09       0
  5027.3     .15       0  5116.6     .11       0
Bank Sta=4974.2,5027.3
XS Rating Curve= 0 ,0
Exp/Cntr=0.3,0.1

Type RM Length L Ch R = 1 ,20578   ,411,411,411
BEGIN DESCRIPTION:
BENS BRANCH 39.0
END DESCRIPTION:
XS GIS Cut Line= 3
      3919967.88     10022711.09      3919500.74     10022436.16
      3918914.78     10022249.52
#Sta/Elev= 30
  4453.9   75.65  4498.9   75.25  4535.2   73.88  4562.9    71.5  4593.2      68
  4600.4   68.05  4696.1   60.79    4739   59.47  4760.5   58.09  4776.1   59.53
  4813.2   60.87  4848.4   59.45  4906.5   60.32  4979.1   59.97  4987.7   57.59
  4988.6   53.52  4989.1   53.02  5000.4   53.02  5009.5   56.89  5027.2   60.39
  5182.9    61.8  5219.4   61.46  5282.3   64.63  5290.2   64.84  5295.4   64.01
  5345.3   65.55  5366.3   65.26  5558.4   70.74  5590.6   71.03  5610.9   70.33
#Mann= 5 ,-1 , 0
  4453.9     .11       0  4562.9     .15       0  4979.1     .09       0
  5027.2     .15       0  5182.9     .11       0
Bank Sta=4979.1,5027.2
XS Rating Curve= 0 ,0
Exp/Cntr=0.3,0.1

Type RM Length L Ch R = 1 ,20167   ,334,334,334
BEGIN DESCRIPTION:
BENS BRANCH 38.0
END DESCRIPTION:
XS GIS Cut Line= 4
      3920017.85     10022511.07      3919670.01     10022262.54
      3919218.62     10022015.15      3919104.62     10021954.73
#Sta/Elev= 30
       0   73.13    63.9   68.03   122.9   66.14   164.7    63.6     215   62.51
   235.9   59.93   301.1    59.1   315.8   56.46   351.4   58.66   380.9   57.24
   416.6   58.78   422.7   58.28   425.8   59.26   465.8   59.08   475.6   58.23
   481.9   56.44   487.6   56.26     498   54.09   503.7   58.39   509.8   60.05
   519.8   60.38   555.4   59.07   585.3   59.96   650.7   59.67   688.6   60.19
   694.3    59.6   732.2   61.25   797.6   67.26   954.4   68.55  1069.8   70.71
#Mann= 5 ,-1 , 0
       0     .11       0   164.7     .15       0   465.8     .09       0
   509.8     .15       0   650.7     .11       0
Bank Sta=465.8,509.8
XS Rating Curve= 0 ,0
Exp/Cntr=0.3,0.1

Type RM Length L Ch R = 1 ,19833   ,352,352,352
BEGIN DESCRIPTION:
Mapping XS 86045e41
END DESCRIPTION:
XS GIS Cut Line= 3
      3920195.19     10022206.12      3919196.92     10021785.11
      3919029.97     10021791.53
#Sta/Elev= 30
       0   69.29   138.2   66.85   170.8      65   207.4   64.85   313.1   61.49
     377   58.93   389.7   59.44   398.7   58.53     408   54.31   413.4   55.05
   420.4   53.11   431.2   57.72   442.6   59.34   484.6   58.59   595.7   59.36
   619.4   59.97   626.6   61.23   648.6   63.45   666.9   61.84   672.3   63.84
   690.6   63.08   743.5   65.23   789.4   64.82   825.5   63.21   849.2   64.23
   902.1   63.53   995.6   64.43  1055.2   65.75  1122.5   68.96    1249   70.64
#Mann= 6 ,-1 , 0
       0     .11       0   313.1     .15       0   389.7     .09       0
   442.6     .15       0   626.6     .11       0   995.6     .15       0
Bank Sta=389.7,442.6
XS Rating Curve= 0 ,0
Exp/Cntr=0.3,0.1

Type RM Length L Ch R = 1 ,19481   ,384,384,384
BEGIN DESCRIPTION:
BENS BRANCH 37.0
END DESCRIPTION:
XS GIS Cut Line= 3
      3920303.73     10021950.06      3919995.53     10021824.18
      3919305.41     10021529.03
#Sta/Elev= 30
  4671.2    70.6  4730.4   68.33  4759.8   65.76  4818.7   65.36  4866.7   62.56
    4918   60.81  4947.7   60.28  4958.4   59.69  4973.6   58.36    4980   55.86
  4990.8   53.55  4995.9   50.47  5007.4   50.47  5012.5   53.51  5026.8   58.52
  5044.9   60.08  5110.4   59.38  5173.7   59.99  5219.1   58.75  5226.4   57.64
  5255.4   58.21  5311.8   59.11  5402.4   59.21  5417.4   58.41    5455    59.6
    5484   59.41  5599.8   63.64  5643.3   68.33  5719.4    68.6  5754.7   69.59
#Mann= 8 ,-1 , 0
  4671.2     .11       0    4918     .17       0  4947.7     .11       0
  4958.4     .07       0  5044.9     .11       0  5255.4     .17       0
  5311.8    .125       0  5417.4     .11       0
Bank Sta=4958.4,5044.9
XS Rating Curve= 0 ,0
Exp/Cntr=0.3,0.1

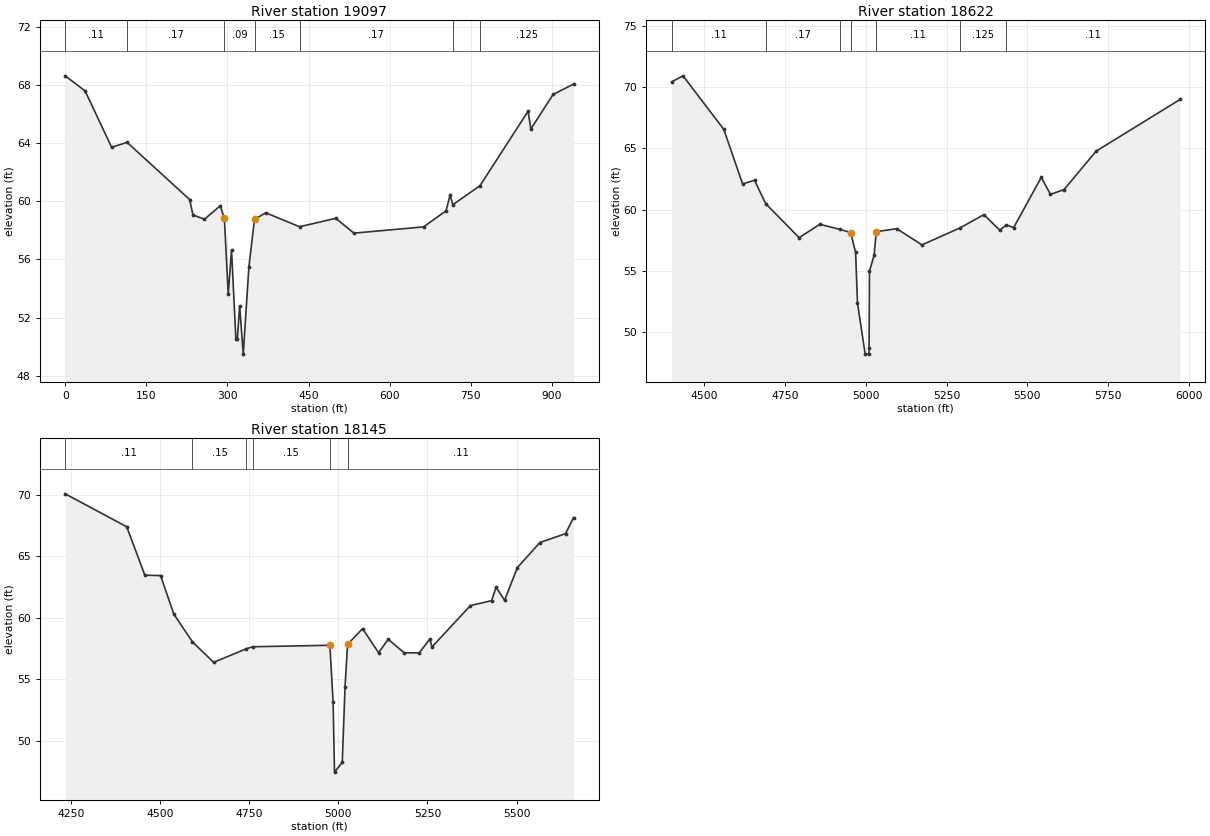
Type RM Length L Ch R = 1 ,19097   ,475,475,475
BEGIN DESCRIPTION:
BENS BRANCH 36.0
END DESCRIPTION:
XS GIS Cut Line= 3
      3920317.85     10021711.07      3920058.23     10021526.84
      3919460.52      10021352.3
#Sta/Elev= 30
       0   68.64    36.8    67.6    85.8   63.72   114.4   64.06   230.1   60.12
   236.2   59.06   257.5   58.77   286.6   59.69   294.3   58.82   301.4    53.6
   307.5   56.65   315.5   50.55   318.3   50.55   322.5   52.81   329.2   49.48
   339.6   55.49     350   58.76   370.8   59.21   433.3   58.25   500.3   58.83
   533.7   57.81   662.5   58.24   704.2   59.35   711.5   60.43   716.7   59.77
   766.7   61.07   855.7    66.2   860.9   64.98   902.1   67.36   939.8   68.07
#Mann= 7 ,-1 , 0
       0     .11       0   114.4     .17       0   294.3     .09       0
     350     .15       0   433.3     .17       0   716.7     .11       0
   766.7    .125       0
Bank Sta=294.3,350
XS Rating Curve= 0 ,0
Exp/Cntr=0.3,0.1

Type RM Length L Ch R = 1 ,18622   ,477,477,477
BEGIN DESCRIPTION:
BENS BRANCH 35.0
END DESCRIPTION:
XS GIS Cut Line= 3
      3920467.83     10021661.03      3920158.23     10021146.84
      3919427.69     10020505.38
#Sta/Elev= 30
  4399.8   70.43  4434.8   70.92  4560.9   66.56  4619.2    62.1  4656.1    62.4
  4690.7   60.49    4794   57.72  4858.1   58.81  4921.3   58.39  4953.2   58.14
  4968.8   56.51  4974.6   52.39  4998.4   48.22  5009.9   48.22  5010.4   48.72
  5011.7   54.99    5026   56.28  5032.6   58.21  5096.2   58.45    5174   57.13
  5292.9   58.53  5365.7    59.6    5415   58.32    5435   58.76  5457.7   58.54
  5543.1   62.64  5571.6   61.25  5613.4   61.64    5713   64.78  5972.2   68.99
#Mann= 7 ,-1 , 0
  4399.8     .11       0  4690.7     .17       0  4921.3     .15       0
  4953.2     .06       0  5032.6     .11       0  5292.9    .125       0
    5435     .11       0
Bank Sta=4953.2,5032.6
XS Rating Curve= 0 ,0
Exp/Cntr=0.3,0.1

Type RM Length L Ch R = 1 ,18145   ,436,436,436
BEGIN DESCRIPTION:
BENS BRANCH 34.0
END DESCRIPTION:
XS GIS Cut Line= 3
      3920517.85     10021611.09      3920388.23     10020856.84
      3920017.84     10020311.06
#Sta/Elev= 30
  4234.7   70.08  4407.2    67.4  4457.9   63.46    4502   63.43  4539.1    60.3
  4591.3   58.04  4650.7   56.37  4742.7   57.48  4760.3   57.64  4976.6   57.76
  4985.6   53.17  4989.6   47.44  5011.3   48.23  5019.1   54.38  5026.2   57.84
  5068.2   59.11  5113.1   57.16  5140.1   58.24  5184.9   57.15  5226.9   57.14
  5256.8   58.26  5262.9   57.63  5370.7   60.99    5430   61.39  5442.5   62.49
  5466.2   61.42  5502.3   64.08  5565.3   66.12  5637.2   66.84  5659.6   68.15
#Mann= 6 ,-1 , 0
  4234.7     .11       0  4591.3     .15       0  4742.7     .17       0
  4760.3     .15       0  4976.6     .06       0  5026.2     .11       0
Bank Sta=4976.6,5026.2
XS Rating Curve= 0 ,0
Exp/Cntr=0.3,0.1