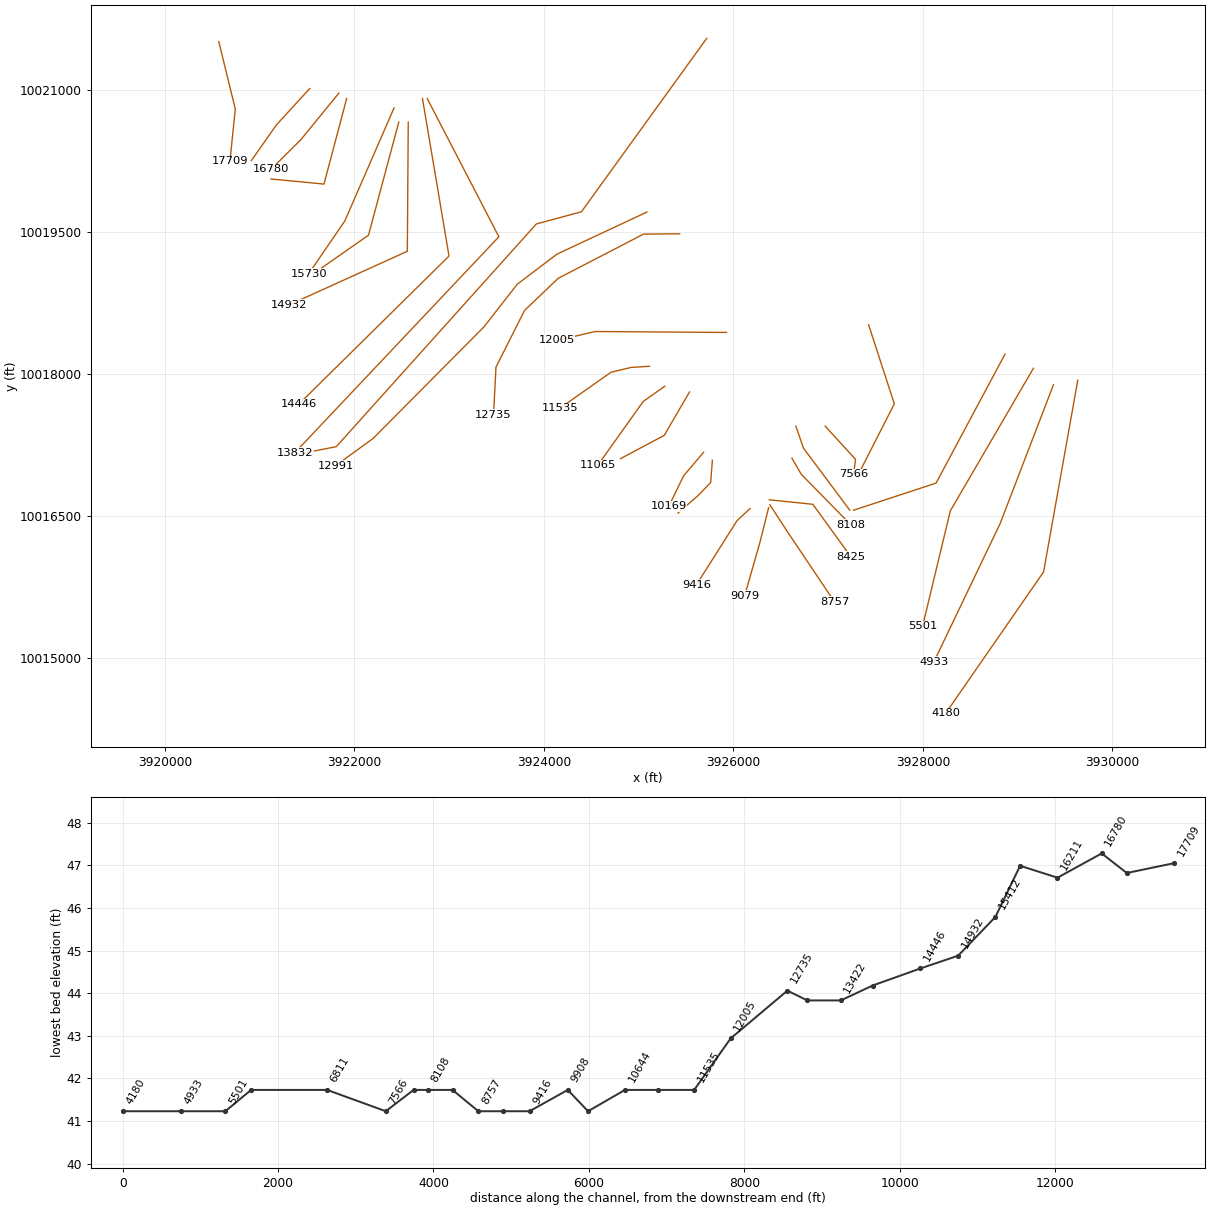
HEC-RAS study BENS BRANCH.prj: BENS BRANCH Base Level Engineering

--- BENS BRANCH.g01 (geometry) --- (continued)

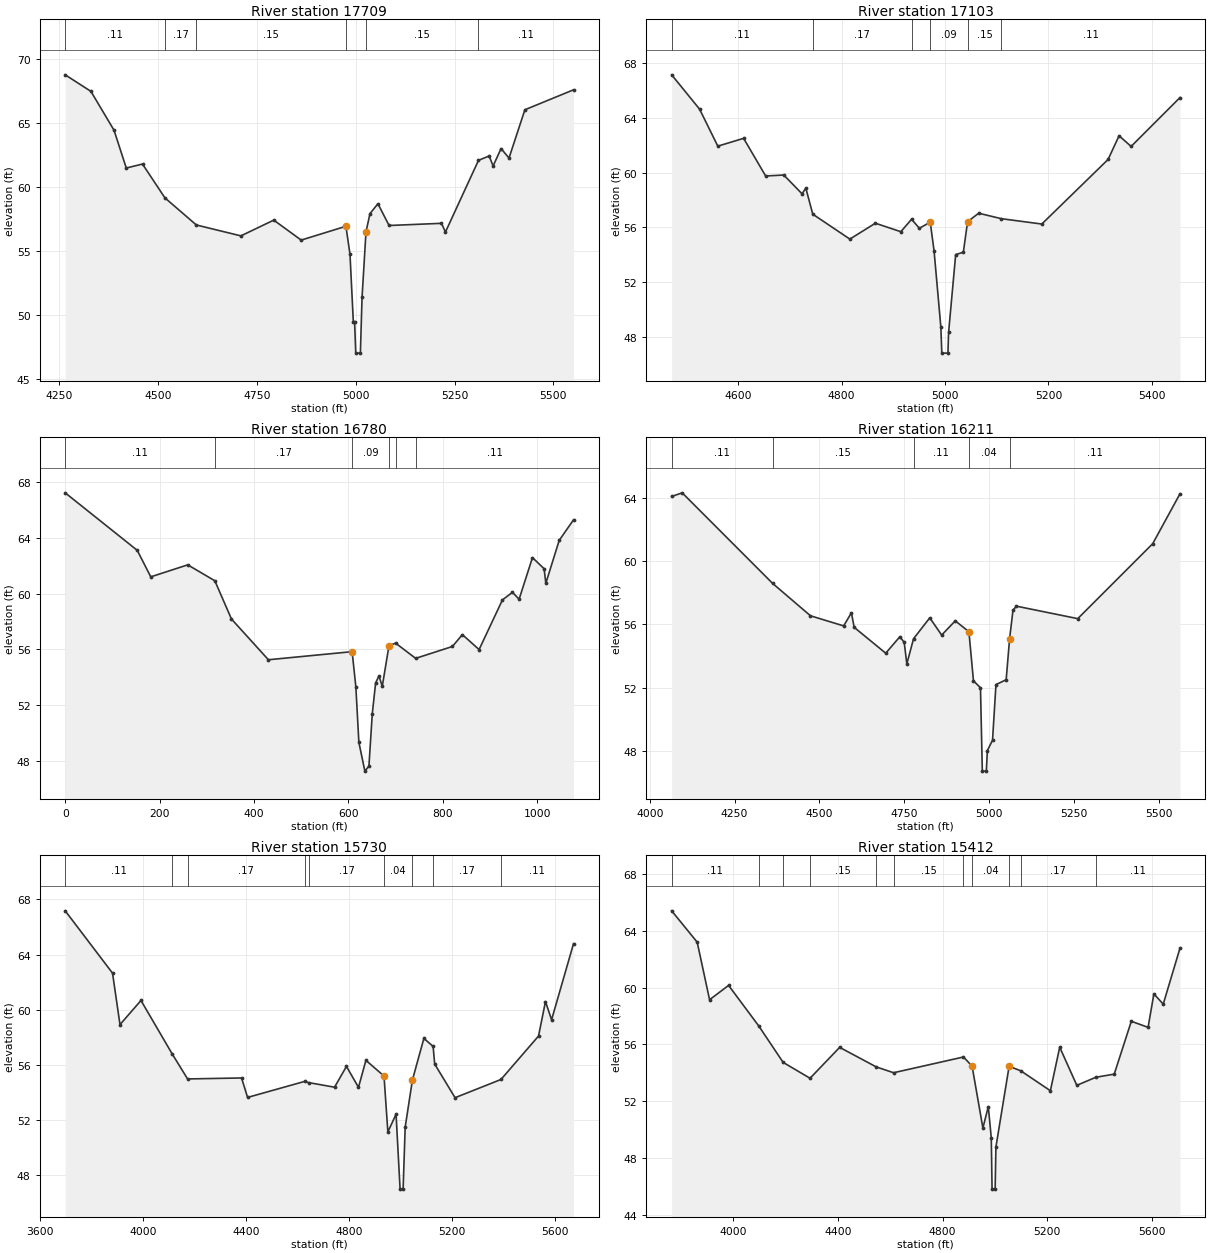
Type RM Length L Ch R = 1 ,17709   ,606,606,606
BEGIN DESCRIPTION:
BENS BRANCH 33.0
END DESCRIPTION:
XS GIS Cut Line= 3
      3920567.84      10021511.1      3920742.06     10020799.87
      3920685.63     10020248.61
#Sta/Elev= 30
  4264.7   68.79  4329.7    67.5  4388.3   64.46  4419.2   61.51  4460.3   61.82
    4517   59.18  4596.6   57.06  4709.3   56.21  4792.5   57.44  4861.9   55.88
  4975.1   56.96  4985.4   54.77  4993.8   49.52    4997   49.52    5000   47.05
  5011.7   47.05  5015.9    51.4  5025.9   56.53    5036   57.95  5056.1   58.72
  5084.3   57.02  5216.9   57.19    5227   56.51  5310.6   62.11  5337.5   62.45
  5347.6   61.67  5367.7   63.03  5387.8   62.29    5428   66.06  5551.1   67.62
#Mann= 6 ,-1 , 0
  4264.7     .11       0    4517     .17       0  4596.6     .15       0
  4975.1     .09       0  5025.9     .15       0  5310.6     .11       0
Bank Sta=4975.1,5025.9
XS Rating Curve= 0 ,0
Exp/Cntr=0.3,0.1

Type RM Length L Ch R = 1 ,17103   ,323,323,323
BEGIN DESCRIPTION:
BENS BRANCH 32.0
END DESCRIPTION:
XS GIS Cut Line= 3
      3921528.49     10021016.85      3921174.29     10020630.08
      3920911.53     10020254.53
#Sta/Elev= 30
  4471.6   67.15  4525.6   64.64  4560.8   61.94  4610.7   62.51  4653.3   59.76
  4688.4   59.83  4723.6   58.46    4731   58.87  4744.4   56.97  4816.1   55.15
  4865.4   56.31  4914.7   55.69  4935.4    56.6  4950.5   55.94  4971.5   56.39
  4978.9    54.3    4992   48.74  4993.9   46.82  5005.7   46.82    5007   48.33
  5020.7   54.02  5035.5   54.19  5043.7   56.42  5065.2   57.04  5109.2   56.64
  5187.2   56.25  5315.4   60.97  5336.6    62.7  5359.9   61.92  5454.4   65.49
#Mann= 6 ,-1 , 0
  4471.6     .11       0  4744.4     .17       0  4935.4     .15       0
  4971.5     .09       0  5043.7     .15       0  5109.2     .11       0
Bank Sta=4971.5,5043.7
XS Rating Curve= 0 ,0
Exp/Cntr=0.3,0.1

Type RM Length L Ch R = 1 ,16780   ,569,569,569
BEGIN DESCRIPTION:
BENS BRANCH 31.0
END DESCRIPTION:
XS GIS Cut Line= 4
      3921835.75     10020968.62      3921434.71     10020476.43
      3921167.85     10020211.07      3921120.25     10020163.06
#Sta/Elev= 30
       0   67.22   152.6    63.1   181.3    61.2   259.6   62.06     317   60.92
   352.2   58.18   430.5   55.26   607.9   55.84   615.8   53.32   622.2   49.34
   634.9   47.28   643.5   47.64   650.6   51.39   657.7    53.6   664.7    54.1
   671.8   53.36     686   56.27   700.1   56.45   742.5   55.36   820.3   56.21
   841.5   57.06   876.9   55.99   926.4   59.55   947.6   60.09   961.7    59.6
     990   62.58  1014.7   61.78  1018.3   60.74  1046.6   63.81    1077   65.29
#Mann= 6 ,-1 , 0
       0     .11       0     317     .17       0   607.9     .09       0
     686     .17       0   700.1     .15       0   742.5     .11       0
Bank Sta=607.9,686
XS Rating Curve= 0 ,0
Exp/Cntr=0.3,0.1

Type RM Length L Ch R = 1 ,16211   ,481,481,481
BEGIN DESCRIPTION:
BENS BRANCH 30.0
END DESCRIPTION:
XS GIS Cut Line= 3
      3921917.84     10020911.03      3921678.23     10020006.84
      3921117.85     10020061.07
#Sta/Elev= 30
  4064.6   64.11  4095.6   64.34  4362.3    58.6  4473.8   56.55  4571.5   55.91
  4594.5   56.74  4602.5   55.82  4695.6   54.18    4737   55.22  4750.1   54.87
  4757.7    53.5  4777.6    55.1  4825.4   56.42  4860.4   55.33  4900.6   56.23
  4940.8   55.54  4954.2   52.43  4974.9   51.99  4980.3   46.71  4992.1   46.71
  4995.2   48.01  5010.4   48.67  5020.5   52.19  5050.6    52.5  5060.7    55.1
  5070.7    56.9  5080.8   57.16  5261.6   56.37  5482.6   61.12    5563   64.28
#Mann= 5 ,-1 , 0
  4064.6     .11       0  4362.3     .15       0  4777.6     .11       0
  4940.8     .04       0  5060.7     .11       0
Bank Sta=4940.8,5060.7
XS Rating Curve= 0 ,0
Exp/Cntr=0.3,0.1

Type RM Length L Ch R = 1 ,15730   ,318,318,318
BEGIN DESCRIPTION:
BENS BRANCH 29.0
END DESCRIPTION:
XS GIS Cut Line= 3
      3922417.86     10020811.09      3921898.23     10019616.84
      3921517.84     10019061.05
#Sta/Elev= 30
  3697.6   67.17  3881.6   62.65  3910.5   58.92  3992.1   60.67  4114.2   56.77
  4173.3   54.98  4383.1   55.05  4406.5   53.64  4628.2    54.8  4645.3   54.71
  4744.6   54.38  4790.8   55.89  4837.6   54.37  4866.5   56.33  4936.8   55.19
  4951.8   51.14  4983.7   52.42  4999.3   46.99  5011.1   46.99  5019.1   51.48
  5047.2    54.9  5091.8   57.92  5127.7   57.34  5133.8   56.06    5213   53.62
  5391.4   54.94  5537.4   58.09  5564.4   60.59  5588.2   59.27  5673.5   64.79
#Mann= 9 ,-1 , 0
  3697.6     .11       0  4114.2     .15       0  4173.3     .17       0
  4628.2     .15       0  4645.3     .17       0  4936.8     .04       0
  5047.2     .15       0  5127.7     .17       0  5391.4     .11       0
Bank Sta=4936.8,5047.2
XS Rating Curve= 0 ,0
Exp/Cntr=0.3,0.1

Type RM Length L Ch R = 1 ,15412   ,480,480,480
BEGIN DESCRIPTION:
BENS BRANCH 28.0
END DESCRIPTION:
XS GIS Cut Line= 3
      3922467.86     10020661.11      3922148.23     10019466.84
      3921567.82     10019061.05
#Sta/Elev= 30
  3763.7   65.42  3861.3   63.21  3908.7   59.15  3981.4   60.16  4097.2   57.29
  4190.1   54.73    4293   53.61  4406.3   55.79  4546.3   54.41  4612.6      54
  4879.9   55.11  4912.8   54.47  4954.2    50.1  4974.9   51.61  4986.3    49.4
  4989.3   45.79  5001.1   45.79    5004   48.76  5054.5   54.45  5098.8   54.14
  5212.4   52.73  5248.1    55.8  5313.5   53.11  5386.2   53.68  5456.6    53.9
    5522   57.63  5586.1    57.2  5608.3   59.56  5644.1   58.84  5708.2   62.79
#Mann= 11 ,-1 , 0
  3763.7     .11       0  4097.2     .15       0  4190.1     .17       0
    4293     .15       0  4546.3     .17       0  4612.6     .15       0
  4879.9     .17       0  4912.8     .04       0  5054.5     .15       0
  5098.8     .17       0  5386.2     .11       0
Bank Sta=4912.8,5054.5
XS Rating Curve= 0 ,0
Exp/Cntr=0.3,0.1

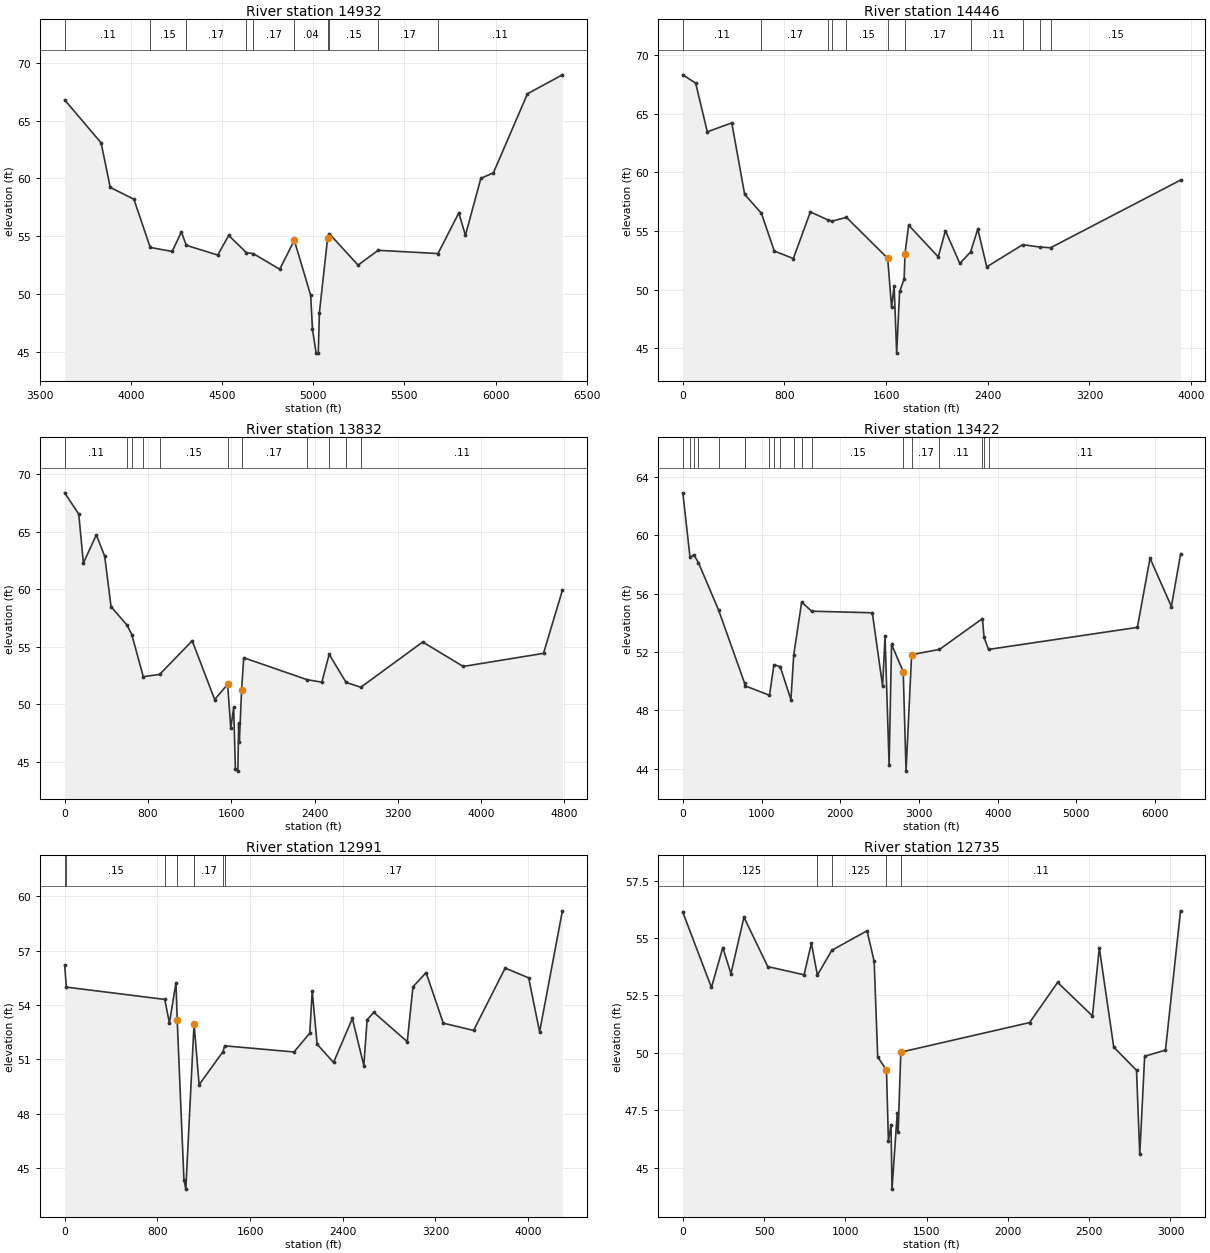
Type RM Length L Ch R = 1 ,14932   ,486,486,486
BEGIN DESCRIPTION:
BENS BRANCH 27.0
END DESCRIPTION:
XS GIS Cut Line= 3
      3922567.85     10020661.11      3922558.23     10019296.84
      3921313.21     10018732.15
#Sta/Elev= 30
  3635.7    66.8  3835.7   63.08  3885.7   59.23  4015.7    58.2  4105.2   54.03
  4225.8   53.68  4275.8   55.37  4303.4   54.21  4475.8   53.37  4535.8   55.07
  4632.9   53.58  4671.5   53.49  4815.8   52.14  4895.8   54.65  4985.8   49.88
  4995.4   46.97  5015.6   44.88  5027.4   44.88  5033.4   48.36  5078.6   54.83
  5088.3   55.21  5245.7    52.5  5355.9   53.78  5684.4    53.5  5798.6   57.02
  5834.9   55.08  5919.6   60.01  5988.7   60.49  6175.3   67.33  6367.1   68.97
#Mann= 10 ,-1 , 0
  3635.7     .11       0  4105.2     .15       0  4303.4     .17       0
  4632.9     .15       0  4671.5     .17       0  4895.8     .04       0
  5078.6     .12       0  5088.3     .15       0  5355.9     .17       0
  5684.4     .11       0
Bank Sta=4895.8,5078.6
XS Rating Curve= 0 ,0
Exp/Cntr=0.3,0.1

Type RM Length L Ch R = 1 ,14446   ,614,614,614
BEGIN DESCRIPTION:
BENS BRANCH 26.0
END DESCRIPTION:
XS GIS Cut Line= 3
      3922717.85     10020911.07      3922998.23     10019246.84
      3921410.61     10017679.66
#Sta/Elev= 30
       0   68.32   101.4   67.61   192.7   63.46   385.4   64.22   486.8   58.12
   618.6   56.51     720   53.29   869.9   52.65    1004   56.63  1145.9   55.92
  1177.6   55.85  1287.9   56.16  1612.4   52.67  1642.8    48.5  1663.1    50.3
    1683   44.58  1706.2   49.84  1741.6   50.88  1748.6   53.06  1776.9    55.5
  2010.3   52.79  2066.8   55.02    2180   52.23  2264.8   53.21  2321.3   55.16
    2392   51.94  2674.9   53.83  2809.3   53.63  2894.2   53.57  3916.9   59.34
#Mann= 11 ,-1 , 0
       0     .11       0   618.6     .17       0  1145.9     .15       0
  1177.6     .17       0  1287.9     .15       0  1612.4     .04       0
  1748.6     .17       0  2264.8     .11       0  2674.9     .15       0
  2809.3    .125       0  2894.2     .15       0
Bank Sta=1612.4,1748.6
XS Rating Curve= 0 ,0
Exp/Cntr=0.3,0.1

Type RM Length L Ch R = 1 ,13832   ,410,410,410
BEGIN DESCRIPTION:
BENS BRANCH 25.0
END DESCRIPTION:
XS GIS Cut Line= 3
      3922767.85     10020911.07      3923524.69      10019450.3
      3921371.01     10017169.24
#Sta/Elev= 30
       0    68.4   135.2   66.55   179.7   62.29   304.1   64.74   384.5   62.88
   445.2    58.5   600.2   56.87   644.4   56.07   755.1    52.4   912.3    52.6
  1225.1   55.52  1440.8   50.41  1565.5   51.74  1595.7   47.91  1623.4   49.73
  1639.9   44.36  1663.6   44.18  1670.9   48.33  1677.8   46.68  1699.1   51.21
  1720.2   54.05  2328.7   52.14  2469.9   51.92  2540.7   54.34  2703.3    51.9
  2844.9   51.48  3439.2   55.42  3828.4   53.29  4599.5   54.43    4781   59.92
#Mann= 11 ,-1 , 0
       0     .11       0   600.2     .17       0   644.4     .15       0
   755.1     .17       0   912.3     .15       0  1565.5     .04       0
  1699.1     .17       0  2328.7     .11       0  2540.7     .15       0
  2703.3    .125       0  2844.9     .11       0
Bank Sta=1565.5,1699.1
XS Rating Curve= 0 ,0
Exp/Cntr=0.3,0.1

Type RM Length L Ch R = 1 ,13422   ,431,431,431
BEGIN DESCRIPTION:
Mapping XS 59f4de35
END DESCRIPTION:
XS GIS Cut Line= 5
      3925719.01     10021546.49      3924396.22     10019714.18
      3923920.53     10019585.71      3921808.28      10017232.9
      3921407.81      10017153.7
#Sta/Elev= 30
       0    62.9    91.4    58.5   141.7   58.64   198.1   58.12   455.8   54.85
   784.6   49.86   793.1   49.67  1101.1   49.03  1157.5   51.12  1237.2   50.99
  1373.4   48.73    1409   51.78  1509.6   55.41  1637.2   54.79  2407.2   54.68
  2537.9   49.67    2569   53.06  2620.7   44.25  2651.8   52.52    2800   50.64
  2835.9   43.83  2906.7   51.81  3260.5   52.17  3806.2   54.28  3827.1   52.99
  3883.9   52.17  5774.4   53.68  5935.3   58.42  6206.4   55.11  6322.7   58.69
#Mann= 19 ,-1 , 0
       0     .15       0    91.4    .125       0   141.7     .11       0
   198.1    .125       0   455.8     .11       0   784.6    .125       0
   793.1     .11       0  1101.1    .125       0  1157.5    .125       0
  1237.2     .15       0    1409     .11       0  1509.6     .15       0
  1637.2     .15       0    2800     .04       0  2906.7     .17       0
  3260.5     .11       0  3806.2     .15       0  3827.1    .125       0
  3883.9     .11       0
Bank Sta=2800,2906.7
XS Rating Curve= 0 ,0
Exp/Cntr=0.3,0.1

Type RM Length L Ch R = 1 ,12991   ,256,256,256
BEGIN DESCRIPTION:
BENS BRANCH 24.0
END DESCRIPTION:
XS GIS Cut Line= 6
      3925087.55     10019711.34      3924138.23     10019266.84
       3923717.9     10018948.22      3923368.94      10018500.3
      3922197.93     10017320.59      3921800.03     10017031.04
#Sta/Elev= 30
       0   56.19    14.3   54.98   863.9    54.3   904.1      53   960.8   55.23
   971.4   53.14  1029.3   44.36  1045.7   43.83  1116.7   52.96  1160.4   49.59
  1366.4   51.42  1380.9   51.74  1979.2    51.4  2115.8   52.44  2136.6   54.77
  2179.1   51.83  2320.5   50.82  2483.1   53.25  2582.1   50.65  2610.4   53.17
    2667   53.59  2956.9   51.97  3006.4      55  3119.5   55.78    3268   52.99
  3529.6   52.59  3802.2   56.03  4005.1   55.49  4099.4   52.51  4296.1   59.19
#Mann= 7 ,-1 , 0
       0    .125       0    14.3     .15       0   863.9     .11       0
   971.4     .04       0  1116.7     .17       0  1366.4     .15       0
  1380.9     .17       0
Bank Sta=971.4,1116.7
XS Rating Curve= 0 ,0
Exp/Cntr=0.3,0.1

Type RM Length L Ch R = 1 ,12735   ,730,730,730
BEGIN DESCRIPTION:
Mapping XS 12c5b649
END DESCRIPTION:
XS GIS Cut Line= 6
      3925433.94     10019481.59      3925052.35      10019478.3
      3924150.19     10019010.72      3923796.02     10018672.18
      3923493.94     10018073.22      3923468.28     10017570.63
#Sta/Elev= 30
       0   56.13   176.1   52.85   246.1   54.59   296.1   53.45   376.1   55.91
   522.6   53.76   746.1    53.4   791.1   54.78   827.9   53.39   916.8   54.47
  1133.3   55.32  1177.1   53.99    1199   49.82  1252.9   49.25  1264.8   46.15
    1281   46.87  1286.9   44.06  1319.2   47.38  1324.9   46.56  1341.1   50.03
  2133.5   51.32  2305.8   53.07  2519.9   51.61  2562.2   54.58  2650.9   50.25
  2791.1   49.24  2811.1   45.57  2841.2   49.85  2969.3   50.12  3061.9   56.19
#Mann= 5 ,-1 , 0
       0    .125       0   827.9     .11       0   916.8    .125       0
  1252.9     .04       0  1341.1     .11       0
Bank Sta=1252.9,1341.1
XS Rating Curve= 0 ,0
Exp/Cntr=0.3,0.1

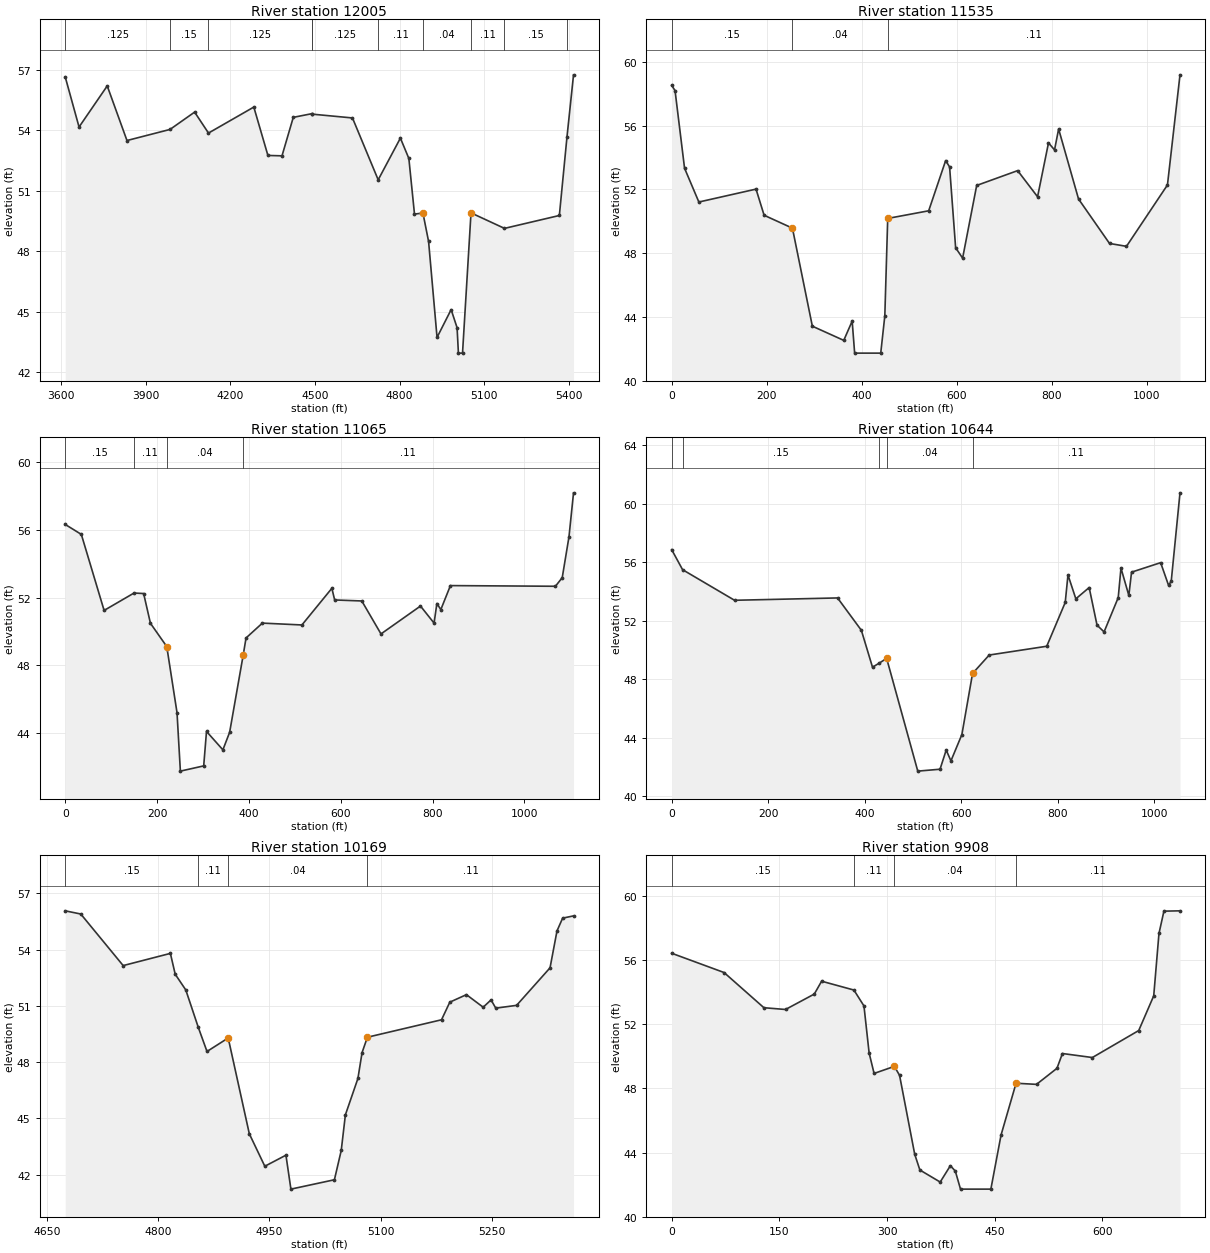
Type RM Length L Ch R = 1 ,12005   ,470,470,470
BEGIN DESCRIPTION:
BENS BRANCH 23.0
END DESCRIPTION:
XS GIS Cut Line= 3
      3925926.95      10018439.5      3924540.89     10018449.19
      3924134.58     10018354.47
#Sta/Elev= 30
  3613.9   56.65    3663   54.16    3763    56.2    3833   53.49  3985.7   54.04
    4073    54.9  4122.2   53.86    4283   55.15    4333   52.75    4383   52.73
    4423   54.64  4488.2   54.82  4489.2    54.8    4633   54.61  4724.2   51.54
    4803   53.61    4833    52.6    4853   49.84    4883   49.89    4903   48.48
    4933   43.72    4983    45.1  5004.1    44.2  5008.8   42.94  5023.4   42.94
  5053.5    49.9  5172.3   49.13  5366.9   49.77    5394   53.67  5417.2   56.75
#Mann= 10 ,-1 , 0
  3613.9    .125       0  3985.7     .15       0  4122.2    .125       0
  4488.2     .11       0  4489.2    .125       0  4724.2     .11       0
    4883     .04       0  5053.5     .11       0  5172.3     .15       0
    5394     .17       0
Bank Sta=4883,5053.5
XS Rating Curve= 0 ,0
Exp/Cntr=0.3,0.1

Type RM Length L Ch R = 1 ,11535   ,470,470,470
BEGIN DESCRIPTION:
BENS BRANCH 22.0
END DESCRIPTION:
XS GIS Cut Line= 4
      3925114.93     10018082.29      3924918.89     10018069.57
      3924707.56     10018018.63      3924170.57     10017639.76
#Sta/Elev= 30
       0   58.53     7.1    58.2    27.1   53.33    57.2   51.21   177.5   52.02
   194.5   50.38   254.1   49.57     296   43.42   362.1   42.53   379.8   43.74
     385   41.73   439.9   41.73   448.5   44.07   454.6   50.18   540.8   50.66
   576.5   53.81   584.8   53.41   597.5   48.34   612.2   47.69   641.8   52.25
     728   53.18   769.9   51.54   792.9   54.92   805.6   54.48   814.2   55.79
   856.1    51.4   921.3   48.61     957   48.43  1043.2   52.28  1069.6   59.19
#Mann= 3 , 0 , 0
       0     .15       0   254.1     .04       0   454.6     .11       0
Bank Sta=254.1,454.6
XS Rating Curve= 0 ,0
Exp/Cntr=0.3,0.1

Type RM Length L Ch R = 1 ,11065   ,421,421,421
BEGIN DESCRIPTION:
BENS BRANCH 21.0
END DESCRIPTION:
XS GIS Cut Line= 3
      3925276.47     10017871.85      3925047.83      10017709.6
      3924568.14      10017035.6
#Sta/Elev= 30
       0   56.33    35.1   55.74    84.7   51.24   149.9   52.27   170.8   52.24
   185.6   50.48   221.2    49.1   243.5   45.19   250.8   41.73   301.6   42.04
   307.7   44.08   343.4   42.99   358.1   44.03   387.7   48.61   393.8   49.61
   429.4   50.49   515.5   50.38   580.7   52.55   586.8   51.86   645.9    51.8
   687.7   49.85   773.7    51.5   803.3   50.49   809.4   51.65     818   51.29
   838.9   52.71  1067.6   52.67  1082.4   53.18  1097.1    55.6    1107    58.2
#Mann= 4 ,-1 , 0
       0     .15       0   149.9     .11       0   221.2     .04       0
   387.7     .11       0
Bank Sta=221.2,387.7
XS Rating Curve= 0 ,0
Exp/Cntr=0.3,0.1

Type RM Length L Ch R = 1 ,10644   ,475,475,475
BEGIN DESCRIPTION:
BENS BRANCH 20.0
END DESCRIPTION:
XS GIS Cut Line= 3
      3925537.31      10017810.6      3925270.06     10017351.96
      3924809.04     10017106.39
#Sta/Elev= 30
       0   56.86    22.6   55.49   130.3    53.4   343.7   53.56     393   51.35
   416.1   48.83   429.7    49.1   445.4   49.43   509.9   41.73     556   41.86
   568.8   43.17   578.6   42.43   601.3   44.23   623.4    48.4   657.9   49.66
   777.1   50.26   815.4   53.25   821.1   55.13   837.4    53.5     865   54.27
   881.3    51.7   895.9   51.24   925.2   53.58   930.9    55.6   947.2   53.73
   952.8   55.32  1013.1   55.97  1029.4   54.43    1035   54.69  1053.2   60.74
#Mann= 5 ,-1 , 0
       0    .125       0    22.6     .15       0   429.7     .11       0
   445.4     .04       0   623.4     .11       0
Bank Sta=445.4,623.4
XS Rating Curve= 0 ,0
Exp/Cntr=0.3,0.1

Type RM Length L Ch R = 1 ,10169   ,261,261,261
BEGIN DESCRIPTION:
BENS BRANCH 19.0
END DESCRIPTION:
XS GIS Cut Line= 3
      3925685.63     10017173.11      3925474.92     10016924.88
       3925317.3       10016601.
#Sta/Elev= 30
  4674.4   56.07  4695.4    55.9  4752.6   53.15  4816.3    53.8  4822.8   52.69
  4837.1   51.85    4854   49.85  4865.7   48.57  4894.3   49.29  4922.8   44.18
  4943.7   42.45  4972.2   43.04  4978.9   41.23  5037.6   41.73  5046.8   43.29
  5052.4   45.19  5069.3   47.13  5074.9   48.51  5082.1   49.33  5182.1   50.26
  5193.3    51.2  5215.7    51.6  5238.3   50.93  5248.9   51.32  5255.3   50.88
  5283.4   51.03  5328.5   53.03  5337.9      55  5345.5   55.68  5360.2    55.8
#Mann= 4 ,-1 , 0
  4674.4     .15       0    4854     .11       0  4894.3     .04       0
  5082.1     .11       0
Bank Sta=4894.3,5082.1
XS Rating Curve= 0 ,0
Exp/Cntr=0.3,0.1

Type RM Length L Ch R = 1 ,9908    ,492,492,492
BEGIN DESCRIPTION:
BENS BRANCH 18.0
END DESCRIPTION:
XS GIS Cut Line= 4
      3925778.38     10017089.17      3925760.44     10016854.19
      3925628.13     10016716.98      3925415.82     10016531.55
#Sta/Elev= 30
       0   56.41      73   55.21   128.5   53.02   158.6   52.91   198.7   53.87
   208.9   54.67   253.9   54.12   267.9   53.13   275.1    50.2     282   48.93
   310.3   49.37   317.5   48.81   338.6    43.9   345.8   42.92   374.1   42.17
   388.3   43.19   395.2   42.85   402.4   41.73   444.7   41.73   458.9    45.1
   479.8   48.32   508.3   48.25   536.8   49.25   544.4   50.17   586.1   49.92
   650.7    51.6   671.6   53.76   678.9   57.64   685.8   59.03   708.2   59.05
#Mann= 4 ,-1 , 0
       0     .15       0   253.9     .11       0   310.3     .04       0
   479.8     .11       0
Bank Sta=310.3,479.8
XS Rating Curve= 0 ,0
Exp/Cntr=0.3,0.1

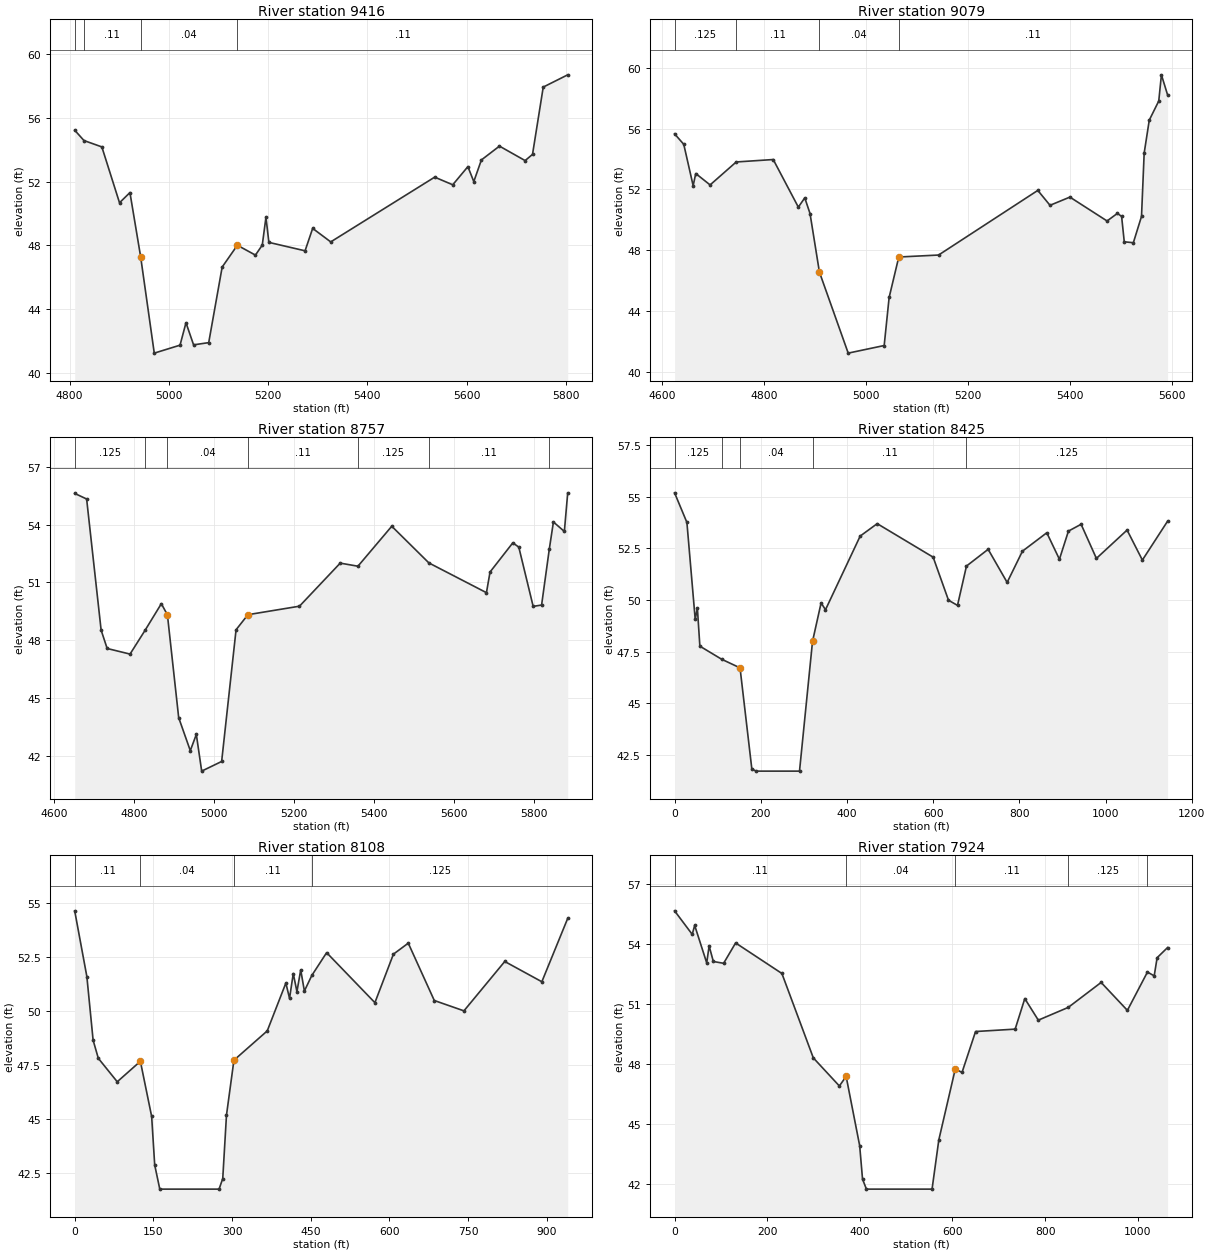
Type RM Length L Ch R = 1 ,9416    ,337,337,337
BEGIN DESCRIPTION:
BENS BRANCH 17.0
END DESCRIPTION:
XS GIS Cut Line= 3
      3926177.02     10016579.43      3926038.28     10016450.05
      3925608.53     10015771.14
#Sta/Elev= 30
  4810.3   55.24    4829   54.59    4865   54.19  4900.6   50.68  4921.6   51.32
  4943.1    47.3  4970.6   41.23  5022.5   41.73  5034.5   43.14  5049.8   41.75
  5080.3   41.89  5107.4   46.64    5138   48.01  5174.4   47.39  5188.2   48.02
  5195.6   49.77  5201.5   48.19  5274.4   47.66  5289.7   49.07  5326.1   48.22
  5535.5   52.29  5571.9   51.81  5602.4   52.95  5614.3   52.01  5629.6   53.37
    5666   54.24  5717.7   53.33  5732.6   53.72  5754.2   57.95  5803.5   58.72
#Mann= 4 ,-1 , 0
  4810.3    .125       0    4829     .11       0  4943.1     .04       0
    5138     .11       0
Bank Sta=4943.1,5138
XS Rating Curve= 0 ,0
Exp/Cntr=0.3,0.1

Type RM Length L Ch R = 1 ,9079    ,322,322,322
BEGIN DESCRIPTION:
BENS BRANCH 16.0
END DESCRIPTION:
XS GIS Cut Line= 3
      3926372.36     10016588.56      3926281.34     10016224.36
      3926118.93     10015656.53
#Sta/Elev= 30
  4624.6   55.65  4642.6   54.96    4661   52.24  4666.1   53.04  4694.2   52.29
  4745.4    53.8  4817.9   53.96  4867.1   50.83  4879.7   51.44    4890   50.41
  4908.4   46.56  4964.8   41.23  5035.3   41.73    5045   44.89  5063.9   47.55
  5141.9   47.68  5336.3   51.93  5360.2   50.95  5399.2   51.49    5472   49.92
  5492.3   50.42  5500.5   50.22  5505.7   48.55  5523.5   48.49  5539.5   50.22
  5544.7   54.38  5554.7   56.55  5573.3   57.81  5578.5   59.53  5590.6   58.21
#Mann= 4 ,-1 , 0
  4624.6    .125       0  4745.4     .11       0  4908.4     .04       0
  5063.9     .11       0
Bank Sta=4908.4,5063.9
XS Rating Curve= 0 ,0
Exp/Cntr=0.3,0.1

Type RM Length L Ch R = 1 ,8757    ,332,332,332
BEGIN DESCRIPTION:
BENS BRANCH 15.0
END DESCRIPTION:
XS GIS Cut Line= 3
      3926385.25     10016619.24      3926570.79     10016334.35
      3927069.04     10015591.32
#Sta/Elev= 30
  4650.9   55.61  4680.8   55.32  4717.1   48.53  4732.2   47.58  4789.5   47.29
  4827.4   48.53  4867.9    49.9  4883.1   49.32  4911.3      44  4940.4   42.29
  4955.5   43.13  4968.9   41.23  5018.9   41.73    5055   48.55  5084.7   49.33
  5213.8   49.77  5315.8      52  5360.2   51.84  5444.9   53.91  5537.9   52.01
    5682   50.47    5691   51.54    5748   53.05    5763   52.83    5799   49.76
  5820.1   49.83  5839.5   52.74  5849.7   54.13  5877.1   53.64  5885.5   55.64
#Mann= 7 ,-1 , 0
  4650.9    .125       0  4827.4     .11       0  4883.1     .04       0
  5084.7     .11       0  5360.2    .125       0  5537.9     .11       0
  5839.5    .125       0
Bank Sta=4883.1,5084.7
XS Rating Curve= 0 ,0
Exp/Cntr=0.3,0.1

Type RM Length L Ch R = 1 ,8425    ,317,317,317
BEGIN DESCRIPTION:
Mapping XS 6bd18065
END DESCRIPTION:
XS GIS Cut Line= 3
      3926379.45     10016671.41      3926838.66     10016624.09
      3927239.48      10016071.8
#Sta/Elev= 30
       0   55.18    28.6   53.75    47.9   49.06    52.9   49.61    58.7   47.77
     109   47.14   151.9   46.72   179.3   41.83   189.4   41.73   289.9   41.73
   320.1      48     340   49.86   350.2   49.53   430.7   53.09   470.2   53.69
     600   52.07   635.6   49.99   656.5   49.74   677.3   51.64   727.6   52.45
   771.7   50.85   807.2   52.36   863.7   53.25     893   51.97   913.9   53.33
   943.3   53.66   978.8   52.01    1050   53.38  1085.5   51.93    1144   53.81
#Mann= 5 ,-1 , 0
       0    .125       0     109     .11       0   151.9     .04       0
   320.1     .11       0   677.3    .125       0
Bank Sta=151.9,320.1
XS Rating Curve= 0 ,0
Exp/Cntr=0.3,0.1

Type RM Length L Ch R = 1 ,8108    ,184,184,184
BEGIN DESCRIPTION:
BENS BRANCH 14.0
END DESCRIPTION:
XS GIS Cut Line= 3
      3926617.85     10017111.07      3926717.54     10016940.51
      3927236.87     10016410.34
#Sta/Elev= 30
       0   54.64    23.2   51.59    35.1   48.64      45    47.8    81.1   46.71
   125.2   47.66   146.7    45.1   152.5   42.85   162.2   41.73   275.2   41.73
   282.2   42.22   289.3   45.16   303.5   47.71     367   49.07   402.5   51.29
   409.5   50.58   416.6   51.73   423.6   50.89   430.8    51.9   437.8   50.92
   451.9   51.64   480.2    52.7   572.2   50.38   607.5   52.63   635.8   53.14
   685.4   50.48   741.9      50   819.7   52.29   890.4   51.35   939.7   54.29
#Mann= 4 ,-1 , 0
       0     .11       0   125.2     .04       0   303.5     .11       0
   451.9    .125       0
Bank Sta=125.2,303.5
XS Rating Curve= 0 ,0
Exp/Cntr=0.3,0.1

Type RM Length L Ch R = 1 ,7924    ,358,358,358
BEGIN DESCRIPTION:
Mapping XS ad9266ad
END DESCRIPTION:
XS GIS Cut Line= 3
      3926659.79     10017450.19      3926739.71     10017217.82
        3927229.     10016561.41
#Sta/Elev= 30
       0   55.68    38.1    54.5    43.4   54.95    69.4   53.07    74.6   53.92
    83.7   53.14   105.9   53.05   131.8   54.07   231.7   52.54   299.5   48.31
   355.8    46.9   370.4   47.38   399.6   43.91   405.8   42.23   414.2   41.73
   555.9   41.73   570.5    44.2     606   47.75   620.6   47.58   649.8   49.63
   735.3   49.75   756.1   51.28   785.3    50.2     850   50.84   920.9   52.09
   977.6   50.69  1020.9   52.61  1035.5   52.42  1041.8   53.33  1064.4   53.84
#Mann= 5 ,-1 , 0
       0     .11       0   370.4     .04       0     606     .11       0
     850    .125       0  1020.9     .11       0
Bank Sta=370.4,606
XS Rating Curve= 0 ,0
Exp/Cntr=0.3,0.1

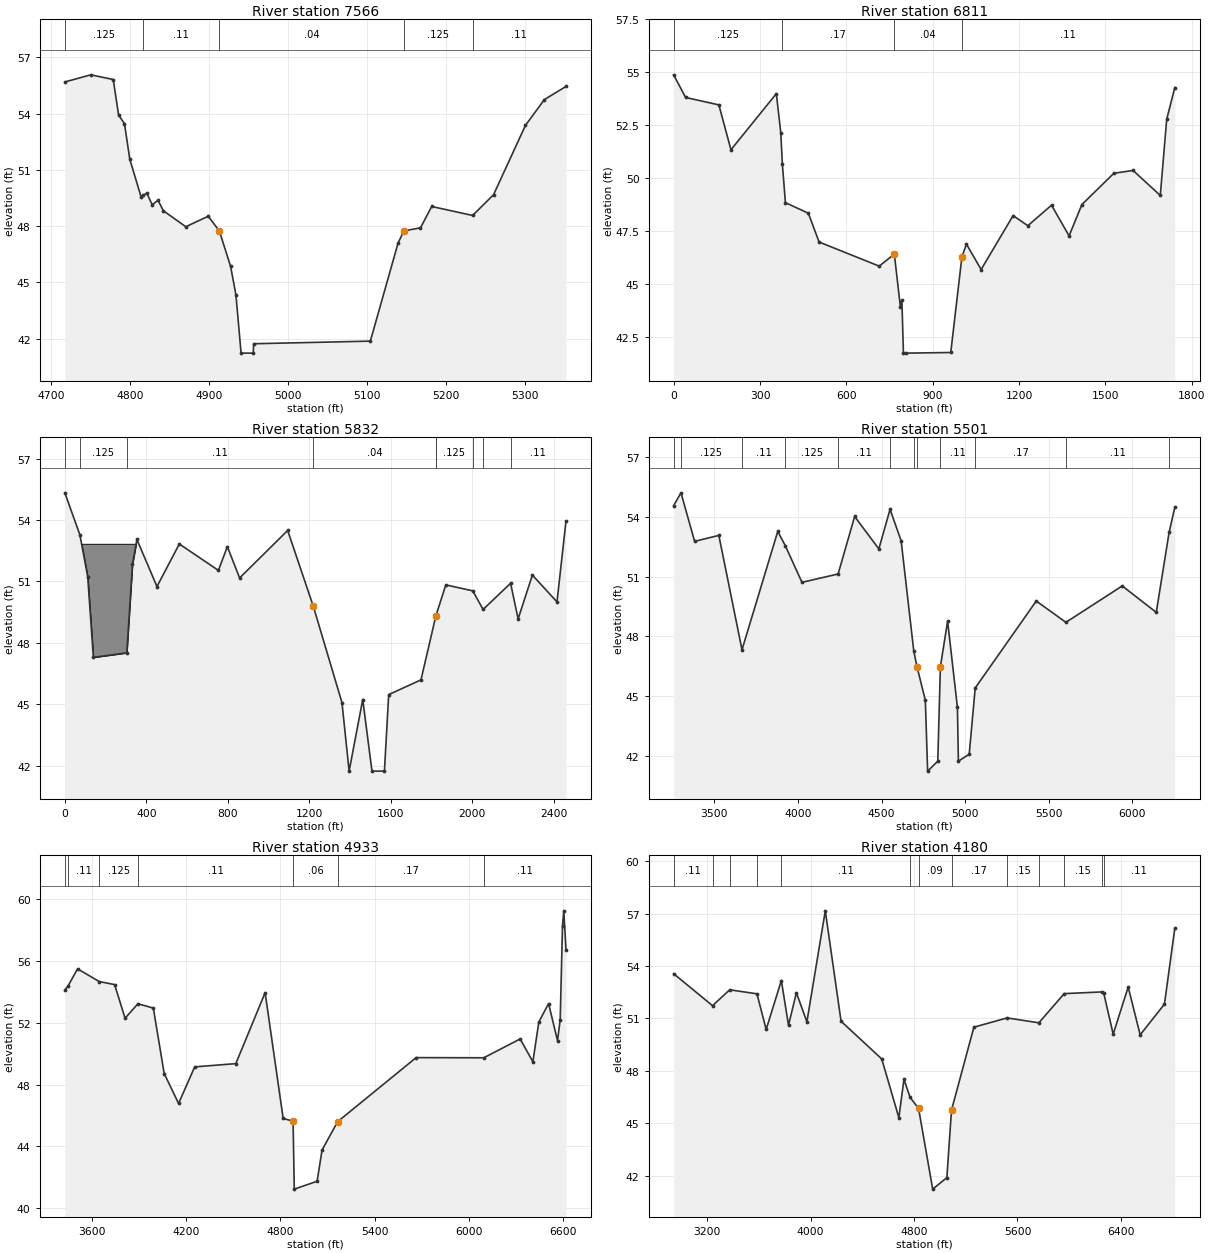
Type RM Length L Ch R = 1 ,7566    ,755,755,755
BEGIN DESCRIPTION:
Mapping XS 183913fe
END DESCRIPTION:
XS GIS Cut Line= 3
      3926969.45     10017449.11      3927289.57     10017099.35
      3927269.22     10016940.08
#Sta/Elev= 30
  4717.3   55.69  4750.2   56.07  4778.6   55.82  4785.4   53.92  4792.8   53.47
  4799.6   51.56  4813.8   49.57  4816.4   49.64  4821.2   49.76  4827.9   49.14
  4835.3   49.38  4842.1   48.82  4870.5   47.97  4898.9   48.53    4913   47.74
  4927.2   45.86    4934   44.33  4940.5   41.23  4955.9   41.23  4956.4   41.73
  5104.2   41.87  5139.4   47.11  5146.8   47.75  5167.7   47.91  5181.9   49.05
  5233.7   48.57  5260.3   49.68  5300.6   53.37  5324.6   54.75    5352   55.45
#Mann= 5 ,-1 , 0
  4717.3    .125       0  4816.4     .11       0    4913     .04       0
  5146.8    .125       0  5233.7     .11       0
Bank Sta=4913,5146.8
XS Rating Curve= 0 ,0
Exp/Cntr=0.3,0.1

Type RM Length L Ch R = 1 ,6811    ,979,979,979
BEGIN DESCRIPTION:
BENS BRANCH 12.0
END DESCRIPTION:
XS GIS Cut Line= 3
      3927428.02     10018520.41      3927699.31     10017684.86
      3927307.41     10016915.76
#Sta/Elev= 30
       0   54.88    41.4   53.81     157   53.46   199.1   51.34   356.8   53.99
   372.2   52.14   377.8   50.65   388.3   48.84   468.1   48.34   505.3   46.98
   714.3   45.84   766.8   46.41   787.7   43.93     793   44.25   798.4   41.75
   808.9   41.73   962.9   41.76  1001.7   46.28  1017.4   46.88  1068.4   45.68
  1179.6   48.23  1230.7   47.75    1313   48.72  1374.1   47.27  1418.6   48.75
  1529.8   50.23  1596.5   50.36    1691   49.18  1713.3   52.78  1741.5   54.28
#Mann= 4 ,-1 , 0
       0    .125       0   377.8     .17       0   766.8     .04       0
  1001.7     .11       0
Bank Sta=766.8,1001.7
XS Rating Curve= 0 ,0
Exp/Cntr=0.3,0.1

Type RM Length L Ch R = 1 ,5832    ,331,331,331
BEGIN DESCRIPTION:
BENS BRANCH 11.0
END DESCRIPTION:
XS GIS Cut Line= 3
      3928867.85     10018211.07      3928140.28     10016848.06
      3927269.47     10016561.62
#Sta/Elev= 30
       0   55.33      74   53.27   112.2   51.23   139.9   47.29   304.2   47.51
   331.8   51.83   353.7   53.05   452.2   50.75   561.9   52.83   753.8   51.54
   797.7    52.7   857.9   51.17  1093.8   53.49  1219.8   49.78  1360.3   45.08
  1395.4   41.73  1462.3   45.23  1507.6   41.73  1568.7   41.73  1589.7   45.47
  1748.2   46.19  1821.3   49.32  1870.1   50.83  2002.5   50.54  2052.9   49.63
    2188   50.91    2225   49.17    2295   51.31  2415.8      50    2460   53.95
#Mann= 9 ,-1 , 0
       0     .11       0      74    .125       0   304.2     .11       0
  1219.8     .04       0  1821.3     .15       0  1821.3    .125       0
  2002.5     .11       0  2052.9    .125       0    2188     .11       0
#Block Obstruct= 1 ,-1
   80.31   360.1   52.84
Bank Sta=1219.8,1821.3
XS Rating Curve= 0 ,0
Exp/Cntr=0.3,0.1

Type RM Length L Ch R = 1 ,5501    ,568,568,568
BEGIN DESCRIPTION:
BENS BRANCH 10.0
END DESCRIPTION:
XS GIS Cut Line= 3
      3929167.85     10018061.07      3928290.45     10016554.66
      3927997.68     10015335.31
#Sta/Elev= 30
  3256.7   54.58  3300.4   55.22    3382   52.78  3526.8   53.08  3665.4   47.33
  3879.2   53.28    3925   52.55    4024   50.72  4240.2   51.14  4339.1   54.03
  4483.9    52.4  4550.9   54.39  4617.1   52.81    4693   47.25  4713.1   46.44
  4761.9   44.79  4775.6   41.23  4836.3   41.73    4852   46.48  4895.1   48.77
  4953.8   44.43  4959.6   41.73  5024.3   42.08  5060.2   45.41  5425.3   49.78
  5602.6   48.71  5939.5   50.54  6143.1   49.21    6220   53.24    6254   54.49
#Mann= 12 ,-1 , 0
  3256.7     .11       0  3300.4    .125       0  3665.4     .11       0
    3925    .125       0  4240.2     .11       0  4550.9     .17       0
    4693     .11       0  4713.1     .06       0    4852     .11       0
  5060.2     .17       0  5602.6     .11       0    6220    .125       0
Bank Sta=4713.1,4852
XS Rating Curve= 0 ,0
Exp/Cntr=0.3,0.1

Type RM Length L Ch R = 1 ,4933    ,753,753,753
BEGIN DESCRIPTION:
BENS BRANCH 9.0
END DESCRIPTION:
XS GIS Cut Line= 3
      3929379.15      10017886.6      3928816.66     10016421.35
      3928117.84     10014961.05
#Sta/Elev= 30
  3428.2   54.11  3448.4   54.39  3509.1    55.5  3646.7   54.68  3744.8   54.48
  3811.4    52.3    3893   53.24  3991.1   52.96  4060.2   48.72  4151.8   46.78
  4254.3   49.15    4516   49.36  4702.4   53.96  4817.1   45.81  4880.2   45.63
  4887.8   41.23  5033.3   41.74  5064.5   43.76  5163.7    45.6  5663.2   49.75
  6093.6   49.74  6324.9   50.96  6405.9   49.48  6443.8   52.06  6505.7   53.25
  6562.7   50.85  6579.8   52.21  6594.4    58.3  6602.5   59.26  6616.6   56.75
#Mann= 7 ,-1 , 0
  3428.2    .125       0  3448.4     .11       0  3646.7    .125       0
    3893     .11       0  4880.2     .06       0  5163.7     .17       0
  6093.6     .11       0
Bank Sta=4880.2,5163.7
XS Rating Curve= 0 ,0
Exp/Cntr=0.3,0.1

Type RM Length L Ch R = 1 ,4180    ,488,488,488
BEGIN DESCRIPTION:
BENS BRANCH 7.0
END DESCRIPTION:
XS GIS Cut Line= 3
      3929636.11     10017935.27      3929274.83     10015908.82
      3928240.83     10014415.21
#Sta/Elev= 30
  2941.6   53.56  3242.1   51.73  3374.8   52.64  3585.5   52.41  3656.9   50.37
  3774.2   53.17  3829.6   50.61  3890.5   52.47  3971.8   50.81    4114   57.16
  4235.9   50.84  4550.6   48.68  4682.8   45.32  4722.4   47.52  4769.6   46.48
  4835.2   45.85  4944.5   41.23  5054.1   41.89  5089.9   45.75  5262.9    50.5
  5519.6   51.03  5765.3   50.75  5961.2   52.42  6256.8   52.52  6266.9   52.45
    6340    50.1  6456.2    52.8  6548.7   50.06  6736.5   51.82  6816.6   56.17
#Mann= 13 ,-1 , 0
  2941.6     .11       0  3242.1    .125       0  3374.8     .11       0
  3585.5    .125       0  3774.2     .11       0  4769.6     .17       0
  4835.2     .09       0  5089.9     .17       0  5519.6     .15       0
  5765.3    .125       0  5961.2     .15       0  6256.8    .125       0
  6266.9     .11       0
Bank Sta=4835.2,5089.9
XS Rating Curve= 0 ,0
Exp/Cntr=0.3,0.1