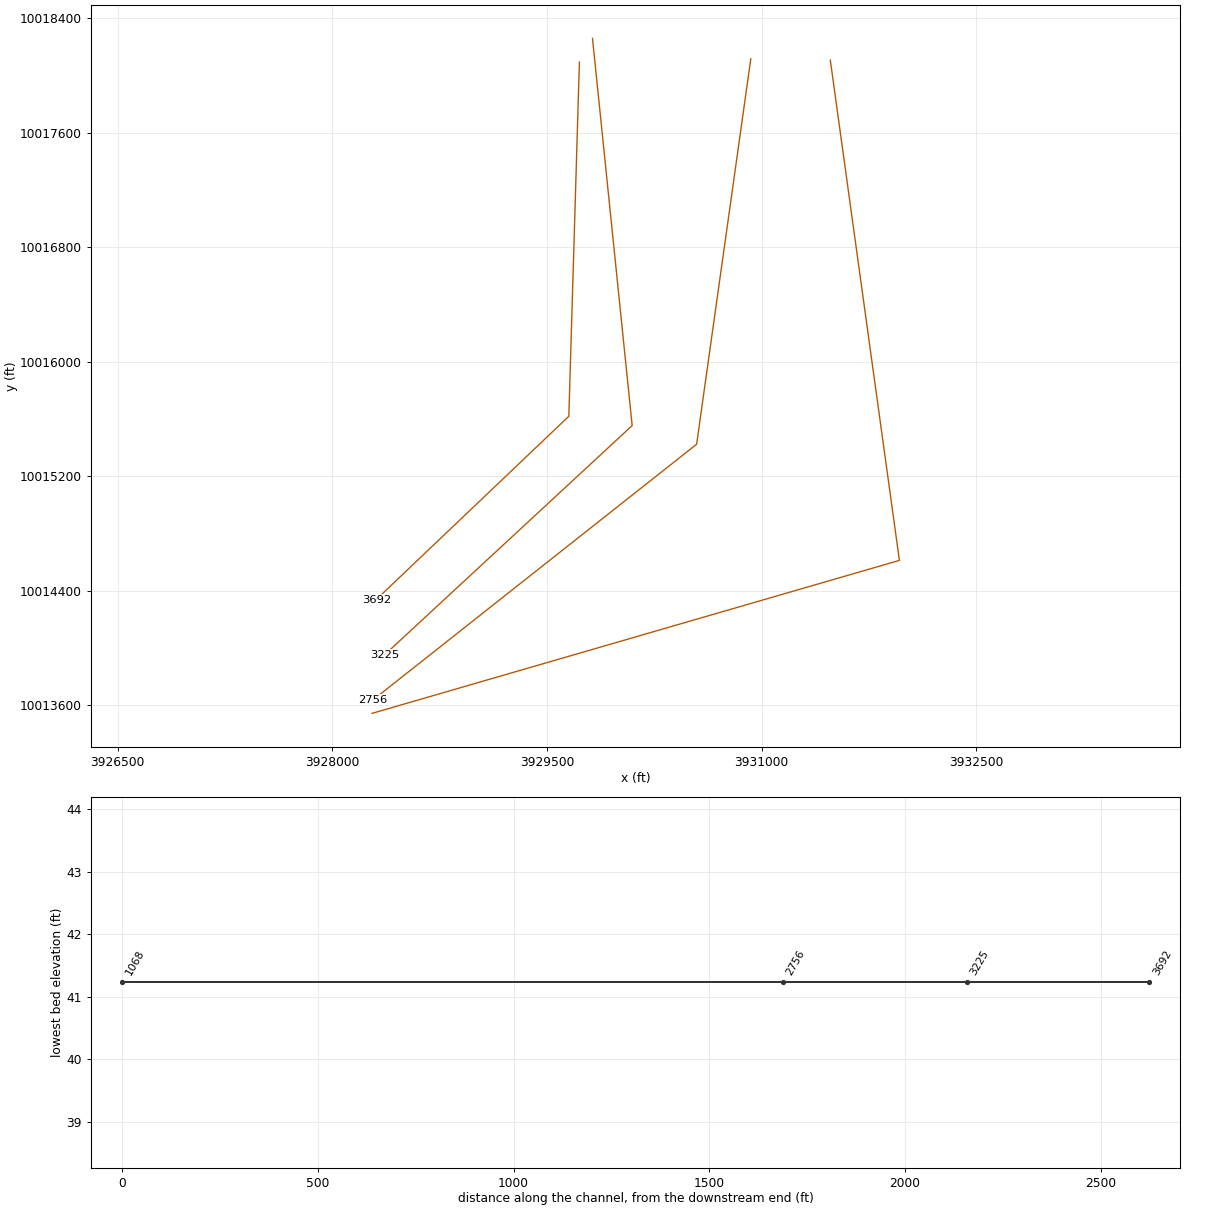
HEC-RAS study BENS BRANCH.prj: BENS BRANCH Base Level Engineering

--- BENS BRANCH.g01 (geometry) --- (continued)

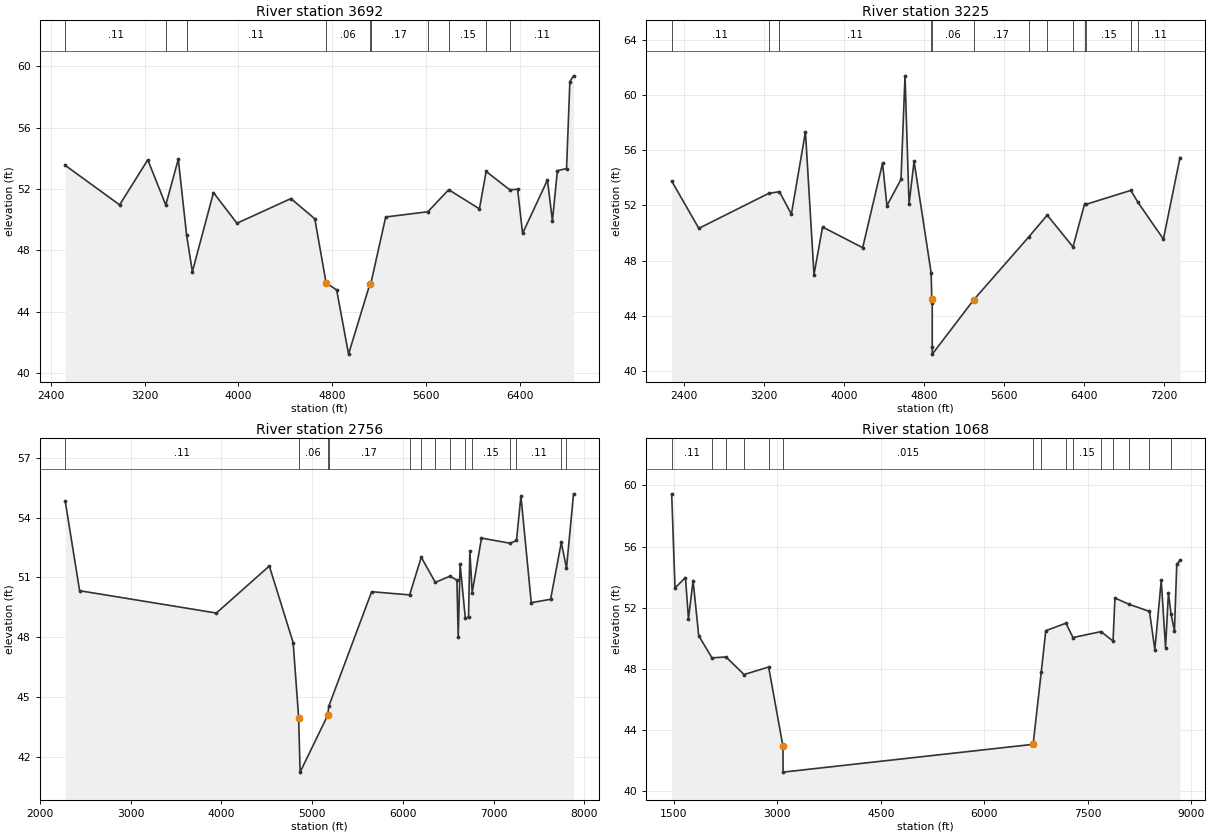
Type RM Length L Ch R = 1 ,3692    ,467,467,467
BEGIN DESCRIPTION:
BENS BRANCH 6.0
END DESCRIPTION:
XS GIS Cut Line= 3
      3929726.38     10018094.95      3929652.43     10015619.76
      3928306.24     10014338.44
#Sta/Elev= 30
  2523.7   53.55  2987.8   50.97  3227.9   53.91  3381.4   50.96    3488   53.95
    3559      49  3608.1   46.61  3788.1   51.77  3988.2   49.77  4448.4   51.38
  4652.3   50.06  4748.6   45.87  4838.6   45.42  4939.9   41.23  5122.5   45.82
  5129.8   45.83  5256.8   50.18  5616.1   50.52  5793.8   51.96  6056.1   50.71
  6113.3   53.15  6313.3   51.96  6381.6   51.98  6424.1   49.11  6636.1   52.59
  6678.5   49.93    6721    53.2    6799   53.34  6827.3   59.01  6858.5   59.39
#Mann= 10 ,-1 , 0
  2523.7     .11       0  3381.4    .125       0    3559     .11       0
  4748.6     .06       0  5122.5     .11       0  5129.8     .17       0
  5616.1    .125       0  5793.8     .15       0  6113.3    .125       0
  6313.3     .11       0
Bank Sta=4748.6,5122.5
XS Rating Curve= 0 ,0
Exp/Cntr=0.3,0.1

Type RM Length L Ch R = 1 ,3225    ,469,469,469
BEGIN DESCRIPTION:
BENS BRANCH 5.0
END DESCRIPTION:
XS GIS Cut Line= 3
      3929817.85     10018261.09      3930095.14     10015554.66
      3928363.55     10013951.31
#Sta/Elev= 30
  2279.4   53.77  2550.8   50.34  3247.6   52.87  3356.2      53  3475.6   51.37
  3616.4   57.33  3701.9   46.99  3787.3   50.44  4188.5   48.94  4387.1   55.07
  4430.6   51.98  4571.4   53.89  4611.6   61.39  4651.8    52.1    4702    55.2
  4872.9   47.11  4878.7   45.23  4883.7   44.96  4883.8   41.73  4884.3   41.23
  5297.6   45.16  5846.1    49.7  6032.9    51.3  6290.2      49  6406.1    52.1
  6420.1   52.08  6868.7   53.09  6939.5   52.23  7194.1   49.56  7359.9   55.47
#Mann= 13 ,-1 , 0
  2279.4     .11       0  3247.6    .125       0  3356.2     .11       0
  4872.9     .11       0  4878.7     .06       0  5297.6     .17       0
  5846.1    .125       0  6032.9     .15       0  6290.2    .125       0
  6406.1     .11       0  6420.1     .15       0  6868.7    .125       0
  6939.5     .11       0
Bank Sta=4878.7,5297.6
XS Rating Curve= 0 ,0
Exp/Cntr=0.3,0.1

Type RM Length L Ch R = 1 ,2756    ,1688,1688,1688
BEGIN DESCRIPTION:
BENS BRANCH 4.0
END DESCRIPTION:
XS GIS Cut Line= 3
       3930924.3     10018117.96      3930545.66     10015424.45
      3928285.41      10013638.8
#Sta/Elev= 30
    2280   54.83  2438.8   50.33  3945.4   49.21  4528.8   51.57  4791.3   47.73
  4851.9   43.97  4868.1   41.23    5172   44.08  5183.6   44.53  5656.2   50.28
  6074.7   50.12  6202.8   52.01  6357.5   50.75  6519.9   51.06  6595.5   50.86
  6609.9      48  6630.7   51.66  6688.1   48.96  6723.7      49  6738.2   52.32
    6764   50.24  6866.4   52.97  7183.2   52.71  7252.1   52.85  7300.8   55.08
  7414.7   49.73  7627.8    49.9  7745.6   52.75    7803   51.46  7880.5   55.19
#Mann= 14 ,-1 , 0
    2280     .11       0  4851.9     .06       0    5172     .11       0
  5183.6     .17       0  6074.7    .125       0  6202.8     .15       0
  6357.5    .125       0  6519.9     .11       0  6688.1    .125       0
    6764     .15       0  7183.2    .125       0  7252.1     .11       0
  7745.6    .125       0    7803     .15       0
Bank Sta=4851.9,5172
XS Rating Curve= 0 ,0
Exp/Cntr=0.3,0.1

Type RM Length L Ch R = 1 ,1068    ,0,0,0
BEGIN DESCRIPTION:
BENS BRANCH 2.0
END DESCRIPTION:
XS GIS Cut Line= 3
      3931479.85     10018109.33      3931962.82     10014612.63
      3928276.69      10013543.3
#Sta/Elev= 30
  1470.1   59.45  1518.8   53.29  1670.2   53.97  1713.5   51.26  1780.3   53.76
  1862.3   50.16  2054.2   48.71  2257.6   48.77  2519.4   47.62  2875.6   48.11
  3083.5   42.91  3084.7   41.23    6709   43.05  6827.3   47.79  6892.5   50.49
  7185.2   50.98  7286.8   50.04    7693   50.43  7867.8   49.81  7894.8   52.63
  8099.3   52.22  8395.7   51.75  8473.4   49.24  8566.2   53.79  8628.6   49.38
  8670.3   52.94  8708.7   51.58  8757.6   50.48  8791.1   54.83  8838.1    55.1
#Mann= 15 ,-1 , 0
  1470.1     .11       0  2054.2     .17       0  2257.6     .11       0
  2519.4     .17       0  2875.6     .11       0  3083.5    .015       0
    6709     .11       0  6827.3     .17       0  7185.2     .11       0
  7286.8     .15       0    7693     .11       0  7867.8    .125       0
  8099.3     .15       0  8395.7     .11       0  8708.7     .15       0
Bank Sta=3083.5,6709
XS Rating Curve= 0 ,0
Exp/Cntr=0.3,0.1

Chan Stop Cuts=-1
Use User Specified Reach Order=0
Composite Channel Slope=5