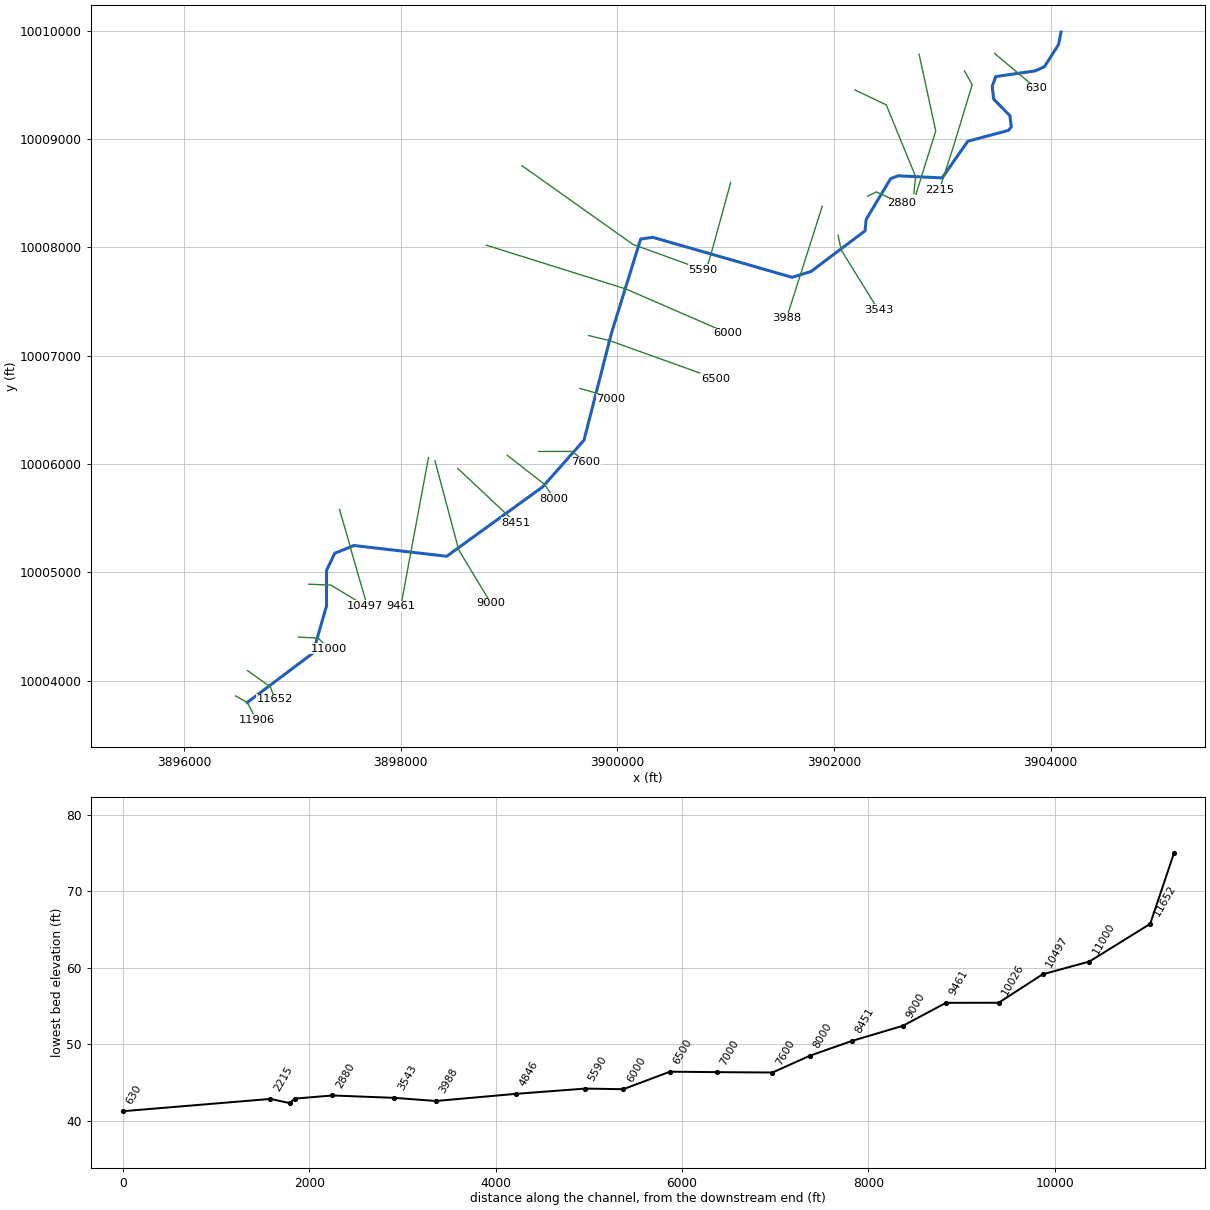
--- BLACKS BRANCH.prj (project) ---

Proj Title=BLACKS BRANCH Base Level Engineering
Current Plan=p01
Default Exp/Contr=0.3,0.1
English Units
Geom File=g01
Flow File=f01
Flow File=f02
Plan File=p01
Y Axis Title=Elevation
X Axis Title(PF)=Main Channel Distance
X Axis Title(XS)=Station
BEGIN DESCRIPTION:
BLACKS BRANCH
END DESCRIPTION:
DSS File=dss
DSS Export Rating Curves= 0
DSS Export Rating Curve Sorted= 0
DSS Export Volume Flow Curves= 0
DXF OffsetX= 0
DXF OffsetY= 0
DXF ScaleX= 1
DXF ScaleY= 10

--- BLACKS BRANCH.p01 (plan) ---

Plan Title=Multiple Run
Program Version=4.10
Short Identifier=Multiple Run
Geom File=g01
Flow File=f01
Subcritical Flow
K Sum by GR= 0
Std Step Tol= 0.01
Critical Tol= 0.01
Num of Std Step Trials= 20
Max Error Tol= 0.3
Flow Tol Ratio= 0.001
Split Flow NTrial= 30
Split Flow Tol= 0.02
Split Flow Ratio= 0.02
Log Output Level= 0
Friction Slope Method= 1
Unsteady Friction Slope Method= 2
Unsteady Bridges Friction Slope Method= 1
Parabolic Critical Depth
Global Vel Dist= 1 , 1 , 1
Global Log Level= 0
CheckData=True
Encroach Param=-1 ,0,0, 0
BEGIN DESCRIPTION:
Multiple Run
END DESCRIPTION:
Computation Interval=1HOUR
Output Interval=1HOUR
Run HTab= 0
Run UNet= 0
Run PostProcess= 0
Run WQNet= 0
UNET Theta= 1
UNET Theta Warmup= 1
UNET ZTol= 0.02
UNET ZSATol= 0.05
UNET MxIter= 20
UNET MaxInSteps= 0
UNET DtIC= 0
UNET DtMin= 0
UNET MaxCRTS= 20
UNET WFStab= 2
UNET SFStab= 1
UNET WFX= 1
UNET SFX= 1
UNET DSS MLevel= 4
UNET DZMax Abort= 100
UNET Convert EG Bridges= 0
UNET Use Existing IB Tables=-1
UNET Froude Reduction=False
UNET Froude Limit= 1
UNET Froude Power= 10
UNET Time Slicing=0,0, 5
UNET Junction Losses=0
Instantaneous Interval=1HOUR
DSS File=dss
Write IC File= 0
Write IC File at Sim End=0
Echo Input=False
Echo Parameters=False
Echo Output=False
Write Detailed= 0
WQ AD Non Conservative
WQ ULTIMATE=-1
WQ Max Comp Step=1HOUR
WQ Output Interval=15MIN
WQ Output Selected Increments= 0
WQ Output face flow=0
WQ Output face velocity=0
WQ Output face area=0
WQ Output face dispersion=0
WQ Output cell volume=0
WQ Output cell surface area=0
WQ Output cell continuity=0
WQ Output cumulative cell continuity=0
WQ Output face conc=0
WQ Output face dconc_dx=0
WQ Output face courant=0
WQ Output face peclet=0
WQ Output face adv mass=0
WQ Output face disp mass=0
WQ Output cell mass=0
WQ Output cell source sink temp=0
WQ Output cell source sink nsm=0
WQ Output MaxMinRange=-1
WQ Daily Max Min Mean=-1
WQ Daily Range=0
WQ Daily Time=0
WQ Create Restart=0
WQ Fixed Restart=0
WQ System Summary=0
WQ Use Fixed Temperature=0
Sorting and Armoring Iterations= 10
XS Update Threshold= 0.02
Hydraulics Update Threshold= 0.02
Energy Slope Method= 1
Volume Change Method= 0
XS Weighting Method= 0
Number of US Weighted Cross Sections= 1
Number of DS Weighted Cross Sections= 1
Upstream XS Weight=0.25
Main XS Weight=0.5
Downstream XS Weight=0.25
Number of DS XS's Weighted with US Boundary= 1
Upstream Boundary Weight= 1
Weight of XSs Associated with US Boundary= 0
Number of US XS's Weighted with DS Boundary= 1
Downstream Boundary Weight= 0.5
Weight of XSs Associated with DS Boundary= 0.5
Sediment Output Level= 4
Mass or Volume Output= 0
Output Increment Type= 1
Profile and TS Output Increment= 10
XS Output Flag= 0
XS Output Increment= 10
Disregard all LS=0
Disregard all Conn=0
Disregard all Breaches=0
Disregard all Pumps=0

--- BLACKS BRANCH.f01 (steady flow) ---

Flow Title=Multiple
Program Version=4.10
Number of Profiles= 7
Profile Names=10-year,25-year,50-year,1pct_min,100-year,1pct_plu,500-year
River Rch & RM=BLACKS BRANCH,Reach-1         ,11906
     582     765    1013     441    1333    4026    2383
River Rch & RM=BLACKS BRANCH,Reach-1         ,11652
     582     765    1013     441    1333    4026    2383
River Rch & RM=BLACKS BRANCH,Reach-1         ,8451
    1098    1508    2057     923    2786    8414    5274
River Rch & RM=BLACKS BRANCH,Reach-1         ,7000
    1085    1460    1964     867    2618    7906    4801
River Rch & RM=BLACKS BRANCH,Reach-1         ,630
    1075    1436    1922     843    2545    7686    4611
Boundary for River Rch & Prof#=BLACKS BRANCH,Reach-1         , 1
Up Type= 0
Dn Type= 3
Dn Slope=0.00092
Boundary for River Rch & Prof#=BLACKS BRANCH,Reach-1         , 2
Up Type= 0
Dn Type= 3
Dn Slope=0.00092
Boundary for River Rch & Prof#=BLACKS BRANCH,Reach-1         , 3
Up Type= 0
Dn Type= 3
Dn Slope=0.00092
Boundary for River Rch & Prof#=BLACKS BRANCH,Reach-1         , 4
Up Type= 0
Dn Type= 3
Dn Slope=0.00092
Boundary for River Rch & Prof#=BLACKS BRANCH,Reach-1         , 5
Up Type= 0
Dn Type= 3
Dn Slope=0.00092
Boundary for River Rch & Prof#=BLACKS BRANCH,Reach-1         , 6
Up Type= 0
Dn Type= 3
Dn Slope=0.00092
Boundary for River Rch & Prof#=BLACKS BRANCH,Reach-1         , 7
Up Type= 0
Dn Type= 3
Dn Slope=0.00092
DSS Import GetInterval= 0
DSS Import GetPeak= 0
DSS Import FillOption= 0

--- BLACKS BRANCH.f02 (steady flow) ---

Flow Title=Orig_BLE_Flows
Program Version=4.10
Number of Profiles= 7
Profile Names=10-year,25-year,50-year,1pct_min,100-year,1pct_plu,500-year
River Rch & RM=BLACKS BRANCH,Reach-1         ,11906
     663     866    1027     400    1208    3648    1665
River Rch & RM=BLACKS BRANCH,Reach-1         ,11652
     663     866    1027     400    1208    3648    1665
River Rch & RM=BLACKS BRANCH,Reach-1         ,8453
    1098    1478    1789     710    2143    6471    3066
River Rch & RM=BLACKS BRANCH,Reach-1         ,7000
    1085    1431    1708     667    2014    6081    2791
River Rch & RM=BLACKS BRANCH,Reach-1         ,630
    1285    1715    2063     811    2450    7398    3448
Boundary for River Rch & Prof#=BLACKS BRANCH,Reach-1         , 1
Up Type= 0
Dn Type= 3
Dn Slope=0.00092
Boundary for River Rch & Prof#=BLACKS BRANCH,Reach-1         , 2
Up Type= 0
Dn Type= 3
Dn Slope=0.00092
Boundary for River Rch & Prof#=BLACKS BRANCH,Reach-1         , 3
Up Type= 0
Dn Type= 3
Dn Slope=0.00092
Boundary for River Rch & Prof#=BLACKS BRANCH,Reach-1         , 4
Up Type= 0
Dn Type= 3
Dn Slope=0.00092
Boundary for River Rch & Prof#=BLACKS BRANCH,Reach-1         , 5
Up Type= 0
Dn Type= 3
Dn Slope=0.00092
Boundary for River Rch & Prof#=BLACKS BRANCH,Reach-1         , 6
Up Type= 0
Dn Type= 3
Dn Slope=0.00092
Boundary for River Rch & Prof#=BLACKS BRANCH,Reach-1         , 7
Up Type= 0
Dn Type= 3
Dn Slope=0.00092
DSS Import GetInterval= 0
DSS Import GetPeak= 0
DSS Import FillOption= 0

--- BLACKS BRANCH.g01 (geometry) ---

Geom Title=Existing Conditions
Program Version=4.10

River Reach=BLACKS BRANCH   ,Reach-1
Reach XY= 30
      3896585.62     10003799.96      3897191.31     10004255.12
      3897317.18     10004691.31      3897317.18       10005019.
      3897393.14     10005177.42      3897570.37     10005248.39
      3898426.12     10005149.21      3899311.54      10005789.4
      3899693.12     10006220.49      3899946.01     10007206.42
      3900215.78     10008076.78      3900328.49     10008092.73
      3901613.69     10007723.74      3901787.96     10007776.92
       3902286.8     10008152.69      3902297.65     10008259.02
      3902523.35     10008634.46      3902592.79      10008660.5
      3902998.61     10008640.97      3903235.15     10008979.51
      3903610.58     10009079.33      3903636.63     10009111.89
      3903623.61     10009216.05      3903473.87     10009367.96
      3903460.85     10009487.32       3903493.4      10009576.3
      3903855.81     10009628.38      3903942.62     10009667.44
      3904072.82     10009871.44      3904095.69     10009987.24

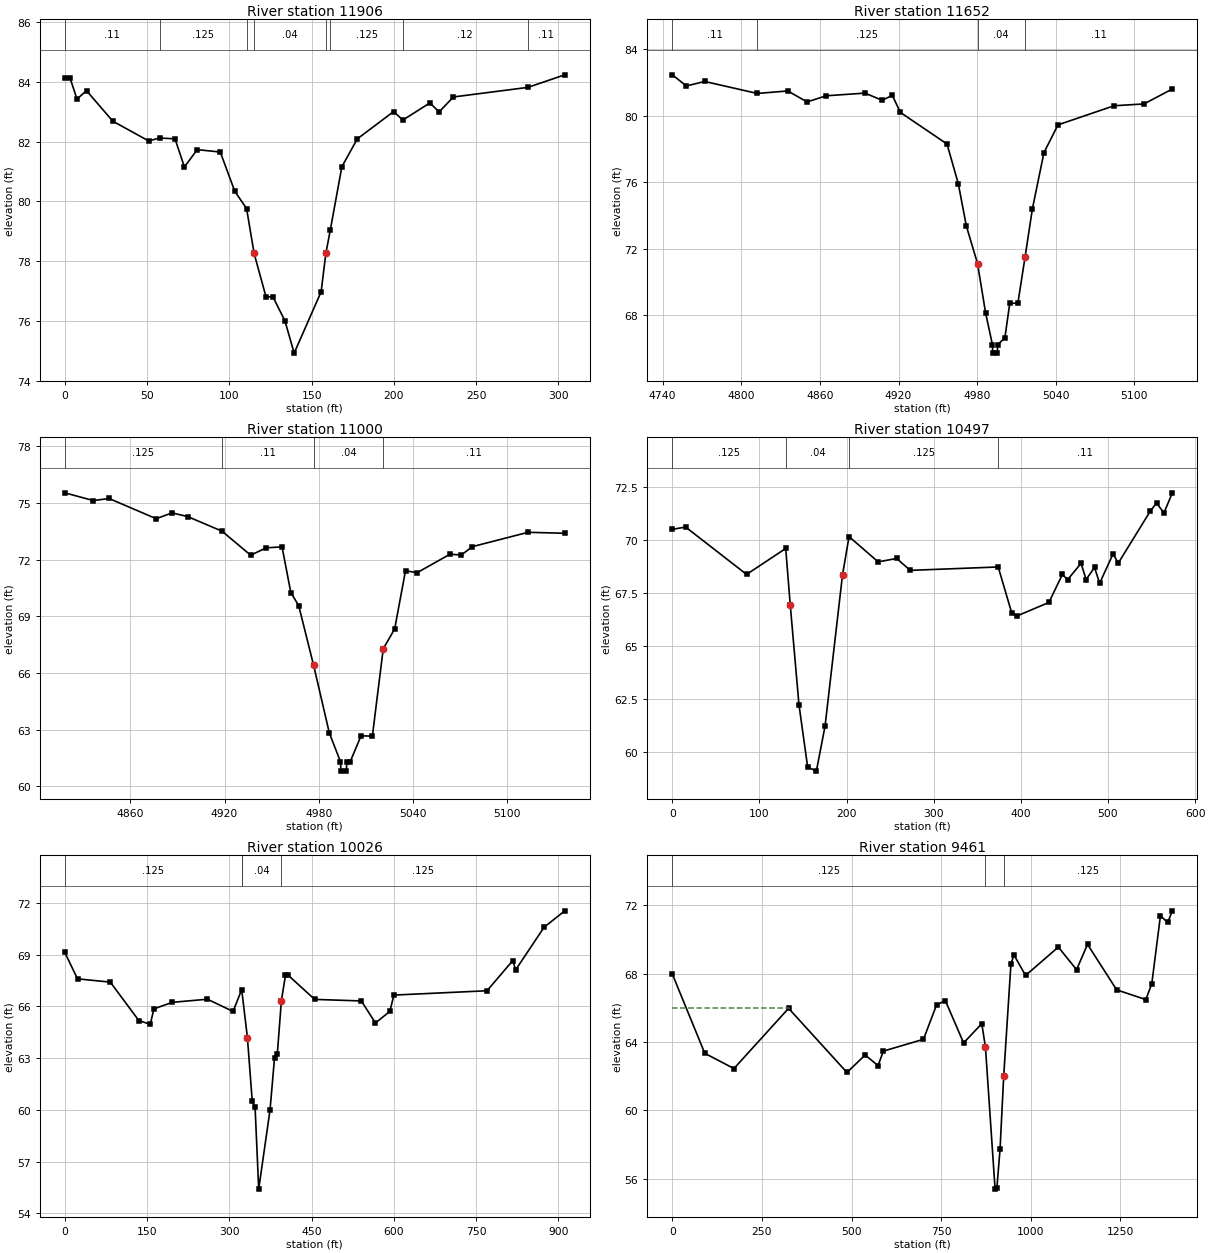
Type RM Length L Ch R = 1 ,11906   ,254,254,254
BEGIN DESCRIPTION:
BLACKS BRANCH 23.0
END DESCRIPTION:
XS GIS Cut Line= 3
      3896477.43     10003860.27      3896586.08     10003800.21
      3896669.85     10003641.19
#Sta/Elev= 30
       0   84.14     3.1   84.14     7.4   83.42    13.2    83.7    29.2   82.68
      51   82.02    57.6   82.12      67   82.09    72.7   81.15    80.5   81.73
    94.5   81.65   103.3   80.34   110.5   79.76  115.07   78.26   122.3   76.81
   126.5   76.81   133.8   76.01   139.4   74.93   155.8   76.98  158.66   78.26
   161.4   79.05   168.4   81.16   177.8   82.09   199.8      83   205.5   82.72
   221.9   83.29   227.5   82.99   236.2   83.49   281.4   83.81   303.9   84.23
#Mann= 8 ,-1 , 0
       0     .11       0    57.6    .125       0   110.5     .11       0
  115.07     .04       0  158.66     .11       0   161.4    .125       0
   205.5     .12       0   281.4     .11       0
Bank Sta=115.07,158.66
XS Rating Curve= 0 ,0
Exp/Cntr=0.3,0.1

Type RM Length L Ch R = 1 ,11652   ,652,652,652
BEGIN DESCRIPTION:
BLACKS BRANCH 23.0
END DESCRIPTION:
XS GIS Cut Line= 3
      3896587.76     10004094.87      3896798.77     10003943.45
      3896841.87     10003829.44
#Sta/Elev= 30
  4747.4   82.46  4758.1   81.79  4772.1   82.06  4812.2   81.34  4835.5   81.49
  4850.2   80.83  4864.9    81.2  4894.4   81.36  4907.5   80.93  4915.3   81.22
  4921.4    80.2    4957    78.3  4965.6   75.92  4971.8   73.36  4980.3   71.11
  4986.5   68.12  4991.7   66.22  4991.9   65.72  4995.4   65.72  4995.7   66.22
  5001.2   66.65  5004.9   68.72  5011.1   68.72  5016.6   71.51  5022.2   74.41
    5031   77.78  5041.7   79.45  5084.5    80.6  5107.4   80.71    5129   81.61
#Mann= 4 ,-1 , 0
  4747.4     .11       0  4812.2    .125       0  4980.3     .04       0
  5016.6     .11       0
Bank Sta=4980.3,5016.6
XS Rating Curve= 0 ,0
Exp/Cntr=0.3,0.1

Type RM Length L Ch R = 1 ,11000   ,503,503,503
BEGIN DESCRIPTION:
BLACKS BRANCH 22.0
END DESCRIPTION:
XS GIS Cut Line= 3
      3897059.67     10004402.98      3897241.17     10004394.29
      3897335.28     10004295.28
#Sta/Elev= 30
  4818.3   75.53  4836.5   75.12  4846.5   75.23  4876.5   74.16  4886.6   74.47
  4896.6   74.27  4918.4    73.5  4936.6   72.23  4946.6   72.62  4956.6   72.67
  4962.2   70.25  4967.2   69.56  4976.7    66.4  4986.7   62.82  4993.8    61.3
  4994.1    60.8  4997.6    60.8  4997.8    61.3    5000    61.3  5006.9   62.67
  5014.1   62.65    5021   67.27  5028.3   68.33  5035.2   71.41  5042.5    71.3
  5063.5   72.28  5070.8   72.24  5077.7   72.68  5113.2   73.44  5136.6   73.39
#Mann= 4 ,-1 , 0
  4818.3    .125       0  4918.4     .11       0  4976.7     .04       0
    5021     .11       0
Bank Sta=4976.7,5021
XS Rating Curve= 0 ,0
Exp/Cntr=0.3,0.1

Type RM Length L Ch R = 1 ,10497   ,471,471,471
BEGIN DESCRIPTION:
BLACKS BRANCH 21.0
END DESCRIPTION:
XS GIS Cut Line= 3
      3897152.68      10004891.6      3897357.76     10004882.87
       3897673.8     10004692.04
#Sta/Elev= 30
       0    70.5    15.2   70.61    85.2   68.38   130.1    69.6   135.3   66.95
   145.3   62.25   155.3   59.31   165.3   59.12   175.3   61.25   195.3   68.36
   202.8   70.16   236.2   68.97   257.5   69.13     273   68.57     374   68.73
   389.5   66.57   395.3   66.42   432.2   67.06   447.7   68.38   453.6   68.13
   469.1    68.9   474.9   68.14   484.6   68.71   490.4   67.96   505.9   69.35
   511.8   68.91   548.6   71.36   555.8   71.74   564.2   71.27   573.9   72.22
#Mann= 4 ,-1 , 0
       0    .125       0   130.1     .04       0   202.8    .125       0
     374     .11       0
Bank Sta=135.3,195.3
XS Rating Curve= 0 ,0
Exp/Cntr=0.3,0.1

Type RM Length L Ch R = 1 ,10026   ,565,565,565
BEGIN DESCRIPTION:
BLACKS BRANCH 20.0
END DESCRIPTION:
XS GIS Cut Line= 4
      3897437.08     10005580.78      3897525.67     10005276.76
       3897547.7     10005191.58      3897689.64      10004703.8
#Sta/Elev= 30
       0   69.12    23.2   67.59      83    67.4   135.1   65.17   155.9   64.96
   162.4   65.85   195.9   66.23   260.1   66.41   306.8    65.7   322.5   66.97
   332.9   64.19   341.7   60.51   346.9   60.15   353.5   55.41   374.2   60.01
   382.3      63   387.5   63.26   394.8   66.32   402.3   67.79   407.5   67.79
   455.5    66.4   540.6   66.31   566.4   65.03   592.6   65.71   599.9   66.65
   769.7    66.9   816.7   68.65   821.9   68.11   873.8   70.58   911.5   71.53
#Mann= 4 ,-1 , 0
       0    .125       0   322.5     .11       0   322.5     .04       0
   394.8    .125       0
Bank Sta=332.9,394.8
XS Rating Curve= 0 ,0
Exp/Cntr=0.3,0.1

Type RM Length L Ch R = 1 ,9461    ,461,461,461
BEGIN DESCRIPTION:
BLACKS BRANCH 19.0
END DESCRIPTION:
XS GIS Cut Line= 2
      3898257.94     10006060.02      3898002.34     10004686.87
#Sta/Elev= 30
       0   67.97    90.5   63.34   171.9   62.45   324.4   65.97   487.2   62.22
     538   63.24     574   62.62   588.9   63.47   700.8   64.16   737.3   66.17
   761.8   66.42   812.7   63.95   863.5   65.07   873.7    63.7   900.6    55.4
   905.7   55.49   914.4   57.72   924.6   61.99   944.9   68.59   953.4   69.09
   985.6   67.89  1077.1   69.55    1128   68.23  1158.5   69.71  1239.9   67.05
  1321.3   66.48  1337.9   67.41    1362   71.38  1382.3   70.99  1395.3   71.67
#Mann= 3 , 0 , 0
       0    .125       0   873.7     .04       0   924.6    .125       0
#XS Ineff= 2 , 0
          326.32   65.96
Permanent Ineff=
       F       F
Bank Sta=873.7,924.6
XS Rating Curve= 0 ,0
Exp/Cntr=0.3,0.1

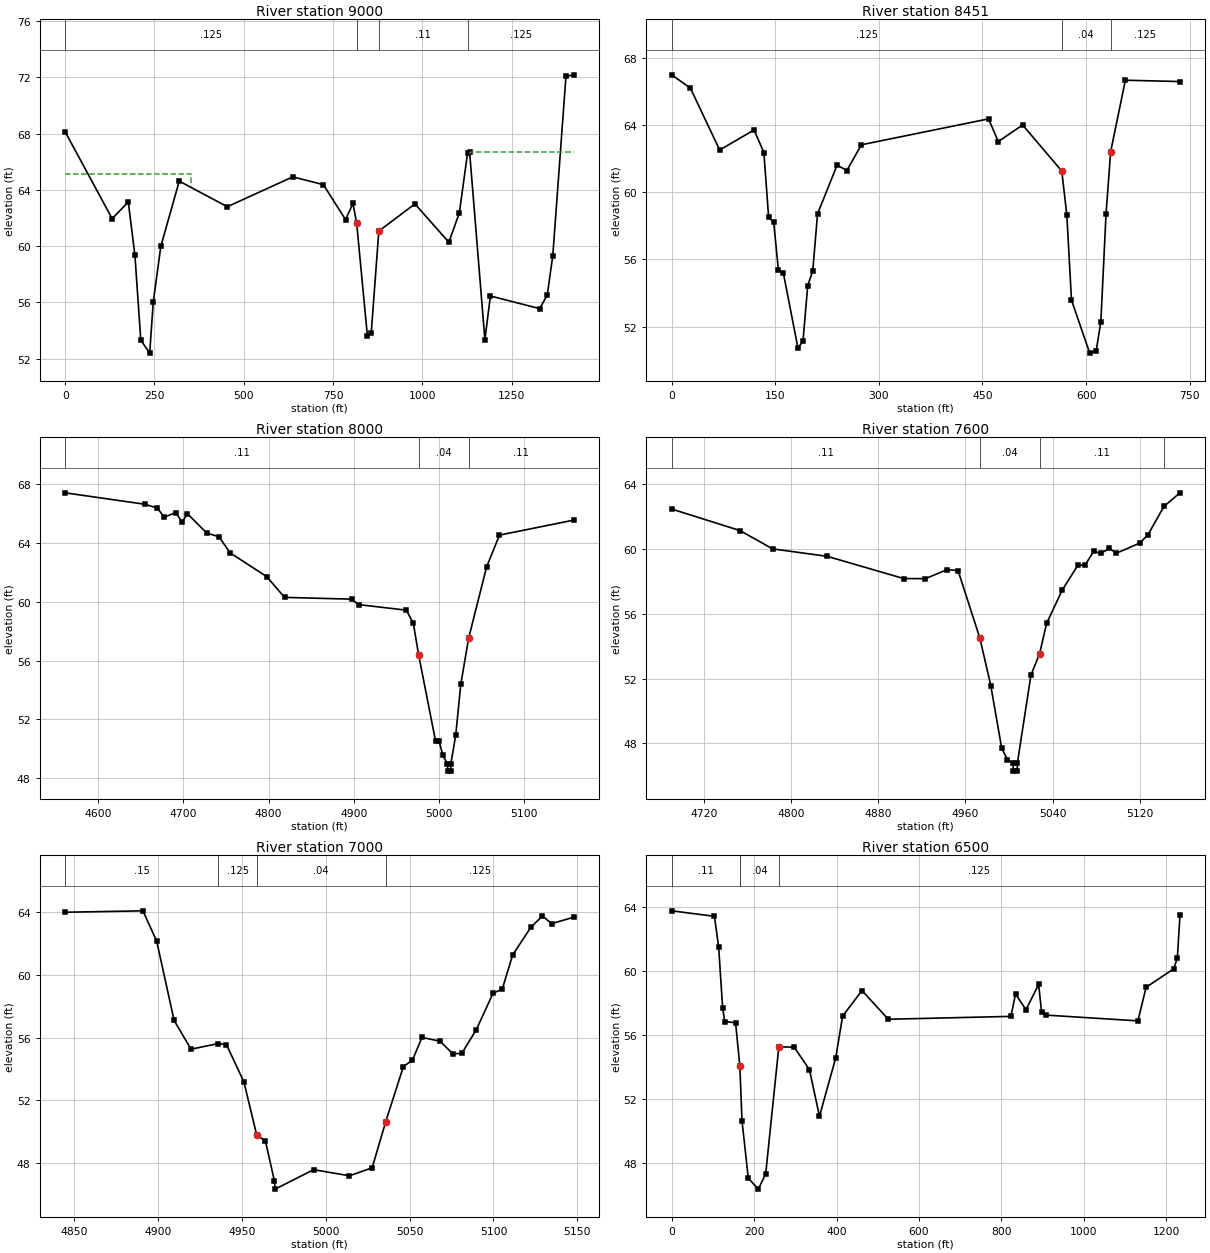
Type RM Length L Ch R = 1 ,9000    ,545,545,545
BEGIN DESCRIPTION:
BLACKS BRANCH 18.0
END DESCRIPTION:
XS GIS Cut Line= 3
      3898318.05     10006029.68      3898537.31     10005207.86
      3898833.94     10004716.39
#Sta/Elev= 30
       0   68.12   131.5   61.95   176.7   63.14   195.2   59.35   211.7   53.33
   236.6    52.4   246.6   56.02   267.7   59.98   319.4   64.62     454    62.8
   637.2   64.92     723   64.37   785.1   61.88   805.8   63.03   816.2   61.65
   846.3   53.62     857   53.82   878.3   61.07   979.3      63  1074.4   60.28
  1103.8   62.36  1126.8   66.61  1132.6   66.67  1175.3   53.36  1190.8   56.46
  1328.7   55.56    1350   56.52  1365.5   59.33  1402.4   72.07  1423.6   72.17
#Mann= 4 ,-1 , 0
       0    .125       0   816.2     .04       0   878.3     .11       0
  1126.8    .125       0
#XS Ineff= 2 , 0
          352.29    65.1 1133.03           66.67
Permanent Ineff=
       F       F
Bank Sta=816.2,878.3
XS Rating Curve= 0 ,0
Exp/Cntr=0.3,0.1

Type RM Length L Ch R = 1 ,8451    ,455,455,455
BEGIN DESCRIPTION:
BLACKS BRANCH 17.0
END DESCRIPTION:
XS GIS Cut Line= 3
      3898528.37     10005960.12      3898969.93     10005544.78
      3899066.93     10005458.59
#Sta/Elev= 30
       0   66.98    27.1   66.19    69.5   62.51   119.3    63.7   133.5   62.36
   140.4    58.5   147.7   58.22   154.5   55.38   161.8   55.17   182.8   50.74
   190.1   51.13     197   54.45   204.3   55.33   211.2   58.71   239.5   61.61
   253.6   61.29   274.7   62.82   458.8   64.36   472.9   63.01   508.1      64
   564.8   61.26   572.1   58.67   578.9   53.58   605.3   50.43   614.7   50.58
   621.4   52.29   628.9    58.7   635.6   62.41   656.9   66.66     736   66.58
#Mann= 3 , 0 , 0
       0    .125       0   564.8     .04       0   635.6    .125       0
Bank Sta=564.8,635.6
XS Rating Curve= 0 ,0
Exp/Cntr=0.3,0.1

Type RM Length L Ch R = 1 ,8000    ,400,400,400
BEGIN DESCRIPTION:
BLACKS BRANCH 16.0
END DESCRIPTION:
XS GIS Cut Line= 3
      3898985.53     10006080.92      3899331.15     10005811.06
      3899417.63     10005679.06
#Sta/Elev= 30
  4561.5   67.43  4655.1   66.65  4669.6   66.39  4677.7   65.77  4691.3   66.09
  4698.5   65.43  4704.9   66.01  4727.5   64.69  4741.9   64.44  4754.8   63.35
    4798   61.72  4818.8   60.31  4897.5   60.19  4905.6   59.82  4961.7   59.44
  4969.9   58.54  4976.2   56.36  4995.9   50.54    5000   50.54  5004.5   49.55
  5009.9   48.98  5010.2   48.48  5013.7   48.48  5013.9   48.98  5019.6   50.93
  5025.6   54.41  5034.7   57.52  5055.8   62.38  5070.9   64.55  5157.8   65.57
#Mann= 3 , 0 , 0
  4561.5     .11       0  4976.2     .04       0  5034.7     .11       0
Bank Sta=4976.2,5034.7
XS Rating Curve= 0 ,0
Exp/Cntr=0.3,0.1

Type RM Length L Ch R = 1 ,7600    ,600,600,600
BEGIN DESCRIPTION:
BLACKS BRANCH 15.0
END DESCRIPTION:
XS GIS Cut Line= 3
      3899275.27     10006116.35      3899583.49     10006117.06
      3899706.65     10006018.28
#Sta/Elev= 30
  4690.7   62.47  4753.3   61.14  4783.3   60.01  4833.3   59.55  4903.3   58.18
  4923.3   58.17  4943.3   58.73  4953.3   58.67  4973.3    54.5  4983.3   51.57
  4993.3    47.7  4998.6   46.99  5003.7   46.79    5004   46.29  5007.5   46.29
  5007.7   46.79  5020.1   52.21  5028.1   53.55  5034.5   55.41  5048.9   57.48
  5063.3   59.01  5069.7      59  5077.7   59.87  5084.1   59.73  5092.1   60.04
  5098.5   59.74  5119.9   60.37  5127.3   60.87  5142.2   62.64  5156.8   63.47
#Mann= 4 ,-1 , 0
  4690.7     .11       0  4973.3     .04       0  5028.1     .11       0
  5142.2    .125       0
Bank Sta=4973.3,5028.1
XS Rating Curve= 0 ,0
Exp/Cntr=0.3,0.1

Type RM Length L Ch R = 1 ,7000    ,500,500,500
BEGIN DESCRIPTION:
BLACKS BRANCH 14.0
END DESCRIPTION:
XS GIS Cut Line= 3
      3899655.41     10006697.92      3899804.71     10006655.53
      3899941.43     10006599.65
#Sta/Elev= 30
  4844.8   63.99  4891.1   64.08  4899.3   62.15  4909.7   57.09  4919.8   55.26
  4936.1   55.62  4940.9   55.55  4951.3   53.17  4958.9   49.79  4964.1   49.41
  4969.5   46.84  4969.9   46.34  4992.8   47.58  5014.2   47.19  5027.7    47.7
  5035.8   50.64  5046.3   54.15  5051.7   54.56  5057.4   56.01  5068.2   55.77
  5075.7   54.97  5081.1   54.99  5089.8   56.51  5099.8   58.84  5105.2   59.08
  5111.4   61.26  5122.2   63.02  5129.2   63.76  5134.6   63.26  5147.7   63.67
#Mann= 4 ,-1 , 0
  4844.8     .15       0  4936.1    .125       0  4958.9     .04       0
  5035.8    .125       0
Bank Sta=4958.9,5035.8
XS Rating Curve= 0 ,0
Exp/Cntr=0.3,0.1

Type RM Length L Ch R = 1 ,6500    ,500,500,500
BEGIN DESCRIPTION:
BLACKS BRANCH 13.0
END DESCRIPTION:
XS GIS Cut Line= 3
      3899737.06     10007186.02      3899928.93     10007139.85
      3900905.11     10006789.11
#Sta/Elev= 30
       0   63.75   103.7   63.41     114   61.49   123.6   57.72   128.7   56.85
   155.1   56.77   165.4   54.07   170.6   50.67   185.9   47.08   210.3    46.4
   228.1   47.35     260   55.27   297.2   55.25   334.3   53.85   358.6   50.94
   398.1   54.59   414.8   57.19   461.8   58.78   525.6   56.99   823.1   57.17
   834.3   58.56   859.7   57.59   890.5   59.16   897.5   57.43   908.1   57.25
  1131.3   56.89  1151.1   58.98  1217.8   60.13  1226.9   60.79  1233.4   63.49
#Mann= 4 ,-1 , 0
       0     .11       0   165.4    .125       0   165.4     .04       0
     260    .125       0
Bank Sta=165.4,260
XS Rating Curve= 0 ,0
Exp/Cntr=0.3,0.1

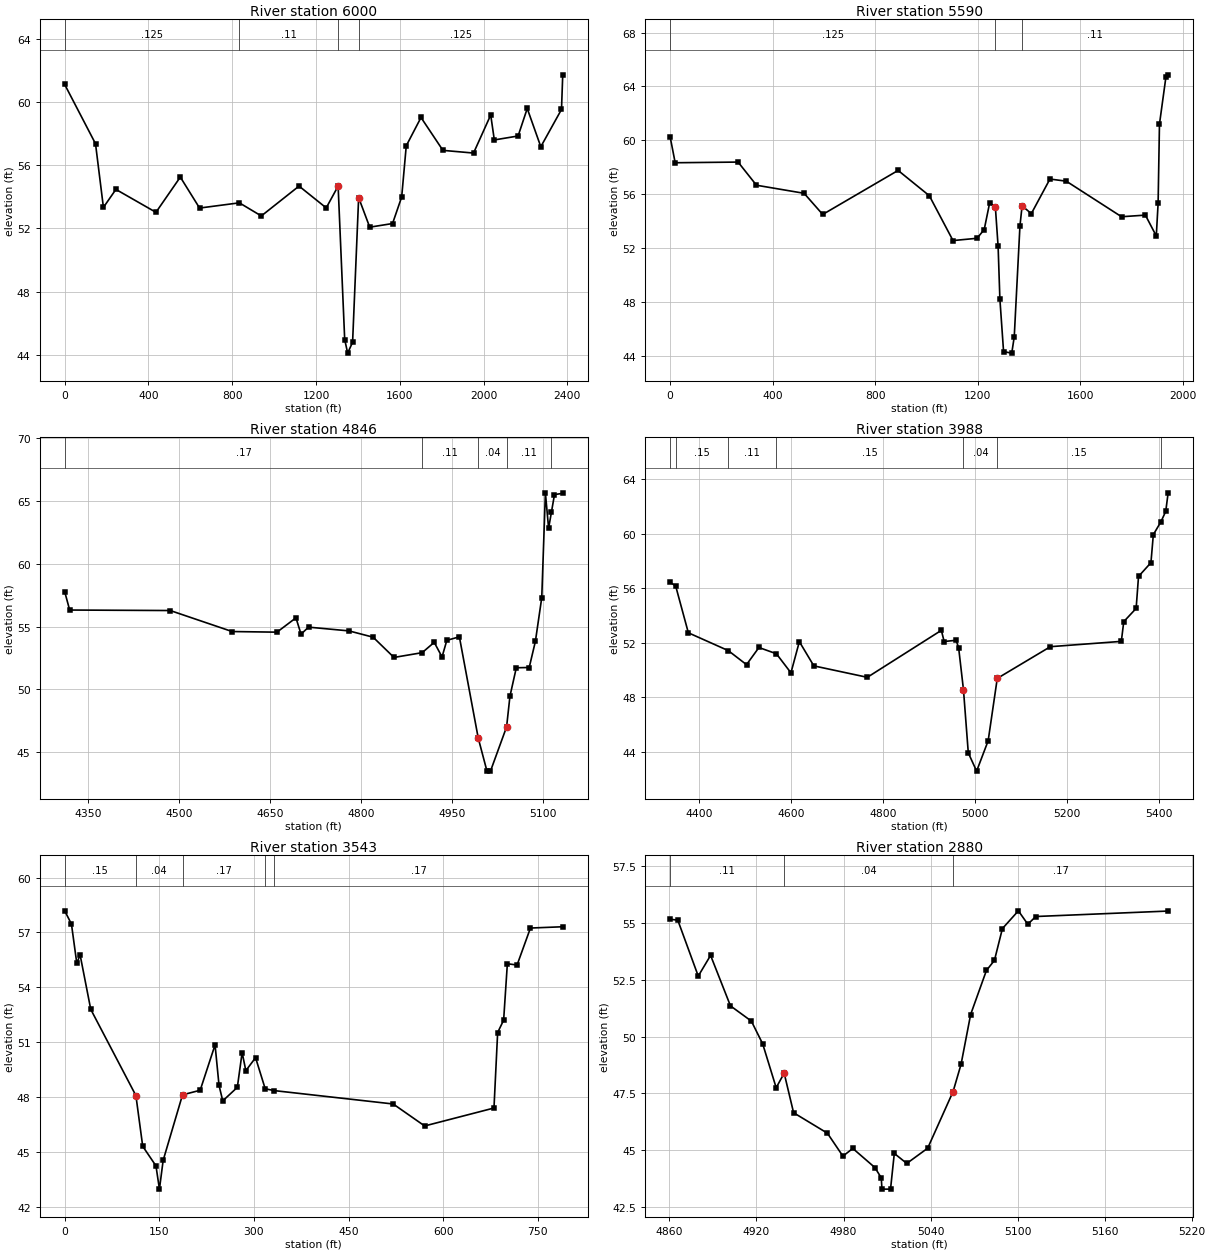
Type RM Length L Ch R = 1 ,6000    ,410,410,410
BEGIN DESCRIPTION:
BLACKS BRANCH 12.0
END DESCRIPTION:
XS GIS Cut Line= 3
      3898791.98     10008019.98        3900079.     10007616.42
      3901024.46     10007205.78
#Sta/Elev= 30
       0   61.11   147.2   57.36   184.9   53.33   244.5   54.47   435.8   53.02
   552.1   55.25   644.1   53.29   834.1   53.62   938.9   52.79  1119.1   54.68
  1248.9    53.3  1305.7   54.68  1337.1   44.97  1351.3   44.11  1374.8    44.8
  1403.7   53.95  1456.6   52.08  1565.6   52.31  1609.2   53.99  1631.1   57.23
  1701.5   59.02  1806.2   56.94  1952.4   56.77  2034.4   59.18  2051.6    57.6
  2165.2   57.85  2208.8   59.59  2273.6   57.17  2372.4   59.53  2378.3   61.72
#Mann= 4 ,-1 , 0
       0    .125       0   834.1     .11       0  1305.7     .04       0
  1403.7    .125       0
Bank Sta=1305.7,1403.7
XS Rating Curve= 0 ,0
Exp/Cntr=0.3,0.1

Type RM Length L Ch R = 1 ,5590    ,744,744,744
BEGIN DESCRIPTION:
BLACKS BRANCH 11.0
END DESCRIPTION:
XS GIS Cut Line= 3
      3899121.69     10008753.44      3900145.05     10008027.17
      3900791.25     10007793.37
#Sta/Elev= 30
       0   60.27    19.8   58.33   265.1   58.38   336.8   56.66   522.6   56.06
   595.1   54.49   889.1   57.76  1010.9   55.88  1103.2   52.55    1197   52.72
  1224.9   53.37  1246.1   55.35  1268.5   55.01  1279.1   52.11    1286   48.21
  1300.4    44.3  1332.3   44.19    1342    45.4  1364.2   53.63  1372.6   55.13
  1408.6   54.55  1481.2   57.12    1545   56.96  1760.4   54.32  1853.4   54.44
  1895.9   52.89    1903   55.32  1908.3    61.2  1933.6   64.72  1942.1   64.86
#Mann= 3 , 0 , 0
       0    .125       0  1268.5     .04       0  1372.6     .11       0
Bank Sta=1268.5,1372.6
XS Rating Curve= 0 ,0
Exp/Cntr=0.3,0.1

Type RM Length L Ch R = 1 ,4846    ,858,858,858
BEGIN DESCRIPTION:
BLACKS BRANCH 10.0
END DESCRIPTION:
XS GIS Cut Line= 3
      3901046.89     10008598.94      3900861.27     10007922.61
      3900824.31     10007808.17
#Sta/Elev= 30
  4311.3   57.77  4319.5   56.31  4485.4   56.27  4587.5    54.6  4661.5   54.55
  4692.8   55.69  4701.2   54.39  4713.5   54.95  4780.4   54.65  4820.1   54.15
  4854.5   52.54    4901   52.92  4920.9   53.74  4933.8   52.58  4941.7    53.9
  4962.4   54.18  4993.5   46.13  5007.9    43.5  5013.7    43.5  5040.3   47.02
  5045.8   49.45  5056.3   51.72  5077.6   51.74  5087.8   53.82  5098.3    57.3
  5104.3   65.63  5109.6   62.81  5114.2   64.08  5119.3   65.49  5132.9   65.59
#Mann= 5 ,-1 , 0
  4311.3     .17       0    4901     .11       0  4993.5     .04       0
  5040.3     .11       0  5114.2     .11       0
Bank Sta=4993.5,5040.3
XS Rating Curve= 0 ,0
Exp/Cntr=0.3,0.1

Type RM Length L Ch R = 1 ,3988    ,445,445,445
BEGIN DESCRIPTION:
Mapping XS 2bfff790
END DESCRIPTION:
XS GIS Cut Line= 2
        3901892.     10008378.87      3901562.53      10007347.1
#Sta/Elev= 30
  4336.8   56.44  4348.9   56.17  4376.5   52.73  4463.4   51.42    4503   50.39
    4530   51.65    4568   51.19  4599.6   49.79  4617.9   52.08  4649.4    50.3
  4765.7   49.46  4926.7   52.91  4932.8   52.09  4958.8   52.18  4964.3   51.63
  4974.8   48.55  4985.3   43.91  5003.4   42.57  5028.5    44.8  5048.3   49.38
  5163.8   51.71  5318.1    52.1  5323.4   53.55  5350.3   54.52  5355.5   56.87
  5382.5   57.88  5387.7   59.94  5404.3   60.89  5414.7   61.65  5419.9   63.01
#Mann= 7 ,-1 , 0
  4336.8     .11       0  4348.9     .15       0  4463.4     .11       0
    4568     .15       0  4974.8     .04       0  5048.3     .15       0
  5404.3     .11       0
Bank Sta=4974.8,5048.3
XS Rating Curve= 0 ,0
Exp/Cntr=0.3,0.1

Type RM Length L Ch R = 1 ,3543    ,663,663,663
BEGIN DESCRIPTION:
BLACKS BRANCH 8.0
END DESCRIPTION:
XS GIS Cut Line= 3
      3902038.14     10008111.52      3902067.04      10007975.3
      3902409.88     10007422.61
#Sta/Elev= 30
       0   58.18    10.7   57.46    19.2   55.31    24.4   55.78    41.3    52.8
   112.9   48.09   123.7   45.32   144.7   44.25   150.2   42.98   156.1   44.55
   186.8   48.13   214.8   48.38   238.4   50.86   244.7   48.64   250.6    47.8
   273.7   48.54   281.3   50.44   287.2   49.45   302.6   50.16   317.9   48.46
   332.5   48.36   520.8   47.63   570.7   46.43   680.6   47.41   686.4   51.53
   695.9   52.21   701.8   55.29   717.2   55.22   738.4   57.24   789.6   57.31
#Mann= 5 ,-1 , 0
       0     .15       0   112.9     .04       0   186.8     .17       0
   317.9     .15       0   332.5     .17       0
Bank Sta=112.9,186.8
XS Rating Curve= 0 ,0
Exp/Cntr=0.3,0.1

Type RM Length L Ch R = 1 ,2880    ,405,405,405
BEGIN DESCRIPTION:
BLACKS BRANCH 6.0
END DESCRIPTION:
XS GIS Cut Line= 3
       3902310.4     10008472.65      3902391.14     10008511.72
      3902621.65     10008406.23
#Sta/Elev= 30
  4860.5   55.16  4865.8   55.12  4879.9   52.66  4888.4   53.57  4902.1   51.35
  4916.5   50.68  4924.3   49.68  4933.6   47.75  4939.1   48.39  4945.6   46.65
  4968.9   45.75  4979.6   44.74  4986.4   45.08  5001.6   44.24    5006   43.79
  5006.5   43.29  5012.4   43.29    5015   44.86  5023.6   44.42    5038   45.09
  5055.5   47.58    5061   48.78  5067.6   50.97  5078.5   52.91    5084   53.35
  5089.5   54.75  5100.5   55.53    5107   54.94  5112.5   55.28  5203.7   55.52
#Mann= 3 , 0 , 0
  4860.5     .11       0  4939.1     .04       0  5055.5     .17       0
Bank Sta=4939.1,5055.5
XS Rating Curve= 0 ,0
Exp/Cntr=0.3,0.1

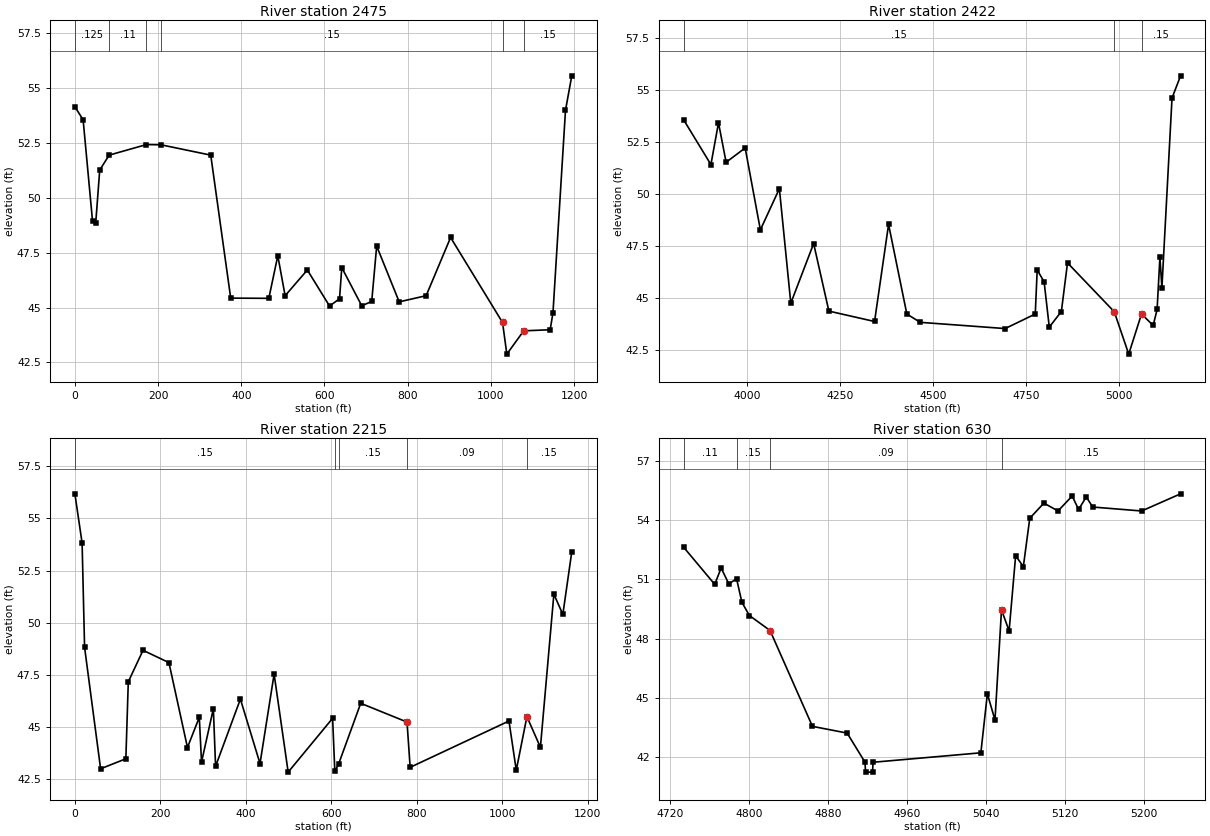
Type RM Length L Ch R = 1 ,2475    ,53,53,53
BEGIN DESCRIPTION:
BLACKS BRANCH 5.0
END DESCRIPTION:
XS GIS Cut Line= 4
      3902192.65     10009453.49      3902482.36     10009315.54
      3902753.38     10008653.99       3902737.5     10008496.09
#Sta/Elev= 30
       0   54.14    19.8   53.55    42.5   48.92    50.1   48.85    59.7   51.26
    82.4   51.94   171.9   52.42     207   52.41   326.6   51.94   374.6   45.43
   466.2   45.42   487.8   47.36   505.4   45.54   558.8   46.71   612.2   45.07
   636.2    45.4   641.6   46.82   689.6   45.08   713.6   45.28   725.5    47.8
   779.6   45.26   844.4   45.54   903.2   48.19  1028.1   44.32  1038.4   42.88
  1078.9   43.94  1142.6   43.99  1149.3   44.76  1179.4   53.98  1194.5   55.55
#Mann= 6 ,-1 , 0
       0    .125       0    82.4     .11       0   171.9    .125       0
     207     .15       0  1028.1     .04       0  1078.9     .15       0
Bank Sta=1028.1,1078.9
XS Rating Curve= 0 ,0
Exp/Cntr=0.3,0.1

Type RM Length L Ch R = 1 ,2422    ,207,207,207
BEGIN DESCRIPTION:
Mapping XS 0bb790ea
END DESCRIPTION:
XS GIS Cut Line= 3
      3902785.67     10009782.57      3902939.32     10009074.22
      3902757.02     10008490.86
#Sta/Elev= 30
  3830.2   53.56  3903.4   51.41  3923.8   53.42  3944.3   51.52  3995.5   52.21
  4036.4   48.27  4087.5   50.25  4118.2   44.74  4179.6   47.61  4220.6   44.36
  4343.4   43.86  4381.1   48.53  4430.2   44.22  4466.2   43.82  4694.5   43.52
  4775.5   44.22  4780.7   46.34  4799.3   45.77  4813.2   43.59  4845.7   44.34
  4862.2   46.68  4987.9   44.33  5026.8   42.29  5061.2   44.22  5092.6   43.67
  5103.1   44.44  5110.7   46.96    5116   45.48  5143.2   54.61  5166.2   55.68
#Mann= 3 , 0 , 0
  3830.2     .15       0  4987.9     .04       0  5061.2     .15       0
Bank Sta=4987.9,5061.2
XS Rating Curve= 0 ,0
Exp/Cntr=0.3,0.1

Type RM Length L Ch R = 1 ,2215    ,1585,1585,1585
BEGIN DESCRIPTION:
BLACKS BRANCH 4.0
END DESCRIPTION:
XS GIS Cut Line= 4
      3903203.48       10009629.      3903275.75     10009501.93
      3903102.08     10008928.39      3902973.18     10008531.25
#Sta/Elev= 30
       0   56.18    16.9   53.82    22.7   48.82    60.2      43   119.3   43.48
     125   47.17   159.5   48.68   220.1   48.09   263.5   44.02   291.2   45.47
   296.4   43.32   324.1   45.88   329.3   43.12   387.4   46.34   433.3   43.25
   466.3   47.54   499.2   42.84   603.2   45.42   608.4   42.88   617.3   43.23
     669   46.14   777.4   45.24   784.7   43.07    1016   45.29  1033.1   42.93
    1058    45.5  1089.6   44.03  1121.1   51.37  1142.1    50.4    1163    53.4
#Mann= 5 ,-1 , 0
       0     .15       0   608.4     .12       0   617.3     .15       0
   777.4     .09       0    1058     .15       0
Bank Sta=777.4,1058
XS Rating Curve= 0 ,0
Exp/Cntr=0.3,0.1

Type RM Length L Ch R = 1 ,630     ,0,0,0
BEGIN DESCRIPTION:
BLACKS BRANCH 3.0
END DESCRIPTION:
XS GIS Cut Line= 2
       3903482.7     10009789.51      3903868.11     10009466.61
#Sta/Elev= 30
  4734.2   52.63  4765.6   50.75  4772.1   51.58  4779.9   50.77  4787.7   51.04
  4793.1   49.84  4800.7   49.17  4821.6   48.41  4864.5   43.55  4899.6   43.21
  4917.7   41.73  4918.2   41.23  4925.3   41.23  4925.8   41.73  5034.9   42.21
  5041.5    45.2  5049.2   43.87  5055.8   49.46  5063.5   48.39  5070.1    52.2
  5077.9   51.65  5084.4    54.1  5098.7   54.87    5113   54.47  5127.3   55.23
  5133.8   54.55  5141.6   55.18  5148.1   54.67  5197.6   54.47    5237   55.34
#Mann= 4 ,-1 , 0
  4734.2     .11       0  4787.7     .15       0  4821.6     .09       0
  5055.8     .15       0
Bank Sta=4821.6,5055.8
XS Rating Curve= 0 ,0
Exp/Cntr=0.3,0.1

Chan Stop Cuts=-1
Use User Specified Reach Order=0
Composite Channel Slope=5