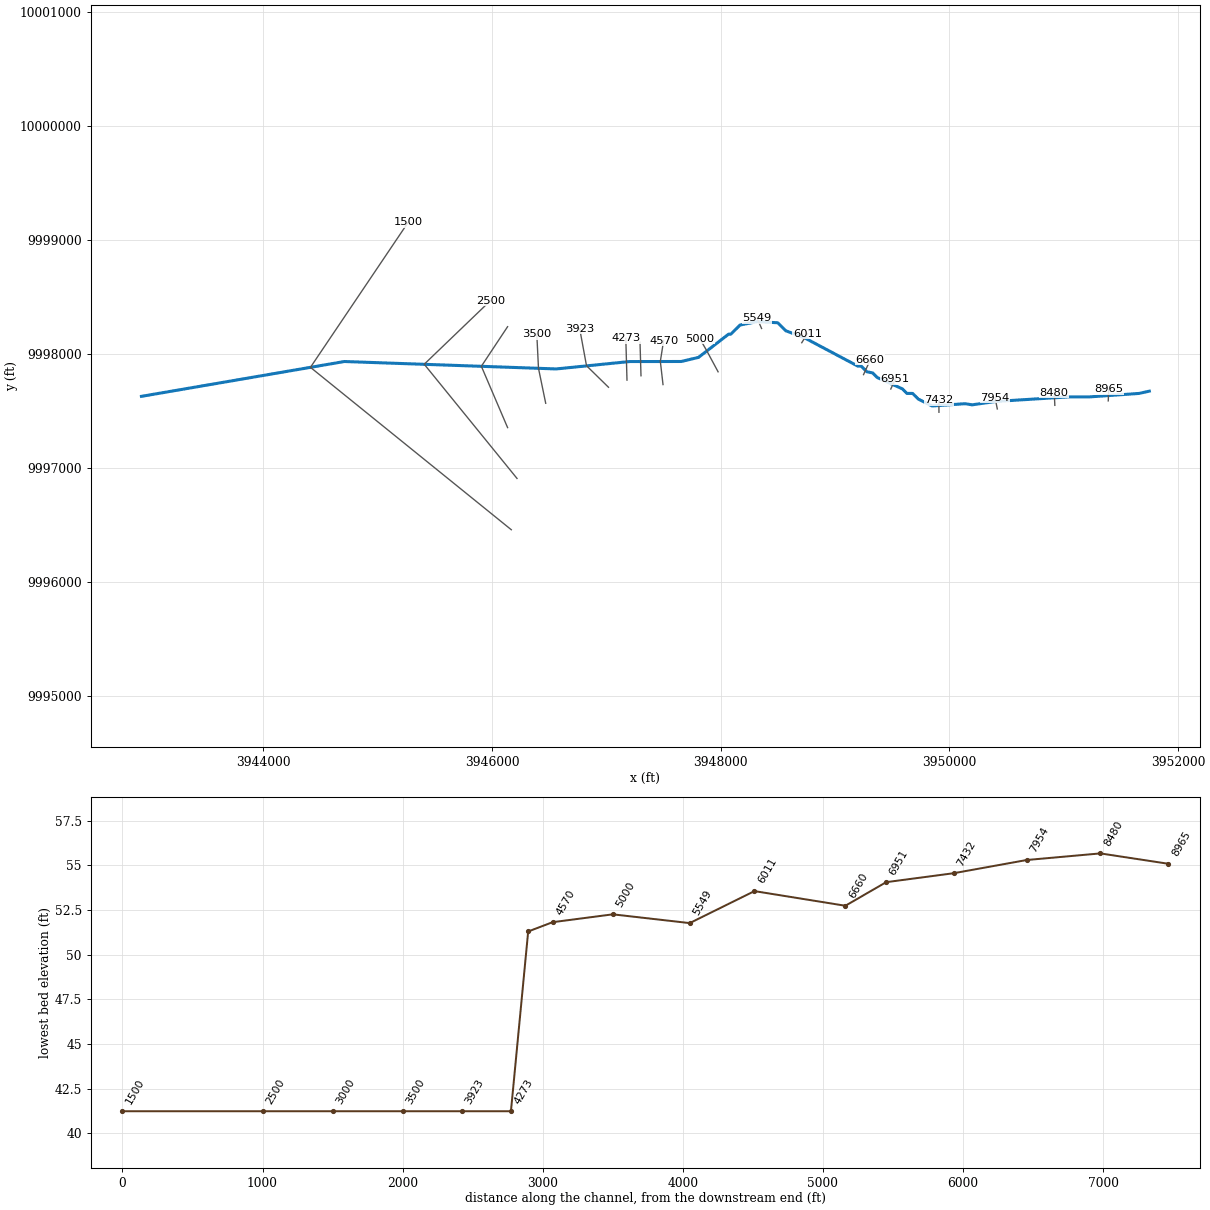
--- DUNKS DITCH.prj (project) ---

Proj Title=DUNKS DITCH Base Level Engineering
Current Plan=p01
Default Exp/Contr=0.3,0.1
English Units
Geom File=g01
Flow File=f01
Flow File=f02
Plan File=p01
Y Axis Title=Elevation
X Axis Title(PF)=Main Channel Distance
X Axis Title(XS)=Station
BEGIN DESCRIPTION:
DUNKS DITCH
END DESCRIPTION:
DSS Export Rating Curves= 0
DSS Export Rating Curve Sorted= 0
DSS Export Volume Flow Curves= 0
DXF OffsetX= 0
DXF OffsetY= 0
DXF ScaleX= 1
DXF ScaleY= 10

--- DUNKS DITCH.p01 (plan) ---

Plan Title=Multiple Run
Short Identifier=Multiple
Geom File=g01
Flow File=f01
Subcritical Flow
K Sum by GR= 0
Std Step Tol= 0.01
Critical Tol= 0.01
Num of Std Step Trials= 20
Max Error Tol= 0.3
Flow Tol Ratio= 0.001
Split Flow NTrial= 30
Split Flow Tol= 0.02
Split Flow Ratio= 0.02
Log Output Level= 0
Friction Slope Method= 1
Unsteady Friction Slope Method= 2
Unsteady Bridges Friction Slope Method= 1
Parabolic Critical Depth
Global Vel Dist=  1 , 1 , 1
Global Log Level= 0
CheckData=True
Encroach Param= -1, 0, 0, 0
BEGIN DESCRIPTION:
Multiple Run
END DESCRIPTION:

--- DUNKS DITCH.f01 (steady flow) ---

Flow Title=Multiple
Program Version=4.10
Number of Profiles= 7
Profile Names=10-year,25-year,50-year,1pct_min,100-year,1pct_plu,500-year
River Rch & RM=DUNKS DITCH,Reach-1         ,8965
     238     295     376     158     478    1444     802
Boundary for River Rch & Prof#=DUNKS DITCH,Reach-1         , 1
Up Type= 0
Dn Type= 3
Dn Slope=0.0001
Boundary for River Rch & Prof#=DUNKS DITCH,Reach-1         , 2
Up Type= 0
Dn Type= 3
Dn Slope=0.0001
Boundary for River Rch & Prof#=DUNKS DITCH,Reach-1         , 3
Up Type= 0
Dn Type= 3
Dn Slope=0.0001
Boundary for River Rch & Prof#=DUNKS DITCH,Reach-1         , 4
Up Type= 0
Dn Type= 3
Dn Slope=0.0001
Boundary for River Rch & Prof#=DUNKS DITCH,Reach-1         , 5
Up Type= 0
Dn Type= 3
Dn Slope=0.0001
Boundary for River Rch & Prof#=DUNKS DITCH,Reach-1         , 6
Up Type= 0
Dn Type= 3
Dn Slope=0.0001
Boundary for River Rch & Prof#=DUNKS DITCH,Reach-1         , 7
Up Type= 0
Dn Type= 3
Dn Slope=0.0001
DSS Import GetInterval= 0
DSS Import GetPeak= 0
DSS Import FillOption= 0

--- DUNKS DITCH.f02 (steady flow) ---

Flow Title=Orig_BLE_Flows
Program Version=4.10
Number of Profiles= 7
Profile Names=10-year,25-year,50-year,1pct_min,100-year,1pct_plu,500-year
River Rch & RM=DUNKS DITCH,Reach-1         ,8965
     238     289     327     122     368    1111     466
Boundary for River Rch & Prof#=DUNKS DITCH,Reach-1         , 1
Up Type= 0
Dn Type= 3
Dn Slope=0.0001
Boundary for River Rch & Prof#=DUNKS DITCH,Reach-1         , 2
Up Type= 0
Dn Type= 3
Dn Slope=0.0001
Boundary for River Rch & Prof#=DUNKS DITCH,Reach-1         , 3
Up Type= 0
Dn Type= 3
Dn Slope=0.0001
Boundary for River Rch & Prof#=DUNKS DITCH,Reach-1         , 4
Up Type= 0
Dn Type= 3
Dn Slope=0.0001
Boundary for River Rch & Prof#=DUNKS DITCH,Reach-1         , 5
Up Type= 0
Dn Type= 3
Dn Slope=0.0001
Boundary for River Rch & Prof#=DUNKS DITCH,Reach-1         , 6
Up Type= 0
Dn Type= 3
Dn Slope=0.0001
Boundary for River Rch & Prof#=DUNKS DITCH,Reach-1         , 7
Up Type= 0
Dn Type= 3
Dn Slope=0.0001
DSS Import GetInterval= 0
DSS Import GetPeak= 0
DSS Import FillOption= 0

--- DUNKS DITCH.g01 (geometry) ---

Geom Title=Existing Conditions
Program Version=4.10

River Reach=DUNKS DITCH     ,Reach-1
Reach XY= 30
      3951748.23      9997676.84      3951658.23      9997656.84
      3951228.23      9997626.84      3951048.23      9997626.84
      3950408.23      9997586.84      3950198.23      9997556.84
      3950138.23      9997566.84      3949848.23      9997546.84
      3949728.23      9997606.84      3949678.23      9997656.84
      3949628.23      9997656.84      3949588.23      9997696.84
      3949368.23      9997796.84      3949328.23      9997836.84
      3949278.23      9997846.84      3949228.23      9997896.84
      3949198.23      9997896.84      3948728.23      9998146.84
      3948568.23      9998206.84      3948498.23      9998276.84
      3948318.23      9998286.84      3948168.23      9998256.84
      3948088.23      9998176.84      3948068.23      9998176.84
      3947805.26      9997973.03       3947654.2      9997937.09
      3947200.69      9997936.47      3946560.88      9997871.75
      3944708.23      9997936.84      3942932.74       9997631.3

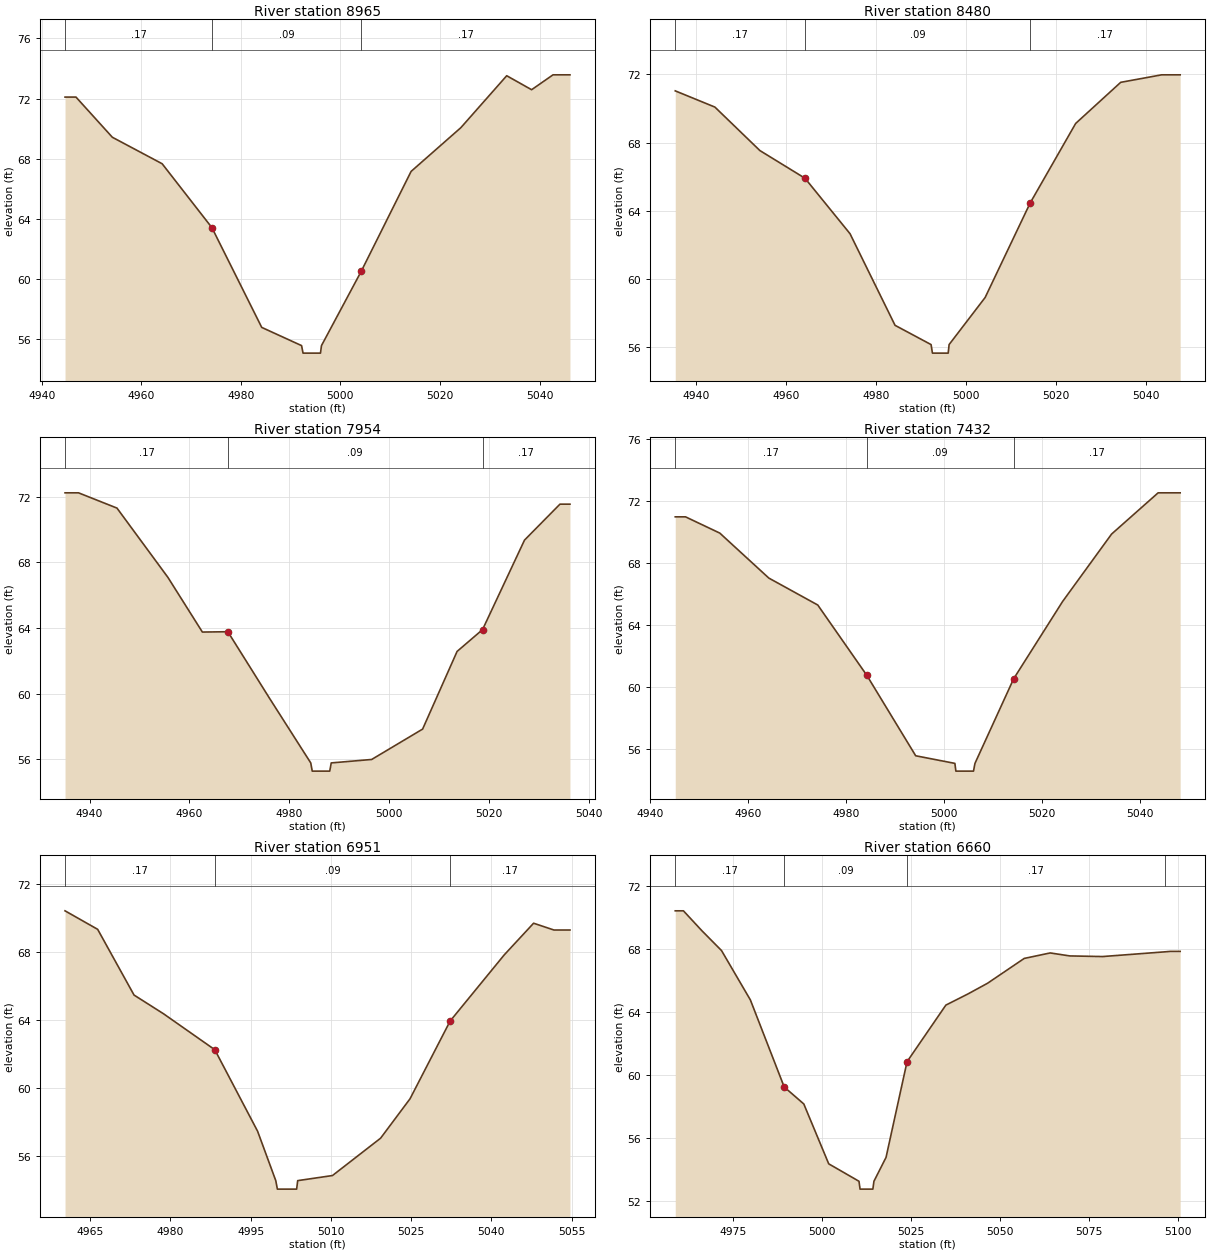
Type RM Length L Ch R = 1 ,8965    ,485,485,485
BEGIN DESCRIPTION:
Mapping XS 2b976f0b
END DESCRIPTION:
XS GIS Cut Line= 2
      3951388.96      9997591.59      3951393.21       9997692.9
#Sta/Elev= 17
  4944.7    72.1  4946.9    72.1  4954.2   69.43  4964.2   67.67  4974.2   63.42
  4984.2   56.79  4992.2   55.58  4992.5   55.08    4996   55.08  4996.2   55.58
  5004.2   60.53  5014.2   67.16  5024.2   70.07  5033.4   73.52  5038.4   72.59
  5042.7   73.58  5046.1   73.58
#Mann= 3 , 0 , 0
  4944.7     .17       0  4974.2     .09       0  5004.2     .17       0
Bank Sta=4974.2,5004.2
XS Rating Curve= 0 ,0
Exp/Cntr=0.3,0.1

Type RM Length L Ch R = 1 ,8480    ,526,526,526
BEGIN DESCRIPTION:
Mapping XS 1a45e1f8
END DESCRIPTION:
XS GIS Cut Line= 2
      3950921.86      9997552.31      3950916.65      9997664.29
#Sta/Elev= 16
  4935.4   71.03  4944.2   70.08  4954.2   67.53  4964.2   65.91  4974.2   62.66
  4984.2   57.29  4992.2   56.16  4992.5   55.66    4996   55.66  4996.2   56.16
  5004.2   58.92  5014.2   64.46  5024.3   69.12  5034.3   71.53  5043.4   71.97
  5047.5   71.97
#Mann= 3 , 0 , 0
  4935.4     .17       0  4964.2     .09       0  5014.2     .17       0
Bank Sta=4964.2,5014.2
XS Rating Curve= 0 ,0
Exp/Cntr=0.3,0.1

Type RM Length L Ch R = 1 ,7954    ,522,522,522
BEGIN DESCRIPTION:
Mapping XS 5bdd17e1
END DESCRIPTION:
XS GIS Cut Line= 2
       3950418.6      9997520.83      3950398.74      9997619.96
#Sta/Elev= 18
  4935.1   72.24  4937.8   72.24  4945.5   71.31  4955.7   67.09  4962.6   63.76
  4967.7   63.78  4976.1    59.7  4984.3   55.79  4984.6   55.29  4988.1   55.29
  4988.4   55.79  4996.5      56  5006.7   57.85  5013.6   62.58  5018.7   63.91
  5027.1   69.36  5034.2   71.55  5036.2   71.55
#Mann= 3 , 0 , 0
  4935.1     .17       0  4967.7     .09       0  5018.7     .17       0
Bank Sta=4967.7,5018.7
XS Rating Curve= 0 ,0
Exp/Cntr=0.3,0.1

Type RM Length L Ch R = 1 ,7432    ,481,481,481
BEGIN DESCRIPTION:
Mapping XS 207797f8
END DESCRIPTION:
XS GIS Cut Line= 2
      3949908.28      9997491.95      3949907.75      9997595.04
#Sta/Elev= 16
  4945.1   70.96  4947.2   70.96  4954.2   69.91  4964.2   67.01  4974.2   65.27
  4984.2   60.74  4994.2   55.54  5002.2   55.05  5002.4   54.55    5006   54.55
  5006.3   55.05  5014.2   60.51  5024.2    65.5  5034.2   69.85  5043.7   72.51
  5048.2   72.51
#Mann= 3 , 0 , 0
  4945.1     .17       0  4984.2     .09       0  5014.2     .17       0
Bank Sta=4984.2,5014.2
XS Rating Curve= 0 ,0
Exp/Cntr=0.3,0.1

Type RM Length L Ch R = 1 ,6951    ,291,291,291
BEGIN DESCRIPTION:
Mapping XS d348e6c9
END DESCRIPTION:
XS GIS Cut Line= 2
      3949486.96      9997695.54      3949526.02      9997781.48
#Sta/Elev= 18
  4960.3   70.44  4966.4   69.35  4973.2   65.48  4978.7   64.38  4988.3   62.26
  4996.3   57.46  4999.7   54.55    5000   54.05  5003.6   54.05  5003.8   54.55
  5010.3   54.85  5019.3   57.05  5024.8   59.37  5032.3   63.95  5042.4   67.84
  5047.9   69.71  5051.7   69.31  5054.7   69.31
#Mann= 3 , 0 , 0
  4960.3     .17       0  4988.3     .09       0  5032.3     .17       0
Bank Sta=4988.3,5032.3
XS Rating Curve= 0 ,0
Exp/Cntr=0.3,0.1

Type RM Length L Ch R = 1 ,6660    ,649,649,649
BEGIN DESCRIPTION:
Mapping XS 42daa152
END DESCRIPTION:
XS GIS Cut Line= 2
      3949248.56      9997821.83      3949307.16      9997950.96
#Sta/Elev= 24
  4958.7   70.44    4961   70.44  4966.2   69.17  4971.7   67.91  4979.8   64.77
  4989.3   59.23  4994.8   58.15  5001.8   54.34  5010.3   53.23  5010.6   52.73
  5014.2   52.73  5014.5   53.23  5017.9   54.75  5023.8   60.84  5034.7   64.44
  5040.9   65.15  5046.4   65.83  5056.7   67.41    5064   67.76  5069.5   67.57
  5078.7   67.53  5096.2   67.83  5097.8   67.86  5100.5   67.86
#Mann= 4 ,-1 , 0
  4958.7     .17       0  4989.3     .09       0  5023.8     .17       0
  5096.2     .11       0
Bank Sta=4989.3,5023.8
XS Rating Curve= 0 ,0
Exp/Cntr=0.3,0.1

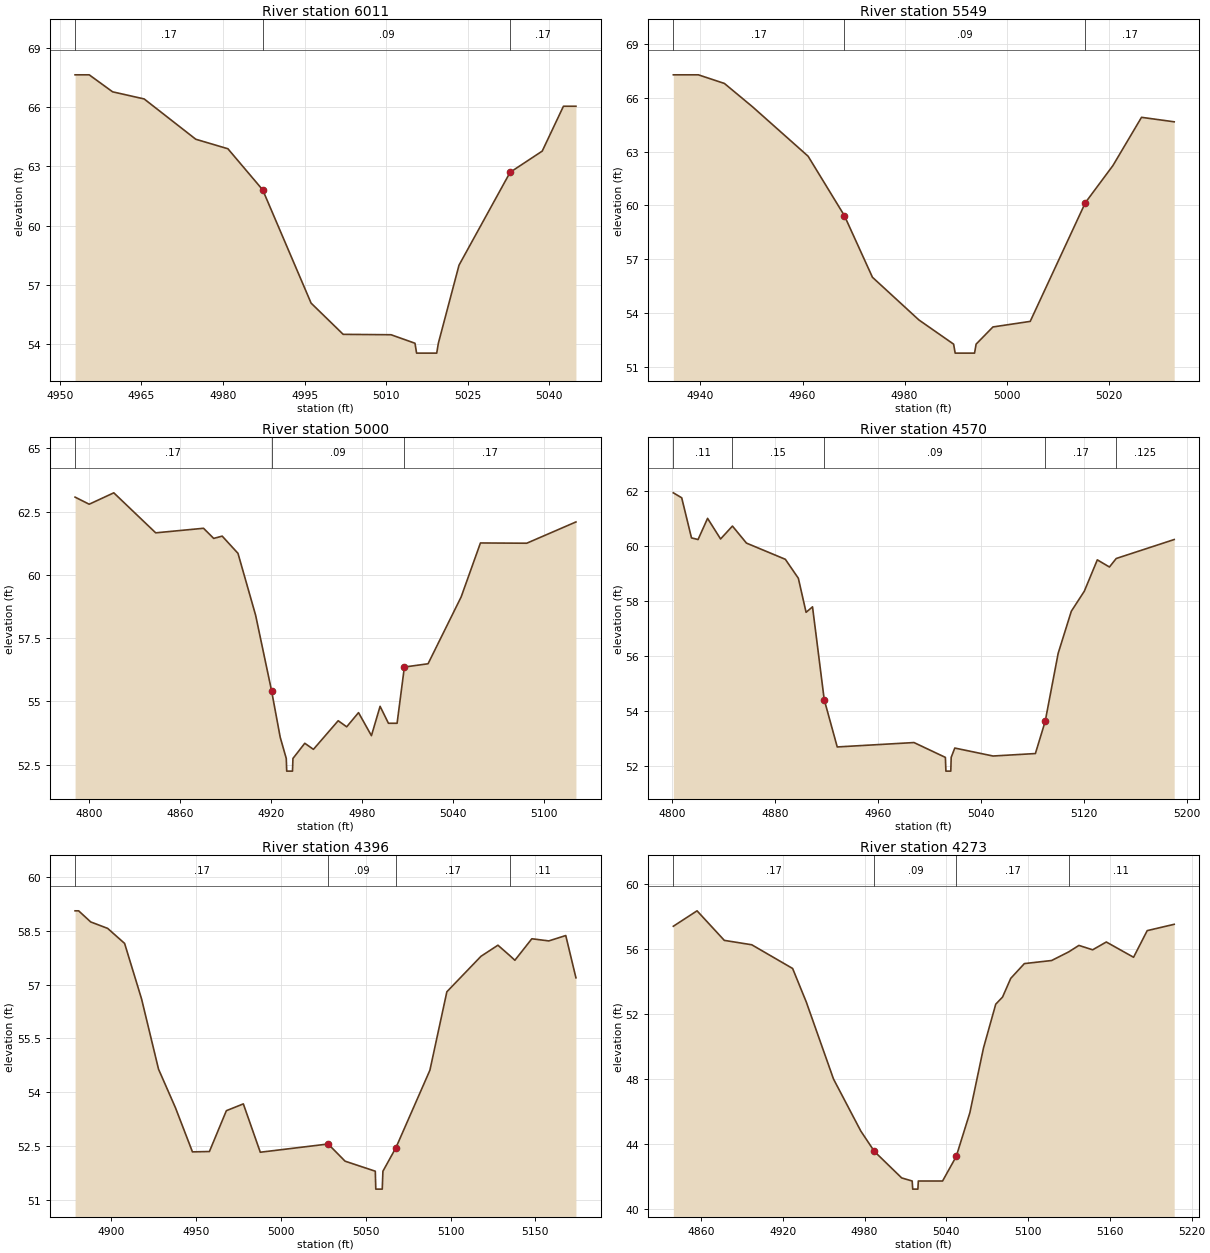
Type RM Length L Ch R = 1 ,6011    ,462,462,462
BEGIN DESCRIPTION:
Mapping XS 2d6f07db
END DESCRIPTION:
XS GIS Cut Line= 2
      3948708.29      9998101.76      3948757.03       9998179.9
#Sta/Elev= 19
  4952.8   67.63  4955.4   67.63  4959.7   66.77  4965.5   66.41    4975   64.37
  4980.9   63.89  4987.3   61.81  4996.2   56.08  5002.1    54.5  5010.9   54.48
  5015.3   54.05  5015.6   53.55  5019.3   53.55  5019.6   54.05  5023.4      58
  5032.8    62.7  5038.7   63.77  5042.6   66.04  5044.9   66.04
#Mann= 3 , 0 , 0
  4952.8     .17       0  4987.3     .09       0  5032.8     .17       0
Bank Sta=4987.3,5032.8
XS Rating Curve= 0 ,0
Exp/Cntr=0.3,0.1

Type RM Length L Ch R = 1 ,5549    ,549,549,549
BEGIN DESCRIPTION:
Mapping XS 907458a8
END DESCRIPTION:
XS GIS Cut Line= 2
      3948356.74      9998226.82       3948318.1      9998316.99
#Sta/Elev= 18
  4934.7   67.28  4939.6   67.28  4944.7    66.8  4950.2    65.5  4961.1   62.74
  4968.2   59.43  4973.7   55.99  4982.8   53.61  4989.6   52.26  4989.9   51.76
  4993.7   51.76    4994   52.26  4997.3   53.22  5004.6   53.53  5015.4   60.15
  5020.8   62.22  5026.4   64.91  5032.8   64.66
#Mann= 3 , 0 , 0
  4934.7     .17       0  4968.2     .09       0  5015.4     .17       0
Bank Sta=4968.2,5015.4
XS Rating Curve= 0 ,0
Exp/Cntr=0.3,0.1

Type RM Length L Ch R = 1 ,5000    ,430,430,430
BEGIN DESCRIPTION:
DUNKS DITCH 10.0
END DESCRIPTION:
XS GIS Cut Line= 3
      3947976.54      9997846.59      3947877.58      9998030.79
      3947817.67      9998135.69
#Sta/Elev= 30
  4790.9   63.07  4800.2   62.79  4816.4   63.24    4844   61.66  4875.5   61.84
  4882.2   61.44  4887.8   61.53  4898.2   60.85  4909.8   58.41  4920.3   55.43
    4926   53.59    4930   52.75  4930.3   52.25  4934.1   52.25  4934.4   52.75
  4942.2   53.35  4947.9   53.11  4964.2   54.24  4969.8      54  4977.6   54.56
  4986.1   53.65  4991.8   54.81  4997.3   54.14    5003   54.14  5007.8   56.36
  5023.4   56.49  5045.2   59.13  5057.9   61.26  5088.4   61.25  5120.8   62.09
#Mann= 3 , 0 , 0
  4790.9     .17       0  4920.3     .09       0  5007.8     .17       0
Bank Sta=4920.3,5007.8
XS Rating Curve= 0 ,0
Exp/Cntr=0.3,0.1

Type RM Length L Ch R = 1 ,4570    ,174,174,174
BEGIN DESCRIPTION:
DUNKS DITCH 9.0
END DESCRIPTION:
XS GIS Cut Line= 3
      3947494.77      9997734.63      3947471.34      9997937.73
      3947499.98      9998120.04
#Sta/Elev= 30
  4800.9   61.94  4807.4   61.76    4815    60.3  4820.1   60.24  4827.5   61.01
  4837.6   60.26  4846.8   60.73  4857.7   60.11  4887.9   59.52    4898   58.83
    4904   57.59    4909   57.79  4918.1   54.41  4928.2   52.69  4987.8   52.85
  5012.2   52.31  5012.6   51.81  5016.4   51.81  5016.7   52.31  5019.5   52.65
  5049.2   52.36  5082.1   52.45  5089.7   53.62  5099.8    56.1    5110   57.63
  5120.1   58.36  5130.2    59.5  5139.6   59.24  5144.9   59.55  5189.9   60.24
#Mann= 5 ,-1 , 0
  4800.9     .11       0  4846.8     .15       0  4918.1     .09       0
  5089.7     .17       0  5144.9    .125       0
Bank Sta=4918.1,5089.7
XS Rating Curve= 0 ,0
Exp/Cntr=0.3,0.1

Type RM Length L Ch R = 1 ,4396    ,123,123,123
BEGIN DESCRIPTION:
Mapping XS 75541f4c
END DESCRIPTION:
XS GIS Cut Line= 2
      3947302.17      9997811.92      3947293.52       9998107.1
#Sta/Elev= 30
  4878.6   59.06  4880.7   59.06  4887.8   58.75  4897.8   58.57  4907.8   58.15
  4917.8    56.6  4927.8   54.64  4937.8   53.56  4947.8   52.33  4957.8   52.34
  4967.8   53.48  4977.8   53.67  4987.8   52.32  5027.8   52.55  5037.8   52.07
  5055.6   51.79  5055.9   51.29  5059.7   51.29  5060.1   51.79  5067.8   52.45
  5087.8   54.61  5097.8    56.8  5117.9   57.79  5127.9    58.1  5134.9   57.81
  5137.9   57.68  5147.9   58.28  5157.9   58.22  5167.9   58.37  5173.9   57.19
#Mann= 4 ,-1 , 0
  4878.6     .17       0  5027.8     .09       0  5067.8     .17       0
  5134.9     .11       0
Bank Sta=5027.8,5067.8
XS Rating Curve= 0 ,0
Exp/Cntr=0.3,0.1

Type RM Length L Ch R = 1 ,4273    ,350,350,350
BEGIN DESCRIPTION:
Mapping XS 50b6aab0
END DESCRIPTION:
XS GIS Cut Line= 2
      3947179.67      9997773.64      3947169.25       9998140.9
#Sta/Elev= 30
  4839.7   57.42  4857.1   58.37  4877.1   56.55  4897.2   56.28  4927.2   54.82
  4937.2   52.76  4957.2   48.01  4977.2   44.81  4987.2   43.55  5007.2   41.92
  5014.9   41.73  5015.3   41.23  5019.1   41.23  5019.4   41.73  5037.2   41.73
  5047.2   43.24  5057.2   45.93  5067.2   49.92  5076.2   52.62  5081.2   53.06
  5087.2   54.21  5097.2   55.12  5117.2   55.31  5129.7   55.84  5137.2   56.24
  5147.3   55.97  5157.3   56.45  5177.3   55.51  5187.3   57.15  5207.1   57.54
#Mann= 4 ,-1 , 0
  4839.7     .17       0  4987.2     .09       0  5047.2     .17       0
  5129.7     .11       0
Bank Sta=4987.2,5047.2
XS Rating Curve= 0 ,0
Exp/Cntr=0.3,0.1

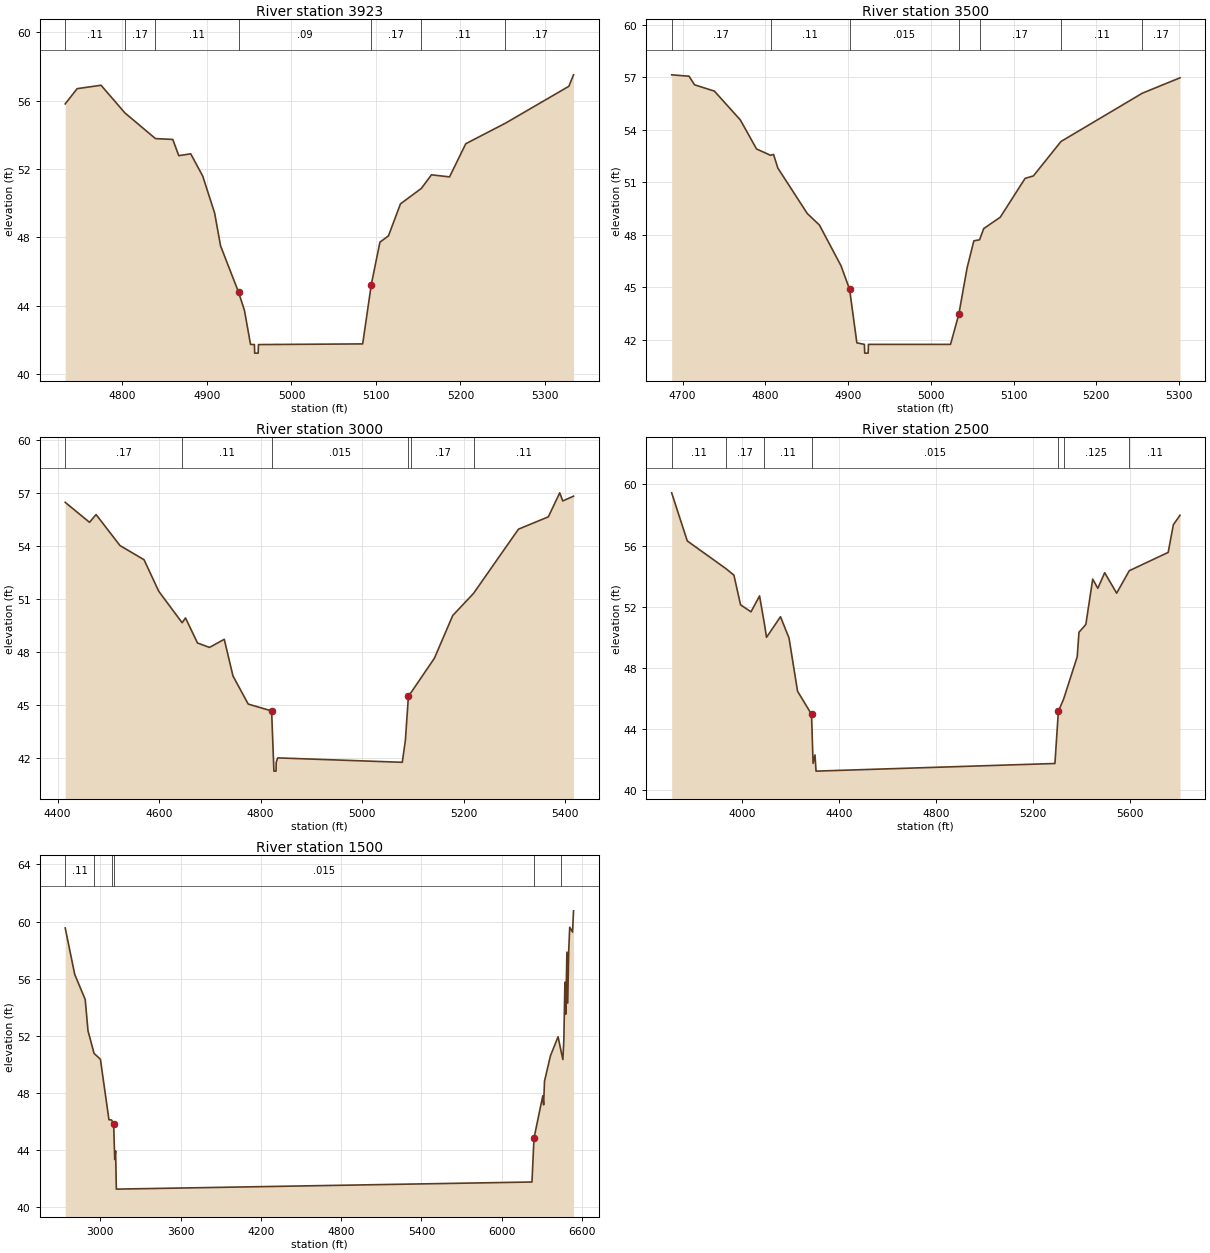
Type RM Length L Ch R = 1 ,3923    ,423,423,423
BEGIN DESCRIPTION:
DUNKS DITCH 8.0
END DESCRIPTION:
XS GIS Cut Line= 3
      3947017.87      9997711.05       3946825.6      9997899.95
      3946765.67      9998226.46
#Sta/Elev= 30
  4732.3   55.81  4746.4    56.7  4774.7    56.9    4803   55.28  4839.1   53.78
  4859.6   53.73  4866.7   52.78  4880.8   52.89    4895   51.59  4909.1   49.43
  4916.1   47.51  4937.4    44.8  4944.4   43.73  4951.6   41.74  4956.2   41.73
  4956.5   41.23  4960.6   41.23    4961   41.73  5084.3   41.77  5094.5   45.24
  5104.7   47.72  5114.8   48.09    5129   49.96  5153.8   50.87  5165.7   51.66
  5187.1   51.54  5206.3   53.48  5253.2   54.68  5328.3   56.84  5333.8   57.51
#Mann= 7 ,-1 , 0
  4732.3     .11       0    4803     .17       0  4839.1     .11       0
  4937.4     .09       0  5094.5     .17       0  5153.8     .11       0
  5253.2     .17       0
Bank Sta=4937.4,5094.5
XS Rating Curve= 0 ,0
Exp/Cntr=0.3,0.1

Type RM Length L Ch R = 1 ,3500    ,500,500,500
BEGIN DESCRIPTION:
DUNKS DITCH 7.0
END DESCRIPTION:
XS GIS Cut Line= 3
      3946468.73      9997570.53      3946405.58       9997877.3
       3946390.7      9998178.03
#Sta/Elev= 30
  4686.8   57.14  4707.8   57.06  4714.4   56.57  4738.4   56.21  4769.8   54.56
  4789.4    52.9  4806.3   52.54  4809.9   52.59  4815.1   51.81  4850.7   49.21
  4865.4   48.55  4891.5   46.22  4901.8   44.88  4910.6   41.82  4919.7   41.73
  4920.1   41.23  4924.2   41.23  4924.6   41.73  5023.8   41.73  5033.8   43.45
  5043.8    46.1    5052   47.65  5058.9   47.71  5063.9   48.35  5083.9      49
  5113.9   51.22  5123.9   51.36  5157.3   53.33  5255.6   56.09  5301.1   56.97
#Mann= 7 ,-1 , 0
  4686.8     .17       0  4806.3     .11       0  4901.8    .015       0
  5033.8     .11       0  5058.9     .17       0  5157.3     .11       0
  5255.6     .17       0
Bank Sta=4901.8,5033.8
XS Rating Curve= 0 ,0
Exp/Cntr=0.3,0.1

Type RM Length L Ch R = 1 ,3000    ,500,500,500
BEGIN DESCRIPTION:
DUNKS DITCH 6.0
END DESCRIPTION:
XS GIS Cut Line= 3
      3946135.38      9997357.04       3945905.9      9997895.14
      3946135.42      9998242.45
#Sta/Elev= 30
    4415   56.46  4462.9   55.33  4475.8   55.77    4523   54.01  4570.3   53.21
  4599.3   51.42  4645.3   49.64    4652   49.91  4675.6   48.49  4699.2   48.24
  4728.3    48.7  4745.5   46.62  4775.5   45.03  4821.6   44.64  4826.1   41.23
  4830.3   41.23  4830.6   41.73  4833.6   41.98    5079   41.73  5085.1   42.98
  5091.1    45.5  5096.9   45.71  5142.3   47.63  5178.4   50.05  5219.3    51.3
  5307.8   54.94  5366.7   55.64  5389.1      57  5395.1   56.54  5416.3   56.81
#Mann= 6 ,-1 , 0
    4415     .17       0  4645.3     .11       0  4821.6    .015       0
  5091.1     .11       0  5096.9     .17       0  5219.3     .11       0
Bank Sta=4821.6,5091.1
XS Rating Curve= 0 ,0
Exp/Cntr=0.3,0.1

Type RM Length L Ch R = 1 ,2500    ,1000,1000,1000
BEGIN DESCRIPTION:
DUNKS DITCH 5.0
END DESCRIPTION:
XS GIS Cut Line= 3
      3946217.84      9996911.08      3945406.22      9997912.99
      3945986.12      9998471.61
#Sta/Elev= 30
  3710.6   59.45  3774.9    56.3  3934.8   54.48  3967.1   54.06  3994.4   52.12
  4037.5   51.66  4072.7    52.7  4092.5    50.9  4101.5   49.99    4159   51.34
  4194.2   49.94  4229.3   46.46  4286.9   44.95  4293.3   41.74  4301.2   42.29
  4305.5   41.23  5289.8   41.73    5304   45.14  5325.9   45.96  5381.7   48.72
  5388.9   50.32  5417.2   50.83  5445.5    53.8  5466.6    53.2  5494.9   54.22
  5544.2   52.88  5596.1   54.35  5756.5   55.55  5777.8   57.36  5805.2   57.98
#Mann= 7 ,-1 , 0
  3710.6     .11       0  3934.8     .17       0  4092.5     .11       0
  4286.9    .015       0    5304     .11       0  5325.9    .125       0
  5596.1     .11       0
Bank Sta=4286.9,5304
XS Rating Curve= 0 ,0
Exp/Cntr=0.3,0.1

Type RM Length L Ch R = 1 ,1500    ,0,0,0
BEGIN DESCRIPTION:
DUNKS DITCH 3.0
END DESCRIPTION:
XS GIS Cut Line= 3
      3946167.88      9996461.05      3944411.01       9997885.7
      3945267.86      9999161.09
#Sta/Elev= 30
  2738.1   59.55  2809.3   56.29  2887.6   54.53  2908.4   52.34  2953.7   50.75
  3001.1   50.34    3065    46.1  3084.6   46.08  3100.2    45.8  3108.1   43.31
  3114.6   43.91  3120.3   41.23    6226   41.73    6241    44.8  6306.9   47.78
    6313   47.14  6319.6    48.8    6364   50.58    6421   51.92  6444.6   50.85
    6457   50.32  6464.2   51.73    6472   55.74    6478    53.5    6487   57.85
    6493   54.28  6500.3   57.89    6508    59.6    6529   59.26  6536.5   60.75
#Mann= 6 ,-1 , 0
  2738.1     .11       0  2953.7     .15       0  3084.6     .11       0
  3100.2    .015       0    6241     .11       0  6444.6     .17       0
Bank Sta=3100.2,6241
XS Rating Curve= 0 ,0
Exp/Cntr=0.3,0.1

Chan Stop Cuts=-1
Use User Specified Reach Order=0
Composite Channel Slope=5