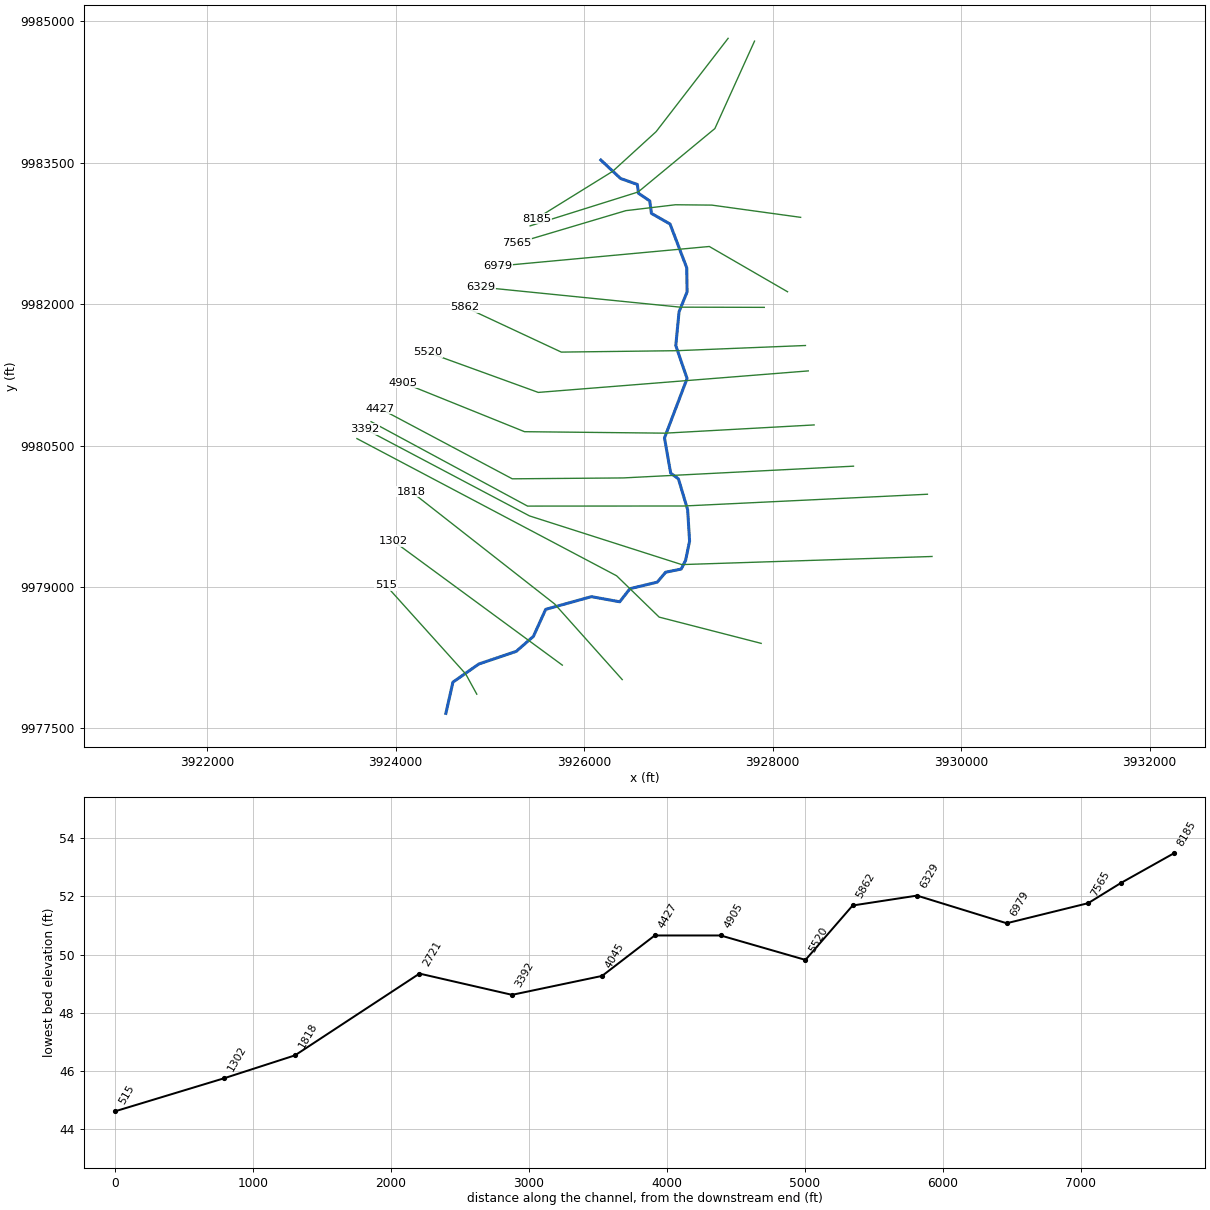
--- FLH 10.prj (project) ---

Proj Title=FLH 10 Base Level Engineering
Current Plan=p01
Default Exp/Contr=0.3,0.1
English Units
Geom File=g01
Flow File=f01
Flow File=f02
Plan File=p01
Y Axis Title=Elevation
X Axis Title(PF)=Main Channel Distance
X Axis Title(XS)=Station
BEGIN DESCRIPTION:
FLH 10
END DESCRIPTION:
DSS Export Rating Curves= 0
DSS Export Rating Curve Sorted= 0
DSS Export Volume Flow Curves= 0
DXF OffsetX= 0
DXF OffsetY= 0
DXF ScaleX= 1
DXF ScaleY= 10

--- FLH 10.p01 (plan) ---

Plan Title=Multiple Run
Short Identifier=Multiple
Geom File=g01
Flow File=f01
Subcritical Flow
K Sum by GR= 0
Std Step Tol= 0.01
Critical Tol= 0.01
Num of Std Step Trials= 20
Max Error Tol= 0.3
Flow Tol Ratio= 0.001
Split Flow NTrial= 30
Split Flow Tol= 0.02
Split Flow Ratio= 0.02
Log Output Level= 0
Friction Slope Method= 1
Unsteady Friction Slope Method= 2
Unsteady Bridges Friction Slope Method= 1
Parabolic Critical Depth
Global Vel Dist=  1 , 1 , 1
Global Log Level= 0
CheckData=True
Encroach Param= -1, 0, 0, 0
BEGIN DESCRIPTION:
Multiple Run
END DESCRIPTION:

--- FLH 10.f01 (steady flow) ---

Flow Title=Multiple
Program Version=4.10
Number of Profiles= 7
Profile Names=10-year,25-year,50-year,1pct_min,100-year,1pct_plu,500-year
River Rch & RM=FLH 10,Reach-1         ,8185
     238     293     370     155     467    1410     769
River Rch & RM=FLH 10,Reach-1         ,7565
     278     344     438     183     554    1673     922
River Rch & RM=FLH 10,Reach-1         ,6329
     325     402     511     214     645    1948    1066
Boundary for River Rch & Prof#=FLH 10,Reach-1         , 1
Up Type= 0
Dn Type= 3
Dn Slope=0.005
Boundary for River Rch & Prof#=FLH 10,Reach-1         , 2
Up Type= 0
Dn Type= 3
Dn Slope=0.005
Boundary for River Rch & Prof#=FLH 10,Reach-1         , 3
Up Type= 0
Dn Type= 3
Dn Slope=0.005
Boundary for River Rch & Prof#=FLH 10,Reach-1         , 4
Up Type= 0
Dn Type= 3
Dn Slope=0.005
Boundary for River Rch & Prof#=FLH 10,Reach-1         , 5
Up Type= 0
Dn Type= 3
Dn Slope=0.005
Boundary for River Rch & Prof#=FLH 10,Reach-1         , 6
Up Type= 0
Dn Type= 3
Dn Slope=0.005
Boundary for River Rch & Prof#=FLH 10,Reach-1         , 7
Up Type= 0
Dn Type= 3
Dn Slope=0.005
DSS Import GetInterval= 0
DSS Import GetPeak= 0
DSS Import FillOption= 0

--- FLH 10.f02 (steady flow) ---

Flow Title=Orig_BLE_Flows
Program Version=4.10
Number of Profiles= 7
Profile Names=10-year,25-year,50-year,1pct_min,100-year,1pct_plu,500-year
River Rch & RM=FLH 10,Reach-1         ,8185
     238     287     322     119     359    1085     447
River Rch & RM=FLH 10,Reach-1         ,7565
     278     337     381     141     426    1288     536
River Rch & RM=FLH 10,Reach-1         ,6329
     325     394     444     164     496    1497     620
Boundary for River Rch & Prof#=FLH 10,Reach-1         , 1
Up Type= 0
Dn Type= 3
Dn Slope=0.005
Boundary for River Rch & Prof#=FLH 10,Reach-1         , 2
Up Type= 0
Dn Type= 3
Dn Slope=0.005
Boundary for River Rch & Prof#=FLH 10,Reach-1         , 3
Up Type= 0
Dn Type= 3
Dn Slope=0.005
Boundary for River Rch & Prof#=FLH 10,Reach-1         , 4
Up Type= 0
Dn Type= 3
Dn Slope=0.005
Boundary for River Rch & Prof#=FLH 10,Reach-1         , 5
Up Type= 0
Dn Type= 3
Dn Slope=0.005
Boundary for River Rch & Prof#=FLH 10,Reach-1         , 6
Up Type= 0
Dn Type= 3
Dn Slope=0.005
Boundary for River Rch & Prof#=FLH 10,Reach-1         , 7
Up Type= 0
Dn Type= 3
Dn Slope=0.005
DSS Import GetInterval= 0
DSS Import GetPeak= 0
DSS Import FillOption= 0

--- FLH 10.g01 (geometry) ---

Geom Title=Existing Conditions
Program Version=4.10

River Reach=FLH 10          ,Reach-1
Reach XY= 30
        3926177.      9983528.89      3926387.07      9983332.71
      3926564.15      9983270.21       3926576.3      9983176.46
      3926696.09      9983094.86      3926713.46      9982962.92
      3926911.37      9982850.07      3927088.46      9982384.79
      3927091.93      9982129.58      3927006.86      9981919.52
      3926972.14      9981560.14      3927091.93      9981211.18
      3926852.34      9980580.97      3926917.67      9980207.32
      3927000.14      9980146.56       3927097.8      9979818.86
      3927118.41      9979485.75      3927076.09      9979281.75
      3927029.44      9979189.52      3926864.51      9979155.89
      3926775.53      9979050.64      3926485.82      9978981.19
      3926377.31       9978842.3      3926076.75      9978896.56
      3925591.72      9978762.01      3925461.51      9978475.55
      3925279.22      9978316.04      3924883.17      9978182.58
      3924607.56      9977989.44      3924532.62      9977658.34

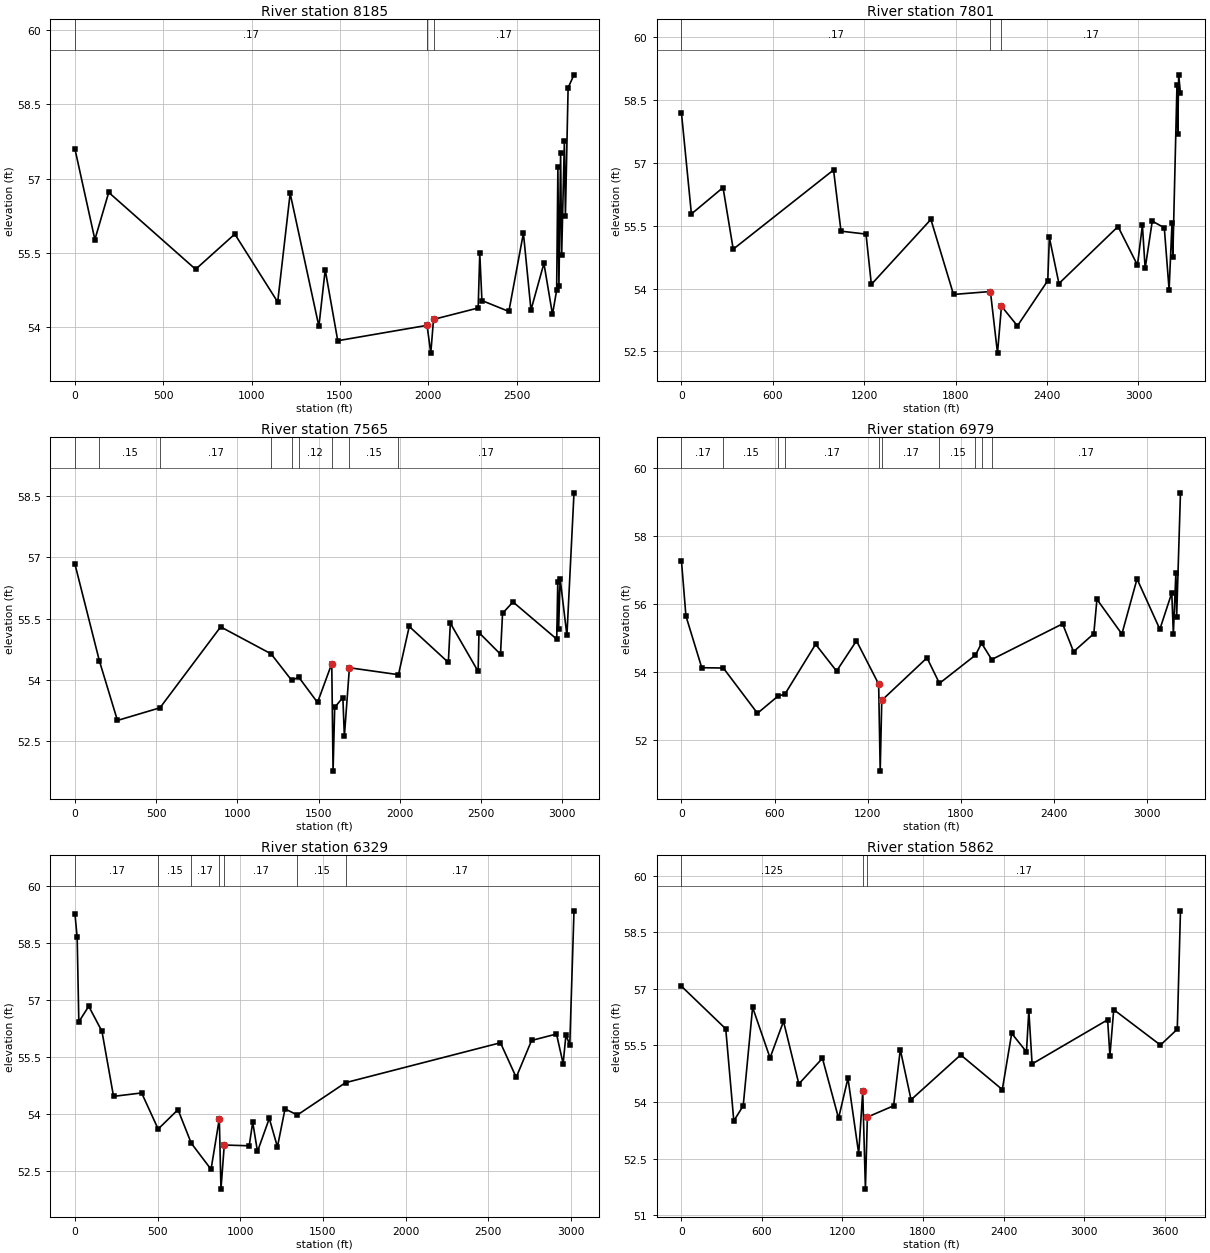
Type RM Length L Ch R = 1 ,8185    ,384,384,384
BEGIN DESCRIPTION:
FLH 10 9.0
END DESCRIPTION:
XS GIS Cut Line= 4
      3927527.29      9984820.23      3926763.49      9983830.21
      3926301.64       9983408.7      3925494.35       9982908.7
#Sta/Elev= 30
       0   57.59   112.6   55.77     191   56.72   682.9   55.17   904.8   55.88
  1147.6   54.51  1218.2    56.7  1380.9   54.02  1416.7   55.16  1487.7   53.73
  1993.3   54.04  2014.5   53.48  2029.9   54.16  2282.7   54.39  2291.8   55.49
    2304   54.54  2456.5   54.32  2538.9    55.9  2581.7   54.35    2655   55.29
  2703.5   54.26  2727.1   54.75  2734.1   57.23    2740   54.83  2749.5   57.51
  2755.4   55.45  2770.8   57.75  2776.6   56.25    2792   58.83  2825.3   59.09
#Mann= 4 ,-1 , 0
       0     .17       0  1993.3     .15       0  1993.3     .09       0
  2029.9     .17       0
Bank Sta=1993.3,2029.9
XS Rating Curve= 0 ,0
Exp/Cntr=0.3,0.1

Type RM Length L Ch R = 1 ,7801    ,236,236,236
BEGIN DESCRIPTION:
Mapping XS 1bbf85f0
END DESCRIPTION:
XS GIS Cut Line= 4
      3927807.43      9984790.55      3927386.74      9983862.99
      3926572.47      9983189.95      3925426.64      9982830.58
#Sta/Elev= 30
       0   58.19    65.3   55.78   272.9   56.41   339.8   54.94   998.4   56.83
  1047.3   55.37  1211.5    55.3  1246.6    54.1  1637.4   55.65  1785.9   53.86
  2028.2   53.93  2074.7   52.46  2100.7   53.58  2205.5   53.11  2404.7   54.19
  2415.1   55.22    2478   54.12  2865.8   55.48  2993.5   54.56  3025.9   55.51
    3044   54.48  3090.7   55.61  3169.7   55.45  3201.2   53.97  3220.4   55.57
  3225.7   54.76  3252.9   58.86  3258.1    57.7    3264    59.1  3275.8   58.66
#Mann= 3 , 0 , 0
       0     .17       0  2028.2     .09       0  2100.7     .17       0
Bank Sta=2028.2,2100.7
XS Rating Curve= 0 ,0
Exp/Cntr=0.3,0.1

Type RM Length L Ch R = 1 ,7565    ,591,591,591
BEGIN DESCRIPTION:
Mapping XS beb052df
END DESCRIPTION:
XS GIS Cut Line= 5
      3928296.55      9982921.04      3927354.21      9983050.92
      3926968.31      9983054.54      3926442.26      9982992.04
      3925286.06      9982647.87
#Sta/Elev= 30
       0   56.83   150.1   54.47   261.4   53.01   523.6   53.32   897.1    55.3
  1207.6   54.64  1334.9   53.99  1377.9   54.07  1493.7   53.45  1581.4    54.4
  1589.4   51.77  1599.5   53.33  1649.8   53.57    1659   52.62  1690.1    54.3
  1992.2   54.13  2058.6   55.31  2299.3   54.43  2311.7   55.39  2482.8   54.21
    2488   55.16  2620.7   54.63  2633.2   55.63  2697.5   55.91    2967      55
  2973.3   56.39  2978.6   55.25  2987.9   56.48  3029.7   55.09  3073.3   58.58
#Mann= 9 ,-1 , 0
       0     .17       0   150.1     .15       0   523.6     .17       0
  1207.6     .15       0  1334.9     .17       0  1377.9     .12       0
  1581.4     .09       0  1690.1     .15       0  1992.2     .17       0
Bank Sta=1581.4,1690.1
XS Rating Curve= 0 ,0
Exp/Cntr=0.3,0.1

Type RM Length L Ch R = 1 ,6979    ,650,650,650
BEGIN DESCRIPTION:
Mapping XS 41973639
END DESCRIPTION:
XS GIS Cut Line= 4
      3928157.66      9982131.61      3927327.68      9982611.83
      3925358.44      9982429.61      3925081.55      9982403.34
#Sta/Elev= 30
       0   57.26    28.8   55.64   130.7   54.12   269.9   54.11   489.5   52.78
   622.9   53.29     666   53.34     864   54.81   998.9   54.02  1127.2   54.91
    1270   53.64  1280.1   51.08  1290.1   53.16  1581.4   54.41  1661.7   53.66
  1893.7   54.49  1932.9   54.84  1998.2   54.36  2455.1   55.41  2525.4   54.59
  2655.9   55.12    2676   56.13  2836.7   55.11  2934.3   56.73  3081.3   55.25
  3158.1   56.32  3168.2   55.11  3184.5   56.91  3189.5   55.62    3214   59.26
#Mann= 10 ,-1 , 0
       0     .17       0   269.9     .15       0   622.9     .11       0
     666     .17       0    1270     .09       0  1290.1     .17       0
  1661.7     .15       0  1893.7     .17       0  1932.9     .15       0
  1998.2     .17       0
Bank Sta=1270,1290.1
XS Rating Curve= 0 ,0
Exp/Cntr=0.3,0.1

Type RM Length L Ch R = 1 ,6329    ,467,467,467
BEGIN DESCRIPTION:
FLH 10 8.0
END DESCRIPTION:
XS GIS Cut Line= 3
      3927911.01        9981966.      3927019.01      9981968.13
      3924902.09      9982180.83
#Sta/Elev= 30
       0   59.26    13.2   58.65    23.2   56.43    83.2   56.84   163.2   56.18
   233.2   54.47   403.2   54.56   503.2   53.61   623.2   54.12   703.2   53.24
   823.2   52.55   873.2   53.88   883.2   52.03   903.2   53.19    1054   53.17
  1075.3   53.79  1104.2   53.02  1175.6   53.89  1224.8   53.14  1270.8   54.14
  1345.4   53.98  1636.9   54.83  2574.2   55.88  2669.5   54.97  2762.5   55.94
  2913.3   56.11  2953.5   55.33  2970.3   56.08  2993.7   55.83  3019.2   59.35
#Mann= 7 ,-1 , 0
       0     .17       0   503.2     .15       0   703.2     .17       0
   873.2     .09       0   903.2     .17       0  1345.4     .15       0
  1636.9     .17       0
Bank Sta=873.2,903.2
XS Rating Curve= 0 ,0
Exp/Cntr=0.3,0.1

Type RM Length L Ch R = 1 ,5862    ,342,342,342
BEGIN DESCRIPTION:
FLH 10 7.0
END DESCRIPTION:
XS GIS Cut Line= 4
      3928347.63      9981561.27      3926984.29      9981506.32
       3925757.4      9981491.37      3924736.06      9981968.39
#Sta/Elev= 30
       0   57.07     330   55.94   390.1    53.5   460.2    53.9   530.2   56.51
   660.3   55.17   760.4   56.14   874.7   54.48  1050.6   55.16  1170.7   53.57
  1240.8   54.63  1320.9   52.63  1350.9   54.28  1370.9   51.69  1385.4    53.6
  1580.9    53.9  1630.9   55.39  1710.9   54.06  2080.9   55.25    2391   54.33
    2461   55.82    2571   55.33  2588.7   56.42    2613   55.01  3175.9   56.18
  3192.9   55.23  3221.3   56.45  3569.6   55.51  3694.9   55.93  3718.7   59.07
#Mann= 3 , 0 , 0
       0    .125       0  1350.9     .09       0  1385.4     .17       0
Bank Sta=1350.9,1385.4
XS Rating Curve= 0 ,0
Exp/Cntr=0.3,0.1

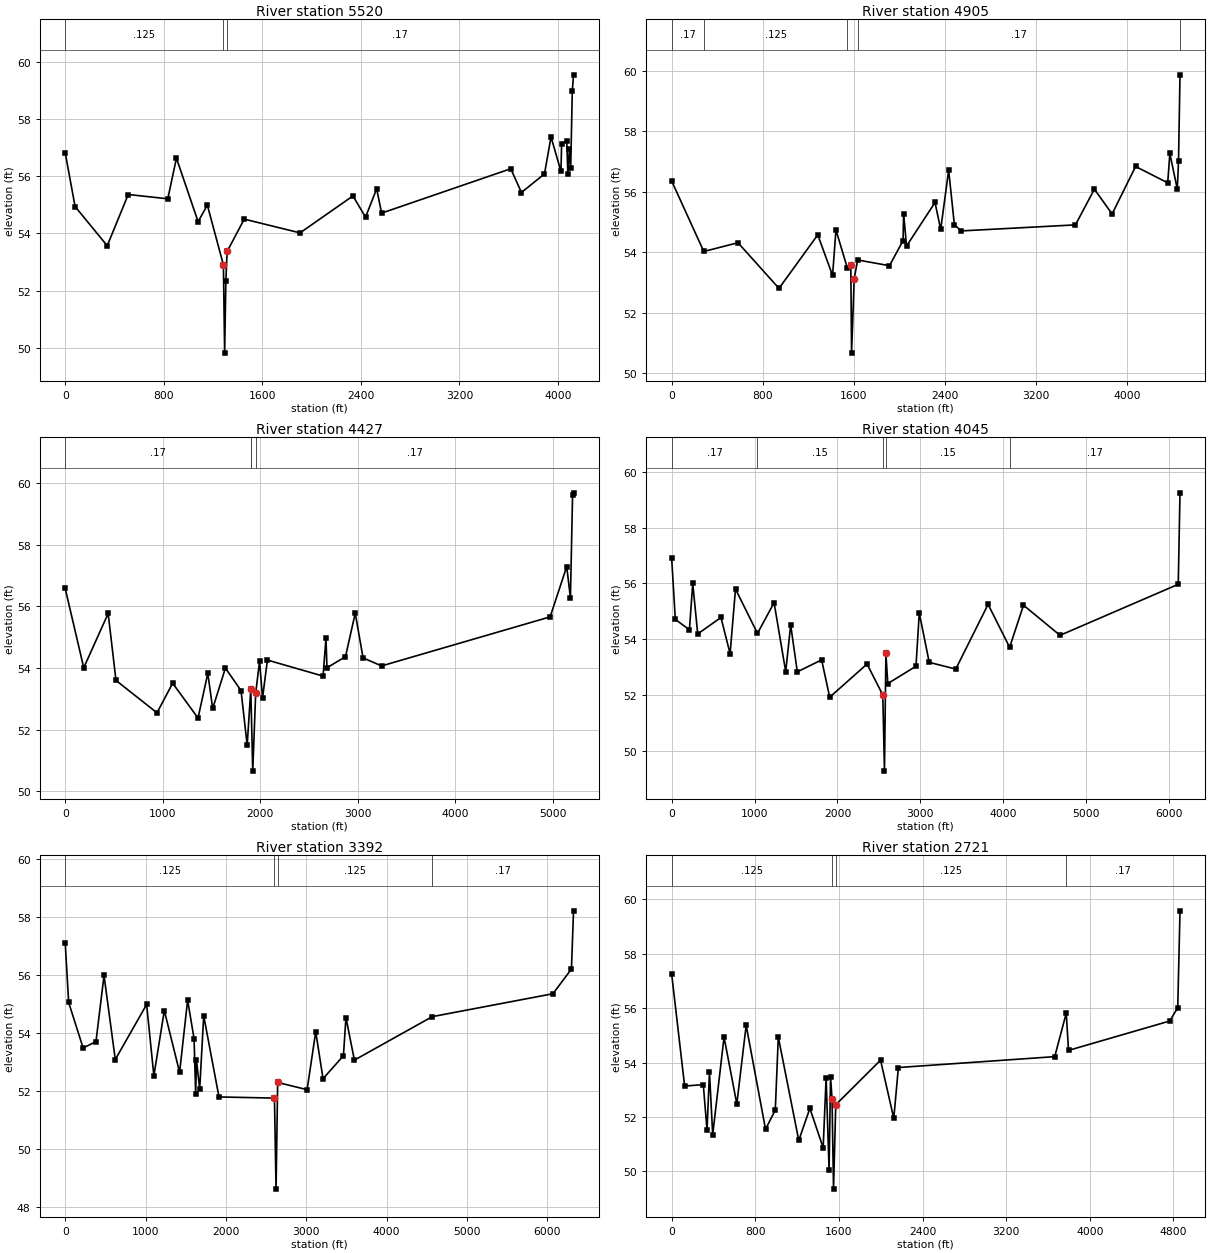
Type RM Length L Ch R = 1 ,5520    ,615,615,615
BEGIN DESCRIPTION:
FLH 10 6.0
END DESCRIPTION:
XS GIS Cut Line= 3
      3928377.77      9981291.77      3925513.26      9981063.57
      3924336.18      9981490.65
#Sta/Elev= 30
       0   56.82    80.2   54.94     341   53.57   511.5   55.36   832.5   55.21
   902.8   56.63  1078.7   54.41  1153.6   54.99    1284    52.9    1294   49.82
    1304   52.35  1314.1   53.37  1453.2    54.5  1905.9   54.02  2335.3   55.31
  2437.6   54.57  2527.9   55.56    2568   54.71  3616.3   56.26  3702.8   55.43
  3889.9   56.08  3943.1   57.37  4023.6   56.17    4029   57.14  4070.8   57.22
  4079.6   56.08  4092.1   56.94  4102.7   56.27  4115.5   58.96  4125.7   59.54
#Mann= 3 , 0 , 0
       0    .125       0    1284     .09       0  1314.1     .17       0
Bank Sta=1284,1314.1
XS Rating Curve= 0 ,0
Exp/Cntr=0.3,0.1

Type RM Length L Ch R = 1 ,4905    ,478,478,478
BEGIN DESCRIPTION:
FLH 10 5.0
END DESCRIPTION:
XS GIS Cut Line= 4
      3928439.66       9980718.6      3926859.29      9980631.32
      3925367.43       9980646.9      3924075.76      9981167.73
#Sta/Elev= 30
       0   56.35   282.2   54.02   582.7   54.31   943.2    52.8  1283.8   54.57
    1414   53.23    1444   54.73  1544.2   53.47  1574.2   53.56    1581   50.66
  1604.2   53.12  1634.2   53.74  1914.2   53.55  2033.5   54.38  2038.5   55.26
  2064.2    54.2  2314.3   55.64  2364.3   54.75  2434.3   56.71  2484.3   54.91
  2544.3    54.7  3548.6    54.9    3715   56.08  3870.7   55.26    4077   56.83
  4359.4   56.29  4378.2   57.26  4443.6   56.08  4454.4      57  4467.4   59.86
#Mann= 5 ,-1 , 0
       0     .17       0   282.2    .125       0  1544.2     .09       0
  1634.2     .17       0  4467.4     .17       0
Bank Sta=1574.2,1604.2
XS Rating Curve= 0 ,0
Exp/Cntr=0.3,0.1

Type RM Length L Ch R = 1 ,4427    ,382,382,382
BEGIN DESCRIPTION:
Mapping XS f8e9ae42
END DESCRIPTION:
XS GIS Cut Line= 4
      3928857.57      9980281.07      3926414.32      9980156.34
      3925237.22       9980146.9      3923836.18      9980891.69
#Sta/Elev= 30
       0   56.58     190   54.01   440.3   55.77   520.4    53.6   940.9   52.55
  1101.2   53.51  1361.5   52.38  1461.6   53.83  1511.7   52.69  1641.9      54
  1802.1   53.27  1865.2    51.5  1902.2   53.31  1922.2   50.66  1952.3   53.18
  1992.3   54.23  2022.4   53.02  2072.4   54.26  2642.9   53.74  2672.9   54.97
  2682.9   54.01  2872.9   54.37  2972.9   55.78  3052.9   54.33  3242.9   54.07
  4970.6   55.66  5140.4   57.29  5178.5   56.28  5200.5   59.61  5210.3   59.68
#Mann= 4 ,-1 , 0
       0     .17       0  1902.2     .15       0  1902.2     .09       0
  1952.3     .17       0
Bank Sta=1902.2,1952.3
XS Rating Curve= 0 ,0
Exp/Cntr=0.3,0.1

Type RM Length L Ch R = 1 ,4045    ,653,653,653
BEGIN DESCRIPTION:
Mapping XS e925eaa5
END DESCRIPTION:
XS GIS Cut Line= 4
      3929641.69      9979983.22      3927058.41      9979858.46
      3925399.01       9979857.6      3923739.29      9980753.43
#Sta/Elev= 30
       0    56.9    43.9   54.71   214.1   54.34   254.1      56   314.2   54.19
   594.5   54.78   704.7   53.48   769.9    55.8    1035   54.21  1235.3   55.31
  1375.4   52.84  1435.5   54.51  1515.6   52.83  1808.8   53.26  1906.1   51.92
  2356.6   53.11  2546.8      52  2566.8   49.27  2584.1   53.49  2606.8   52.41
  2946.8   53.03  2986.8   54.94  3106.8   53.17  3426.8   52.93  3816.8   55.25
  4076.8   53.71  4243.8   55.22  4684.6   54.14  6110.6   55.97  6131.7   59.25
#Mann= 5 ,-1 , 0
       0     .17       0    1035     .15       0  2546.8     .09       0
  2584.1     .15       0  4076.8     .17       0
Bank Sta=2546.8,2584.1
XS Rating Curve= 0 ,0
Exp/Cntr=0.3,0.1

Type RM Length L Ch R = 1 ,3392    ,671,671,671
BEGIN DESCRIPTION:
FLH 10 4.0
END DESCRIPTION:
XS GIS Cut Line= 4
      3929690.68      9979322.87      3927035.15      9979236.83
      3925419.85      9979753.43      3923674.97      9980675.58
#Sta/Elev= 30
       0   57.12    42.9   55.06   222.9   53.49     383   53.71   483.1   55.99
   623.2   53.09  1013.4   54.99  1103.4   52.53  1233.5   54.78  1423.6   52.65
  1523.6   55.14  1603.7   53.81  1623.7   51.91  1633.7   53.07  1673.7   52.07
  1723.7    54.6  1913.8    51.8  2604.2   51.76  2624.2   48.62  2644.2    52.3
  3010.7   52.05  3117.7   54.05  3208.9   52.43  3462.5   53.22    3494   54.54
    3599   53.07  4568.4   54.57  6069.6   55.36  6300.4   56.21  6326.4   58.22
#Mann= 4 ,-1 , 0
       0    .125       0  2604.2     .04       0  2644.2    .125       0
  4568.4     .17       0
Bank Sta=2604.2,2644.2
XS Rating Curve= 0 ,0
Exp/Cntr=0.3,0.1

Type RM Length L Ch R = 1 ,2721    ,903,903,903
BEGIN DESCRIPTION:
Mapping XS af7d7046
END DESCRIPTION:
XS GIS Cut Line= 4
      3927877.92      9978401.16      3926795.71      9978679.64
      3926344.33      9979118.01      3923589.12      9980573.74
#Sta/Elev= 30
       0   57.25     124   53.14   302.6   53.19   338.2   51.51   361.5   53.65
   392.5   51.35     501   54.94   623.2   52.48   712.6   55.37   897.9   51.55
   991.3   52.26    1020   54.94  1215.9   51.14  1322.1   52.32  1449.2   50.87
  1477.5   53.44  1505.8   50.06    1520   53.48  1534.1   52.66  1548.3   49.35
  1569.6   52.45  1998.3   54.09  2124.7   51.95  2168.7   53.82  3664.4   54.22
  3774.5   55.82  3796.5   54.45  4764.5   55.53  4841.2   56.02  4862.8   59.58
#Mann= 4 ,-1 , 0
       0    .125       0  1534.1     .04       0  1569.6    .125       0
  3774.5     .17       0
Bank Sta=1534.1,1569.6
XS Rating Curve= 0 ,0
Exp/Cntr=0.3,0.1

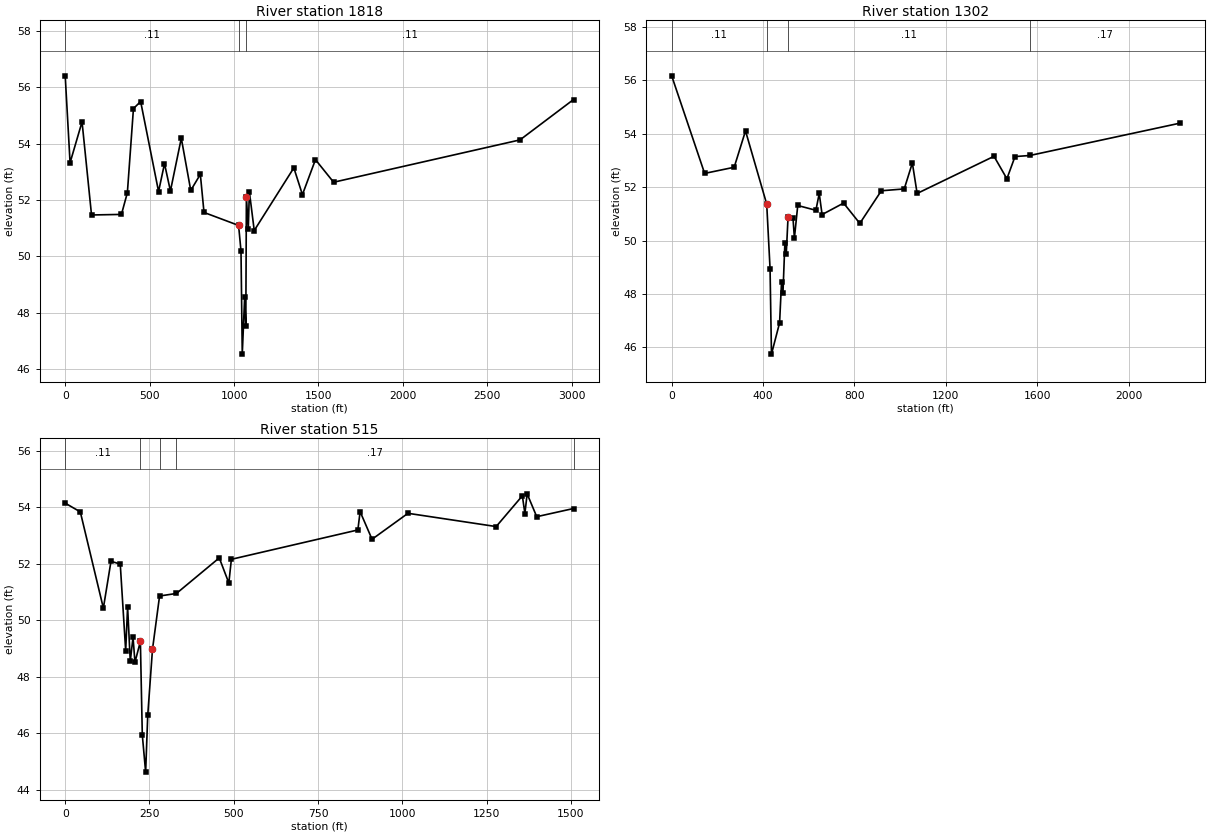
Type RM Length L Ch R = 1 ,1818    ,516,516,516
BEGIN DESCRIPTION:
FLH 10 2.0
END DESCRIPTION:
XS GIS Cut Line= 3
      3926403.93       9978016.7      3925688.03      9978817.99
      3924163.87      9980012.15
#Sta/Elev= 30
       0    56.4    28.8   53.32    99.7   54.77   155.9   51.47   333.1   51.49
   368.2   52.26   404.2   55.24   446.8   55.49     553    52.3   588.1   53.29
   623.2   52.32   687.6   54.19   743.6   52.34   800.4   52.91   822.1   51.56
    1027    51.1  1041.2   50.19  1048.7   46.54  1062.9   48.56  1069.6   47.52
  1073.2   52.12  1084.4   50.96  1090.7    52.3  1119.6   50.92  1354.2   53.14
    1405   52.19  1482.2   53.43  1589.8   52.63  2693.7   54.13  3010.8   55.56
#Mann= 3 , 0 , 0
       0     .11       0    1027     .04       0  1073.2     .11       0
Bank Sta=1027,1073.2
XS Rating Curve= 0 ,0
Exp/Cntr=0.3,0.1

Type RM Length L Ch R = 1 ,1302    ,787,787,787
BEGIN DESCRIPTION:
Mapping XS ea19a22f
END DESCRIPTION:
XS GIS Cut Line= 2
      3925768.29       9978170.1      3923974.48      9979487.55
#Sta/Elev= 30
       0   56.16   144.2   52.51   273.5   52.74   323.1    54.1   415.9   51.36
   430.5   48.95   436.7   45.75   472.2   46.92   480.7   48.44   486.9   48.03
   495.3   49.89   501.5   49.51   509.2   50.87   530.8   50.85     537   50.09
   551.7   51.31   631.1   51.13   645.7   51.76   658.2   50.97   752.3    51.4
   823.3   50.64   917.4   51.86  1017.7   51.93  1053.2    52.9  1074.1   51.76
  1410.5   53.15  1466.9   52.31  1502.4   53.14  1567.2   53.18  2224.4   54.39
#Mann= 4 ,-1 , 0
       0     .11       0   415.9     .07       0   509.2     .11       0
  1567.2     .17       0
Bank Sta=415.9,509.2
XS Rating Curve= 0 ,0
Exp/Cntr=0.3,0.1

Type RM Length L Ch R = 1 ,515     ,0,0,0
BEGIN DESCRIPTION:
FLH 10 1.0
END DESCRIPTION:
XS GIS Cut Line= 3
      3924860.78      9977861.83      3924742.72      9978077.11
      3923898.09      9979015.33
#Sta/Elev= 30
       0   54.15    44.8   53.84   113.2   50.43   135.8   52.09   163.3   51.99
   179.4   48.92   185.1   50.48     193   48.55   201.2    49.4   206.9   48.51
     223   49.25   228.7   45.94   238.6   44.62   244.8   46.63   258.9   48.97
   279.9   50.86   329.9   50.95     457   52.21   485.4   51.32   492.9   52.16
   868.1    53.2   874.8   53.85   910.2   52.87  1016.8   53.79  1278.4   53.32
  1356.1   54.41  1363.6   53.78  1370.3   54.48  1398.7   53.67  1507.9   53.96
#Mann= 5 ,-1 , 0
       0     .11       0     223     .06       0   279.9     .11       0
   329.9     .17       0  1507.9     .11       0
Bank Sta=223,258.9
XS Rating Curve= 0 ,0
Exp/Cntr=0.3,0.1

Chan Stop Cuts=-1
Use User Specified Reach Order=0
Composite Channel Slope=5