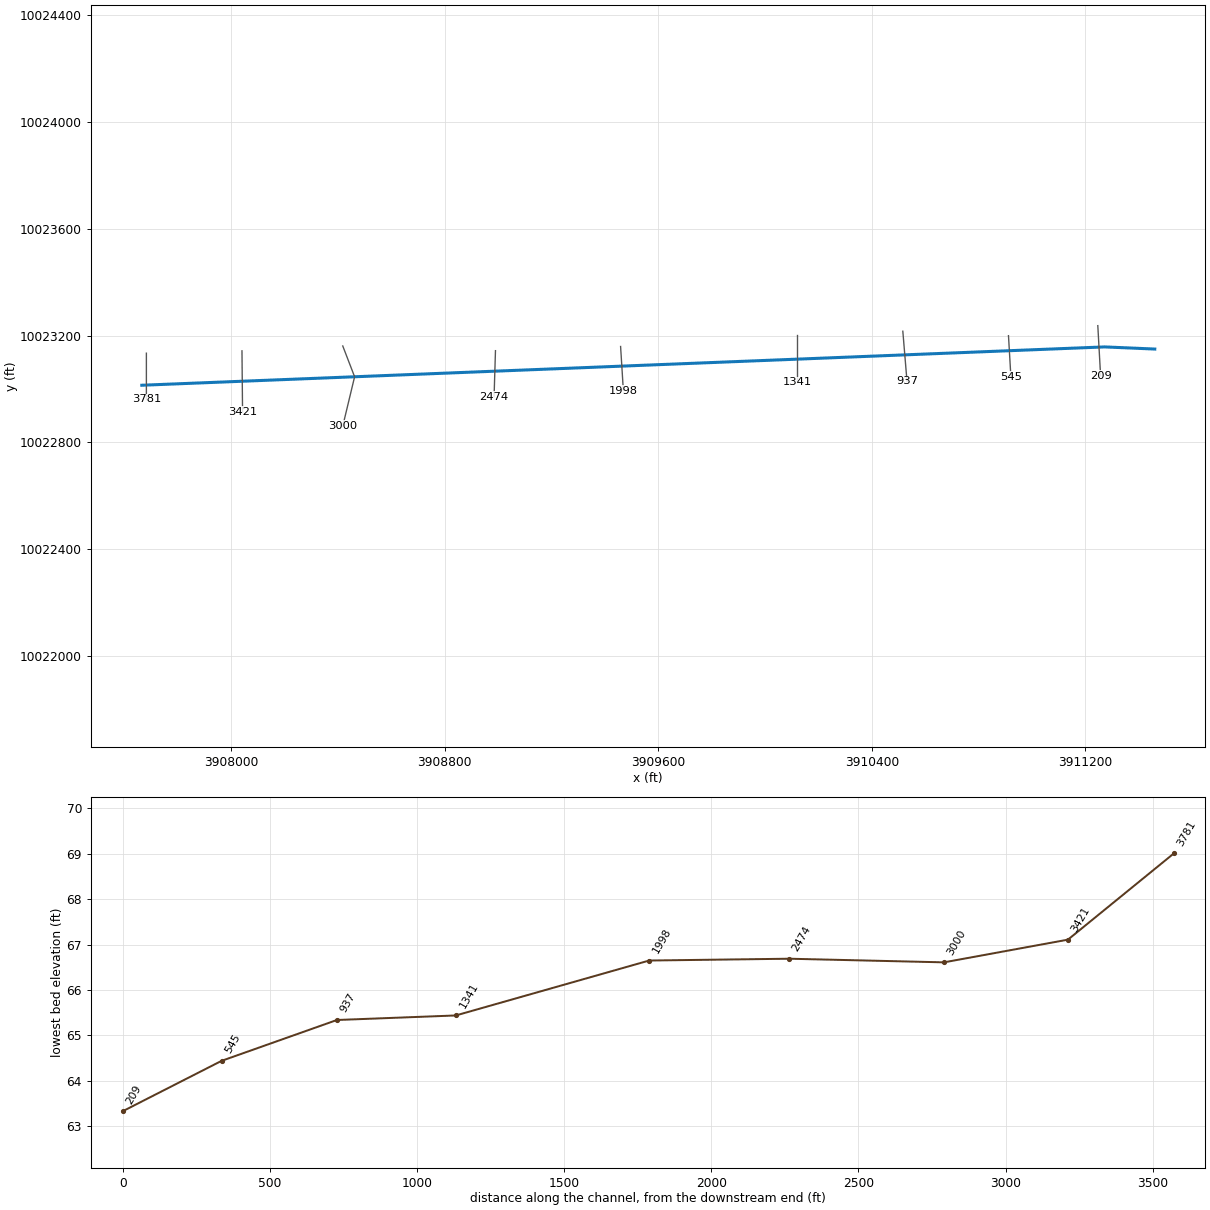
--- FLH 12.prj (project) ---

Proj Title=FLH 12 Base Level Engineering
Current Plan=p01
Default Exp/Contr=0.3,0.1
English Units
Geom File=g01
Flow File=f01
Flow File=f02
Plan File=p01
Y Axis Title=Elevation
X Axis Title(PF)=Main Channel Distance
X Axis Title(XS)=Station
BEGIN DESCRIPTION:
FLH 12
END DESCRIPTION:
DSS Export Rating Curves= 0
DSS Export Rating Curve Sorted= 0
DSS Export Volume Flow Curves= 0
DXF OffsetX= 0
DXF OffsetY= 0
DXF ScaleX= 1
DXF ScaleY= 10

--- FLH 12.p01 (plan) ---

Plan Title=Multiple Run
Short Identifier=Multiple
Geom File=g01
Flow File=f01
Subcritical Flow
K Sum by GR= 0
Std Step Tol= 0.01
Critical Tol= 0.01
Num of Std Step Trials= 20
Max Error Tol= 0.3
Flow Tol Ratio= 0.001
Split Flow NTrial= 30
Split Flow Tol= 0.02
Split Flow Ratio= 0.02
Log Output Level= 0
Friction Slope Method= 1
Unsteady Friction Slope Method= 2
Unsteady Bridges Friction Slope Method= 1
Parabolic Critical Depth
Global Vel Dist=  1 , 1 , 1
Global Log Level= 0
CheckData=True
Encroach Param= -1, 0, 0, 0
BEGIN DESCRIPTION:
Multiple Run
END DESCRIPTION:

--- FLH 12.f01 (steady flow) ---

Flow Title=Multiple
Program Version=4.10
Number of Profiles= 7
Profile Names=10-year,25-year,50-year,1pct_min,100-year,1pct_plu,500-year
River Rch & RM=FLH 12,Reach-1         ,3781
      67      72      84      32      96     290     132
Boundary for River Rch & Prof#=FLH 12,Reach-1         , 1
Up Type= 0
Dn Type= 3
Dn Slope=0.005
Boundary for River Rch & Prof#=FLH 12,Reach-1         , 2
Up Type= 0
Dn Type= 3
Dn Slope=0.005
Boundary for River Rch & Prof#=FLH 12,Reach-1         , 3
Up Type= 0
Dn Type= 3
Dn Slope=0.005
Boundary for River Rch & Prof#=FLH 12,Reach-1         , 4
Up Type= 0
Dn Type= 3
Dn Slope=0.005
Boundary for River Rch & Prof#=FLH 12,Reach-1         , 5
Up Type= 0
Dn Type= 3
Dn Slope=0.005
Boundary for River Rch & Prof#=FLH 12,Reach-1         , 6
Up Type= 0
Dn Type= 3
Dn Slope=0.005
Boundary for River Rch & Prof#=FLH 12,Reach-1         , 7
Up Type= 0
Dn Type= 3
Dn Slope=0.005
DSS Import GetInterval= 0
DSS Import GetPeak= 0
DSS Import FillOption= 0

--- FLH 12.f02 (steady flow) ---

Flow Title=Orig_BLE_Flows
Program Version=4.10
Number of Profiles= 7
Profile Names=10-year,25-year,50-year,1pct_min,100-year,1pct_plu,500-year
River Rch & RM=FLH 12,Reach-1         ,3781
      67      71      73      25      74     225      77
Boundary for River Rch & Prof#=FLH 12,Reach-1         , 1
Up Type= 0
Dn Type= 3
Dn Slope=0.005
Boundary for River Rch & Prof#=FLH 12,Reach-1         , 2
Up Type= 0
Dn Type= 3
Dn Slope=0.005
Boundary for River Rch & Prof#=FLH 12,Reach-1         , 3
Up Type= 0
Dn Type= 3
Dn Slope=0.005
Boundary for River Rch & Prof#=FLH 12,Reach-1         , 4
Up Type= 0
Dn Type= 3
Dn Slope=0.005
Boundary for River Rch & Prof#=FLH 12,Reach-1         , 5
Up Type= 0
Dn Type= 3
Dn Slope=0.005
Boundary for River Rch & Prof#=FLH 12,Reach-1         , 6
Up Type= 0
Dn Type= 3
Dn Slope=0.005
Boundary for River Rch & Prof#=FLH 12,Reach-1         , 7
Up Type= 0
Dn Type= 3
Dn Slope=0.005
DSS Import GetInterval= 0
DSS Import GetPeak= 0
DSS Import FillOption= 0

--- FLH 12.g01 (geometry) ---

Geom Title=Existing Conditions
Program Version=4.10

River Reach=FLH 12          ,Reach-1
Reach XY= 3
      3907665.03     10023014.02      3911272.27     10023157.62
       3911459.8     10023149.58

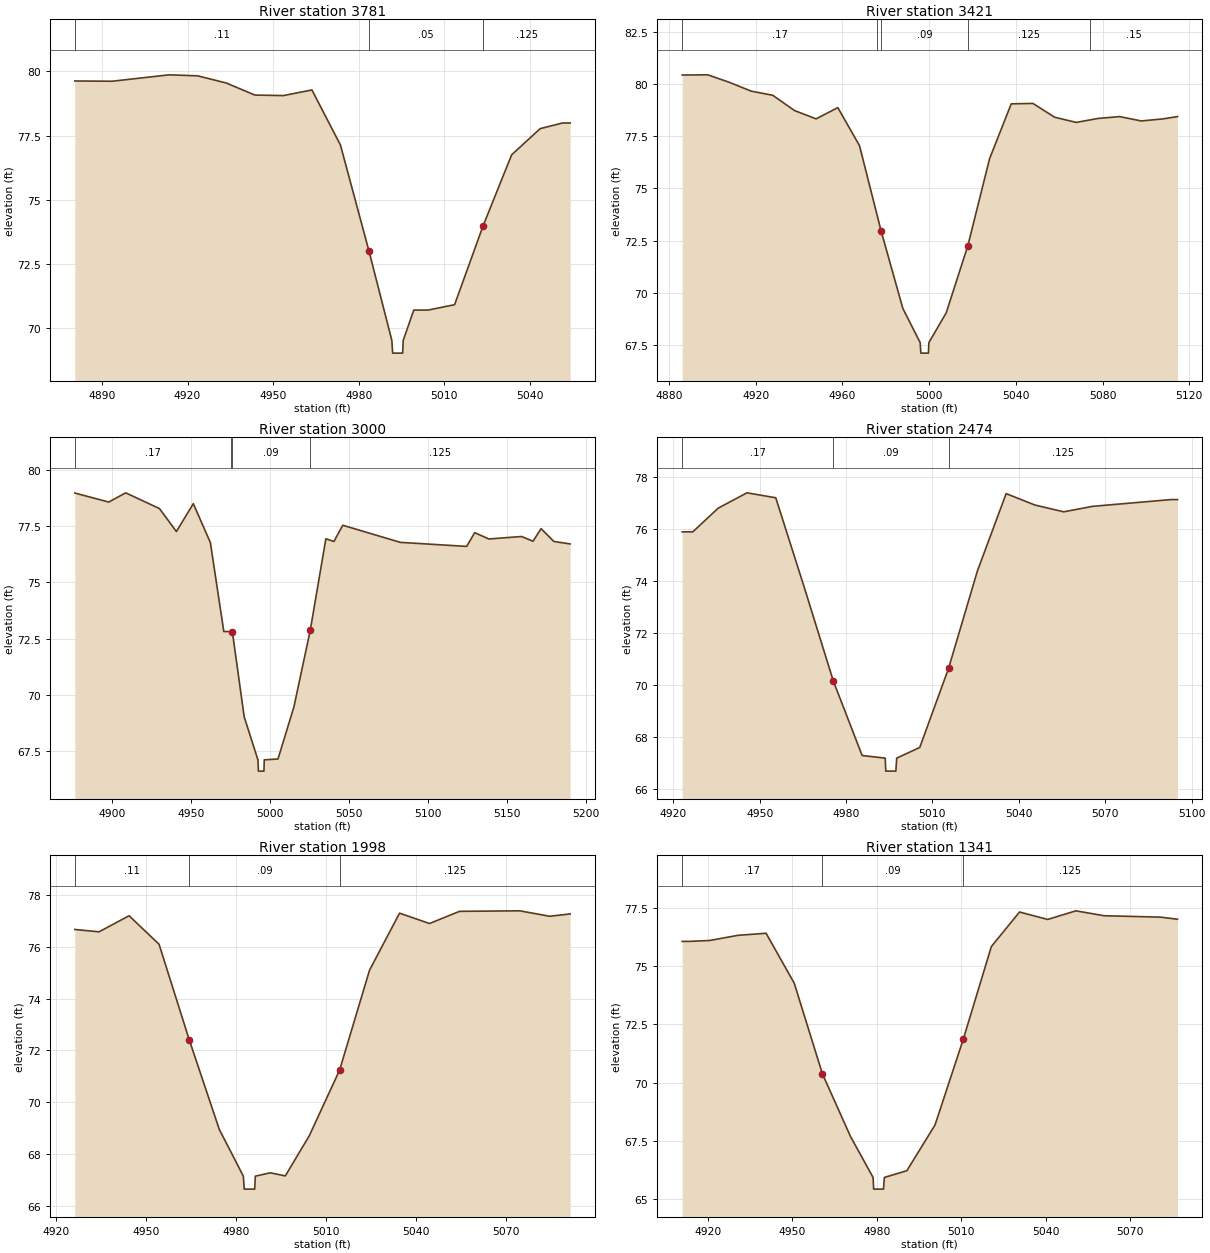
Type RM Length L Ch R = 1 ,3781    ,360,360,360
BEGIN DESCRIPTION:
FLH 12 7.0
END DESCRIPTION:
XS GIS Cut Line= 3
      3907682.19      10023134.2      3907682.15      10023014.7
      3907682.19      10022960.6
#Sta/Elev= 23
  4880.5   79.63  4893.6   79.62  4913.6   79.87  4923.6   79.83  4933.6   79.55
  4943.6   79.08  4953.6   79.06  4963.6   79.28  4973.6   77.13  4983.6   72.99
  4991.6   69.51  4991.9   69.01  4995.4   69.01  4995.6   69.51  4999.3   70.69
  5000.1   70.69  5004.3   70.69  5013.6    70.9  5023.6   73.98  5033.6   76.75
  5043.6   77.77  5051.4   77.99  5054.1   77.99
#Mann= 3 , 0 , 0
  4880.5     .11       0  4983.6     .05       0  5023.6    .125       0
Bank Sta=4983.6,5023.6
XS Rating Curve= 0 ,0
Exp/Cntr=0.3,0.1

Type RM Length L Ch R = 1 ,3421    ,421,421,421
BEGIN DESCRIPTION:
Mapping XS a23dca12
END DESCRIPTION:
XS GIS Cut Line= 2
      3908040.26     10023142.89      3908042.41      10022914.4
#Sta/Elev= 29
  4886.1   80.43  4897.9   80.44  4907.9   80.08  4917.9   79.66  4927.9   79.46
  4937.9   78.73  4947.9   78.33  4957.9   78.87  4967.9   77.05  4975.9   73.77
  4977.9   72.95  4987.9   69.25  4995.9   67.61  4996.2   67.11  4999.7   67.11
  4999.9   67.61  5007.9   69.04  5017.9   72.26  5027.9   76.42  5037.9   79.05
  5047.9   79.07  5057.9   78.41  5067.9   78.16  5074.2   78.28  5077.9   78.35
  5087.9   78.44  5097.9   78.23  5107.9   78.33  5114.6   78.44
#Mann= 5 ,-1 , 0
  4886.1     .17       0  4975.9    .125       0  4977.9     .09       0
  5017.9    .125       0  5074.2     .15       0
Bank Sta=4977.9,5017.9
XS Rating Curve= 0 ,0
Exp/Cntr=0.3,0.1

Type RM Length L Ch R = 1 ,3000    ,526,526,526
BEGIN DESCRIPTION:
FLH 12 6.0
END DESCRIPTION:
XS GIS Cut Line= 3
      3908417.83     10023161.12       3908462.2     10023045.75
      3908417.86      10022861.1
#Sta/Elev= 30
  4876.4   78.96  4897.9   78.56  4908.6   78.97    4930   78.27  4940.7   77.25
  4951.4   78.49  4962.2   76.76  4970.7   72.81  4975.4   72.81  4976.1   72.81
  4983.6   69.02  4992.3   67.11  4992.6   66.61  4996.1   66.61  4996.3   67.11
    5005   67.15  5015.1   69.47  5025.4   72.86  5035.3   76.93  5040.4   76.81
    5046   77.53  5082.4   76.77  5124.4   76.59  5129.5    77.2  5138.5   76.92
  5159.1   77.03  5166.4   76.82  5171.5   77.38  5179.6   76.81  5189.9    76.7
#Mann= 4 ,-1 , 0
  4876.4     .17       0  4975.4    .125       0  4976.1     .09       0
  5025.4    .125       0
Bank Sta=4976.1,5025.4
XS Rating Curve= 0 ,0
Exp/Cntr=0.3,0.1

Type RM Length L Ch R = 1 ,2474    ,476,476,476
BEGIN DESCRIPTION:
Mapping XS 0505f936
END DESCRIPTION:
XS GIS Cut Line= 2
      3908989.91     10023143.53       3908984.7     10022971.61
#Sta/Elev= 22
  4923.1   75.89  4926.8   75.89  4935.6    76.8  4945.6   77.39  4955.6    77.2
  4965.6   73.72  4975.6   70.15  4977.7   69.55  4985.6   67.29  4993.6   67.19
  4993.8   66.69  4997.3   66.69  4997.6   67.19  5005.6    67.6  5015.6   70.64
  5025.6   74.38  5035.6   77.36  5045.6   76.92  5055.6   76.66  5065.6   76.87
  5092.8   77.13  5095.1   77.13
#Mann= 3 , 0 , 0
  4923.1     .17       0  4975.6     .09       0  5015.6    .125       0
Bank Sta=4975.6,5015.6
XS Rating Curve= 0 ,0
Exp/Cntr=0.3,0.1

Type RM Length L Ch R = 1 ,1998    ,657,657,657
BEGIN DESCRIPTION:
Mapping XS 6ce52c84
END DESCRIPTION:
XS GIS Cut Line= 2
      3909458.66     10023159.16      3909468.97     10022994.28
#Sta/Elev= 22
  4926.3   76.67  4934.4   76.58  4944.4    77.2  4954.4    76.1  4964.5    72.4
  4974.5   68.95  4978.7   68.01  4982.5   67.15  4982.8   66.65  4986.3   66.65
  4986.5   67.15  4991.5   67.28  4996.5   67.16  5004.5   68.71  5014.6   71.24
  5024.6    75.1  5034.6    77.3  5044.6    76.9  5054.6   77.37  5074.7   77.39
  5084.7   77.18  5091.5   77.27
#Mann= 3 , 0 , 0
  4926.3     .11       0  4964.5     .09       0  5014.6    .125       0
Bank Sta=4964.5,5014.6
XS Rating Curve= 0 ,0
Exp/Cntr=0.3,0.1

Type RM Length L Ch R = 1 ,1341    ,404,404,404
BEGIN DESCRIPTION:
Mapping XS ac9cc901
END DESCRIPTION:
XS GIS Cut Line= 2
      3910120.12     10023200.86      3910120.12     10023024.96
#Sta/Elev= 22
  4910.9   76.05  4913.3   76.05  4920.7   76.09  4930.7   76.31  4940.7    76.4
  4950.7   74.26  4960.7   70.38  4970.7   67.69  4978.7   65.94  4978.9   65.44
  4982.4   65.44  4982.7   65.94  4990.7   66.23  5000.7   68.19  5010.7   71.85
  5020.7   75.83  5030.7   77.31  5040.7   76.99  5050.7   77.36  5060.7   77.15
  5080.7   77.09  5086.8      77
#Mann= 3 , 0 , 0
  4910.9     .17       0  4960.7     .09       0  5010.7    .125       0
Bank Sta=4960.7,5010.7
XS Rating Curve= 0 ,0
Exp/Cntr=0.3,0.1

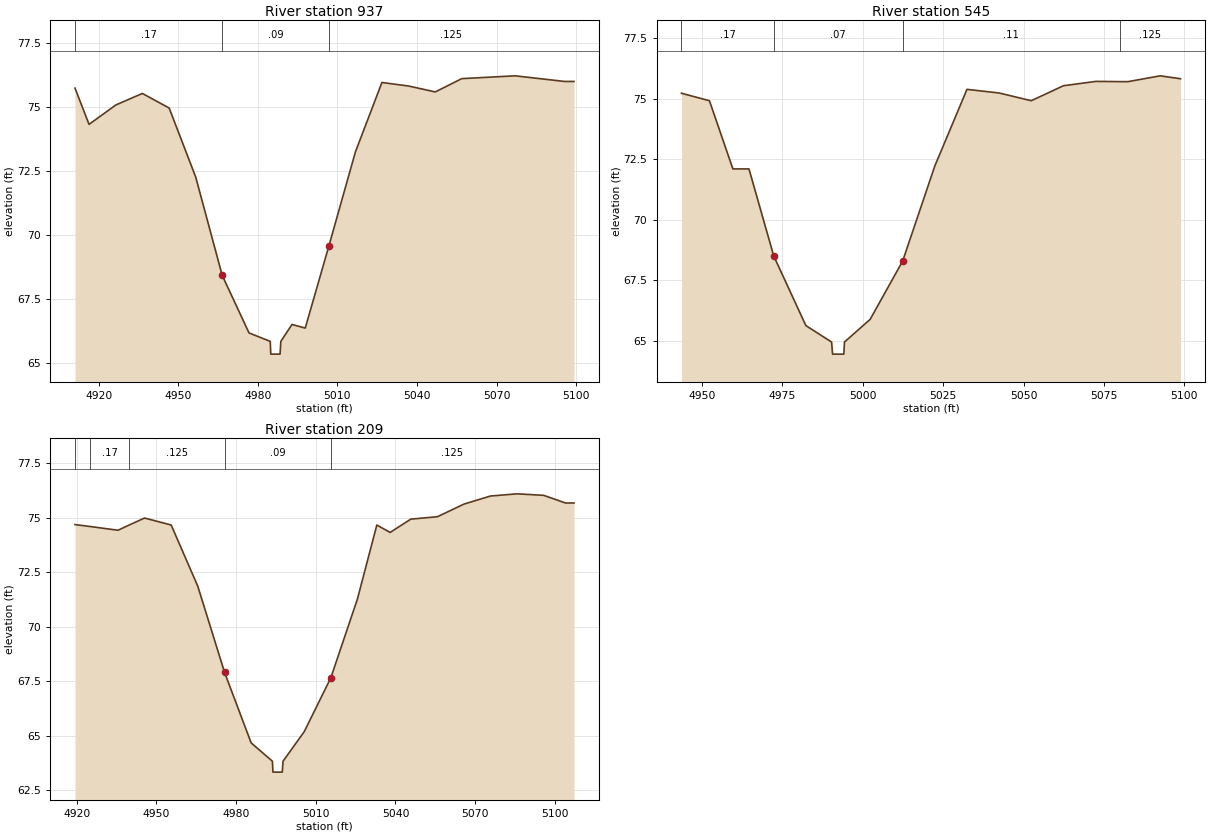
Type RM Length L Ch R = 1 ,937     ,392,392,392
BEGIN DESCRIPTION:
Mapping XS 28cc1497
END DESCRIPTION:
XS GIS Cut Line= 2
      3910515.96      10023216.4      3910531.58     10023028.95
#Sta/Elev= 24
  4911.1   75.75  4916.4   74.33  4926.5   75.09  4936.5   75.54  4946.6   74.97
  4956.6   72.27  4966.6   68.42  4976.7   66.17  4980.8      66  4984.7   65.84
  4984.9   65.34  4988.4   65.34  4988.7   65.84  4992.9    66.5  4997.9   66.36
  5006.8   69.57  5016.8   73.25  5026.8   75.97  5036.9   75.83  5046.9    75.6
  5056.9   76.12    5077   76.23  5095.6   76.01  5099.2   76.01
#Mann= 3 , 0 , 0
  4911.1     .17       0  4966.6     .09       0  5006.8    .125       0
Bank Sta=4966.6,5006.8
XS Rating Curve= 0 ,0
Exp/Cntr=0.3,0.1

Type RM Length L Ch R = 1 ,545     ,336,336,336
BEGIN DESCRIPTION:
Mapping XS d292efdb
END DESCRIPTION:
XS GIS Cut Line= 2
      3910911.79     10023199.71      3910920.83     10023044.77
#Sta/Elev= 23
  4943.6   75.23  4952.3   74.92  4959.6    72.1  4964.6    72.1  4972.3    68.5
  4981.6   65.82  4982.3   65.62  4990.3   64.94  4990.6   64.44  4994.1   64.44
  4994.3   64.94  5002.3   65.88  5012.4   68.29  5022.4   72.22  5032.4   75.39
  5042.4   75.24  5052.4   74.92  5062.4   75.54  5072.5   75.72    5080   75.71
  5082.5   75.71  5092.5   75.95  5098.8   75.83
#Mann= 4 ,-1 , 0
  4943.6     .17       0  4972.3     .07       0  5012.4     .11       0
    5080    .125       0
Bank Sta=4972.3,5012.4
XS Rating Curve= 0 ,0
Exp/Cntr=0.3,0.1

Type RM Length L Ch R = 1 ,209     ,0,0,0
BEGIN DESCRIPTION:
Mapping XS 14759f9f
END DESCRIPTION:
XS GIS Cut Line= 2
      3911246.42     10023237.25      3911256.84     10023049.74
#Sta/Elev= 26
  4919.4   74.68  4925.2   74.59  4935.6   74.42  4939.8   74.66  4945.6   74.98
  4955.6   74.66  4965.6   71.86  4975.7    67.9  4985.7   64.67  4993.7   63.83
  4993.9   63.33  4997.4   63.33  4997.7   63.83  5005.7   65.19  5015.7   67.66
  5025.7   71.27    5033   74.66    5038   74.32  5045.8   74.93  5055.8   75.04
  5065.8   75.62  5075.8   75.99  5085.8   76.09  5095.8   76.02    5104   75.67
  5107.2   75.67
#Mann= 5 ,-1 , 0
  4919.4    .125       0  4925.2     .17       0  4939.8    .125       0
  4975.7     .09       0  5015.7    .125       0
Bank Sta=4975.7,5015.7
XS Rating Curve= 0 ,0
Exp/Cntr=0.3,0.1

Chan Stop Cuts=-1
Use User Specified Reach Order=0
Composite Channel Slope=5