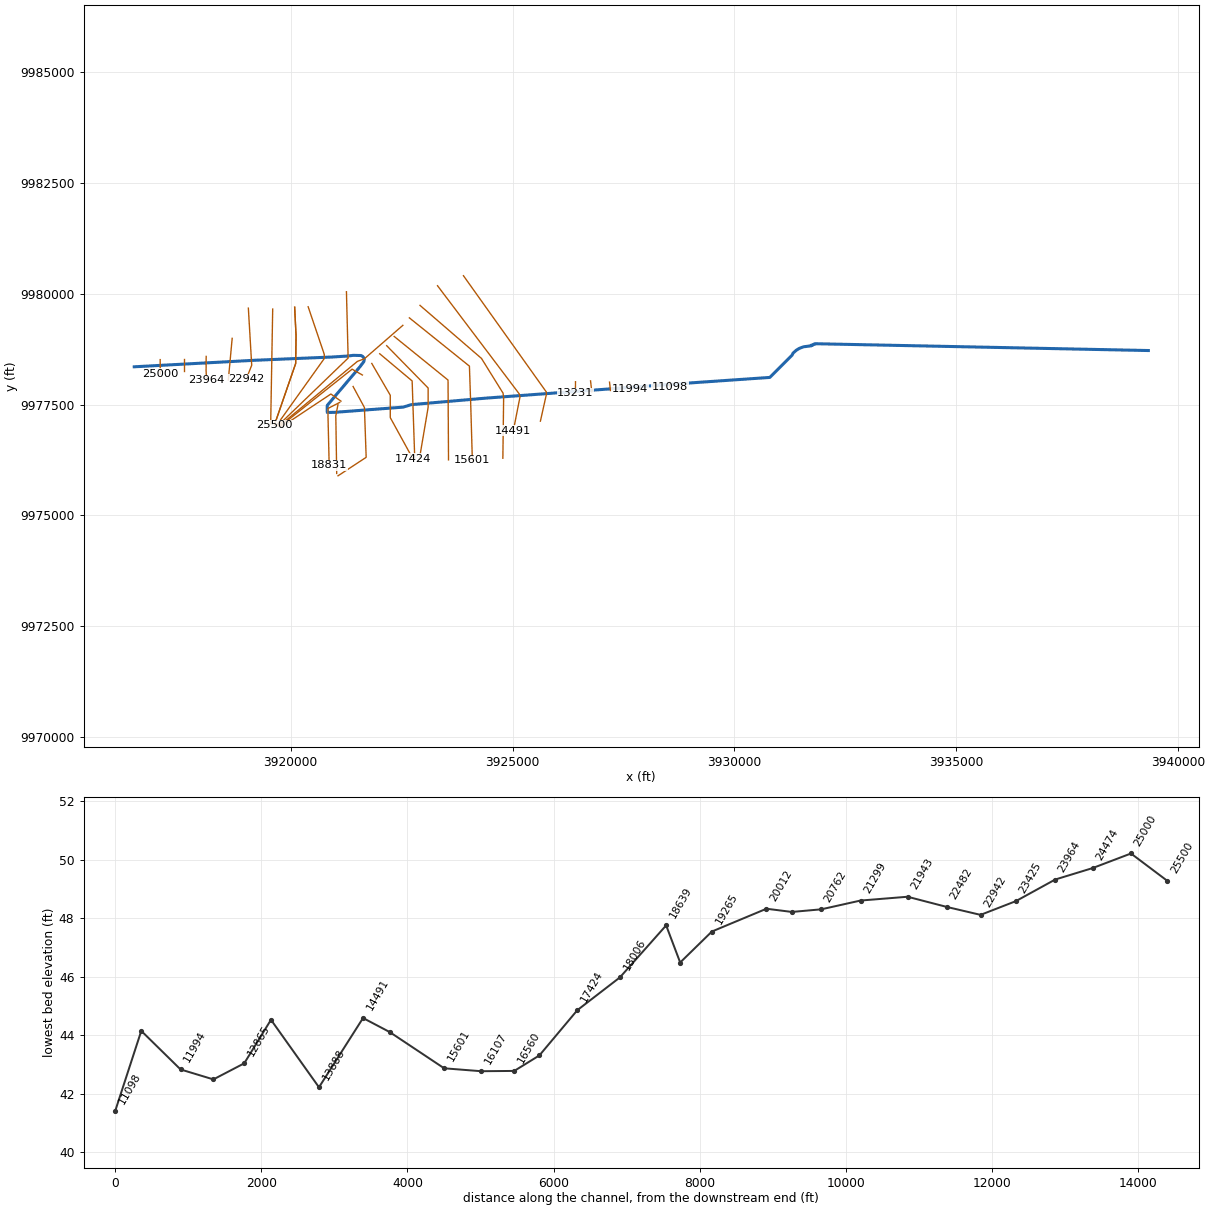
--- G103 15 00.prj (project) ---

Proj Title=G103 15 00 Base Level Engineering
Current Plan=p01
Default Exp/Contr=0.3,0.1
English Units
Geom File=g01
Flow File=f01
Flow File=f02
Plan File=p01
Y Axis Title=Elevation
X Axis Title(PF)=Main Channel Distance
X Axis Title(XS)=Station
BEGIN DESCRIPTION:
G103 15 00
END DESCRIPTION:
DSS Export Rating Curves= 0
DSS Export Rating Curve Sorted= 0
DSS Export Volume Flow Curves= 0
DXF OffsetX= 0
DXF OffsetY= 0
DXF ScaleX= 1
DXF ScaleY= 10

--- G103 15 00.p01 (plan) ---

Plan Title=Multiple Run
Program Version=4.10
Short Identifier=Multiple
Geom File=g01
Flow File=f01
Subcritical Flow
K Sum by GR= 0
Std Step Tol= 0.01
Critical Tol= 0.01
Num of Std Step Trials= 20
Max Error Tol= 0.3
Flow Tol Ratio= 0.001
Split Flow NTrial= 30
Split Flow Tol= 0.02
Split Flow Ratio= 0.02
Log Output Level= 0
Friction Slope Method= 1
Unsteady Friction Slope Method= 2
Unsteady Bridges Friction Slope Method= 1
Parabolic Critical Depth
Global Vel Dist= 1 , 1 , 1
Global Log Level= 0
CheckData=True
Encroach Param=-1 ,0,0, 0
BEGIN DESCRIPTION:
Multiple Run
END DESCRIPTION:
Computation Interval=1HOUR
Output Interval=1HOUR
Run HTab= 0
Run UNet= 0
Run PostProcess= 0
Run WQNet= 0
UNET Theta= 1
UNET Theta Warmup= 1
UNET ZTol= 0.02
UNET ZSATol= 0.05
UNET MxIter= 20
UNET MaxInSteps= 0
UNET DtIC= 0
UNET DtMin= 0
UNET MaxCRTS= 20
UNET WFStab= 2
UNET SFStab= 1
UNET WFX= 1
UNET SFX= 1
UNET DSS MLevel= 4
UNET DZMax Abort= 100
UNET Convert EG Bridges= 0
UNET Use Existing IB Tables=-1
UNET Froude Reduction=False
UNET Froude Limit= 1
UNET Froude Power= 10
UNET Time Slicing=0,0, 5
UNET Junction Losses=0
Instantaneous Interval=1HOUR
Write IC File= 0
Write IC File at Sim End=0
Echo Input=False
Echo Parameters=False
Echo Output=False
Write Detailed= 0
WQ AD Non Conservative
WQ ULTIMATE=-1
WQ Max Comp Step=1HOUR
WQ Output Interval=15MIN
WQ Output Selected Increments= 0
WQ Output face flow=0
WQ Output face velocity=0
WQ Output face area=0
WQ Output face dispersion=0
WQ Output cell volume=0
WQ Output cell surface area=0
WQ Output cell continuity=0
WQ Output cumulative cell continuity=0
WQ Output face conc=0
WQ Output face dconc_dx=0
WQ Output face courant=0
WQ Output face peclet=0
WQ Output face adv mass=0
WQ Output face disp mass=0
WQ Output cell mass=0
WQ Output cell source sink temp=0
WQ Output cell source sink nsm=0
WQ Output MaxMinRange=-1
WQ Daily Max Min Mean=-1
WQ Daily Range=0
WQ Daily Time=0
WQ Create Restart=0
WQ Fixed Restart=0
WQ System Summary=0
WQ Use Fixed Temperature=0
Sorting and Armoring Iterations= 10
XS Update Threshold= 0.02
Hydraulics Update Threshold= 0.02
Energy Slope Method= 1
Volume Change Method= 0
XS Weighting Method= 0
Number of US Weighted Cross Sections= 1
Number of DS Weighted Cross Sections= 1
Upstream XS Weight=0.25
Main XS Weight=0.5
Downstream XS Weight=0.25
Number of DS XS's Weighted with US Boundary= 1
Upstream Boundary Weight= 1
Weight of XSs Associated with US Boundary= 0
Number of US XS's Weighted with DS Boundary= 1
Downstream Boundary Weight= 0.5
Weight of XSs Associated with DS Boundary= 0.5
Sediment Output Level= 4
Mass or Volume Output= 0
Output Increment Type= 1
Profile and TS Output Increment= 10
XS Output Flag= 0
XS Output Increment= 10
Disregard all LS=0
Disregard all Conn=0
Disregard all Breaches=0
Disregard all Pumps=0

--- G103 15 00.f01 (steady flow) ---

Flow Title=Multiple
Program Version=4.10
Number of Profiles= 7
Profile Names=10-year,25-year,50-year,1pct_min,100-year,1pct_plu,500-year
River Rch & RM=G103 15 00,Reach-1         ,25500
     160     193     242     100     302     912     488
River Rch & RM=G103 15 00,Reach-1         ,20360
     159     188     232      95     286     864     449
River Rch & RM=G103 15 00,Reach-1         ,16904
     256     317     404     170     512    1546     857
River Rch & RM=G103 15 00,Reach-1         ,14856
     400     494     627     261     788    2380    1293
River Rch & RM=G103 15 00,Reach-1         ,9928
     472     588     750     314     949    2866    1576
Boundary for River Rch & Prof#=G103 15 00,Reach-1         , 1
Up Type= 0
Dn Type= 3
Dn Slope=0.00021
Boundary for River Rch & Prof#=G103 15 00,Reach-1         , 2
Up Type= 0
Dn Type= 3
Dn Slope=0.00021
Boundary for River Rch & Prof#=G103 15 00,Reach-1         , 3
Up Type= 0
Dn Type= 3
Dn Slope=0.00021
Boundary for River Rch & Prof#=G103 15 00,Reach-1         , 4
Up Type= 0
Dn Type= 3
Dn Slope=0.00021
Boundary for River Rch & Prof#=G103 15 00,Reach-1         , 5
Up Type= 0
Dn Type= 3
Dn Slope=0.00021
Boundary for River Rch & Prof#=G103 15 00,Reach-1         , 6
Up Type= 0
Dn Type= 3
Dn Slope=0.00021
Boundary for River Rch & Prof#=G103 15 00,Reach-1         , 7
Up Type= 0
Dn Type= 3
Dn Slope=0.00021
DSS Import GetInterval= 0
DSS Import GetPeak= 0
DSS Import FillOption= 0

--- G103 15 00.f02 (steady flow) ---

Flow Title=Orig_BLE_Flows
Program Version=4.10
Number of Profiles= 7
Profile Names=10-year,25-year,50-year,1pct_min,100-year,1pct_plu,500-year
River Rch & RM=G103 15 00,Reach-1         ,25500
     160     189     210      77     232     701     284
River Rch & RM=G103 15 00,Reach-1         ,20360
     159     184     202      73     220     664     261
River Rch & RM=G103 15 00,Reach-1         ,16904
     256     311     351     131     394    1191     498
River Rch & RM=G103 15 00,Reach-1         ,14903
     618     784     910     347    1047    3162    1390
River Rch & RM=G103 15 00,Reach-1         ,9928
     678     860    1000     381    1151    3475    1528
Boundary for River Rch & Prof#=G103 15 00,Reach-1         , 1
Up Type= 0
Dn Type= 3
Dn Slope=0.00021
Boundary for River Rch & Prof#=G103 15 00,Reach-1         , 2
Up Type= 0
Dn Type= 3
Dn Slope=0.00021
Boundary for River Rch & Prof#=G103 15 00,Reach-1         , 3
Up Type= 0
Dn Type= 3
Dn Slope=0.00021
Boundary for River Rch & Prof#=G103 15 00,Reach-1         , 4
Up Type= 0
Dn Type= 3
Dn Slope=0.00021
Boundary for River Rch & Prof#=G103 15 00,Reach-1         , 5
Up Type= 0
Dn Type= 3
Dn Slope=0.00021
Boundary for River Rch & Prof#=G103 15 00,Reach-1         , 6
Up Type= 0
Dn Type= 3
Dn Slope=0.00021
Boundary for River Rch & Prof#=G103 15 00,Reach-1         , 7
Up Type= 0
Dn Type= 3
Dn Slope=0.00021
DSS Import GetInterval= 0
DSS Import GetPeak= 0
DSS Import FillOption= 0

--- G103 15 00.g01 (geometry) ---

Geom Title=Existing Conditions
Program Version=4.10

River Reach=G103 15 00      ,Reach-1
Reach XY= 30
      3916477.34      9978355.97      3919159.63       9978501.8
      3920957.47        9978578.      3921298.18       9978599.7
      3921411.02       9978614.9      3921588.98      9978610.56
      3921630.21      9978584.51      3921662.76      9978536.77
      3921651.91      9978476.01      3921562.93      9978356.65
       3920826.3      9977485.19       3920826.3      9977324.72
      3920998.37      9977328.23      3922534.83      9977445.42
      3922721.46      9977501.84      3924409.83      9977649.41
      3928939.98       9977987.3      3930797.44      9978116.05
      3931298.23      9978616.84      3931322.05      9978664.81
      3931391.49      9978727.74      3931463.11      9978771.15
      3931558.59      9978808.04      3931728.23      9978829.08
      3931738.23      9978846.84      3931768.23      9978846.84
      3931788.23      9978866.84      3931808.23      9978866.84
      3931818.23      9978876.84      3939326.91      9978723.18

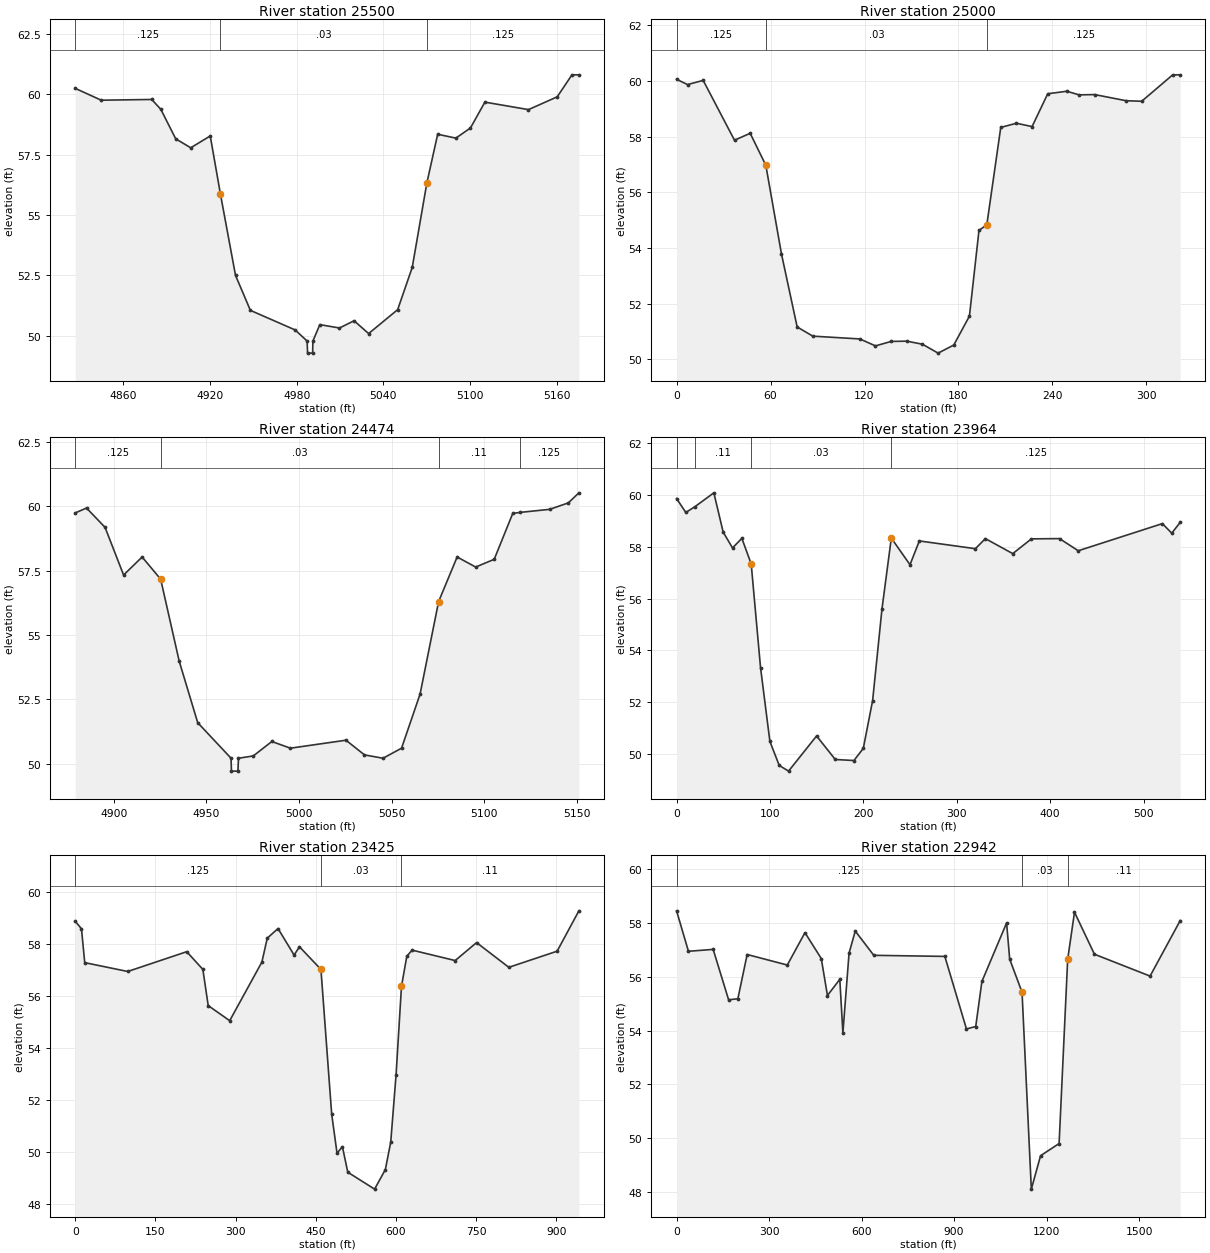
Type RM Length L Ch R = 1 ,25500   ,500,500,500
BEGIN DESCRIPTION:
G103-15-00 51.0
END DESCRIPTION:
XS GIS Cut Line= 4
      3920091.71      9979700.39      3920123.39      9979049.78
      3920114.28      9978429.99      3919634.68       9977039.8
#Sta/Elev= 30
  4826.6   60.24  4844.6   59.75  4879.6   59.78  4885.9   59.37  4896.2   58.15
  4906.6   57.78  4920.1   58.27  4927.2   55.85  4937.6    52.5  4947.9   51.05
  4978.9   50.24  4987.2   49.78  4987.5   49.28    4991   49.28  4991.2   49.78
    4996   50.46  5009.6   50.32  5019.7   50.62  5029.8   50.09  5049.9   51.08
    5060   52.83  5070.1   56.32  5077.6   58.34  5090.2   58.18  5100.3    58.6
  5110.3   59.67  5140.5   59.36  5160.4   59.89  5170.6    60.8  5175.4    60.8
#Mann= 3 , 0 , 0
  4826.6    .125       0  4927.2     .03       0  5070.1    .125       0
Bank Sta=4927.2,5070.1
XS Rating Curve= 0 ,0
Exp/Cntr=0.3,0.1

Type RM Length L Ch R = 1 ,25000   ,526,526,526
BEGIN DESCRIPTION:
Mapping XS e2f68eb3
END DESCRIPTION:
XS GIS Cut Line= 3
      3917061.48      9978518.03      3917063.22       9978271.5
      3917065.26      9978196.49
#Sta/Elev= 30
       0   60.06       7   59.87      17   60.02      37   57.87      47   58.12
      57   56.97      67   53.78      77   51.16      87   50.83     117   50.73
     127   50.48     137   50.64     147   50.65     157   50.54     167   50.22
     177   50.51     187   51.55   193.1   54.63   198.1   54.83     207   58.33
     217   58.48     227   58.36     237   59.54   249.2   59.63     257    59.5
     267   59.51     287   59.29     297   59.27   316.8   60.22   321.6   60.22
#Mann= 3 , 0 , 0
       0    .125       0      57     .03       0   198.1    .125       0
Bank Sta=57,198.1
XS Rating Curve= 0 ,0
Exp/Cntr=0.3,0.1

Type RM Length L Ch R = 1 ,24474   ,510,510,510
BEGIN DESCRIPTION:
Mapping XS bf62ff30
END DESCRIPTION:
XS GIS Cut Line= 2
      3917587.53      9978537.13      3917587.53      9978265.33
#Sta/Elev= 29
  4879.2   59.74  4885.3   59.93  4895.3   59.18  4905.3   57.33  4915.3   58.03
  4925.3   57.17  4935.3   53.99  4945.3    51.6  4963.3   50.22  4963.5   49.72
    4967   49.72  4967.3   50.22  4975.3   50.31  4985.3   50.87  4995.3   50.61
  5025.3   50.92  5035.3   50.35  5045.3   50.22  5055.3   50.61  5065.3   52.71
  5075.3    56.3  5085.3   58.03  5095.3   57.64  5105.3   57.94  5115.3   59.72
  5119.2   59.76  5135.3   59.88  5145.3   60.13    5151   60.52
#Mann= 4 ,-1 , 0
  4879.2    .125       0  4925.3     .03       0  5075.3     .11       0
  5119.2    .125       0
Bank Sta=4925.3,5075.3
XS Rating Curve= 0 ,0
Exp/Cntr=0.3,0.1

Type RM Length L Ch R = 1 ,23964   ,539,539,539
BEGIN DESCRIPTION:
Mapping XS 422e2e9a
END DESCRIPTION:
XS GIS Cut Line= 3
      3918097.94      9978590.94      3918096.21      9978264.56
      3918106.96      9978052.03
#Sta/Elev= 30
       0   59.87     9.9   59.33    19.9   59.56    39.9   60.09    49.9   58.57
    59.9   57.96    69.9   58.33    79.9   57.34    89.9   53.33    99.9   50.48
   109.9   49.55   119.9   49.33   149.9   50.69   169.9   49.78   189.9   49.74
   199.9   50.21   209.9   52.06   219.9    55.6   229.9   58.34   249.9   57.31
   259.9   58.23   319.9   57.93   330.6   58.32   359.9   57.74   379.9   58.31
     410   58.32     430   57.85   520.1    58.9   530.1   58.53   539.2   58.95
#Mann= 4 ,-1 , 0
       0    .125       0    19.9     .11       0    79.9     .03       0
   229.9    .125       0
Bank Sta=79.9,229.9
XS Rating Curve= 0 ,0
Exp/Cntr=0.3,0.1

Type RM Length L Ch R = 1 ,23425   ,483,483,483
BEGIN DESCRIPTION:
Mapping XS 76166162
END DESCRIPTION:
XS GIS Cut Line= 2
      3918683.83      9978998.83      3918597.08      9978060.48
#Sta/Elev= 30
       0   58.88    11.7   58.59    17.8   57.29    98.2   56.95   208.6   57.71
   238.8   57.03   248.8   55.64     289   55.06   349.2   57.31   359.3   58.23
   379.4    58.6   409.5   57.58   419.5    57.9   459.7   57.03   479.8   51.47
   489.8   49.97   499.9   50.22   509.9   49.24   560.1   48.59   580.2   49.34
   590.3    50.4   600.3   52.99   610.4   56.38   620.4   57.54   630.4   57.77
   710.8   57.37   750.9   58.06   811.2   57.11   901.6   57.73   942.3   59.28
#Mann= 3 , 0 , 0
       0    .125       0   459.7     .03       0   610.4     .11       0
Bank Sta=459.7,610.4
XS Rating Curve= 0 ,0
Exp/Cntr=0.3,0.1

Type RM Length L Ch R = 1 ,22942   ,460,460,460
BEGIN DESCRIPTION:
Mapping XS d96fe37b
END DESCRIPTION:
XS GIS Cut Line= 3
      3919048.31      9979679.55      3919123.98      9978391.29
      3918997.96      9978072.35
#Sta/Elev= 30
       0   58.44    38.5   56.94   118.7   57.01   168.8   55.14   198.8   55.18
   228.9   56.82   359.1   56.43   416.4   57.63   469.3   56.67   489.3    55.3
   529.4    55.9   539.4   53.91   559.4   56.87   579.5   57.69   639.6   56.79
     870   56.75   940.1   54.06   970.2   54.15   990.2   55.82  1070.3   57.99
  1080.3   56.65  1120.4   55.42  1150.5   48.12  1180.5   49.36  1240.6   49.81
  1268.4   56.64  1290.5   58.39  1355.2   56.83  1535.6   56.02  1633.4   58.08
#Mann= 3 , 0 , 0
       0    .125       0  1120.4     .03       0  1268.4     .11       0
Bank Sta=1120.4,1268.4
XS Rating Curve= 0 ,0
Exp/Cntr=0.3,0.1

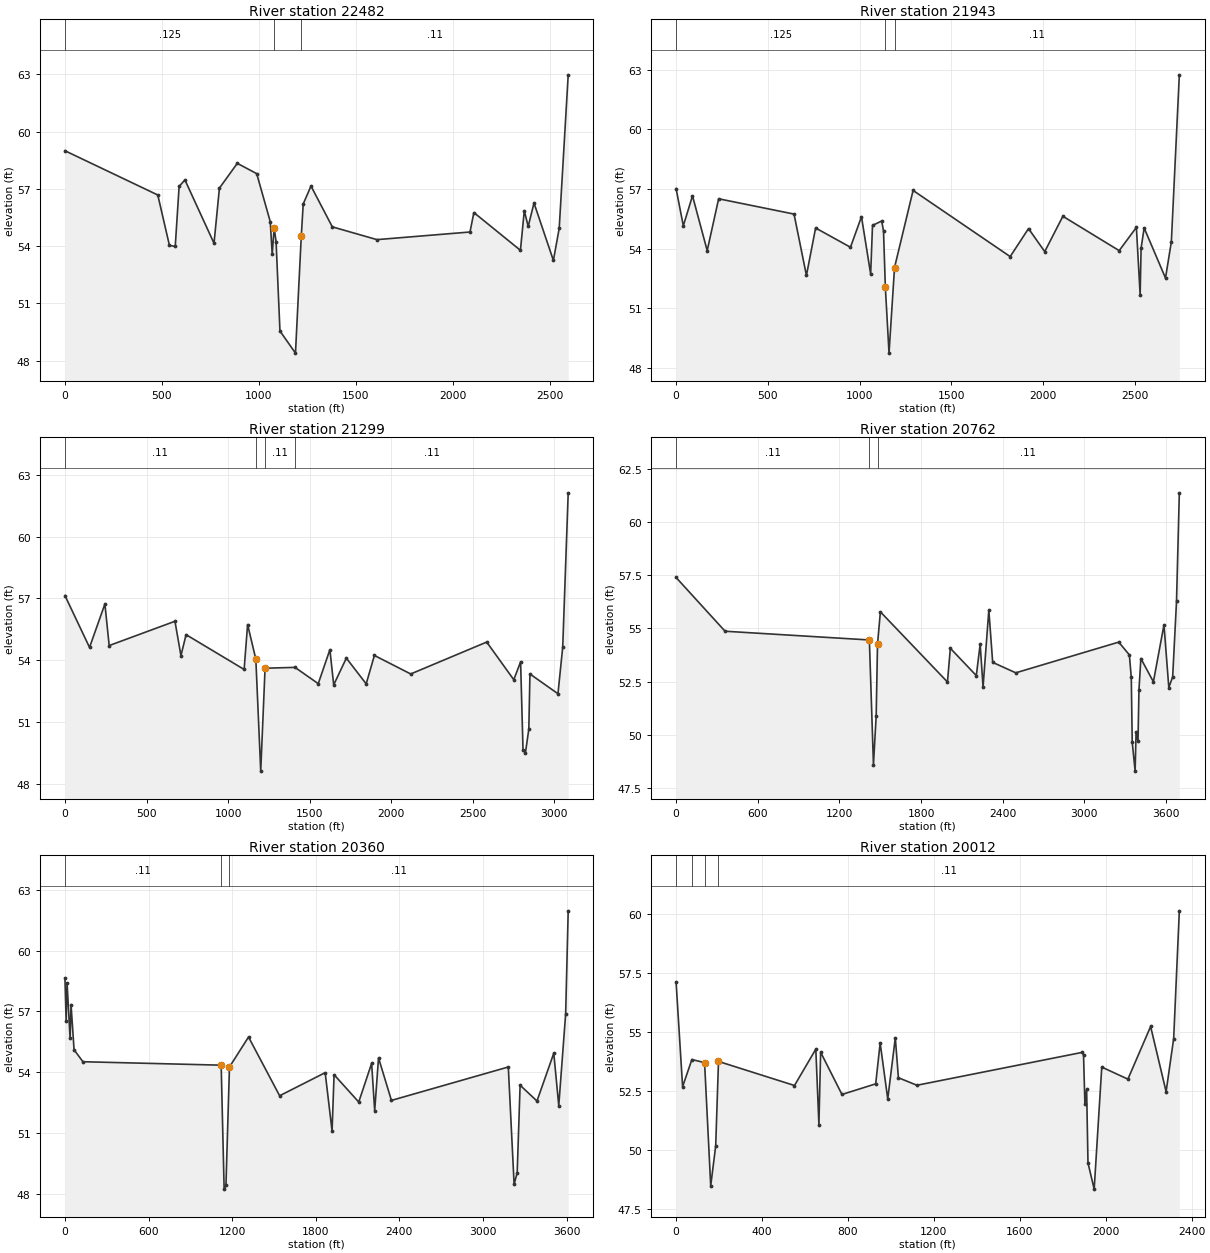
Type RM Length L Ch R = 1 ,22482   ,539,539,539
BEGIN DESCRIPTION:
Mapping XS c1d9af11
END DESCRIPTION:
XS GIS Cut Line= 2
      3919596.86      9979659.79      3919551.35      9977063.23
#Sta/Elev= 30
       0      59   478.8   56.68   538.8   54.04   568.8   53.98   588.8   57.13
   618.8   57.47   768.8   54.15   796.6   57.04   888.9   58.34   988.9    57.8
  1058.9   55.28  1068.9   53.57  1078.9   54.96  1088.9   54.23  1108.9   49.55
  1188.9   48.39  1218.9   54.54  1228.9   56.21  1268.9   57.15  1378.9   55.01
    1609   54.34    2089   54.74    2109   55.76  2349.1   53.78  2369.1   55.86
  2389.1   55.03  2419.1   56.26  2519.1   53.25  2549.1   54.93  2595.5   62.98
#Mann= 3 , 0 , 0
       0    .125       0  1078.9     .03       0  1218.9     .11       0
Bank Sta=1078.9,1218.9
XS Rating Curve= 0 ,0
Exp/Cntr=0.3,0.1

Type RM Length L Ch R = 1 ,21943   ,644,644,644
BEGIN DESCRIPTION:
Mapping XS ac4716d7
END DESCRIPTION:
XS GIS Cut Line= 4
      3920091.71      9979700.39      3920123.39      9979049.78
      3920114.28      9978429.99      3919634.68       9977039.8
#Sta/Elev= 30
       0   57.02    39.4   55.15    89.4   56.66   169.5    53.9   231.8   56.51
   642.6   55.74   710.1   52.65   760.1   55.04   950.1   54.07  1010.1   55.61
  1060.1   52.72  1070.1   55.17  1120.1   55.39  1130.1   54.89  1140.1   52.06
  1160.1   48.74  1190.1   53.05  1291.2   56.93  1820.2    53.6  1920.1   55.01
  2008.4   53.85  2107.3   55.63    2414    53.9  2507.8   55.07  2528.2   51.68
  2533.5   54.03  2550.1   55.04  2666.4   52.52  2698.2   54.34  2741.8   62.75
#Mann= 3 , 0 , 0
       0    .125       0  1140.1     .03       0  1190.1     .11       0
Bank Sta=1140.1,1190.1
XS Rating Curve= 0 ,0
Exp/Cntr=0.3,0.1

Type RM Length L Ch R = 1 ,21299   ,537,537,537
BEGIN DESCRIPTION:
Mapping XS f915ab9b
END DESCRIPTION:
XS GIS Cut Line= 4
      3920395.53      9979711.67      3920759.05      9978637.33
      3920759.35      9978542.98      3919681.99      9977029.38
#Sta/Elev= 30
       0   57.14   150.7   54.62     245   56.73   271.1   54.71   674.5   55.89
   711.2   54.22   742.7   55.24  1098.6   53.55  1119.9   55.73  1170.4   54.05
  1200.4   48.61    1227   53.61  1410.5   53.65  1553.1   52.86  1624.5   54.51
  1647.8    52.8  1725.3    54.1    1847   52.85  1897.4   54.23    2120   53.33
    2586   54.88    2752   53.05  2793.8   53.92  2808.6   49.66  2823.3   49.49
  2844.2   50.65  2851.1   53.33  3022.9   52.37    3052   54.63  3085.7   62.13
#Mann= 4 ,-1 , 0
       0     .11       0  1170.4     .03       0    1227     .11       0
  1410.5     .11       0
Bank Sta=1170.4,1227
XS Rating Curve= 0 ,0
Exp/Cntr=0.3,0.1

Type RM Length L Ch R = 1 ,20762   ,402,402,402
BEGIN DESCRIPTION:
Mapping XS 5fa99e94
END DESCRIPTION:
XS GIS Cut Line= 3
      3921258.36      9980050.87      3921296.83      9978552.82
      3919713.24      9977024.17
#Sta/Elev= 30
       0   57.39   359.9   54.87  1420.3   54.46  1450.3   48.61  1470.3   50.88
  1480.3   54.27  1501.3   55.78  1994.2   52.49  2015.3   54.07  2206.2   52.79
  2234.5   54.26  2255.8   52.26  2298.2   55.86  2326.5   53.41  2496.3   52.92
  3252.9   54.36  3330.9   53.76    3345   52.71    3352   49.67  3373.3   48.31
  3380.3   50.13  3394.4   49.71  3401.4   52.11  3415.5   53.59  3507.6    52.5
  3585.3   55.17  3620.8   52.23  3649.1   52.73  3677.4   56.27  3698.2   61.36
#Mann= 3 , 0 , 0
       0     .11       0  1420.3     .03       0  1480.3     .11       0
Bank Sta=1420.3,1480.3
XS Rating Curve= 0 ,0
Exp/Cntr=0.3,0.1

Type RM Length L Ch R = 1 ,20360   ,348,348,348
BEGIN DESCRIPTION:
Mapping XS b81c3736
END DESCRIPTION:
XS GIS Cut Line= 4
      3922529.13      9979291.73      3921662.76      9978536.77
      3921507.51      9978479.75      3919736.68      9977013.75
#Sta/Elev= 30
       0   58.62     8.5    56.5    15.1    58.4      37   55.66    43.6   57.33
    65.4    55.1     129   54.51  1121.1   54.34  1142.4   48.22  1155.4    48.4
  1180.6   54.25  1317.4   55.73  1540.6   52.83  1867.5   53.97    1917   51.09
  1931.3   53.87  2108.4   52.52  2200.9   54.43  2222.8   52.09  2250.4    54.7
  2342.9    52.6  3181.7   54.25  3223.4   48.46  3245.5   49.03  3266.4   53.35
  3387.5   52.57  3508.1   54.93  3543.8   52.34  3593.3   56.88  3611.6   61.96
#Mann= 3 , 0 , 0
       0     .11       0  1121.1     .03       0  1180.6     .11       0
Bank Sta=1121.1,1180.6
XS Rating Curve= 0 ,0
Exp/Cntr=0.3,0.1

Type RM Length L Ch R = 1 ,20012   ,747,747,747
BEGIN DESCRIPTION:
Mapping XS 3aa1a5dd
END DESCRIPTION:
XS GIS Cut Line= 3
      3921617.97      9978170.39      3921386.06      9978302.44
      3919761.48      9977009.11
#Sta/Elev= 30
       0    57.1    30.3   52.67    73.5   53.82   132.6   53.69   161.2   48.47
   184.3   50.16   197.4   53.74   551.1   52.72   650.4   54.26   664.8   51.06
   672.8   54.13   772.1   52.34   929.1   52.79   949.9   54.52   985.2   52.15
  1020.4   54.74  1034.8   53.05    1121   52.73  1888.5   54.12  1896.5   54.03
  1902.9   51.95  1910.9   52.56  1917.3   49.44  1946.1   48.33  1981.4    53.5
  2103.1   52.99  2208.8   55.22  2280.9   52.46  2316.1   54.71  2342.5   60.12
#Mann= 4 ,-1 , 0
       0     .17       0    73.5     .11       0   132.6     .03       0
   197.4     .11       0
Bank Sta=132.6,197.4
XS Rating Curve= 0 ,0
Exp/Cntr=0.3,0.1

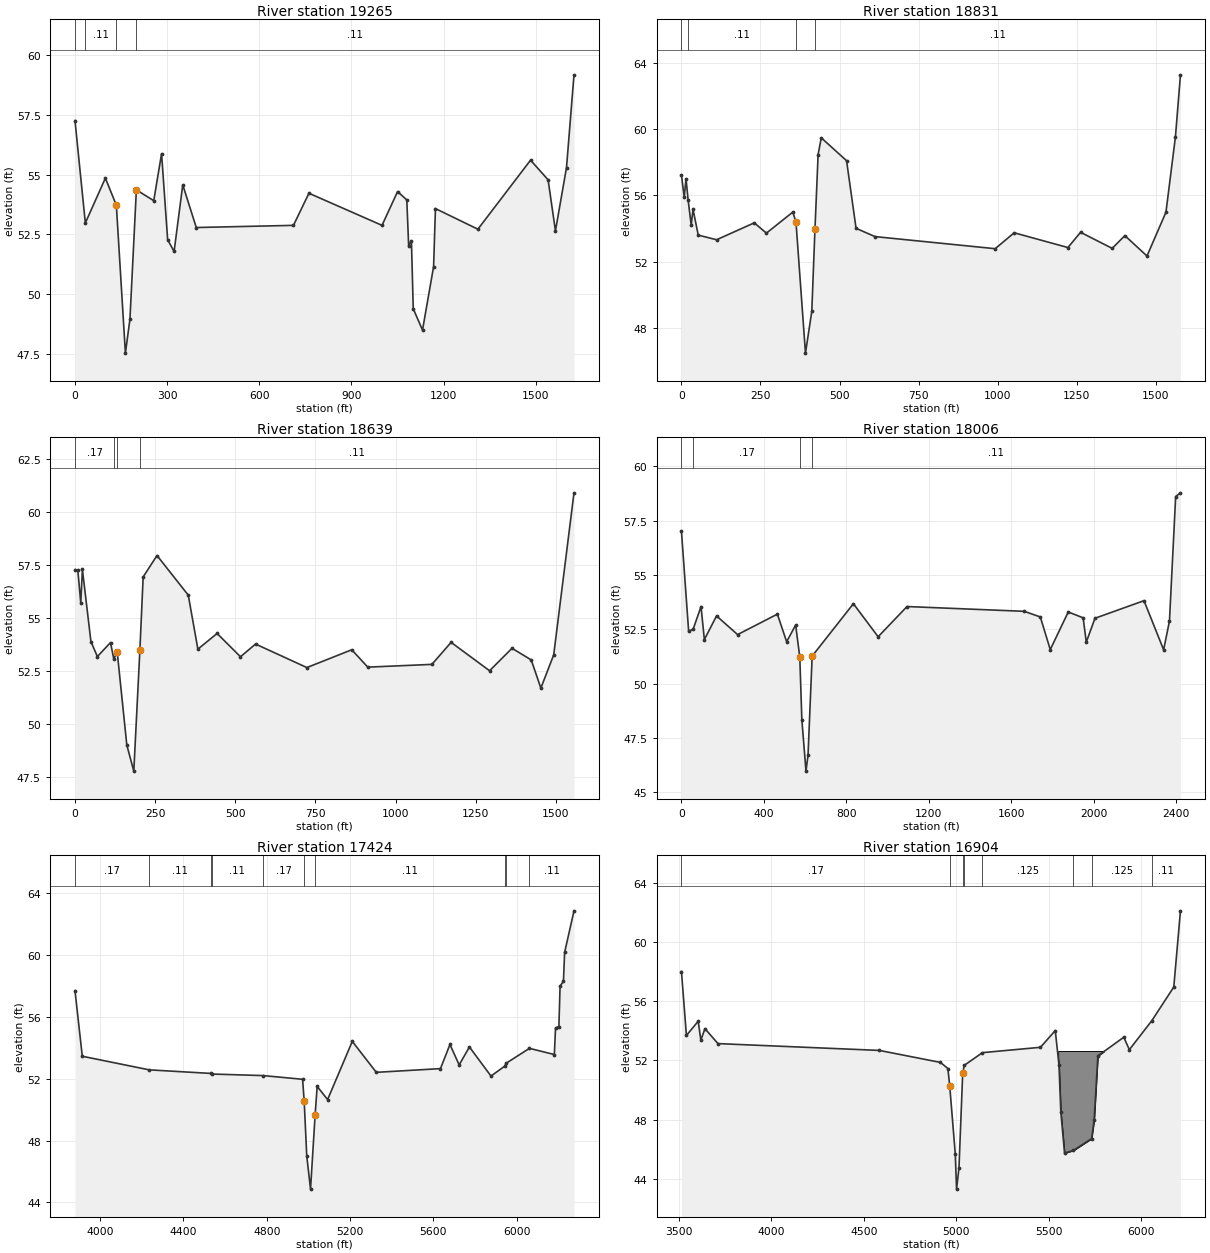
Type RM Length L Ch R = 1 ,19265   ,434,434,434
BEGIN DESCRIPTION:
Mapping XS 70f687ce
END DESCRIPTION:
XS GIS Cut Line= 3
      3921135.27      9977580.09      3920907.76      9977741.33
      3919787.53      9976996.08
#Sta/Elev= 30
       0   57.25    33.7   52.98    98.9   54.85   134.6   53.72   164.1   47.55
   178.9   48.97   199.8   54.36   256.4   53.91   281.8   55.87   301.6   52.28
   322.6   51.79   350.8   54.57   394.8   52.79   711.1   52.88   761.5   54.22
   999.4   52.88    1050   54.29  1080.1   53.94  1086.1   52.02  1095.1   52.24
  1101.1    49.4  1131.2   48.51  1167.3   51.16  1173.3   53.58  1311.5   52.72
  1482.9    55.6    1540   54.78  1563.9   52.65  1599.9   55.29  1624.3   59.16
#Mann= 4 ,-1 , 0
       0     .17       0    33.7     .11       0   134.6     .03       0
   199.8     .11       0
Bank Sta=134.6,199.8
XS Rating Curve= 0 ,0
Exp/Cntr=0.3,0.1

Type RM Length L Ch R = 1 ,18831   ,192,192,192
BEGIN DESCRIPTION:
Mapping XS 77c92a1f
END DESCRIPTION:
XS GIS Cut Line= 4
       3921106.7      9977552.11      3920841.94      9977415.39
      3920843.03      9977232.02      3920869.57      9976134.32
#Sta/Elev= 30
       0   57.23     8.7    55.9    14.4   57.01    21.2   55.71    30.9    54.2
    36.5   55.17    53.1   53.61   111.2   53.33   230.3   54.35   268.8   53.73
   352.3      55   362.3   54.39   392.3   46.49   412.3   49.01   422.3   53.96
   432.3   58.47   442.3   59.48   522.3    58.1   552.3   54.02   612.3   53.52
   992.4   52.79  1052.5   53.75  1222.5   52.86  1262.5   53.78  1362.6   52.81
  1402.6   53.58  1472.6   52.35  1532.6   54.99  1562.6   59.54  1578.5   63.28
#Mann= 4 ,-1 , 0
       0     .17       0    21.2     .11       0   362.3     .06       0
   422.3     .11       0
Bank Sta=362.3,422.3
XS Rating Curve= 0 ,0
Exp/Cntr=0.3,0.1

Type RM Length L Ch R = 1 ,18639   ,633,633,633
BEGIN DESCRIPTION:
Mapping XS cef64eac
END DESCRIPTION:
XS GIS Cut Line= 3
      3921067.03      9977499.86      3921018.85      9977251.16
      3921038.84      9975947.69
#Sta/Elev= 30
       0   57.27     8.9   57.24      18    55.7    23.1   57.28    49.7   53.88
    69.8   53.17   110.8   53.83     121   53.06   131.7   53.39   161.7   48.99
   183.5   47.76   202.5   53.48   212.7   56.93   255.9   57.94   353.4   56.07
   383.4   53.52   443.4   54.26   516.3   53.16   563.4   53.76   723.5   52.65
   863.5   53.49   913.5   52.67  1113.5    52.8  1173.5   53.84  1293.5    52.5
  1363.5   53.56  1423.5   53.01  1453.5   51.68  1493.6   53.25  1556.9    60.9
#Mann= 4 ,-1 , 0
       0     .17       0     121     .11       0   131.7     .06       0
   202.5     .11       0
Bank Sta=131.7,202.5
XS Rating Curve= 0 ,0
Exp/Cntr=0.3,0.1

Type RM Length L Ch R = 1 ,18006   ,582,582,582
BEGIN DESCRIPTION:
Mapping XS 96e202b8
END DESCRIPTION:
XS GIS Cut Line= 4
      3921408.57      9977911.02      3921663.84      9977436.41
       3921702.9      9976312.27      3921069.22      9975895.61
#Sta/Elev= 30
       0   57.01    34.9   52.41    56.8   52.51      95   53.55   111.2   52.03
   170.3   53.12   272.4   52.26   465.5    53.2   510.5   51.93   554.2    52.7
   574.3   51.22   584.3   48.34   604.3   45.98   614.3   46.72   634.3   51.27
   834.4   53.68   954.5   52.16  1094.6   53.55  1663.7   53.33  1741.6   53.07
  1789.8   51.57  1877.2    53.3  1949.5   53.03  1964.6   51.91  2006.7   53.01
  2244.7   53.82    2340   51.56  2368.3   52.88  2398.4   58.61  2421.7   58.78
#Mann= 4 ,-1 , 0
       0     .15       0    56.8     .17       0   574.3     .06       0
   634.3     .11       0
Bank Sta=574.3,634.3
XS Rating Curve= 0 ,0
Exp/Cntr=0.3,0.1

Type RM Length L Ch R = 1 ,17424   ,520,520,520
BEGIN DESCRIPTION:
Mapping XS 11db1f1b
END DESCRIPTION:
XS GIS Cut Line= 4
      3921829.47      9978431.37      3922245.89      9977714.05
      3922245.89      9977209.07      3922755.85      9976279.13
#Sta/Elev= 30
  3879.9   57.69  3914.9   53.45  4236.1   52.57  4531.2   52.34  4535.8    52.3
  4783.1    52.2  4972.3   51.96  4979.9   50.55  4992.3      47  5010.4   44.86
  5032.3   49.64  5042.3    51.5  5092.3   50.65  5210.8   54.41  5326.1   52.41
    5634   52.65  5679.6   54.21  5723.7   52.89    5773   54.05  5876.4   52.17
  5943.7   52.82  5948.3   52.99  6061.1   53.96  6180.6   53.56  6186.3   55.28
  6202.4   55.37  6208.1   57.99  6224.2   58.29  6229.9   60.16  6274.9   62.85
#Mann= 10 ,-1 , 0
  3879.9     .17       0  4236.1     .11       0  4531.2     .17       0
  4535.8     .11       0  4783.1     .17       0  4979.9     .06       0
  5032.3     .11       0  5943.7     .17       0  5948.3    .125       0
  6061.1     .11       0
Bank Sta=4979.9,5032.3
XS Rating Curve= 0 ,0
Exp/Cntr=0.3,0.1

Type RM Length L Ch R = 1 ,16904   ,344,344,344
BEGIN DESCRIPTION:
Mapping XS 805e0aec
END DESCRIPTION:
XS GIS Cut Line= 3
      3922008.48      9978650.06      3922738.75      9978036.79
      3922796.97      9976294.98
#Sta/Elev= 30
  3514.2   57.99    3541   53.68  3604.8   54.64    3619   53.36  3641.1   54.14
  3711.4   53.13  4583.6   52.67  4913.8   51.86  4953.8   51.45  4963.8   50.27
  4993.8   45.67  5000.7   43.31  5013.8   44.75  5033.9   51.13  5042.1   51.66
  5140.5   52.52  5454.1   52.88  5534.1   54.01  5554.1   51.69  5564.2    48.5
  5584.2   45.74  5632.2   45.92  5730.5   46.72  5744.3   47.97  5764.3    52.3
  5904.3   53.56  5934.4   52.72    6056   54.68  6174.5   56.95  6210.6   62.09
#Mann= 8 ,-1 , 0
  3514.2     .17       0  4963.8     .06       0  5033.9     .17       0
  5042.1     .11       0  5140.5    .125       0  5632.2     .15       0
  5730.5    .125       0    6056     .11       0
#Block Obstruct= 1 ,-1
 5549.87  5796.5   52.63
Bank Sta=4963.8,5033.9
XS Rating Curve= 0 ,0
Exp/Cntr=0.3,0.1

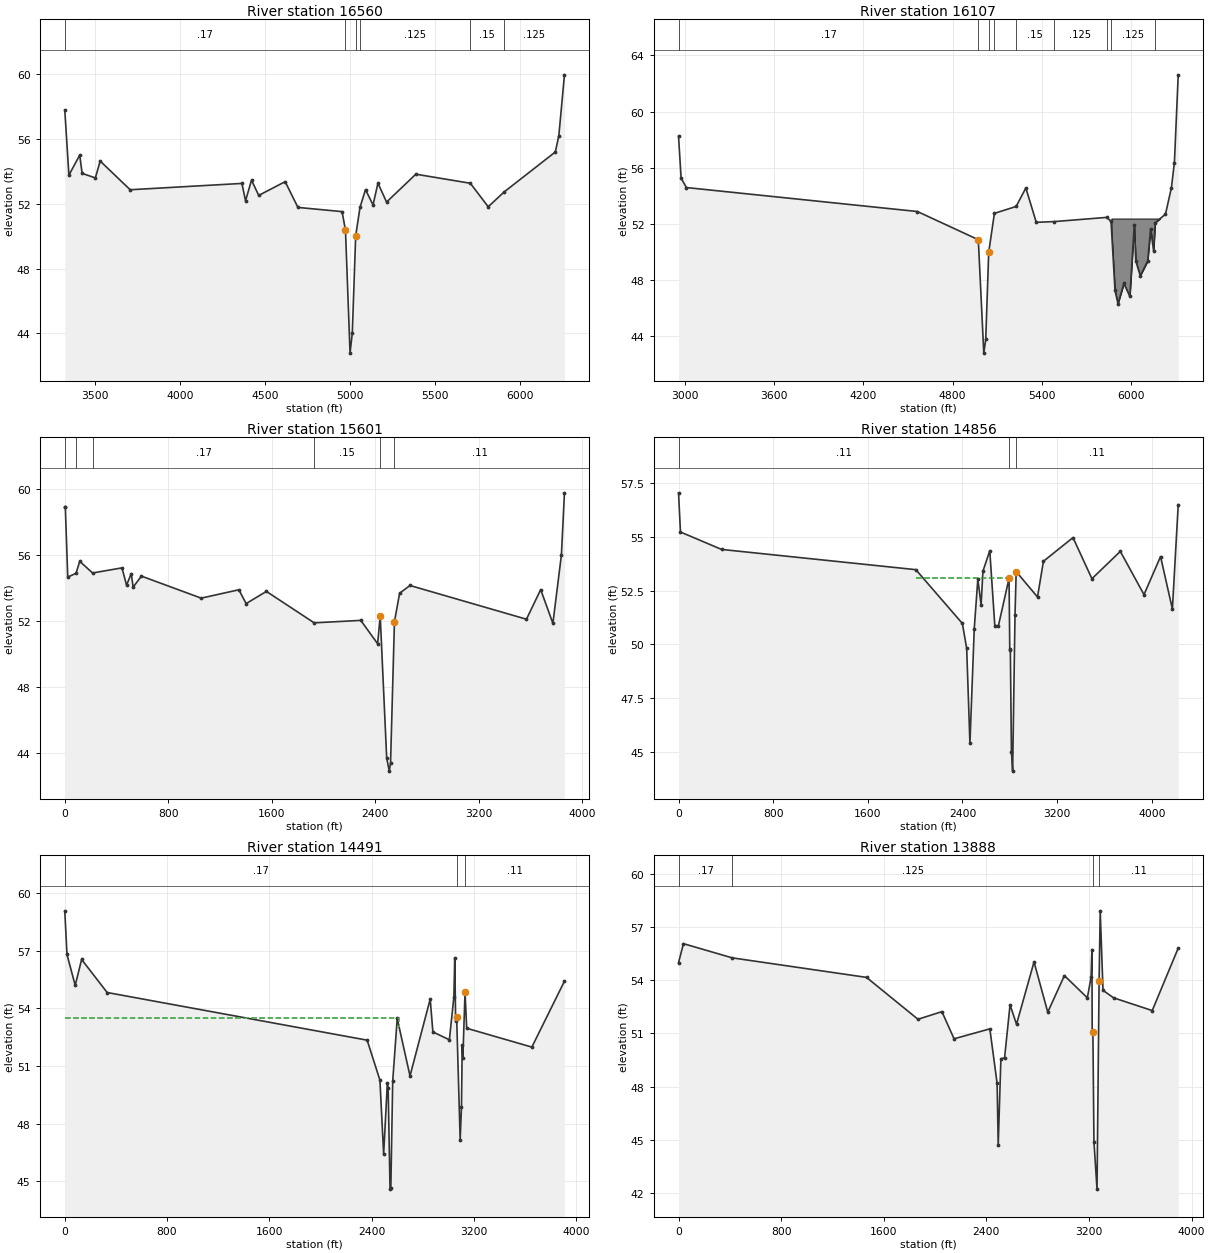
Type RM Length L Ch R = 1 ,16560   ,453,453,453
BEGIN DESCRIPTION:
Mapping XS a7eadfa2
END DESCRIPTION:
XS GIS Cut Line= 4
      3922165.08      9978832.78      3923099.19      9977877.05
      3923099.19      9977440.48      3922904.66      9976288.47
#Sta/Elev= 30
  3321.4   57.78  3345.8   53.76  3409.4      55  3423.5   53.87  3501.4   53.59
  3529.7   54.63  3706.4   52.86  4364.1   53.25  4385.4   52.18  4420.6   53.45
  4463.1   52.51  4618.7   53.36  4693.8   51.77  4953.8   51.51  4973.8   50.35
  5000.6   42.78  5013.8   44.01  5033.8   50.02  5059.2   51.77  5091.6   52.87
  5135.9   51.92  5164.8   53.27  5215.5    52.1  5387.9   53.82  5708.7   53.26
  5813.8   51.81  5908.4   52.73  6208.9   55.19  6229.6    56.2  6262.7   59.95
#Mann= 6 ,-1 , 0
  3321.4     .17       0  4973.8     .06       0  5033.8     .17       0
  5059.2    .125       0  5708.7     .15       0  5908.4    .125       0
Bank Sta=4973.8,5033.8
XS Rating Curve= 0 ,0
Exp/Cntr=0.3,0.1

Type RM Length L Ch R = 1 ,16107   ,506,506,506
BEGIN DESCRIPTION:
Mapping XS fcc94e29
END DESCRIPTION:
XS GIS Cut Line= 3
      3922334.38      9979041.09      3923547.38      9978056.71
       3923558.3      9976255.41
#Sta/Elev= 30
  2955.4   58.23  2972.7   55.25    3008   54.58  4563.2   52.87  4973.2   50.86
  5010.1   42.77  5023.2   43.75  5043.2   49.96  5081.6   52.74  5227.7   53.23
  5293.2   54.55  5363.2    52.1  5480.6   52.15  5836.4   52.45  5866.6   52.18
  5893.2   47.24  5913.2    46.3  5953.2   47.74  5993.2   46.81  6023.2   51.94
  6033.2   49.34  6063.2   48.29  6113.2   49.34  6133.2   51.64  6153.2   50.06
  6163.8   52.07  6233.2   52.68  6273.2   54.58  6293.2   56.36  6318.9   62.62
#Mann= 9 ,-1 , 0
  2955.4     .17       0  4973.2     .06       0  5043.2     .17       0
  5081.6    .125       0  5227.7     .15       0  5480.6    .125       0
  5836.4     .15       0  5866.6    .125       0  6163.8     .11       0
#Block Obstruct= 1 ,-1
 5869.27  6203.5   52.37
Bank Sta=4973.2,5043.2
XS Rating Curve= 0 ,0
Exp/Cntr=0.3,0.1

Type RM Length L Ch R = 1 ,15601   ,745,745,745
BEGIN DESCRIPTION:
Mapping XS 88dedd31
END DESCRIPTION:
XS GIS Cut Line= 4
      3922675.93      9979461.25      3924029.41      9978371.19
      3924059.26      9977489.09      3924095.48      9976247.43
#Sta/Elev= 30
       0   58.93     4.1   58.93      23   54.66      87   54.89   115.7   55.62
   214.9   54.91   442.1   55.22   477.5   54.17     514   54.87   528.4   54.05
   592.4   54.72  1054.7   53.38  1345.8   53.89    1402   53.05  1558.6   53.79
  1928.1   51.88  2288.3   52.03  2418.4   50.61  2438.4    52.3  2488.4   43.68
  2508.4   42.87  2518.4   43.38  2548.4   51.95  2588.5   53.68  2668.5   54.15
  3568.9    52.1  3678.9    53.9  3773.3   51.85    3839      56  3862.7   59.78
#Mann= 6 ,-1 , 0
       0     .17       0      87     .11       0   214.9     .17       0
  1928.1     .15       0  2438.4     .06       0  2548.4     .11       0
Bank Sta=2438.4,2548.4
XS Rating Curve= 0 ,0
Exp/Cntr=0.3,0.1

Type RM Length L Ch R = 1 ,14856   ,365,365,365
BEGIN DESCRIPTION:
Mapping XS c3a001ec
END DESCRIPTION:
XS GIS Cut Line= 5
      3922915.99      9979742.57      3924301.41      9978544.65
      3924787.52      9977759.93      3924800.23      9977651.47
      3924782.98       9976291.7
#Sta/Elev= 30
       0   57.04    16.1   55.22   363.8   54.41  2005.7   53.47  2399.2   50.97
  2435.6   49.81    2463    45.4  2499.6   50.73  2529.7   53.03  2557.5   51.84
  2572.9    53.4  2630.8   54.35  2673.3   50.87    2704   50.87  2793.7   53.07
  2799.6   49.79  2804.6   49.76  2813.8   45.02  2823.9   44.11  2844.1   51.38
  2854.1   53.38  3034.2    52.2  3084.2   53.86  3334.2   54.96  3494.2   53.05
  3734.3   54.32  3934.3   52.31  4074.3   54.08  4174.3   51.64  4223.7   56.49
#Mann= 3 , 0 , 0
       0     .11       0  2793.7     .06       0  2854.1     .11       0
#XS Ineff= 1 ,-1
  2006.3 2783.56   53.09
Permanent Ineff=
       F
Bank Sta=2793.7,2854.1
XS Rating Curve= 0 ,0
Exp/Cntr=0.3,0.1

Type RM Length L Ch R = 1 ,14491   ,603,603,603
BEGIN DESCRIPTION:
Mapping XS 067e57cf
END DESCRIPTION:
XS GIS Cut Line= 4
      3923310.11      9980186.63      3925151.84      9977744.62
      3925167.98      9977671.66      3925018.29      9976910.69
#Sta/Elev= 30
       0   59.07    17.2    56.8    81.7   55.19   131.7   56.54   331.5   54.82
  2365.4   52.34  2465.3   50.26  2494.4    46.4  2523.6   50.13  2529.8   49.83
  2544.4   44.59  2550.7   44.64  2565.2    50.2  2600.6   53.47  2700.6   50.48
  2858.7   54.48  2879.6   52.77  3008.6   52.36    3044    54.6  3050.6   56.62
  3057.7   53.34  3065.4   53.55    3093   47.17  3103.3   48.85    3109   52.07
  3114.1   51.42  3131.1   54.84  3144.2   52.96  3653.8   51.98  3908.9   55.41
#Mann= 3 ,-1 , 0
       0     .17       0  3065.4     .06       0  3131.1     .11       0
#XS Ineff= 2 , 0
         2614.68    53.5
Permanent Ineff=
       F       F
Bank Sta=3065.4,3131.1
XS Rating Curve= 0 ,0
Exp/Cntr=0.3,0.1

Type RM Length L Ch R = 1 ,13888   ,657,657,657
BEGIN DESCRIPTION:
G103-15-00 28.0
END DESCRIPTION:
XS GIS Cut Line= 4
      3923894.86       9980412.2      3925765.47      9977782.62
       3925760.6      9977719.09      3925628.49      9977128.87
#Sta/Elev= 30
       0   54.98    38.2   56.05   418.6   55.25  1465.4   54.15  1866.7   51.79
  2053.2   52.22  2147.9   50.69    2427   51.25  2483.6   48.18  2492.2    44.7
  2513.1   49.57  2541.7   49.61  2584.4    52.6  2634.9   51.51  2771.4   55.02
  2878.4   52.19  3008.1   54.25    3187      53  3216.5   54.17  3222.7   55.72
  3224.9    51.1  3230.3    51.1  3238.6   44.88  3262.5   42.22  3278.7   53.93
  3287.3    57.9  3309.2   53.42  3391.2      53    3693   52.28  3895.6    55.8
#Mann= 4 ,-1 , 0
       0     .17       0   418.6    .125       0  3230.3     .06       0
  3278.7     .11       0
#XS Ineff= 2 , 0
         2584.86   52.58
Permanent Ineff=
       F       F
Bank Sta=3230.3,3278.7
XS Rating Curve= 0 ,0
Exp/Cntr=0.3,0.1

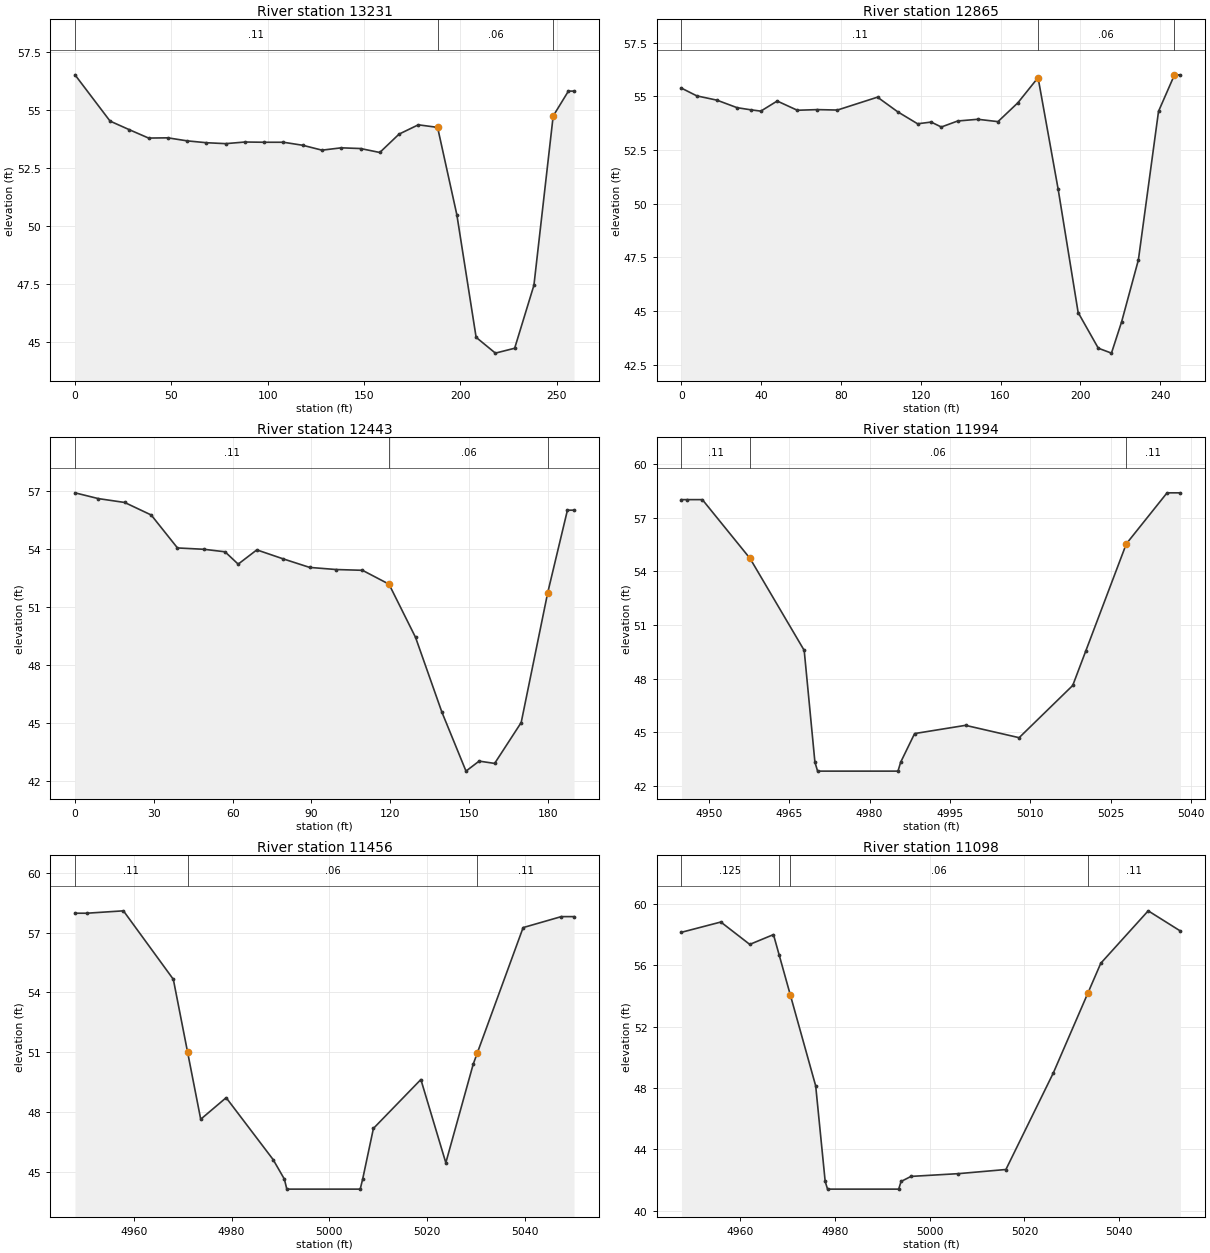
Type RM Length L Ch R = 1 ,13231   ,366,366,366
BEGIN DESCRIPTION:
Mapping XS 44c3e122
END DESCRIPTION:
XS GIS Cut Line= 2
      3926419.35      9978019.25      3926417.94      9977760.22
#Sta/Elev= 27
       0    56.5    18.2   54.51    28.2   54.14    38.2   53.78    48.2   53.79
    58.2   53.66    68.2   53.58    78.2   53.54    88.2   53.61    98.2    53.6
   108.2    53.6   118.2   53.47   128.2   53.26   138.2   53.36   148.2   53.33
   158.2   53.16   168.2   53.95   178.2   54.35   188.2   54.24   198.2   50.48
   208.2   45.21   218.2   44.53   228.2   44.74   238.2   47.45   248.2   54.73
   256.1    55.8     259    55.8
#Mann= 3 , 0 , 0
       0     .11       0   188.2     .06       0   248.2     .11       0
Bank Sta=188.2,248.2
XS Rating Curve= 0 ,0
Exp/Cntr=0.3,0.1

Type RM Length L Ch R = 1 ,12865   ,422,422,422
BEGIN DESCRIPTION:
Mapping XS 2e25e33d
END DESCRIPTION:
XS GIS Cut Line= 2
      3926758.78      9978038.77       3926786.5      9977790.14
#Sta/Elev= 29
       0   55.38     7.7   55.02    17.8   54.82    27.9   54.47    34.8   54.37
    39.8   54.31      48   54.78    58.1   54.35    68.1   54.38    78.2   54.36
    98.3   54.96   108.4   54.28   118.4   53.72   125.2    53.8   130.3   53.57
   138.5   53.85   148.6   53.93   158.7   53.82   168.7    54.7   178.8   55.87
   188.9   50.66   198.9   44.93     209   43.27   215.6   43.04   220.7    44.5
   229.1   47.38   239.2    54.3   247.2      56   250.2      56
#Mann= 3 , 0 , 0
       0     .11       0   178.8     .06       0   247.2     .11       0
Bank Sta=178.8,247.2
XS Rating Curve= 0 ,0
Exp/Cntr=0.3,0.1

Type RM Length L Ch R = 1 ,12443   ,449,449,449
BEGIN DESCRIPTION:
Mapping XS 1b24111f
END DESCRIPTION:
XS GIS Cut Line= 2
      3927186.39      9978009.88      3927206.83      9977821.04
#Sta/Elev= 23
       0   56.93     8.9   56.63    18.9   56.43      29   55.78      39   54.07
    49.1      54    57.1   53.87    62.1   53.23    69.2   53.97    79.3    53.5
    89.3   53.06    99.4   52.95   109.4   52.91   119.5   52.19   129.6   49.43
   139.6   45.56   148.8   42.49   153.8   43.01   159.7   42.89   169.8   45.01
   179.9   51.75   187.4   56.03   189.9   56.03
#Mann= 3 , 0 , 0
       0     .11       0   119.5     .06       0   179.9     .11       0
Bank Sta=119.5,179.9
XS Rating Curve= 0 ,0
Exp/Cntr=0.3,0.1

Type RM Length L Ch R = 1 ,11994   ,538,538,538
BEGIN DESCRIPTION:
Mapping XS 8d52ee8c
END DESCRIPTION:
XS GIS Cut Line= 2
      3927655.79      9977943.88      3927648.79      9977851.05
#Sta/Elev= 17
  4944.9   58.01  4945.9   58.01  4948.8   58.01  4957.7   54.72  4967.8   49.58
  4969.8   43.33  4970.3   42.83  4985.3   42.83  4985.8   43.33  4988.4   44.93
  4997.9   45.39  5007.9    44.7  5017.9   47.62 5020.3649.56829  5027.9   55.54
  5035.5   58.39    5038   58.39
#Mann= 3 , 0 , 0
  4944.9     .11       0  4957.7     .06       0  5027.9     .11       0
Bank Sta=4957.7,5027.9
XS Rating Curve= 0 ,0
Exp/Cntr=0.3,0.1

Type RM Length L Ch R = 1 ,11456   ,358,358,358
BEGIN DESCRIPTION:
Mapping XS d8a44b22
END DESCRIPTION:
XS GIS Cut Line= 2
      3928198.22      9977980.76      3928177.38      9977880.91
#Sta/Elev= 20
    4948   57.97  4950.4   57.97  4957.9   58.09  4968.1   54.66    497151.03001
  4973.7   47.65  4978.9   48.73  4988.5   45.63  4990.8   44.65  4991.3   44.15
  5006.3   44.15  5006.8   44.65    5009   47.19  5018.7   49.64  5023.8   45.47
  5029.4   50.41 5030.2450.97351  5039.6   57.25  5047.4    57.8    5050    57.8
#Mann= 3 , 0 , 0
    4948     .11       0    4971     .06       0 5030.24     .11       0
Bank Sta=4971,5030.24
XS Rating Curve= 0 ,0
Exp/Cntr=0.3,0.1

Type RM Length L Ch R = 1 ,11098   ,598,598,598
BEGIN DESCRIPTION:
G103-15-00 22.0
END DESCRIPTION:
XS GIS Cut Line= 2
      3928541.97      9978009.35      3928547.95      9977904.32
#Sta/Elev= 19
  4947.7   58.15    4956   58.82  4962.1   57.36  4967.1      58  4968.3   56.67
 4970.6554.06359    4976   48.13    4978    41.9  4978.5    41.4  4993.5    41.4
    4994    41.9  4996.1   42.23  5006.1   42.41  5016.1   42.68  5026.1   48.98
 5033.4154.20669  5036.1   56.13  5046.1   59.55  5052.9   58.23
#Mann= 4 ,-1 , 0
  4947.7    .125       0  4968.3     .11       0 4970.65     .06       0
 5033.41     .11       0
Bank Sta=4970.65,5033.41
XS Rating Curve= 0 ,0
Exp/Cntr=0.3,0.1