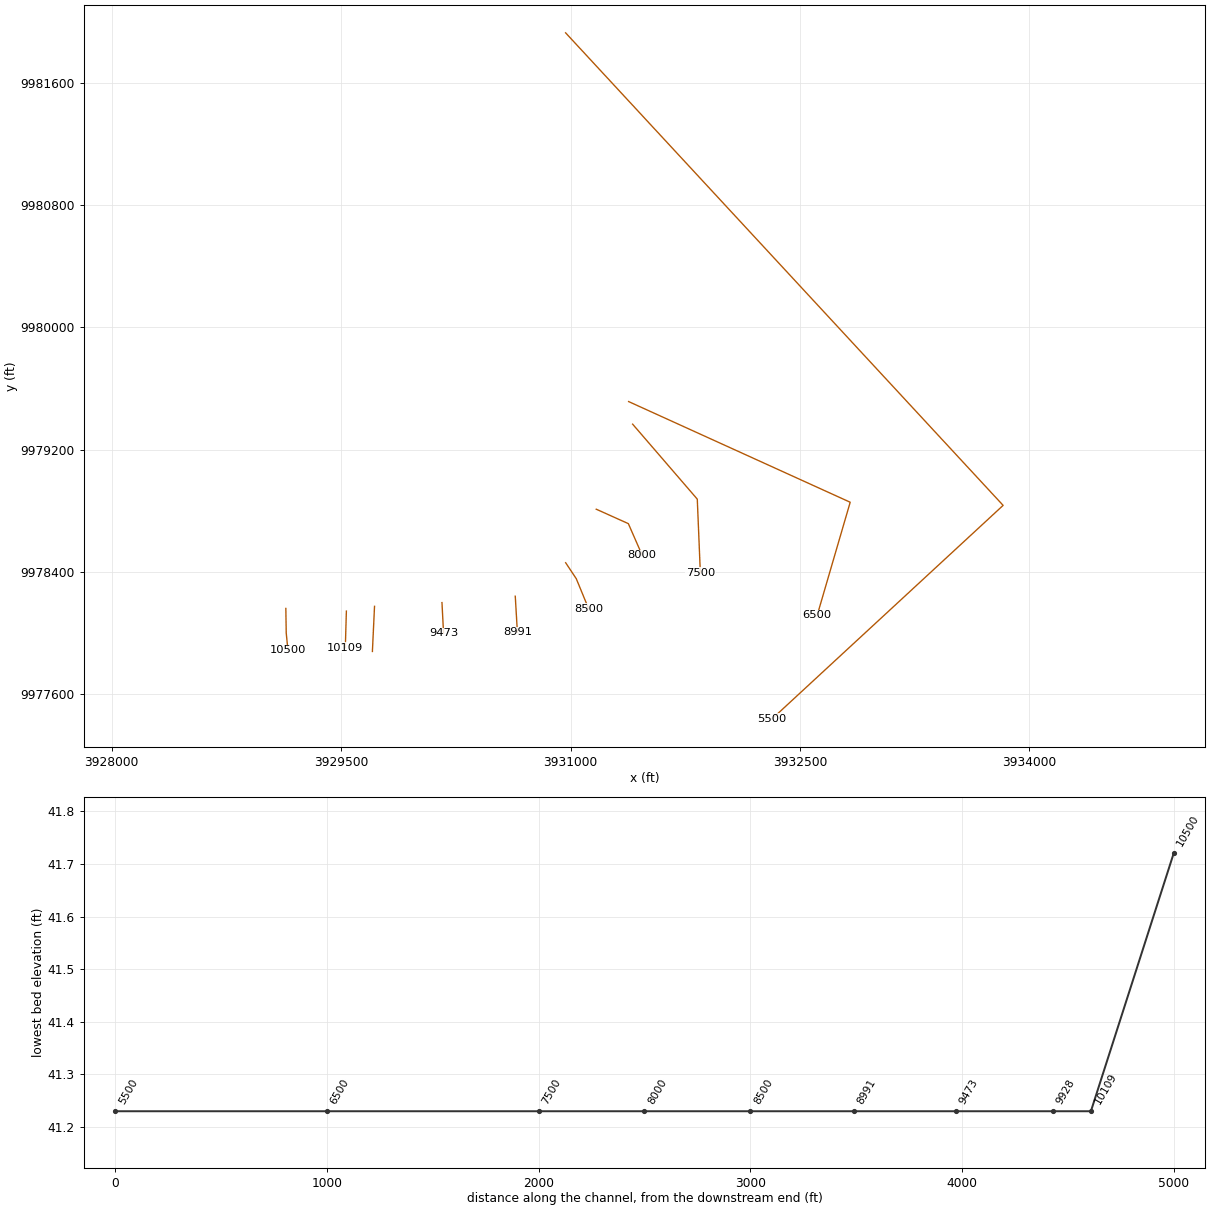
HEC-RAS study G103 15 00.prj: G103 15 00 Base Level Engineering

--- G103 15 00.g01 (geometry) --- (continued)

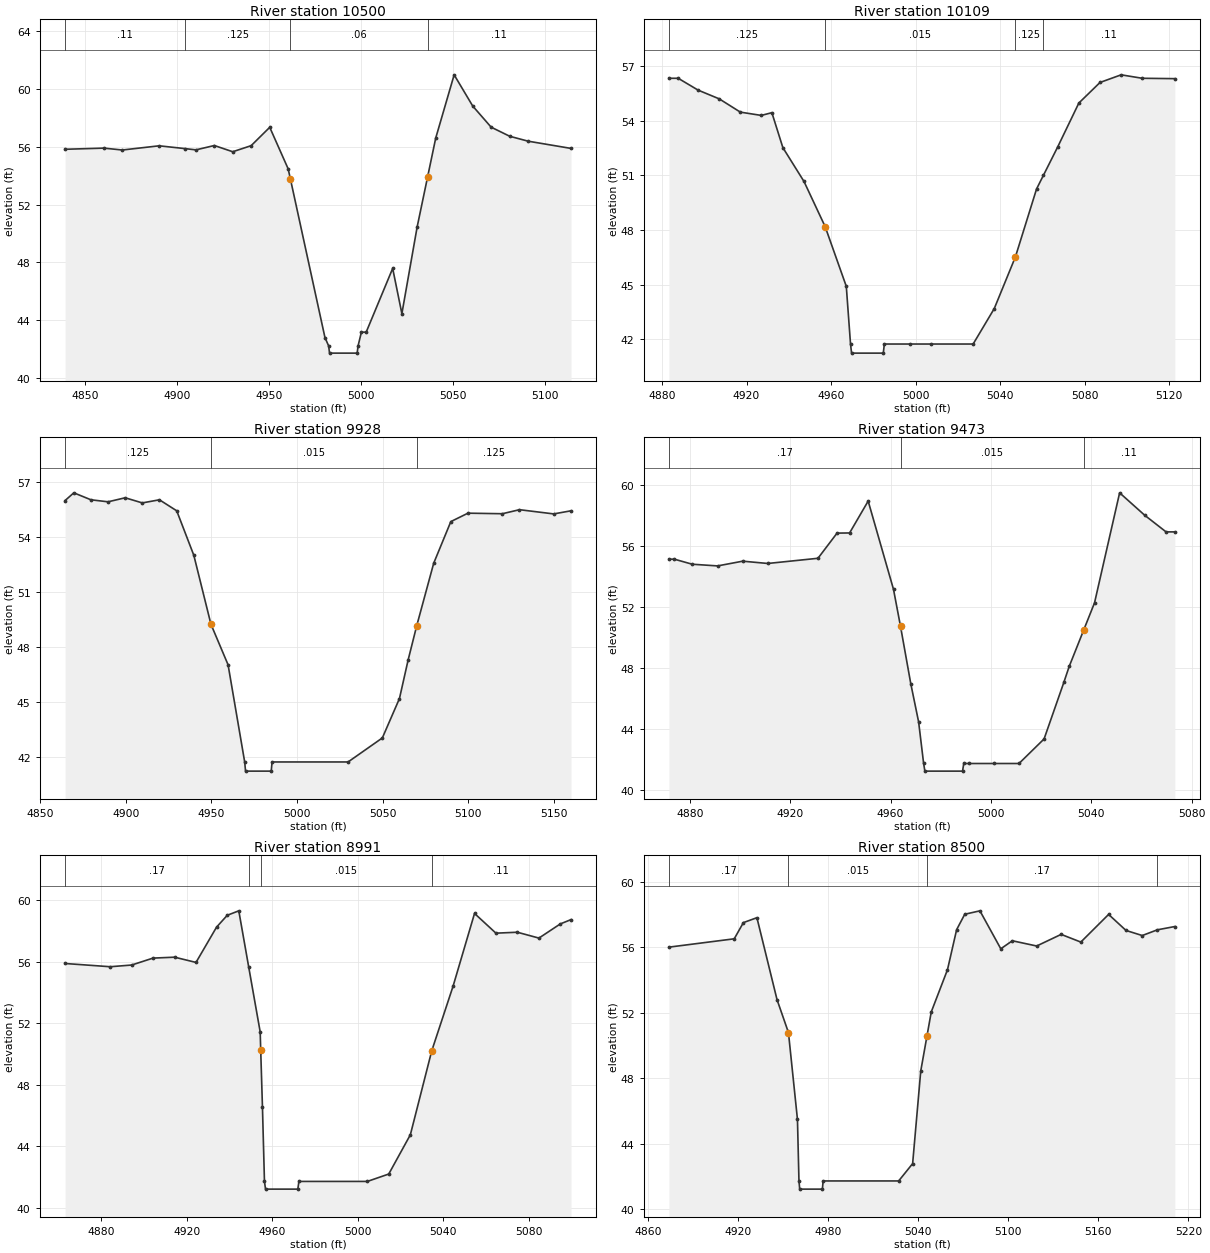
Type RM Length L Ch R = 1 ,10500   ,391,391,391
BEGIN DESCRIPTION:
G103-15-00 21.0
END DESCRIPTION:
XS GIS Cut Line= 3
      3929138.43      9978162.21      3929140.99      9978001.23
      3929152.32      9977887.89
#Sta/Elev= 30
    4839   55.82  4860.1    55.9  4870.1   55.77  4890.1   56.06  4903.9   55.87
  4910.1   55.78  4920.1   56.08  4930.1   55.65  4940.1   56.07  4950.2   57.34
  4960.2   54.47 4961.4753.74228  4980.2    42.8  4982.2   42.22  4982.7   41.72
  4997.7   41.72  4998.2   42.22    5000   43.17  5002.6   43.17    5017   47.58
    5022   44.45  5030.3   50.45 5035.9953.91493  5040.4    56.6  5050.4   60.97
  5060.5   58.81  5070.5   57.35  5080.6   56.72  5090.6   56.38  5113.9   55.88
#Mann= 4 ,-1 , 0
    4839     .11       0  4903.9    .125       0 4961.47     .06       0
 5035.99     .11       0
Bank Sta=4961.47,5035.99
XS Rating Curve= 0 ,0
Exp/Cntr=0.3,0.1

Type RM Length L Ch R = 1 ,10109   ,181,181,181
BEGIN DESCRIPTION:
Mapping XS 2a72cbb3
END DESCRIPTION:
XS GIS Cut Line= 2
      3929534.26      9978144.91      3929527.33      9977905.71
#Sta/Elev= 28
  4883.3   56.33  4887.7   56.33  4897.1   55.68  4907.1    55.2  4917.1   54.47
    4927   54.29    4932   54.44  4937.2   52.52  4947.2   50.66  4957.2   48.18
  4967.2    44.9  4969.2   41.73  4969.7   41.23  4984.7   41.23  4985.2   41.73
  4997.2   41.73  5007.2   41.73  5027.2   41.73  5037.2   43.68  5047.2   46.52
  5057.2   50.25  5060.4   50.99  5067.2   52.56  5077.2   54.97  5087.2    56.1
  5097.2   56.52  5107.2   56.33  5122.6   56.31
#Mann= 4 ,-1 , 0
  4883.3    .125       0  4957.2    .015       0  5047.2    .125       0
  5060.4     .11       0
Bank Sta=4957.2,5047.2
XS Rating Curve= 0 ,0
Exp/Cntr=0.3,0.1

Type RM Length L Ch R = 1 ,9928    ,455,455,455
BEGIN DESCRIPTION:
Mapping XS de21172f
END DESCRIPTION:
XS GIS Cut Line= 2
      3929718.29      9978176.16       3929704.4      9977880.98
#Sta/Elev= 27
  4864.5   55.99  4869.6   56.41  4879.6   56.03  4889.6   55.92  4899.6   56.14
  4909.6   55.86  4919.6   56.03  4929.7   55.43  4939.7      53  4949.7   49.24
  4959.7   47.03  4969.4   41.73  4969.9   41.23  4984.9   41.23  4985.4   41.73
  5029.8   41.73  5049.8   43.04  5059.8   45.19 5064.86   47.29  5069.8   49.13
  5079.8   52.57  5089.8   54.84  5099.8    55.3  5119.9   55.27  5129.9   55.49
  5149.9   55.26    5160   55.43
#Mann= 3 , 0 , 0
  4864.5    .125       0  4949.7    .015       0  5069.8    .125       0
Bank Sta=4949.7,5069.8
XS Rating Curve= 0 ,0
Exp/Cntr=0.3,0.1

Type RM Length L Ch R = 1 ,9473    ,482,482,482
BEGIN DESCRIPTION:
Mapping XS 734093c5
END DESCRIPTION:
XS GIS Cut Line= 2
      3930159.26       9978200.4      3930169.67      9977999.07
#Sta/Elev= 30
  4871.7   55.12  4873.9   55.12    4881   54.79  4891.1   54.68  4901.1   54.99
  4911.1   54.84  4931.1   55.18  4938.7   56.83  4943.7   56.84  4951.1   58.93
  4961.2   53.14    496450.70977 4968.09   46.95  4971.2   44.46  4973.2   41.73
  4973.7   41.23  4988.7   41.23  4989.2   41.73  4991.2   41.73  5001.2   41.73
  5011.2   41.73  5021.2   43.34 5029.08   47.05  5031.2   48.09    503750.48466
  5041.3   52.26  5051.3   59.47  5061.3      58  5069.8   56.91  5073.3   56.91
#Mann= 3 , 0 , 0
  4871.7     .17       0    4964    .015       0    5037     .11       0
Bank Sta=4964,5037
XS Rating Curve= 0 ,0
Exp/Cntr=0.3,0.1

Type RM Length L Ch R = 1 ,8991    ,491,491,491
BEGIN DESCRIPTION:
Mapping XS 46a42644
END DESCRIPTION:
XS GIS Cut Line= 2
      3930638.42      9978242.15      3930652.31      9978006.06
#Sta/Elev= 28
  4863.2   55.88  4884.3   55.67  4894.3   55.78  4904.3   56.23  4914.4   56.29
  4924.4   55.95    4934   58.24    4939   59.01  4944.4    59.3    4949   55.68
  4954.4   51.44 4954.6450.27366 4955.46   46.56  4956.4   41.73  4956.9   41.23
    4972   41.23  4972.5   41.73  5004.5   41.73  5014.5   42.21  5024.6   44.76
  5034.6   50.21  5044.6   54.42  5054.6   59.13  5064.6   57.85  5074.6   57.91
  5084.7   57.53  5094.7   58.45  5099.7   58.73
#Mann= 4 ,-1 , 0
  4863.2     .17       0    4949     .11       0 4954.64    .015       0
  5034.6     .11       0
Bank Sta=4954.64,5034.6
XS Rating Curve= 0 ,0
Exp/Cntr=0.3,0.1

Type RM Length L Ch R = 1 ,8500    ,500,500,500
BEGIN DESCRIPTION:
G103-15-00 17.0
END DESCRIPTION:
XS GIS Cut Line= 3
      3930967.88      9978461.03      3931037.55      9978356.17
      3931117.86      9978161.05
#Sta/Elev= 30
  4874.1   56.02  4917.6   56.53  4923.7   57.52  4932.7   57.82  4946.1   52.81
  4953.7    50.8  4959.7   45.49  4960.7   41.73  4961.2   41.23  4976.3   41.23
  4976.8   41.73  5027.1   41.73  5036.4   42.79  5041.8   48.45    5046 50.6161
  5048.8   52.06  5059.6   54.64  5065.7   57.09  5071.1   58.03  5081.2   58.24
  5095.1   55.92  5102.8   56.41    5119   56.09  5135.3    56.8  5148.4   56.33
  5166.9   58.02  5178.5   57.04  5189.3   56.73  5199.4   57.08    5211   57.28
#Mann= 4 ,-1 , 0
  4874.1     .17       0  4953.7    .015       0    5046     .17       0
  5199.4     .11       0
Bank Sta=4953.7,5046
XS Rating Curve= 0 ,0
Exp/Cntr=0.3,0.1

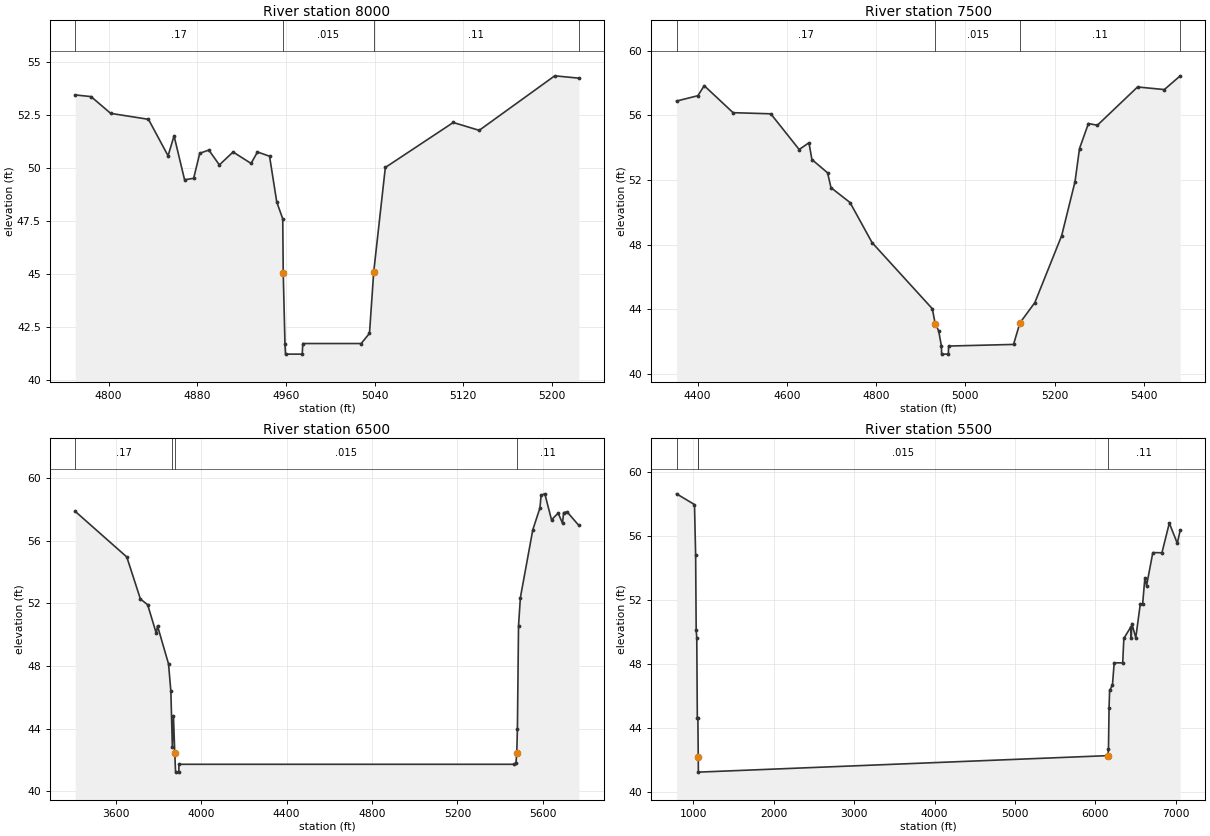
Type RM Length L Ch R = 1 ,8000    ,500,500,500
BEGIN DESCRIPTION:
G103-15-00 16.0
END DESCRIPTION:
XS GIS Cut Line= 3
      3931167.87      9978811.06      3931377.81      9978716.63
      3931467.85      9978511.08
#Sta/Elev= 30
  4769.8   53.45  4784.1   53.37  4801.8   52.58  4835.9    52.3  4853.6   50.58
    4859   51.52  4868.5   49.45  4876.7   49.52  4882.2    50.7  4890.4   50.85
  4899.9   50.15  4912.3   50.76  4928.5   50.22  4934.3   50.76  4945.2   50.56
  4951.7    48.4  4957.1   47.61 4957.55   45.05  4959.1   41.73  4959.6   41.23
  4974.7   41.23  4975.2   41.73  5027.9   41.73  5035.4   42.21 5039.22   45.11
  5049.7   50.03    5111   52.15  5134.4   51.78  5202.6   54.35  5224.4   54.24
#Mann= 4 ,-1 , 0
  4769.8     .17       0 4957.55    .015       0 5039.22     .11       0
  5224.4     .17       0
Bank Sta=4957.55,5039.22
XS Rating Curve= 0 ,0
Exp/Cntr=0.3,0.1

Type RM Length L Ch R = 1 ,7500    ,1000,1000,1000
BEGIN DESCRIPTION:
G103-15-00 15.0
END DESCRIPTION:
XS GIS Cut Line= 3
       3931405.8      9979367.09      3931828.48      9978876.84
      3931848.47      9978395.46
#Sta/Elev= 30
  4352.7   56.89  4400.5   57.22  4414.7   57.84  4479.4   56.17  4563.9    56.1
  4627.6   53.89  4649.5   54.31  4656.1   53.27  4691.2   52.45  4698.9   51.53
  4741.6   50.61    4791   48.13    4926   44.04  4932.6    43.1  4940.2   42.68
  4946.4   41.73  4946.9   41.23    4962   41.23  4962.5   41.73  5108.1   41.83
 5122.39   43.16  5155.9   44.42    5216   48.56    5246   51.91    5256   53.95
    5276    55.5    5296   55.39  5386.1   57.76  5446.2    57.6  5481.8   58.45
#Mann= 4 ,-1 , 0
  4352.7     .17       0  4932.6    .015       0 5122.39     .11       0
  5481.8    .125       0
Bank Sta=4932.6,5122.39
XS Rating Curve= 0 ,0
Exp/Cntr=0.3,0.1

Type RM Length L Ch R = 1 ,6500    ,1000,1000,1000
BEGIN DESCRIPTION:
G103-15-00 13.0
END DESCRIPTION:
XS GIS Cut Line= 3
      3931379.78      9979514.66      3932828.27      9978856.53
      3932612.61      9978117.87
#Sta/Elev= 30
    3409   57.87  3650.7   54.96  3714.4   52.28  3748.5   51.91  3789.1   50.08
  3794.6   50.56  3846.2   48.14  3857.2    46.4  3864.2   42.83  3869.3   44.83
 3875.56   42.44  3879.3   41.23  3894.5   41.23    3895   41.73  5464.1   41.73
  5474.5   41.81 5478.38   42.46  5481.4   44.01  5486.6   50.56  5495.3   52.37
  5553.6    56.7    5587   58.09  5592.3    58.9  5609.9   58.99  5641.2   57.33
  5672.4   57.76  5692.7   57.11  5697.9   57.79  5714.1   57.84  5769.5   56.97
#Mann= 4 ,-1 , 0
    3409     .17       0  3864.2     .11       0 3875.56    .015       0
 5478.38     .11       0
Bank Sta=3875.56,5478.38
XS Rating Curve= 0 ,0
Exp/Cntr=0.3,0.1

Type RM Length L Ch R = 1 ,5500    ,0,0,0
BEGIN DESCRIPTION:
G103-15-00 11.0
END DESCRIPTION:
XS GIS Cut Line= 3
      3930967.44      9981925.67      3933828.06      9978836.01
      3932317.27      9977440.04
#Sta/Elev= 30
   789.4   58.61  1012.5   57.94  1026.7   54.77  1033.5   50.09  1040.9   49.61
  1047.7   44.63  1054.6    44.6  1059.4   42.17  1060.6   41.23  6157.4   42.26
  6164.2   42.69  6171.2   45.23  6178.4   46.33  6213.5   46.66  6235.1   48.06
  6341.1   48.05  6355.3   49.58  6440.3   50.28  6447.1   49.59  6454.5   50.51
  6503.8   49.62  6560.5   51.75  6588.9    51.7  6617.2   53.37  6638.2   52.88
  6715.9   54.94  6829.3   54.93  6921.2   56.78  7020.4   55.52    7057   56.35
#Mann= 4 ,-1 , 0
   789.4     .17       0  1054.6     .08       0  1059.4    .015       0
  6157.4     .11       0
Bank Sta=1059.4,6157.4
XS Rating Curve= 0 ,0
Exp/Cntr=0.3,0.1

Chan Stop Cuts=-1
Use User Specified Reach Order=0
Composite Channel Slope=5