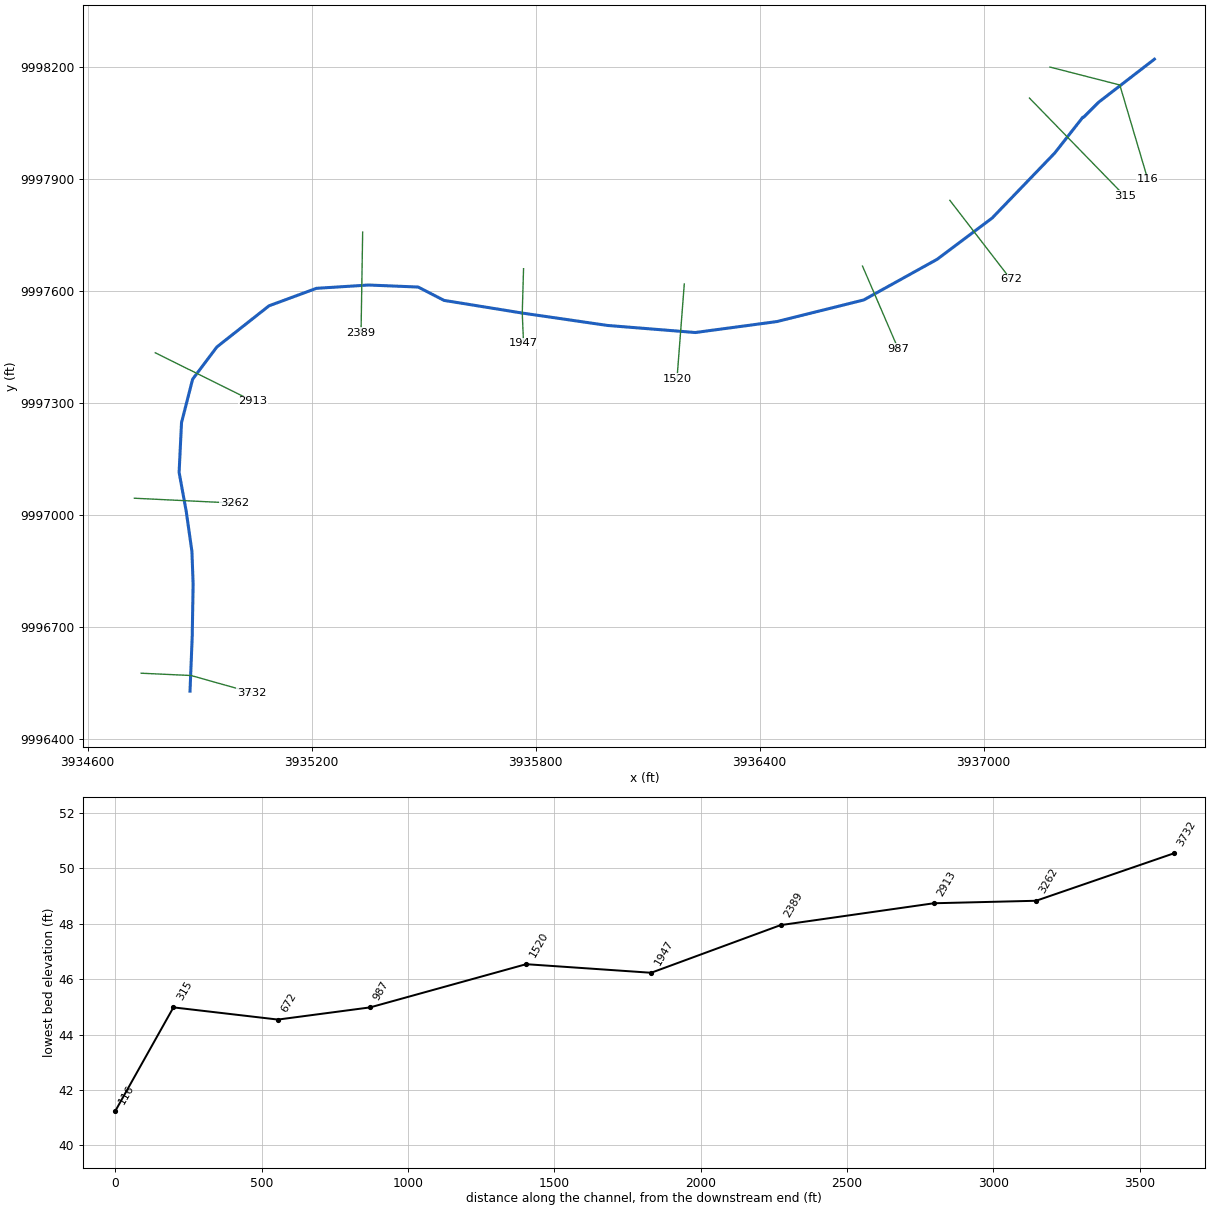
--- G103 24 02.prj (project) ---

Proj Title=G103 24 02 Base Level Engineering
Current Plan=p01
Default Exp/Contr=0.3,0.1
English Units
Geom File=g01
Flow File=f01
Flow File=f02
Plan File=p01
Y Axis Title=Elevation
X Axis Title(PF)=Main Channel Distance
X Axis Title(XS)=Station
BEGIN DESCRIPTION:
G103 24 02
END DESCRIPTION:
DSS Export Rating Curves= 0
DSS Export Rating Curve Sorted= 0
DSS Export Volume Flow Curves= 0
DXF OffsetX= 0
DXF OffsetY= 0
DXF ScaleX= 1
DXF ScaleY= 10

--- G103 24 02.p01 (plan) ---

Plan Title=Multiple Run
Short Identifier=Multiple
Geom File=g01
Flow File=f01
Subcritical Flow
K Sum by GR= 0
Std Step Tol= 0.01
Critical Tol= 0.01
Num of Std Step Trials= 20
Max Error Tol= 0.3
Flow Tol Ratio= 0.001
Split Flow NTrial= 30
Split Flow Tol= 0.02
Split Flow Ratio= 0.02
Log Output Level= 0
Friction Slope Method= 1
Unsteady Friction Slope Method= 2
Unsteady Bridges Friction Slope Method= 1
Parabolic Critical Depth
Global Vel Dist=  1 , 1 , 1
Global Log Level= 0
CheckData=True
Encroach Param= -1, 0, 0, 0
BEGIN DESCRIPTION:
Multiple Run
END DESCRIPTION:

--- G103 24 02.f01 (steady flow) ---

Flow Title=Multiple
Program Version=4.10
Number of Profiles= 7
Profile Names=10-year,25-year,50-year,1pct_min,100-year,1pct_plu,500-year
River Rch & RM=G103 24 02,Reach-1         ,3732
     212     261     332     140     423    1277     703
River Rch & RM=G103 24 02,Reach-1         ,116
     845    1119    1492     653    1972    5955    3583
Boundary for River Rch & Prof#=G103 24 02,Reach-1         , 1
Up Type= 0
Dn Type= 3
Dn Slope=0.005
Boundary for River Rch & Prof#=G103 24 02,Reach-1         , 2
Up Type= 0
Dn Type= 3
Dn Slope=0.005
Boundary for River Rch & Prof#=G103 24 02,Reach-1         , 3
Up Type= 0
Dn Type= 3
Dn Slope=0.005
Boundary for River Rch & Prof#=G103 24 02,Reach-1         , 4
Up Type= 0
Dn Type= 3
Dn Slope=0.005
Boundary for River Rch & Prof#=G103 24 02,Reach-1         , 5
Up Type= 0
Dn Type= 3
Dn Slope=0.005
Boundary for River Rch & Prof#=G103 24 02,Reach-1         , 6
Up Type= 0
Dn Type= 3
Dn Slope=0.005
Boundary for River Rch & Prof#=G103 24 02,Reach-1         , 7
Up Type= 0
Dn Type= 3
Dn Slope=0.005
DSS Import GetInterval= 0
DSS Import GetPeak= 0
DSS Import FillOption= 0

--- G103 24 02.f02 (steady flow) ---

Flow Title=Orig_BLE_Flows
Program Version=4.10
Number of Profiles= 7
Profile Names=10-year,25-year,50-year,1pct_min,100-year,1pct_plu,500-year
River Rch & RM=G103 24 02,Reach-1         ,3732
     212     256     289     107     325     980     409
River Rch & RM=G103 24 02,Reach-1         ,116
     845    1097    1297     502    1517    4582    2083
Boundary for River Rch & Prof#=G103 24 02,Reach-1         , 1
Up Type= 0
Dn Type= 3
Dn Slope=0.005
Boundary for River Rch & Prof#=G103 24 02,Reach-1         , 2
Up Type= 0
Dn Type= 3
Dn Slope=0.005
Boundary for River Rch & Prof#=G103 24 02,Reach-1         , 3
Up Type= 0
Dn Type= 3
Dn Slope=0.005
Boundary for River Rch & Prof#=G103 24 02,Reach-1         , 4
Up Type= 0
Dn Type= 3
Dn Slope=0.005
Boundary for River Rch & Prof#=G103 24 02,Reach-1         , 5
Up Type= 0
Dn Type= 3
Dn Slope=0.005
Boundary for River Rch & Prof#=G103 24 02,Reach-1         , 6
Up Type= 0
Dn Type= 3
Dn Slope=0.005
Boundary for River Rch & Prof#=G103 24 02,Reach-1         , 7
Up Type= 0
Dn Type= 3
Dn Slope=0.005
DSS Import GetInterval= 0
DSS Import GetPeak= 0
DSS Import FillOption= 0

--- G103 24 02.g01 (geometry) ---

Geom Title=Existing Conditions
Program Version=4.10

River Reach=G103 24 02      ,Reach-1
Reach XY= 26
      3934874.38      9996529.42      3934880.31      9996676.44
      3934882.71      9996816.34      3934879.49      9996903.59
      3934864.16      9997011.35      3934845.17      9997115.48
      3934851.62      9997248.54      3934881.38      9997365.02
      3934946.33      9997451.39       3935086.1      9997561.61
      3935213.07      9997608.41       3935352.8      9997617.27
      3935485.48      9997611.87      3935554.94      9997576.09
      3935764.38      9997542.17      3935992.72      9997508.99
       3936228.1      9997490.05      3936446.57       9997519.4
      3936679.12      9997577.24      3936875.72      9997686.14
      3937023.05      9997796.64      3937190.74      9997970.83
      3937266.13      9998066.84      3937268.23      9998066.84
      3937308.23      9998106.84      3937457.79      9998222.23

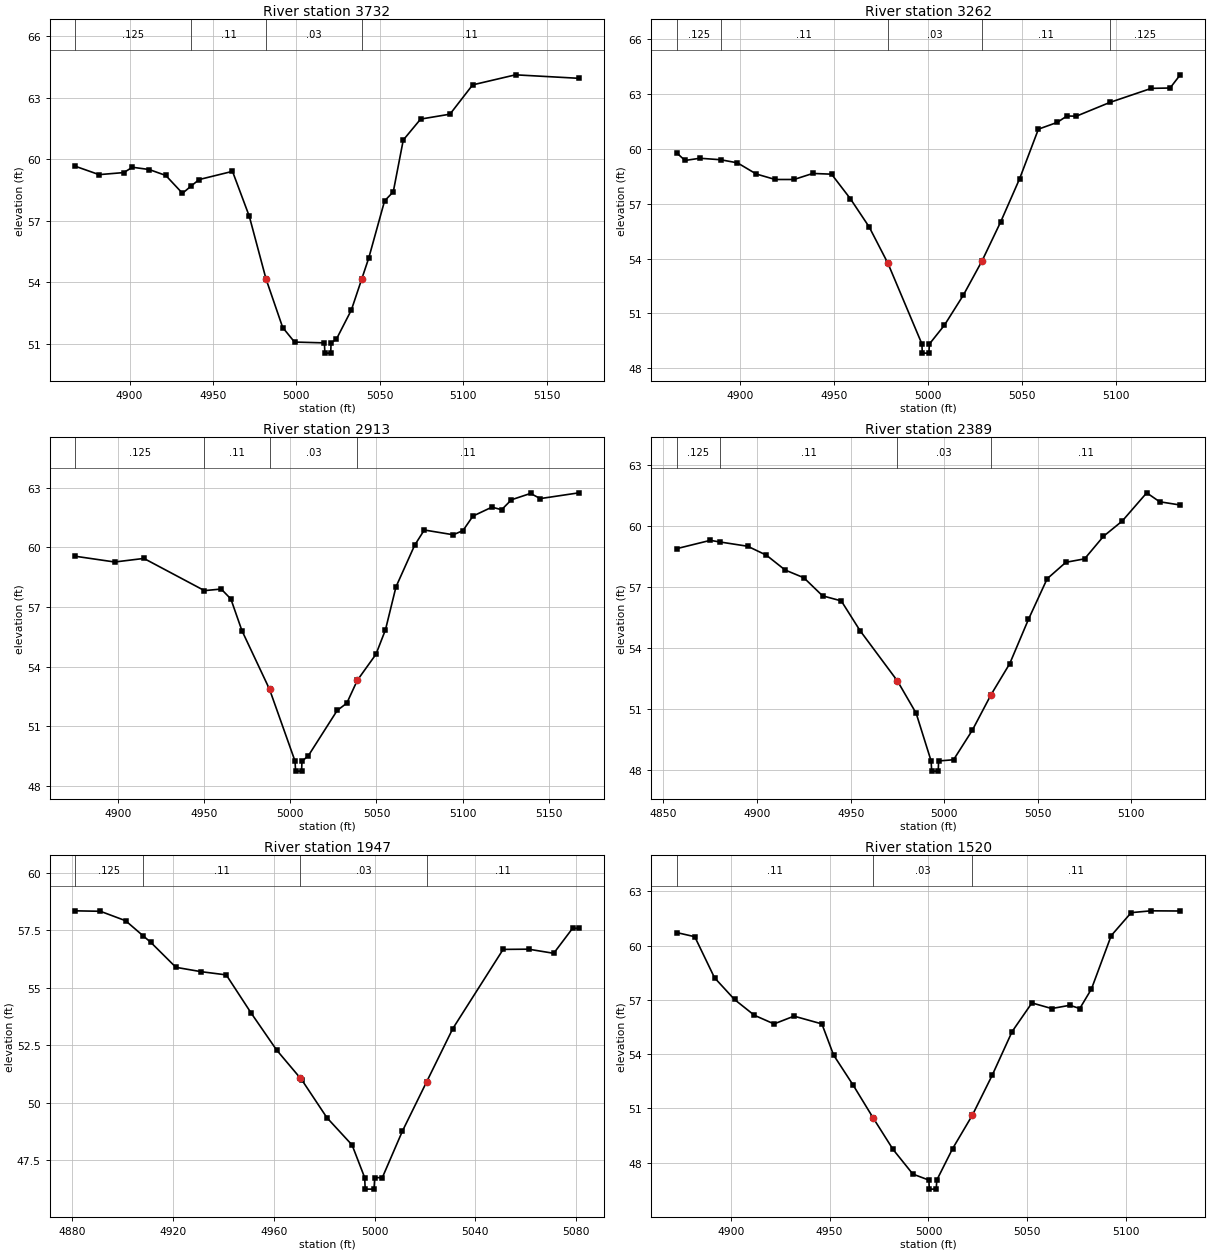
Type RM Length L Ch R = 1 ,3732    ,470,470,470
BEGIN DESCRIPTION:
G103-24-02 7.0
END DESCRIPTION:
XS GIS Cut Line= 3
      3934743.61       9996577.4      3934877.18      9996571.25
      3935039.19      9996525.69
#Sta/Elev= 30
  4867.4   59.66  4881.7   59.25  4896.5   59.35  4901.7   59.61  4911.7    59.5
  4921.7   59.21  4931.7   58.34    4937    58.7  4941.7   59.01  4961.7   59.41
  4971.8   57.21  4981.8   54.16  4991.8   51.79  4998.9   51.08  5016.8   51.04
  5017.1   50.54  5020.6   50.54  5020.8   51.04    5024   51.22    5033   52.65
  5039.154.13398  5043.4   55.18  5052.9   57.97  5058.1   58.41  5064.1   60.94
  5074.5   61.96  5092.1    62.2  5105.7   63.63  5131.4   64.12  5169.4   63.95
#Mann= 4 ,-1 , 0
  4867.4    .125       0    4937     .11       0  4981.8     .03       0
  5039.1     .11       0
Bank Sta=4981.8,5039.1
XS Rating Curve= 0 ,0
Exp/Cntr=0.3,0.1

Type RM Length L Ch R = 1 ,3262    ,349,349,349
BEGIN DESCRIPTION:
Mapping XS c21b517b
END DESCRIPTION:
XS GIS Cut Line= 2
      3934725.45      9997046.15      3934993.24      9997033.15
#Sta/Elev= 30
  4866.3   59.78  4870.8   59.36  4878.7   59.48  4889.7    59.4  4898.7   59.23
  4908.7   58.62  4918.8   58.32  4928.8   58.32  4938.8   58.65  4948.8   58.61
  4958.8   57.27  4968.8   55.73  4978.8   53.74  4996.9   49.33  4997.1   48.83
  5000.6   48.83  5000.9   49.33  5008.9   50.36  5018.9   51.99  5028.9   53.87
  5038.9   56.02  5048.9   58.36  5058.9   61.07  5068.9   61.44  5074.1   61.79
  5079.1   61.78  5096.9   62.53    5119    63.3    5129   63.32  5134.4   64.04
#Mann= 5 ,-1 , 0
  4866.3    .125       0  4889.7     .11       0  4978.8     .03       0
  5028.9     .11       0  5096.9    .125       0
Bank Sta=4978.8,5028.9
XS Rating Curve= 0 ,0
Exp/Cntr=0.3,0.1

Type RM Length L Ch R = 1 ,2913    ,524,524,524
BEGIN DESCRIPTION:
Mapping XS 1dee1014
END DESCRIPTION:
XS GIS Cut Line= 2
      3934781.33      9997435.77      3935042.85       9997306.1
#Sta/Elev= 30
  4875.4   59.55  4898.3   59.26  4915.2   59.44  4950.3   57.82    4960    57.9
  4965.6    57.4    4972   55.81    4988   52.86  5002.8   49.24  5003.1   48.74
  5006.6   48.74  5006.8   49.24  5010.4    49.5  5027.2   51.79  5032.8   52.16
  5038.9   53.31  5049.7   54.62  5055.2   55.85  5061.3   58.01  5072.1    60.1
  5077.7   60.87  5094.5   60.63  5100.1   60.84  5105.9   61.57  5116.9   62.02
  5122.5   61.89  5128.2   62.39  5139.3   62.71  5144.9   62.45  5167.3   62.74
#Mann= 4 ,-1 , 0
  4875.4    .125       0  4950.3     .11       0    4988     .03       0
  5038.9     .11       0
Bank Sta=4988,5038.9
XS Rating Curve= 0 ,0
Exp/Cntr=0.3,0.1

Type RM Length L Ch R = 1 ,2389    ,442,442,442
BEGIN DESCRIPTION:
Mapping XS dacea489
END DESCRIPTION:
XS GIS Cut Line= 2
      3935336.87      9997759.09      3935332.53      9997490.03
#Sta/Elev= 29
    4857    58.9    4875   59.31  4880.2   59.23    4895   59.02    4905   58.58
    4915   57.85    4925   57.47    4935   56.58    4945   56.33    4955   54.87
    4975   52.39    4985    50.8    4993   48.45  4993.3   47.95  4996.8   47.95
    4997   48.45    5005   48.51    5015   49.96    5025   51.71    5035   53.24
    5045   55.42    5055   57.42    5065   58.23    5075    58.4  5085.1   59.51
  5095.1   60.26  5108.2   61.65  5115.1   61.21  5126.1   61.05
#Mann= 4 ,-1 , 0
    4857    .125       0  4880.2     .11       0    4975     .03       0
    5025     .11       0
Bank Sta=4975,5025
XS Rating Curve= 0 ,0
Exp/Cntr=0.3,0.1

Type RM Length L Ch R = 1 ,1947    ,427,427,427
BEGIN DESCRIPTION:
G103-24-02 4.0
END DESCRIPTION:
XS GIS Cut Line= 3
      3935767.85      9997661.02      3935764.38      9997542.17
      3935767.85      9997461.05
#Sta/Elev= 27
  4881.1   58.35  4891.1   58.33  4901.1   57.92  4908.2   57.25  4911.1   56.98
  4921.1   55.89  4931.1    55.7  4941.1   55.56  4951.1   53.88  4961.1   52.29
 4970.5951.05634  4971.1   50.99  4981.1   49.34  4991.1   48.15  4996.1   46.73
  4996.3   46.23  4999.8   46.23  5000.1   46.73  5003.1   46.73  5011.1   48.76
 5020.7750.91639  5031.1   53.22  5051.1   56.67  5061.2   56.68  5071.2    56.5
  5078.7   57.59  5081.2   57.59
#Mann= 4 ,-1 , 0
  4881.1    .125       0  4908.2     .11       0 4970.59     .03       0
 5020.77     .11       0
Bank Sta=4970.59,5020.77
XS Rating Curve= 0 ,0
Exp/Cntr=0.3,0.1

Type RM Length L Ch R = 1 ,1520    ,533,533,533
BEGIN DESCRIPTION:
Mapping XS 426634bc
END DESCRIPTION:
XS GIS Cut Line= 2
      3936198.42      9997620.25      3936178.89       9997366.3
#Sta/Elev= 30
  4872.6   60.72  4881.8   60.49  4891.8   58.22  4901.9   57.02  4911.9   56.15
  4921.9   55.67    4932    56.1  4946.1   55.67    4952   53.95    4962   52.27
  4972.1   50.46  4982.1   48.73  4992.1   47.37  5000.2   47.04  5000.4   46.54
  5003.9   46.54  5004.2   47.04  5012.2   48.78  5022.2   50.63  5032.2   52.83
  5042.3   55.25  5052.3   56.83  5062.3   56.52  5071.5    56.7  5076.5   56.52
  5082.4    57.6  5092.4   60.55  5102.5   61.82  5112.5   61.92  5127.3   61.91
#Mann= 3 , 0 , 0
  4872.6     .11       0  4972.1     .03       0  5022.2     .11       0
Bank Sta=4972.1,5022.2
XS Rating Curve= 0 ,0
Exp/Cntr=0.3,0.1

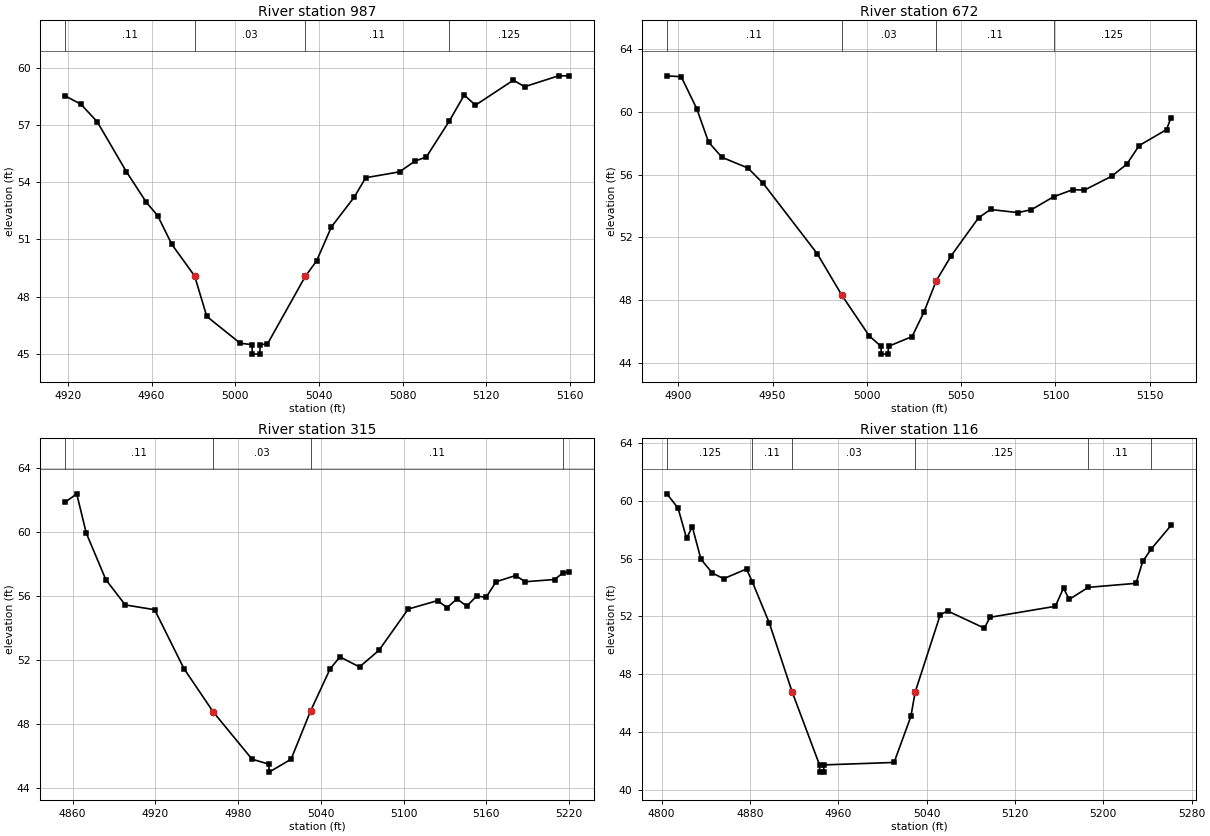
Type RM Length L Ch R = 1 ,987     ,315,315,315
BEGIN DESCRIPTION:
Mapping XS a33b60e8
END DESCRIPTION:
XS GIS Cut Line= 2
      3936675.83      9997668.02      3936771.33      9997446.64
#Sta/Elev= 30
  4918.6   58.54  4926.2    58.1    4934   57.18    4948   54.55  4957.5   52.95
  4962.9   52.25  4969.7   50.74  4980.6   49.08  4986.4   46.96  5002.4   45.55
    5008   45.48  5008.2   44.98  5011.7   44.98    5012   45.48  5015.4   45.51
  5033.5   49.06  5038.9   49.87    5046   51.66  5056.9   53.22  5062.4   54.24
  5078.6   54.55  5085.9   55.11  5091.4   55.33  5102.4   57.22  5109.5   58.58
  5114.9   58.05    5133   59.36  5138.4   59.02  5154.6   59.59  5159.7   59.59
#Mann= 4 ,-1 , 0
  4918.6     .11       0  4980.6     .03       0  5033.5     .11       0
  5102.4    .125       0
Bank Sta=4980.6,5033.5
XS Rating Curve= 0 ,0
Exp/Cntr=0.3,0.1

Type RM Length L Ch R = 1 ,672     ,357,357,357
BEGIN DESCRIPTION:
Mapping XS eedf603e
END DESCRIPTION:
XS GIS Cut Line= 2
       3936909.8      9997844.19      3937072.94      9997632.45
#Sta/Elev= 30
    4894    62.3  4901.6   62.24  4909.8   60.21  4916.1   58.07  4923.2    57.1
  4936.9   56.42  4945.1   55.43  4973.7   50.95  4986.8   48.29  5001.3    45.7
  5007.5   45.04  5007.7   44.54  5011.2   44.54  5011.5   45.04    5024   45.66
  5030.3   47.23  5036.8   49.22  5044.8   50.83  5059.3   53.25  5065.6   53.77
  5080.1   53.57  5087.3   53.76  5099.1   54.59  5109.1   55.03  5115.4   55.01
  5129.9    55.9  5137.8   56.66  5144.4   57.85  5158.9   58.87  5161.3   59.64
#Mann= 4 ,-1 , 0
    4894     .11       0  4986.8     .03       0  5036.8     .11       0
  5099.1    .125       0
Bank Sta=4986.8,5036.8
XS Rating Curve= 0 ,0
Exp/Cntr=0.3,0.1

Type RM Length L Ch R = 1 ,315     ,199,199,199
BEGIN DESCRIPTION:
Mapping XS a392bb15
END DESCRIPTION:
XS GIS Cut Line= 2
      3937123.03      9998118.11      3937377.95      9997856.18
#Sta/Elev= 30
  4854.5   61.86    4863   62.39  4869.9   59.94  4884.1   57.02  4898.2   55.44
  4919.5   55.14  4940.7   51.46    4962   48.74  4990.1   45.79  5002.2   45.48
  5002.5   44.98  5018.4   45.79  5032.5    48.8  5046.7   51.44  5053.8   52.19
    5068   51.56  5082.1    52.6  5103.3   55.18  5124.6   55.71  5131.5   55.27
  5138.7   55.82  5145.7   55.36  5152.9   55.99  5159.8   55.92    5167   56.89
  5181.2   57.28  5188.1   56.89  5209.4   57.03  5215.2   57.42    5220    57.5
#Mann= 4 ,-1 , 0
  4854.5     .11       0    4962     .03       0  5032.5     .11       0
  5215.2    .125       0
Bank Sta=4962,5032.5
XS Rating Curve= 0 ,0
Exp/Cntr=0.3,0.1

Type RM Length L Ch R = 1 ,116     ,0,0,0
BEGIN DESCRIPTION:
G103-24-02 1.0
END DESCRIPTION:
XS GIS Cut Line= 3
      3937178.03      9998201.11      3937365.09      9998153.17
      3937439.92      9997900.64
#Sta/Elev= 30
  4804.8   60.48  4814.9   59.49  4822.6   57.41  4827.8    58.2  4835.6   55.96
  4845.9      55  4856.2   54.61  4876.9   55.28  4882.2   54.38  4897.5   51.55
  4918.2   46.78    4943   41.73  4943.2   41.23  4946.7   41.23    4947   41.73
  5010.5    41.9  5025.7   45.08 5029.55  46.755  5052.3   52.11  5058.9   52.38
  5092.2   51.19  5097.4   51.94  5156.5    52.7  5163.9   53.96  5169.1   53.18
  5186.3   54.01  5229.6   54.29  5235.6    55.8  5243.3   56.66  5261.3    58.3
#Mann= 6 ,-1 , 0
  4804.8    .125       0  4882.2     .11       0  4918.2     .03       0
 5029.55    .125       0  5186.3     .11       0  5243.3    .125       0
Bank Sta=4918.2,5029.55
XS Rating Curve= 0 ,0
Exp/Cntr=0.3,0.1

Chan Stop Cuts=-1
Use User Specified Reach Order=0
Composite Channel Slope=5