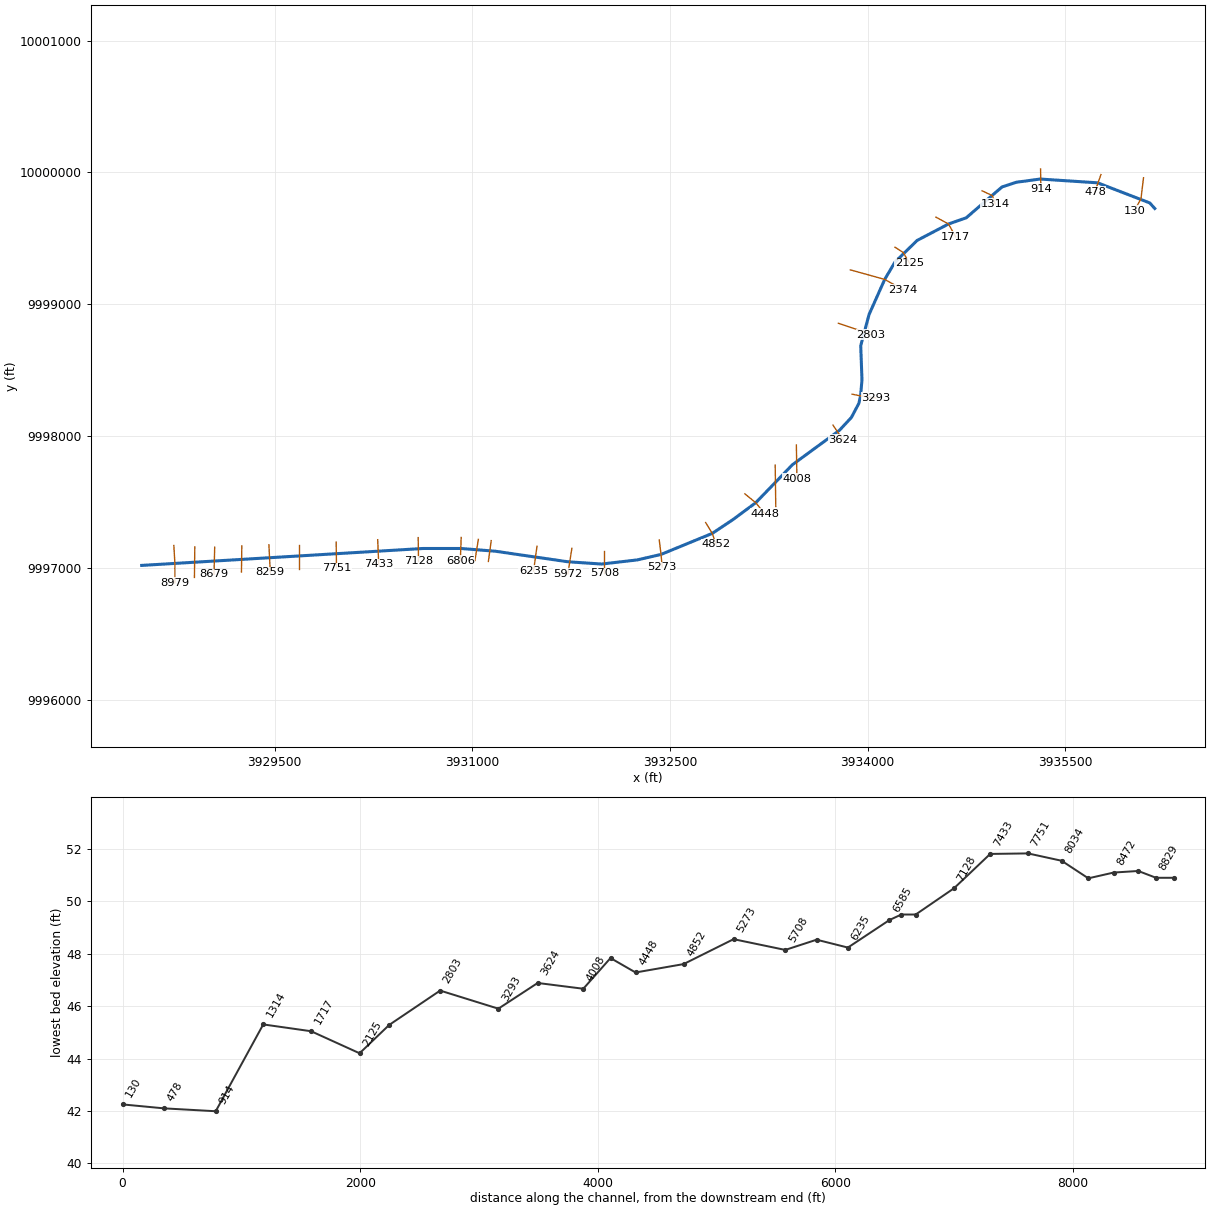
--- G103 24 03.prj (project) ---

Proj Title=G103 24 03 Base Level Engineering
Current Plan=p01
Default Exp/Contr=0.3,0.1
English Units
Geom File=g01
Flow File=f01
Flow File=f02
Plan File=p01
Y Axis Title=Elevation
X Axis Title(PF)=Main Channel Distance
X Axis Title(XS)=Station
BEGIN DESCRIPTION:
G103 24 03
END DESCRIPTION:
DSS Export Rating Curves= 0
DSS Export Rating Curve Sorted= 0
DSS Export Volume Flow Curves= 0
DXF OffsetX= 0
DXF OffsetY= 0
DXF ScaleX= 1
DXF ScaleY= 10

--- G103 24 03.p01 (plan) ---

Plan Title=Multiple Run
Short Identifier=Multiple
Geom File=g01
Flow File=f01
Subcritical Flow
K Sum by GR= 0
Std Step Tol= 0.01
Critical Tol= 0.01
Num of Std Step Trials= 20
Max Error Tol= 0.3
Flow Tol Ratio= 0.001
Split Flow NTrial= 30
Split Flow Tol= 0.02
Split Flow Ratio= 0.02
Log Output Level= 0
Friction Slope Method= 1
Unsteady Friction Slope Method= 2
Unsteady Bridges Friction Slope Method= 1
Parabolic Critical Depth
Global Vel Dist=  1 , 1 , 1
Global Log Level= 0
CheckData=True
Encroach Param= -1, 0, 0, 0
BEGIN DESCRIPTION:
Multiple Run
END DESCRIPTION:

--- G103 24 03.f01 (steady flow) ---

Flow Title=Multiple
Program Version=4.10
Number of Profiles= 7
Profile Names=10-year,25-year,50-year,1pct_min,100-year,1pct_plu,500-year
River Rch & RM=G103 24 03,Reach-1         ,8979
     240     299     382     161     486    1468     817
River Rch & RM=G103 24 03,Reach-1         ,7751
     368     465     600     256     772    2331    1323
River Rch & RM=G103 24 03,Reach-1         ,1314
     410     522     676     289     872    2633    1507
Boundary for River Rch & Prof#=G103 24 03,Reach-1         , 1
Up Type= 0
Dn Type= 3
Dn Slope=0.005
Boundary for River Rch & Prof#=G103 24 03,Reach-1         , 2
Up Type= 0
Dn Type= 3
Dn Slope=0.005
Boundary for River Rch & Prof#=G103 24 03,Reach-1         , 3
Up Type= 0
Dn Type= 3
Dn Slope=0.005
Boundary for River Rch & Prof#=G103 24 03,Reach-1         , 4
Up Type= 0
Dn Type= 3
Dn Slope=0.005
Boundary for River Rch & Prof#=G103 24 03,Reach-1         , 5
Up Type= 0
Dn Type= 3
Dn Slope=0.005
Boundary for River Rch & Prof#=G103 24 03,Reach-1         , 6
Up Type= 0
Dn Type= 3
Dn Slope=0.005
Boundary for River Rch & Prof#=G103 24 03,Reach-1         , 7
Up Type= 0
Dn Type= 3
Dn Slope=0.005
DSS Import GetInterval= 0
DSS Import GetPeak= 0
DSS Import FillOption= 0

--- G103 24 03.f02 (steady flow) ---

Flow Title=Orig_BLE_Flows
Program Version=4.10
Number of Profiles= 7
Profile Names=10-year,25-year,50-year,1pct_min,100-year,1pct_plu,500-year
River Rch & RM=G103 24 03,Reach-1         ,8979
     240     293     332     124     374    1128     475
River Rch & RM=G103 24 03,Reach-1         ,7751
     368     456     522     197     594    1793     769
River Rch & RM=G103 24 03,Reach-1         ,1314
     410     512     588     222     671    2027     876
Boundary for River Rch & Prof#=G103 24 03,Reach-1         , 1
Up Type= 0
Dn Type= 3
Dn Slope=0.005
Boundary for River Rch & Prof#=G103 24 03,Reach-1         , 2
Up Type= 0
Dn Type= 3
Dn Slope=0.005
Boundary for River Rch & Prof#=G103 24 03,Reach-1         , 3
Up Type= 0
Dn Type= 3
Dn Slope=0.005
Boundary for River Rch & Prof#=G103 24 03,Reach-1         , 4
Up Type= 0
Dn Type= 3
Dn Slope=0.005
Boundary for River Rch & Prof#=G103 24 03,Reach-1         , 5
Up Type= 0
Dn Type= 3
Dn Slope=0.005
Boundary for River Rch & Prof#=G103 24 03,Reach-1         , 6
Up Type= 0
Dn Type= 3
Dn Slope=0.005
Boundary for River Rch & Prof#=G103 24 03,Reach-1         , 7
Up Type= 0
Dn Type= 3
Dn Slope=0.005
DSS Import GetInterval= 0
DSS Import GetPeak= 0
DSS Import FillOption= 0

--- G103 24 03.g01 (geometry) ---

Geom Title=Existing Conditions
Program Version=4.10

River Reach=G103 24 03      ,Reach-1
Reach XY= 30
      3928490.51      9997017.93      3930625.92       9997146.4
      3930914.12       9997146.4      3931174.54      9997125.57
      3931723.15      9997045.71      3931980.09      9997028.35
      3932250.92       9997059.6      3932431.48      9997101.26
      3932820.37      9997260.99      3932976.62      9997365.15
      3933150.23      9997493.63      3933428.23      9997781.84
      3933785.12      9998042.98      3933876.14      9998140.83
      3933932.76      9998247.86      3933945.81      9998304.28
      3933956.42      9998427.01      3933946.89      9998685.28
      3934010.07      9998921.87      3934128.92      9999188.56
      3934207.32      9999320.88       3934375.4       9999484.6
      3934613.06      9999609.05      3934747.59      9999656.15
      3935019.07      9999890.24      3935127.52      9999925.85
      3935308.32      9999950.26      3935744.69      9999921.55
      3936140.21      9999768.95      3936178.23      9999726.84

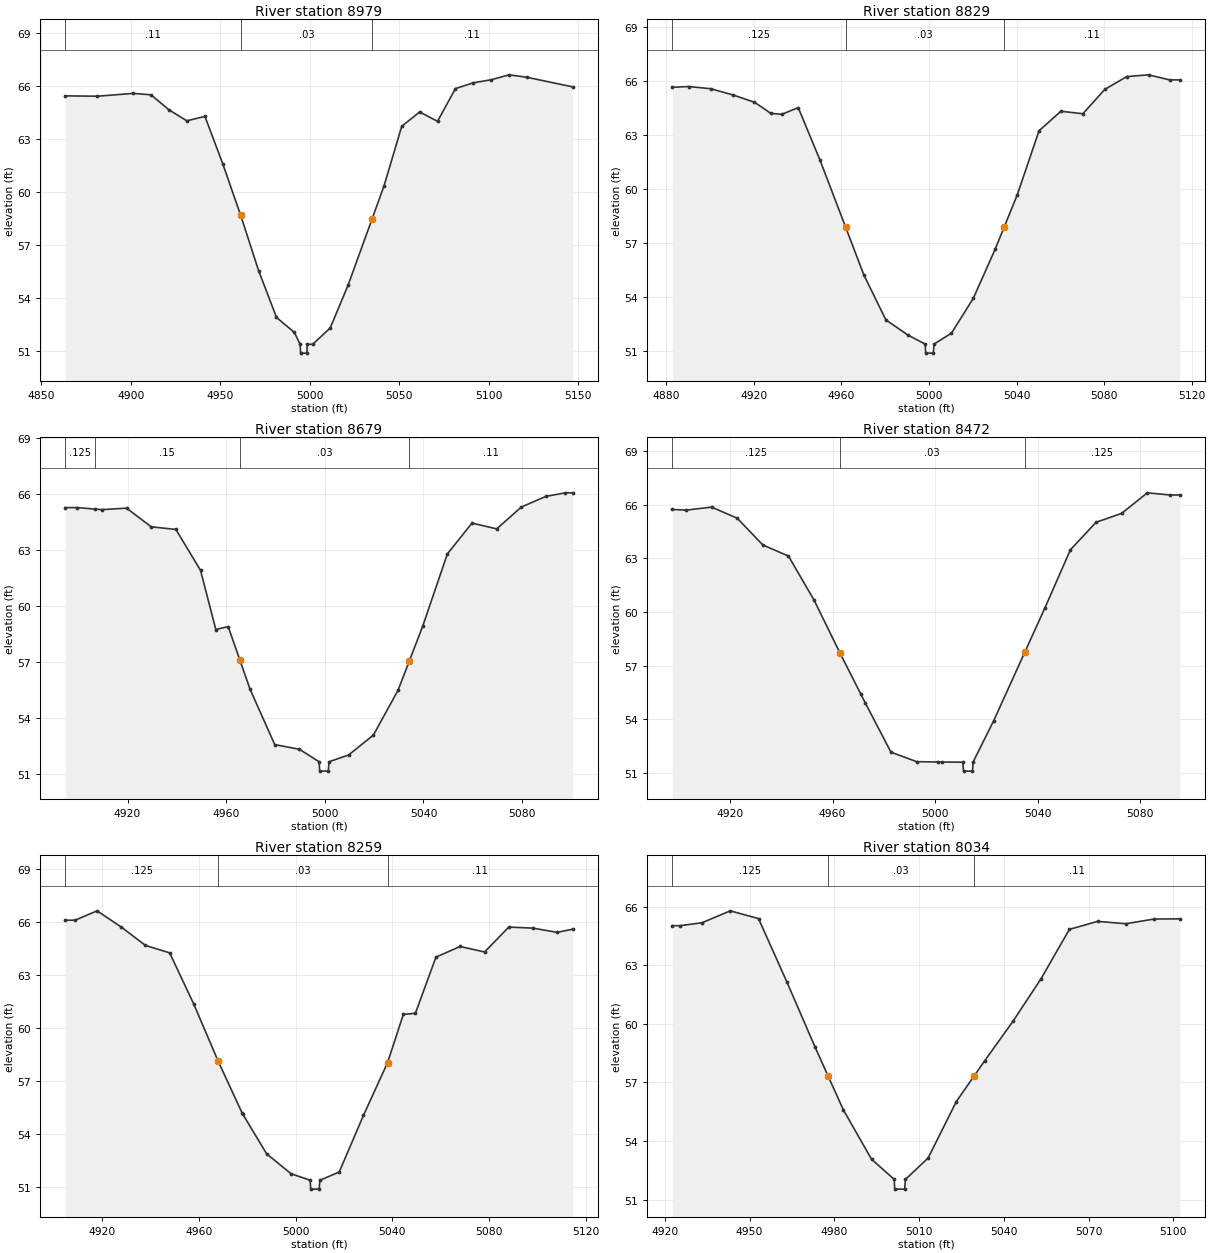
Type RM Length L Ch R = 1 ,8979    ,150,150,150
BEGIN DESCRIPTION:
G103-24-03 19.0
END DESCRIPTION:
XS GIS Cut Line= 3
      3928734.53      9997168.99      3928742.24      9997035.73
      3928742.34      9996885.62
#Sta/Elev= 30
  4863.4   65.44  4881.4   65.42  4901.4   65.58  4911.4    65.5  4921.4   64.65
  4931.4   64.03  4941.5   64.28  4951.5   61.59  4961.5   58.68  4971.5   55.56
  4981.5   52.91  4991.5   52.06  4994.7   51.39    4995   50.89  4998.5   50.89
  4998.7   51.39  5001.7   51.39  5011.5   52.31  5021.5   54.73    503558.50325
  5041.5   60.32  5051.5   63.72  5061.5   64.53  5071.5      64  5081.5   65.85
  5091.5   66.18  5101.5   66.35  5111.5   66.63  5121.5   66.49    5147   65.95
#Mann= 3 , 0 , 0
  4863.4     .11       0  4961.5     .03       0    5035     .11       0
Bank Sta=4961.5,5035
XS Rating Curve= 0 ,0
Exp/Cntr=0.3,0.1

Type RM Length L Ch R = 1 ,8829    ,150,150,150
BEGIN DESCRIPTION:
Mapping XS 9881c75a
END DESCRIPTION:
XS GIS Cut Line= 2
      3928893.38      9997158.55      3928890.78      9996926.76
#Sta/Elev= 30
  4882.8   65.64  4890.3   65.68  4900.3   65.56  4910.3   65.22  4920.3   64.81
  4927.8   64.19  4932.8   64.14  4940.3   64.51  4950.3   61.58  4961.9   57.89
  4970.3   55.22  4980.3   52.74  4990.3    51.9  4998.3   51.39  4998.5   50.89
    5002   50.89  5002.3   51.39  5010.3      52  5020.3   53.94  5030.3   56.67
 5034.3957.89301  5040.3   59.66  5050.3   63.23  5060.3   64.31  5070.3   64.17
  5080.3   65.52  5090.3   66.23  5100.3   66.33  5109.9   66.05  5114.6   66.05
#Mann= 3 , 0 , 0
  4882.8    .125       0  4961.9     .03       0 5034.39     .11       0
Bank Sta=4961.9,5034.39
XS Rating Curve= 0 ,0
Exp/Cntr=0.3,0.1

Type RM Length L Ch R = 1 ,8679    ,207,207,207
BEGIN DESCRIPTION:
Mapping XS df408ad2
END DESCRIPTION:
XS GIS Cut Line= 2
      3929044.43        9997156.      3929039.22      9996950.27
#Sta/Elev= 30
  4894.7   65.26  4899.7   65.26  4906.7   65.18  4909.6   65.15  4919.6   65.23
  4929.6   64.23  4939.6   64.09  4949.6    61.9  4955.8   58.73  4960.8   58.89
  4965.6   57.08  4969.7   55.53  4979.7   52.57  4989.7   52.32  4997.7   51.65
  4997.9   51.15  5001.4   51.15  5001.7   51.65  5009.7   52.02  5019.7   53.08
  5029.7   55.48 5034.28 57.0508  5039.7   58.91  5049.7   62.78  5059.7   64.43
  5069.7   64.12  5079.7   65.29  5089.7   65.86  5097.6   66.05  5100.5   66.05
#Mann= 4 ,-1 , 0
  4894.7    .125       0  4906.7     .15       0  4965.6     .03       0
 5034.28     .11       0
Bank Sta=4965.6,5034.28
XS Rating Curve= 0 ,0
Exp/Cntr=0.3,0.1

Type RM Length L Ch R = 1 ,8472    ,213,213,213
BEGIN DESCRIPTION:
Mapping XS 57d0db5e
END DESCRIPTION:
XS GIS Cut Line= 2
      3929250.16       9997166.4      3929247.55      9996968.42
#Sta/Elev= 27
  4897.5   65.74  4902.8    65.7  4912.8   65.87  4922.8   65.25  4932.8   63.75
  4942.8   63.13  4952.8   60.66  4962.8   57.73    4971   55.41  4972.8    54.9
  4982.8   52.15  4992.8   51.62  5001.3    51.6  5002.8    51.6  5010.8   51.59
  5011.1   51.09  5014.6   51.09  5014.8   51.59  5022.8   53.89    503557.74526
  5042.8   60.21  5052.8   63.48  5062.8   65.02  5072.8   65.52  5082.8   66.67
  5091.7   66.55  5095.5   66.55
#Mann= 3 , 0 , 0
  4897.5    .125       0  4962.8     .03       0    5035    .125       0
Bank Sta=4962.8,5035
XS Rating Curve= 0 ,0
Exp/Cntr=0.3,0.1

Type RM Length L Ch R = 1 ,8259    ,225,225,225
BEGIN DESCRIPTION:
Mapping XS e31a9562
END DESCRIPTION:
XS GIS Cut Line= 2
      3929455.88      9997174.22      3929466.23      9996964.68
#Sta/Elev= 28
  4904.7    66.1  4908.8    66.1  4917.9   66.63  4927.9   65.71  4937.9   64.67
  4947.9   64.25  4957.9   61.34  4967.9   58.13  4977.9   55.17  4978.1   55.12
    4988   52.87    4998   51.75    5006   51.37  5006.2   50.87  5009.7   50.87
    5010   51.37    5018   51.84    5028   55.04    5038   58.04  5044.5   60.76
  5049.5   60.83    5058   64.01    5068   64.61  5078.1    64.3  5088.1   65.71
  5098.1   65.65  5108.1   65.41  5114.5   65.59
#Mann= 3 , 0 , 0
  4904.7    .125       0  4967.9     .03       0    5038     .11       0
Bank Sta=4967.9,5038
XS Rating Curve= 0 ,0
Exp/Cntr=0.3,0.1

Type RM Length L Ch R = 1 ,8034    ,283,283,283
BEGIN DESCRIPTION:
Mapping XS c73aa2a5
END DESCRIPTION:
XS GIS Cut Line= 2
      3929685.05      9997171.54      3929685.05      9996991.94
#Sta/Elev= 25
  4922.7   65.02  4925.4   65.02  4933.2   65.17  4943.2   65.78  4953.2   65.38
  4963.2   62.15  4973.2   58.81  4977.8   57.33  4983.2    55.6  4993.2   53.07
  5001.2   52.04  5001.4   51.54  5004.9   51.54  5005.2   52.04  5013.2   53.13
  5023.2   56.02 5029.5857.34702  5033.2    58.1  5043.2   60.12  5053.2   62.31
  5063.2   64.83  5073.2   65.24  5083.2   65.12  5093.2   65.36  5102.3   65.37
#Mann= 3 , 0 , 0
  4922.7    .125       0  4977.8     .03       0 5029.58     .11       0
Bank Sta=4977.8,5029.58
XS Rating Curve= 0 ,0
Exp/Cntr=0.3,0.1

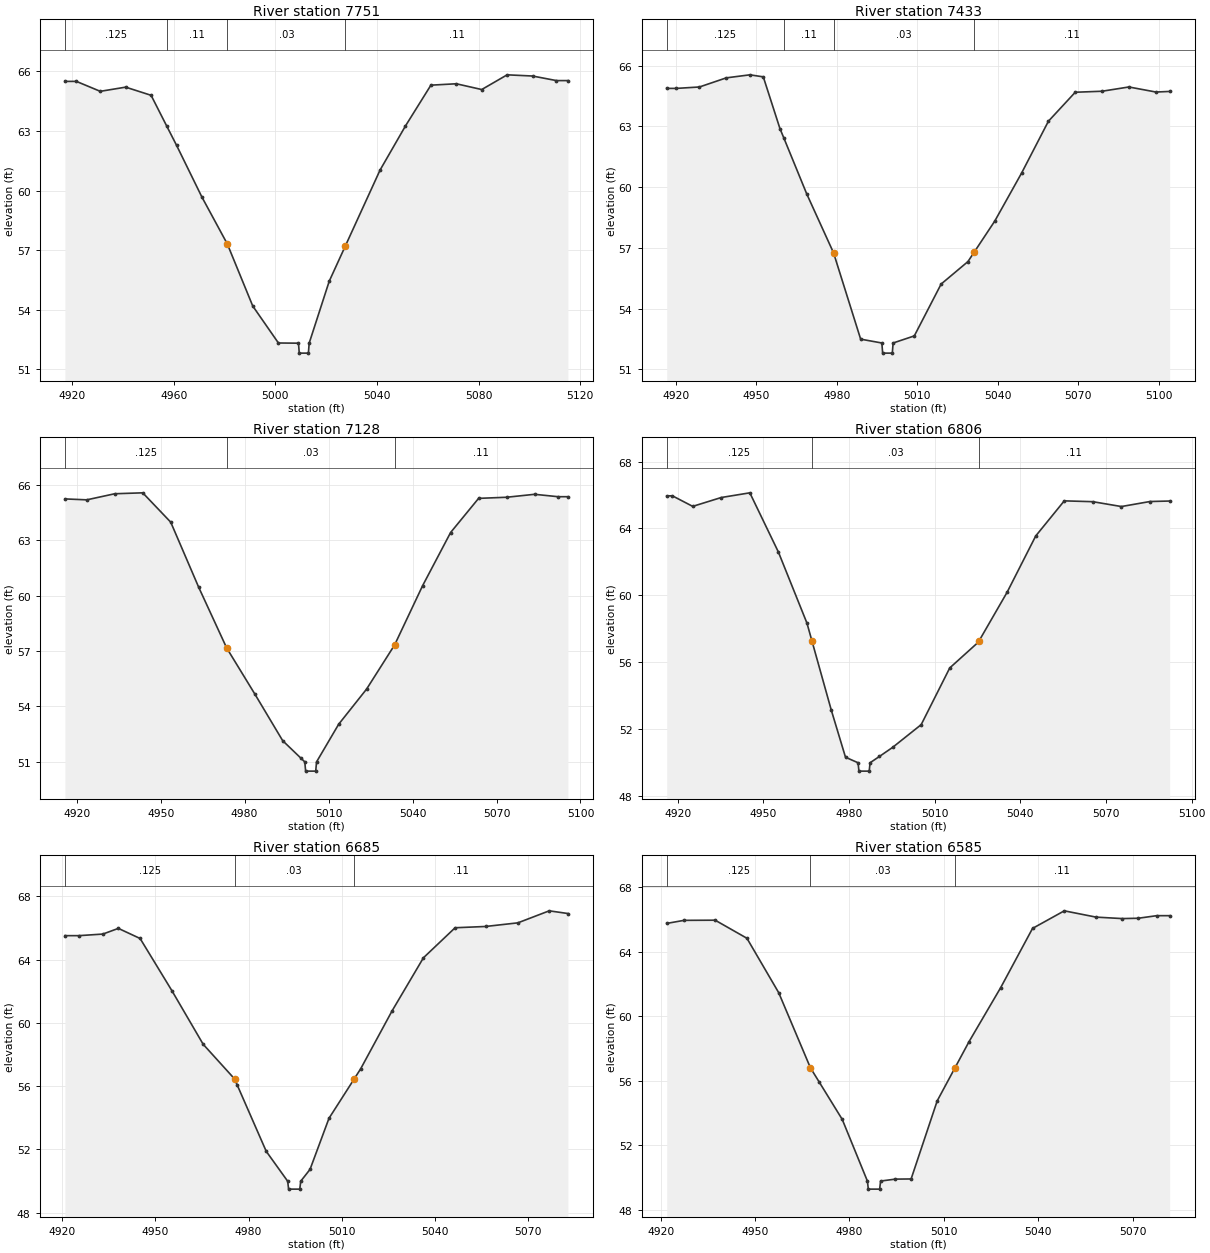
Type RM Length L Ch R = 1 ,7751    ,318,318,318
BEGIN DESCRIPTION:
Mapping XS 677598a0
END DESCRIPTION:
XS GIS Cut Line= 2
       3929966.3      9997195.01      3929968.91      9996997.13
#Sta/Elev= 26
  4917.2   65.49  4921.7   65.49  4931.1   64.99  4941.1    65.2  4951.1   64.79
  4957.3   63.23  4961.1   62.28  4971.1   59.67  4981.1   57.31  4991.1   54.19
  5001.2   52.33  5009.1   52.32  5009.4   51.82    5013   51.82  5013.3   52.32
  5021.2   55.44 5027.59 57.2259  5041.2   61.03  5051.2   63.25  5061.2    65.3
  5071.2   65.37  5081.2   65.08  5091.2   65.82  5101.2   65.76  5110.6   65.53
  5115.1   65.53
#Mann= 4 ,-1 , 0
  4917.2    .125       0  4957.3     .11       0  4981.1     .03       0
 5027.59     .11       0
Bank Sta=4981.1,5027.59
XS Rating Curve= 0 ,0
Exp/Cntr=0.3,0.1

Type RM Length L Ch R = 1 ,7433    ,305,305,305
BEGIN DESCRIPTION:
Mapping XS 5f785834
END DESCRIPTION:
XS GIS Cut Line= 2
       3930281.4      9997213.27      3930289.21      9997025.93
#Sta/Elev= 27
  4916.6   64.87  4920.2   64.87  4928.8   64.94  4938.8   65.39  4947.6   65.54
  4952.6   65.44  4958.8   62.89  4960.3   62.41  4968.8   59.66  4978.8   56.75
  4988.9   52.49  4996.8    52.3  4997.1    51.8  5000.7    51.8    5001    52.3
  5008.9   52.65  5018.9   55.21  5028.9   56.32 5031.2356.78602  5038.9   58.32
  5048.9   60.69  5058.9   63.25  5068.9   64.68  5078.9   64.73  5088.9   64.94
    5099   64.69  5104.1   64.72
#Mann= 4 ,-1 , 0
  4916.6    .125       0  4960.3     .11       0  4978.8     .03       0
 5031.23     .11       0
Bank Sta=4978.8,5031.23
XS Rating Curve= 0 ,0
Exp/Cntr=0.3,0.1

Type RM Length L Ch R = 1 ,7128    ,322,322,322
BEGIN DESCRIPTION:
Mapping XS 254f1996
END DESCRIPTION:
XS GIS Cut Line= 2
       3930588.7      9997228.86       3930591.3      9997049.18
#Sta/Elev= 24
  4915.8   65.24  4923.6   65.19  4933.6   65.52  4943.6   65.57  4953.6   63.98
  4963.6   60.45  4973.6   57.16  4983.6   54.68  4993.6   52.14  5000.2   51.18
  5001.5   50.99  5001.8   50.49  5005.4   50.49  5005.7   50.99  5013.6   53.03
  5023.6   54.94  5033.6   57.33  5043.6   60.54  5053.6   63.42  5063.6   65.27
  5073.6   65.33  5083.6   65.49    5092   65.36  5095.5   65.36
#Mann= 3 , 0 , 0
  4915.8    .125       0  4973.6     .03       0  5033.6     .11       0
Bank Sta=4973.6,5033.6
XS Rating Curve= 0 ,0
Exp/Cntr=0.3,0.1

Type RM Length L Ch R = 1 ,6806    ,121,121,121
BEGIN DESCRIPTION:
Mapping XS 4917bb19
END DESCRIPTION:
XS GIS Cut Line= 2
      3930915.08      9997230.15      3930908.65      9997054.17
#Sta/Elev= 27
  4916.2   65.95  4918.2   65.95  4925.3   65.32  4935.3   65.85  4945.3   66.13
  4955.3   62.59  4965.3   58.34 4967.0457.27743  4973.8   53.15  4978.8   50.32
  4983.2   49.99  4983.5   49.49  4987.1   49.49  4987.4   49.99  4990.7   50.37
  4995.3   50.91  5005.3   52.27  5015.3   55.66  5025.3    57.2 5025.5657.27705
  5035.4   60.19  5045.4   63.55  5055.4   65.65  5065.4    65.6  5075.4   65.31
  5085.4   65.61  5092.3   65.64
#Mann= 3 , 0 , 0
  4916.2    .125       0 4967.04     .03       0 5025.56     .11       0
Bank Sta=4967.04,5025.56
XS Rating Curve= 0 ,0
Exp/Cntr=0.3,0.1

Type RM Length L Ch R = 1 ,6685    ,100,100,100
BEGIN DESCRIPTION:
Mapping XS 54699d25
END DESCRIPTION:
XS GIS Cut Line= 2
       3931045.3        9997215.      3931019.38      9997055.19
#Sta/Elev= 25
  4920.9   65.52  4925.4   65.52  4933.1   65.62  4938.1   65.98  4945.1   65.34
  4955.3   62.05  4965.4   58.65  4975.5   56.46  4976.3    56.1  4985.7   51.88
  4992.6   49.99  4992.9   49.49  4996.5   49.49  4996.8   49.99  4999.8   50.74
  5005.9   53.97 5013.9556.44029  5016.1    57.1  5026.2   60.76  5036.3   64.12
  5046.5   66.02  5056.3    66.1  5066.7   66.33  5076.8   67.09  5082.8   66.92
#Mann= 3 , 0 , 0
  4920.9    .125       0  4975.5     .03       0 5013.95     .11       0
Bank Sta=4975.5,5013.95
XS Rating Curve= 0 ,0
Exp/Cntr=0.3,0.1

Type RM Length L Ch R = 1 ,6585    ,350,350,350
BEGIN DESCRIPTION:
Mapping XS 38ede81c
END DESCRIPTION:
XS GIS Cut Line= 2
      3931142.95      9997206.32      3931121.25       9997047.9
#Sta/Elev= 25
  4921.9   65.74  4927.4   65.93  4937.3   65.94  4947.4   64.82  4957.5   61.45
  4967.6   56.79  4970.3   55.94  4977.7    53.6  4985.7   49.78    4986   49.28
  4989.6   49.28  4989.9   49.78  4994.6    49.9  4999.6   49.91  5007.9   54.75
 5013.5756.80463    5018   58.41  5028.1   61.77  5038.2   65.43  5048.3   66.52
  5058.4   66.13  5066.7   66.04  5071.8   66.06  5077.7   66.22  5081.8   66.22
#Mann= 3 , 0 , 0
  4921.9    .125       0  4967.6     .03       0 5013.57     .11       0
Bank Sta=4967.6,5013.57
XS Rating Curve= 0 ,0
Exp/Cntr=0.3,0.1

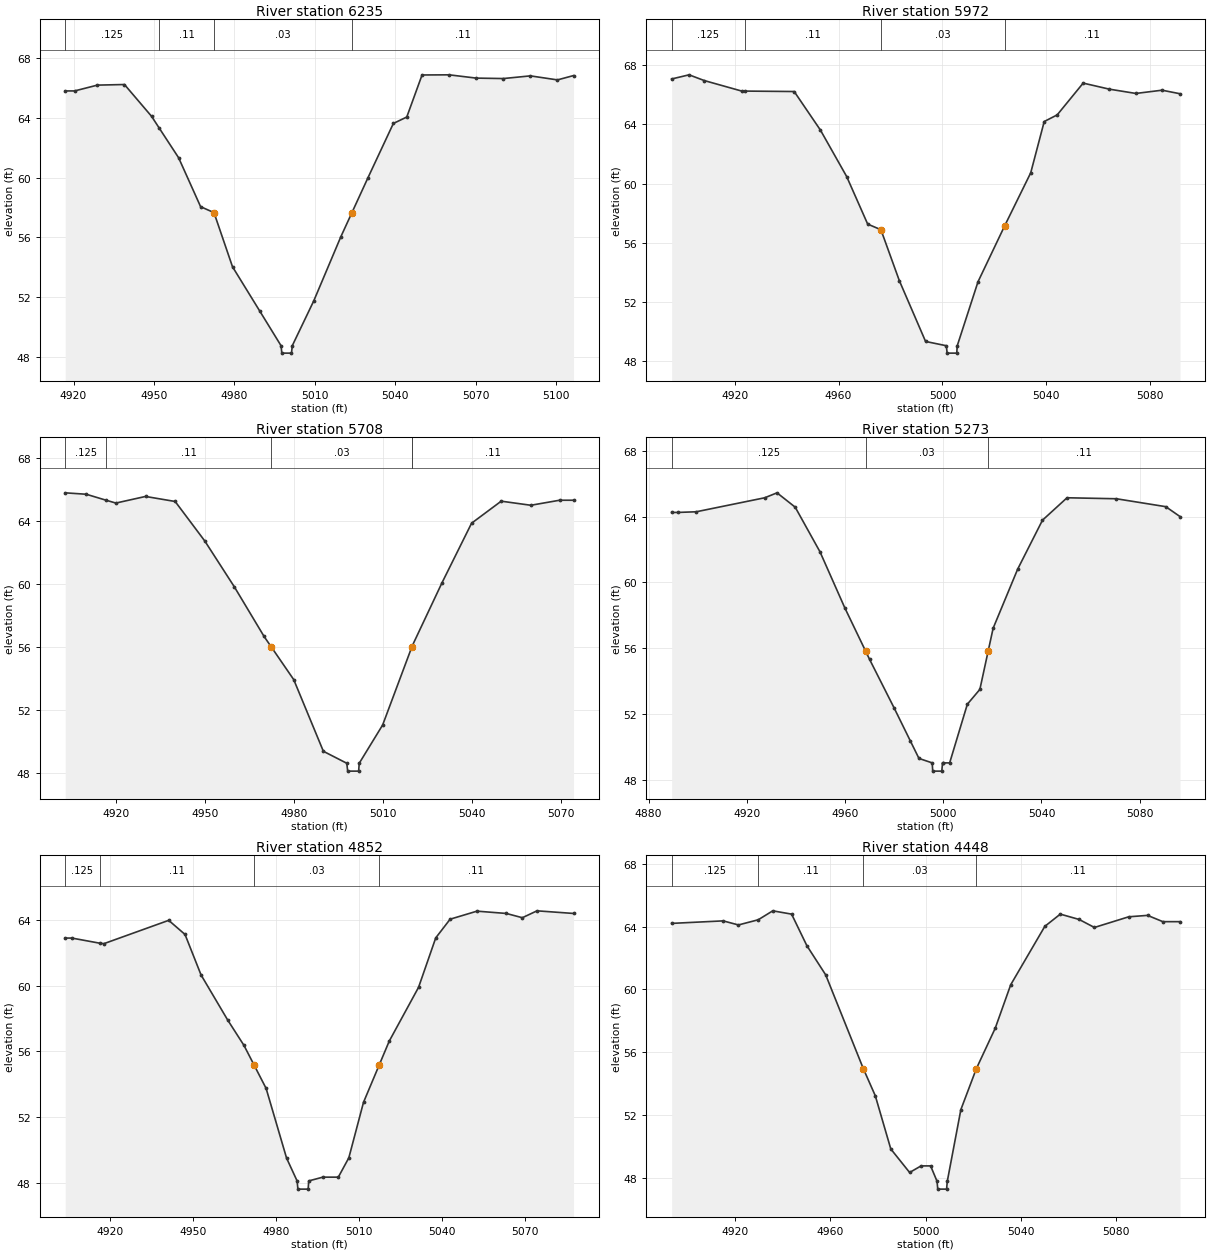
Type RM Length L Ch R = 1 ,6235    ,263,263,263
BEGIN DESCRIPTION:
Mapping XS c102ed7f
END DESCRIPTION:
XS GIS Cut Line= 2
      3931490.18      9997162.93      3931464.27      9996975.11
#Sta/Elev= 28
  4916.9   65.81  4920.4   65.81  4928.9    66.2    4939   66.24  4949.1   64.11
    4952   63.31  4959.2   61.33  4967.4   58.05  4972.4   57.65  4979.3   54.02
  4989.4   51.07  4997.4   48.73  4997.7   48.23  5001.3   48.23  5001.6   48.73
  5009.6   51.73  5019.7   56.03 5023.7357.60606  5029.8   59.98  5039.3   63.63
  5044.3   64.06    5050   66.88  5060.1   66.89  5070.2   66.67  5080.3   66.64
  5090.4   66.82  5100.5   66.55  5106.5   66.84
#Mann= 4 ,-1 , 0
  4916.9    .125       0    4952     .11       0  4972.4     .03       0
 5023.73     .11       0
Bank Sta=4972.4,5023.73
XS Rating Curve= 0 ,0
Exp/Cntr=0.3,0.1

Type RM Length L Ch R = 1 ,5972    ,264,264,264
BEGIN DESCRIPTION:
Mapping XS f09d4049
END DESCRIPTION:
XS GIS Cut Line= 2
      3931754.93      9997147.71      3931724.83      9996954.23
#Sta/Elev= 26
  4895.7   67.08  4902.4   67.36  4908.3   66.97  4922.7   66.26    4924   66.26
  4942.9   66.23    4953   63.62  4963.1   60.48  4971.2   57.26  4976.3   56.88
  4983.4   53.43  4993.5   49.32  5001.5   49.03  5001.8   48.53  5005.5   48.53
  5005.7   49.03  5013.7   53.36  5023.9   57.12    5034   60.73  5039.2    64.2
  5044.2   64.65  5054.2    66.8  5064.3   66.39  5074.5    66.1  5084.6   66.32
  5091.5   66.08
#Mann= 4 ,-1 , 0
  4895.7    .125       0    4924     .11       0  4976.3     .03       0
  5023.9     .11       0
Bank Sta=4976.3,5023.9
XS Rating Curve= 0 ,0
Exp/Cntr=0.3,0.1

Type RM Length L Ch R = 1 ,5708    ,435,435,435
BEGIN DESCRIPTION:
Mapping XS 44910ddb
END DESCRIPTION:
XS GIS Cut Line= 2
      3932002.33      9997128.21      3932002.33      9996956.71
#Sta/Elev= 25
  4902.7   65.81  4909.8   65.72  4916.5   65.34  4919.8   65.16  4929.8   65.58
  4939.8   65.26  4949.8   62.75  4959.8   59.83  4969.8   56.69  4972.256.03229
  4979.8   53.95  4989.8    49.4  4997.7   48.64    4998   48.14  5001.7   48.14
  5001.9   48.64  5009.8   51.07 5019.6656.02975  5019.8    56.1  5029.8   60.09
  5039.8   63.88  5049.8   65.28  5059.8   65.02  5069.5   65.34  5074.2   65.34
#Mann= 5 ,-1 , 0
  4902.7    .125       0  4916.5     .11       0  4972.2     .03       0
 5019.66     .11       0  5019.8     .11       0
Bank Sta=4972.2,5019.66
XS Rating Curve= 0 ,0
Exp/Cntr=0.3,0.1

Type RM Length L Ch R = 1 ,5273    ,421,421,421
BEGIN DESCRIPTION:
G103-24-03 13.0
END DESCRIPTION:
XS GIS Cut Line= 3
      3932417.86      9997211.02      3932431.48      9997101.26
      3932440.62       9997005.3
#Sta/Elev= 29
  4889.4   64.25  4891.9   64.25  4899.4   64.29  4927.3   65.14  4932.3   65.44
  4939.7   64.57  4949.8   61.86  4959.9   58.46 4968.4555.81028    4970   55.33
    4980   52.38  4986.6   50.38  4990.1   49.32  4995.5   49.05  4995.7   48.55
  4999.4   48.55  4999.7   49.05    5000   49.05  5002.6   49.05  5009.8   52.61
  5014.9   53.51 5018.2555.81168  5020.3   57.22  5030.3   60.81  5040.4   63.78
  5050.4   65.14  5070.5   65.08  5090.6    64.6  5096.4      64
#Mann= 3 , 0 , 0
  4889.4    .125       0 4968.45     .03       0 5018.25     .11       0
Bank Sta=4968.45,5018.25
XS Rating Curve= 0 ,0
Exp/Cntr=0.3,0.1

Type RM Length L Ch R = 1 ,4852    ,404,404,404
BEGIN DESCRIPTION:
G103-24-03 12.0
END DESCRIPTION:
XS GIS Cut Line= 3
      3932770.33      9997343.03      3932820.37      9997260.99
      3932848.68      9997178.09
#Sta/Elev= 30
  4903.9    62.9  4906.3    62.9  4916.3   62.59  4917.9   62.56  4941.3   63.98
  4947.2   63.12    4953   60.65  4962.6   57.91  4968.5   56.36 4972.2355.13843
  4976.5   53.74  4983.9   49.49  4987.7    48.1    4988    47.6  4991.7    47.6
  4991.9    48.1    4997   48.33  5002.6   48.33  5006.4   49.51  5011.7   52.89
 5017.3155.14002    5021   56.62  5031.6    59.9  5037.8   62.91    5043   64.05
  5052.7   64.54  5063.3    64.4  5069.1   64.14  5074.4   64.56  5087.6    64.4
#Mann= 4 ,-1 , 0
  4903.9    .125       0  4916.3     .11       0 4972.23     .03       0
 5017.31     .11       0
Bank Sta=4972.23,5017.31
XS Rating Curve= 0 ,0
Exp/Cntr=0.3,0.1

Type RM Length L Ch R = 1 ,4448    ,211,211,211
BEGIN DESCRIPTION:
G103-24-03 11.0
END DESCRIPTION:
XS GIS Cut Line= 3
      3933067.83      9997561.09      3933150.23      9997493.63
      3933217.84      9997411.08
#Sta/Elev= 30
  4893.5   64.21  4915.1   64.37  4921.5   64.11  4929.8   64.44  4935.9   65.01
  4943.8    64.8  4950.2   62.79  4958.1   60.93 4973.8754.95823  4978.9   53.23
  4985.4   49.84  4993.3   48.34  4998.1   48.76  5002.1   48.76  5004.8   47.78
  5005.1   47.28  5008.8   47.28  5009.1   47.78  5014.8   52.35  5021.3   54.96
  5029.2   57.53  5035.7    60.3    5050   64.02  5056.5    64.8  5064.4   64.46
  5070.8   63.95  5085.2   64.63  5093.1   64.72  5099.5   64.32  5106.7   64.32
#Mann= 4 ,-1 , 0
  4893.5    .125       0  4929.8     .11       0 4973.87     .03       0
  5021.3     .11       0
Bank Sta=4973.87,5021.3
XS Rating Curve= 0 ,0
Exp/Cntr=0.3,0.1

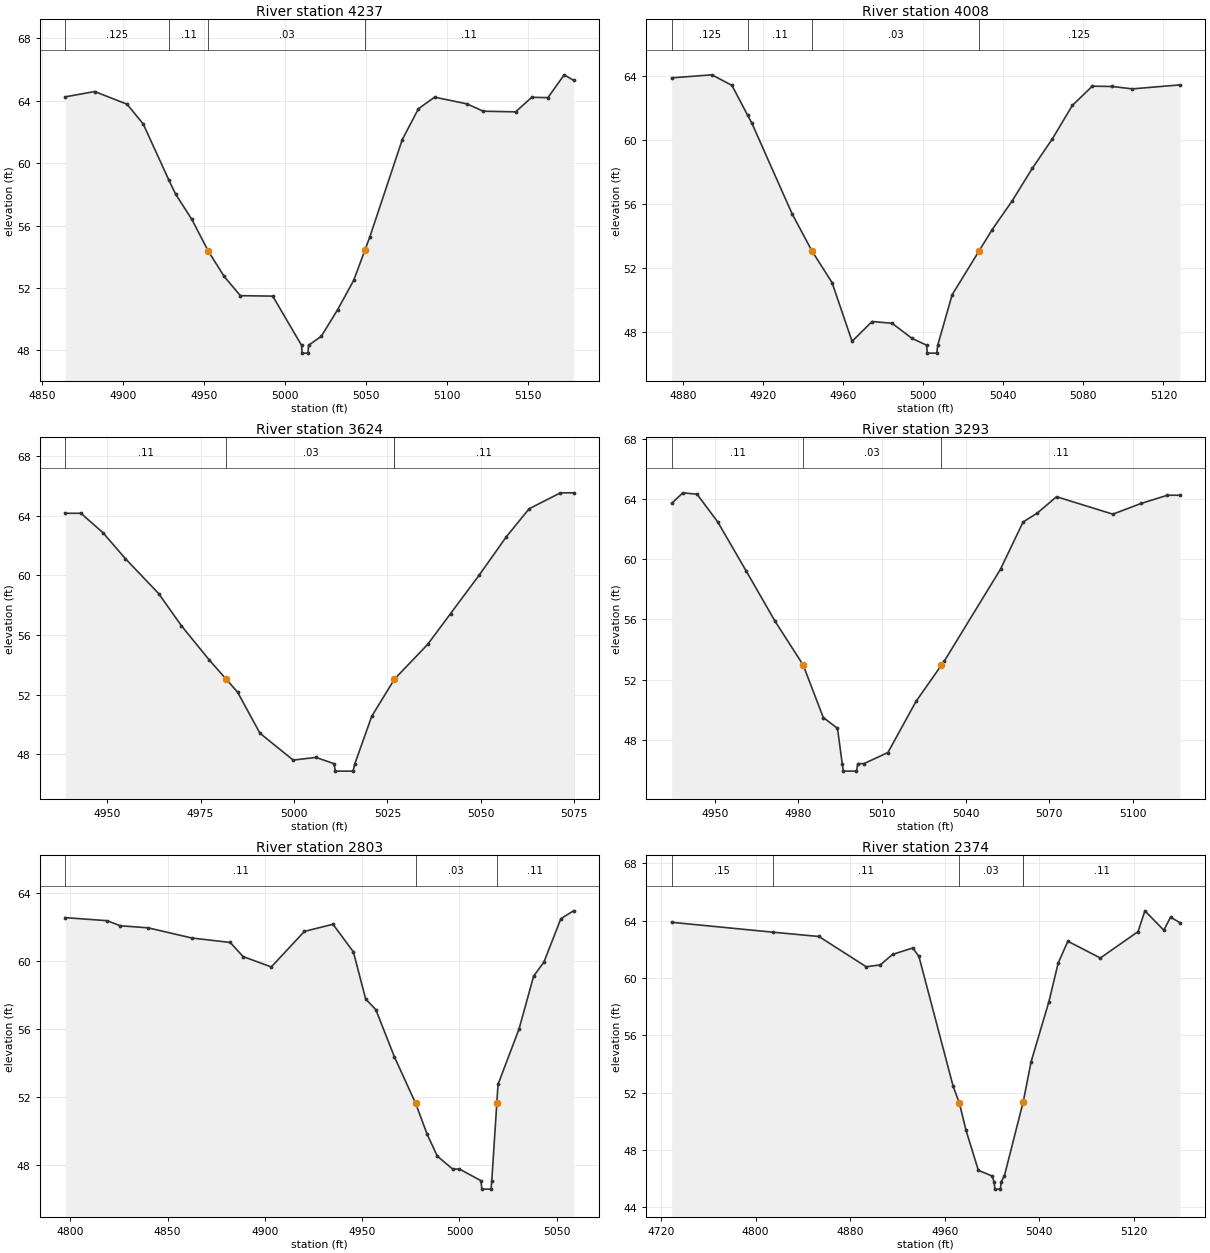
Type RM Length L Ch R = 1 ,4237    ,229,229,229
BEGIN DESCRIPTION:
Mapping XS e51b37c6
END DESCRIPTION:
XS GIS Cut Line= 2
       3933297.9      9997779.24      3933302.23      9997465.27
#Sta/Elev= 30
  4864.2   64.24  4882.4   64.58  4902.4   63.77  4912.4    62.5  4928.1   58.94
  4932.4   58.01  4942.4    56.4 4952.5854.36027  4962.4   52.74  4972.4   51.51
  4992.4   51.48  5010.2   48.33  5010.5   47.83  5014.2   47.83  5014.5   48.33
  5022.4   48.91  5032.4    50.6  5042.4   52.49  5049.4  54.443  5052.4   55.28
  5072.4    61.5  5082.4   63.48  5092.4   64.22  5112.4   63.79  5122.4   63.32
  5142.4   63.28  5152.4   64.21  5162.4   64.19  5172.4   65.65  5178.2    65.3
#Mann= 4 ,-1 , 0
  4864.2    .125       0  4928.1     .11       0 4952.58     .03       0
  5049.4     .11       0
Bank Sta=4952.58,5049.4
XS Rating Curve= 0 ,0
Exp/Cntr=0.3,0.1

Type RM Length L Ch R = 1 ,4008    ,384,384,384
BEGIN DESCRIPTION:
Mapping XS 223f82ac
END DESCRIPTION:
XS GIS Cut Line= 2
      3933458.49      9997931.14      3933462.83      9997677.27
#Sta/Elev= 27
  4874.4    63.9  4894.5   64.09  4904.5   63.43  4912.3   61.57  4914.5   61.05
  4934.5    55.4  4944.5   53.05  4954.5   51.08  4964.5    47.4  4974.5   48.64
  4984.5   48.53  4994.5   47.58  5001.7   47.16  5002.1   46.66  5006.8   46.66
  5007.3   47.16  5014.5   50.32 5027.8953.05159  5034.5    54.4  5044.5    56.2
  5054.5   58.23  5064.5   60.07  5074.5   62.17  5084.5   63.38  5094.5   63.36
  5104.5   63.21  5128.3   63.46
#Mann= 4 ,-1 , 0
  4874.4    .125       0  4912.3     .11       0  4944.5     .03       0
 5027.89    .125       0
Bank Sta=4944.5,5027.89
XS Rating Curve= 0 ,0
Exp/Cntr=0.3,0.1

Type RM Length L Ch R = 1 ,3624    ,331,331,331
BEGIN DESCRIPTION:
Mapping XS fb397e8f
END DESCRIPTION:
XS GIS Cut Line= 2
      3933736.29      9998083.02      3933812.23      9997970.19
#Sta/Elev= 26
  4938.8   64.16    4943   64.16  4948.9   62.86  4954.9   61.12  4963.8   58.78
  4969.9   56.62  4977.3   54.34 4981.9353.02402  4984.9   52.18  4990.9   49.42
  4999.8   47.62  5005.9    47.8  5010.7   47.38  5011.1   46.88  5015.8   46.88
  5016.3   47.38  5020.8   50.55 5026.8453.02539  5026.9   53.05  5035.8   55.38
  5041.9   57.44  5049.6   60.03  5056.8   62.58  5062.9   64.46  5071.3   65.53
  5074.8   65.53
#Mann= 4 ,-1 , 0
  4938.8     .11       0 4981.93     .03       0 5026.84     .11       0
  5026.9     .11       0
Bank Sta=4981.93,5026.84
XS Rating Curve= 0 ,0
Exp/Cntr=0.3,0.1

Type RM Length L Ch R = 1 ,3293    ,490,490,490
BEGIN DESCRIPTION:
G103-24-03 8.0
END DESCRIPTION:
XS GIS Cut Line= 3
      3933881.65      9998317.42      3933945.81      9998304.28
      3934061.74      9998289.21
#Sta/Elev= 27
  4934.5   63.73  4938.5   64.43  4943.6   64.34    4951    62.5  4961.2   59.24
  4971.5   55.91  4981.7   52.96 4981.7552.93586  4988.9   49.47    4994   48.75
  4995.7    46.4  4996.1    45.9  5000.8    45.9  5001.3    46.4  5003.5    46.4
  5012.1   47.14  5022.2   50.55 5031.2252.93459  5032.3   53.22  5052.5   59.35
  5060.6   62.49  5065.6   63.07  5072.6   64.17  5092.8   63.01  5102.9   63.72
  5112.4   64.27  5116.9   64.27
#Mann= 3 , 0 , 0
  4934.5     .11       0 4981.75     .03       0 5031.22     .11       0
Bank Sta=4981.75,5031.22
XS Rating Curve= 0 ,0
Exp/Cntr=0.3,0.1

Type RM Length L Ch R = 1 ,2803    ,429,429,429
BEGIN DESCRIPTION:
G103-24-03 7.0
END DESCRIPTION:
XS GIS Cut Line= 3
      3933777.46      9998855.63      3933969.48        9998791.
      3934023.88      9998769.21
#Sta/Elev= 30
  4797.4   62.56  4818.9   62.38  4825.8   62.08    4840   61.96  4862.5   61.36
  4882.2    61.1  4888.8   60.27  4903.3   59.66  4920.3   61.75    4935   62.17
  4945.5   60.54  4951.8   57.77    4957   57.15  4966.6   54.36 4977.4951.63061
  4983.3   49.84  4988.6   48.53  4996.5   47.77    5000   47.77    5011   47.09
  5011.5   46.59  5016.2   46.59  5016.6   47.09 5019.1751.63579  5019.8   52.75
  5030.6   56.01  5038.1   59.12  5043.4   59.95  5052.1    62.5  5058.6   62.96
#Mann= 3 , 0 , 0
  4797.4     .11       0 4977.49     .03       0 5019.17     .11       0
Bank Sta=4977.49,5019.17
XS Rating Curve= 0 ,0
Exp/Cntr=0.3,0.1

Type RM Length L Ch R = 1 ,2374    ,249,249,249
BEGIN DESCRIPTION:
G103-24-03 6.0
END DESCRIPTION:
XS GIS Cut Line= 3
      3933867.81      9999261.08      3934128.92      9999188.56
      3934267.87      9999111.06
#Sta/Elev= 30
    4729   63.89  4814.7    63.2  4853.6    62.9  4893.6   60.79  4905.5   60.92
  4915.9   61.65    4933    62.1  4938.2   61.51  4967.2   52.44 4972.4251.28326
  4978.1   49.37  4988.5   46.59    5000    46.2  5001.9   45.78  5002.4   45.28
  5007.2   45.28  5007.7   45.78  5010.5    46.2 5026.4751.38091  5026.5   51.39
  5033.1   54.16  5048.2   58.36    5056   61.04  5064.2   62.57  5091.7    61.4
  5123.6   63.24  5129.4   64.69  5145.4   63.34  5151.1   64.25  5159.1   63.86
#Mann= 5 ,-1 , 0
    4729     .15       0  4814.7     .11       0 4972.42     .03       0
 5026.47     .08       0  5026.5     .11       0
Bank Sta=4972.42,5026.47
XS Rating Curve= 0 ,0
Exp/Cntr=0.3,0.1

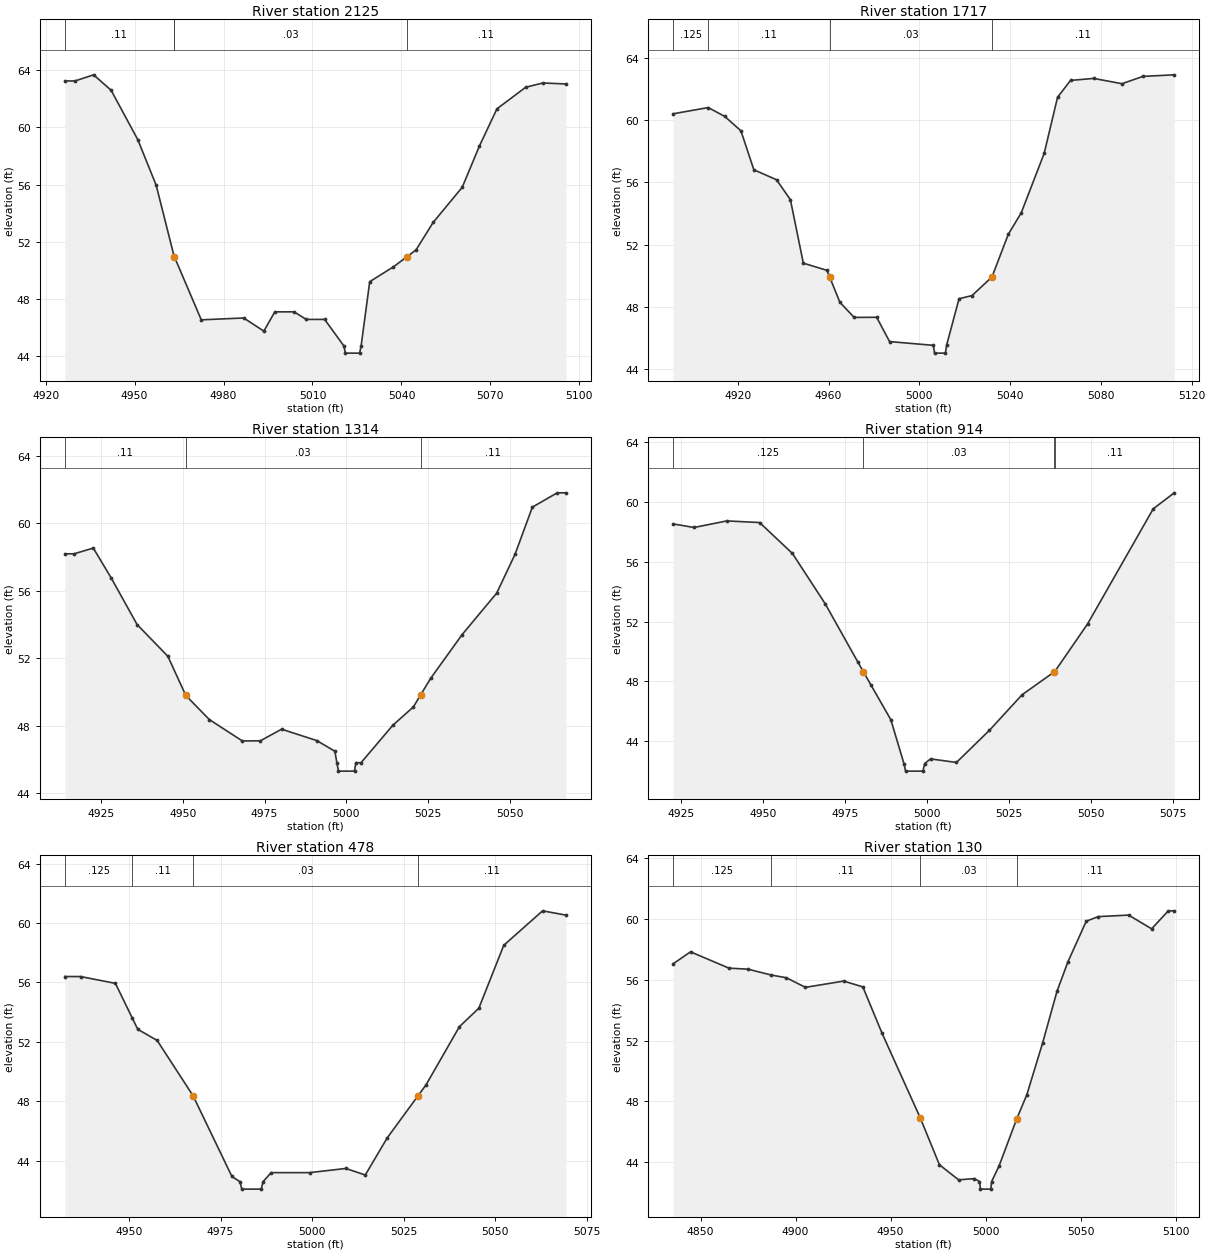
Type RM Length L Ch R = 1 ,2125    ,408,408,408
BEGIN DESCRIPTION:
G103-24-03 5.0
END DESCRIPTION:
XS GIS Cut Line= 3
      3934207.17      9999432.88        3934269.      9999393.14
      3934317.85      9999311.08
#Sta/Elev= 30
  4926.5   63.25  4929.9   63.25  4936.2   63.68  4942.1    62.6  4951.1   59.14
  4957.3   55.95  4963.3   51.01 4963.4450.94176  4972.5   46.53  4986.8   46.66
  4993.6   45.74  4997.3   47.09  5003.8   47.09  5007.9   46.56  5014.1   46.56
  5020.6    44.7  5021.1    44.2  5025.9    44.2  5026.4    44.7  5029.3    49.2
  5037.3   50.24 5041.8150.94027  5044.9   51.42  5050.7   53.35  5060.5   55.81
  5066.3    58.7  5072.2    61.3  5081.9   62.81  5087.7   63.11  5095.5   63.04
#Mann= 4 ,-1 , 0
  4926.5     .11       0  4963.3     .08       0 4963.44     .03       0
 5041.81     .11       0
Bank Sta=4963.44,5041.81
XS Rating Curve= 0 ,0
Exp/Cntr=0.3,0.1

Type RM Length L Ch R = 1 ,1717    ,403,403,403
BEGIN DESCRIPTION:
G103-24-03 4.0
END DESCRIPTION:
XS GIS Cut Line= 3
      3934517.85      9999661.07      3934613.06      9999609.05
      3934667.87      9999511.03
#Sta/Elev= 30
  4891.5   60.39    4907   60.79  4914.3   60.22  4921.4    59.3  4927.1    56.8
  4937.1   56.16  4943.2   54.88  4948.9   50.81  4959.3   50.35 4960.4749.92907
    4965    48.3  4971.3   47.33  4981.2   47.34  4986.9   45.78  5006.2   45.54
  5006.7   45.04  5011.5   45.04    5012   45.54  5017.5   48.53  5023.2   48.73
 5032.0149.92772  5039.2   52.66  5044.9   54.04    5055   57.85  5060.9   61.45
  5066.6   62.53  5076.8   62.66  5089.3   62.32  5098.5   62.79  5112.3   62.89
#Mann= 4 ,-1 , 0
  4891.5    .125       0    4907     .11       0 4960.47     .03       0
 5032.01     .11       0
Bank Sta=4960.47,5032.01
XS Rating Curve= 0 ,0
Exp/Cntr=0.3,0.1

Type RM Length L Ch R = 1 ,1314    ,400,400,400
BEGIN DESCRIPTION:
G103-24-03 3.0
END DESCRIPTION:
XS GIS Cut Line= 3
      3934867.83      9999861.08      3934945.78      9999824.52
      3934967.86      9999761.05
#Sta/Elev= 29
  4913.9    58.2  4916.7    58.2  4922.6   58.54  4928.1   56.76    4936      54
  4945.4   52.12 4950.85 49.8111  4950.9   49.79  4958.1   48.36  4968.2   47.09
  4973.7    47.1  4980.2   47.79    4991   47.11  4996.5   46.48  4997.1    45.8
  4997.6    45.3  5002.5    45.3  5002.9    45.8  5004.5    45.8  5014.2   48.02
  5020.5   49.11 5022.6949.81246  5025.8   50.81  5035.4    53.4    5046   55.87
  5051.6   58.17  5056.9   60.97  5064.5   61.82  5067.2   61.82
#Mann= 3 , 0 , 0
  4913.9     .11       0 4950.85     .03       0 5022.69     .11       0
Bank Sta=4950.85,5022.69
XS Rating Curve= 0 ,0
Exp/Cntr=0.3,0.1

Type RM Length L Ch R = 1 ,914     ,436,436,436
BEGIN DESCRIPTION:
Mapping XS 1ae02543
END DESCRIPTION:
XS GIS Cut Line= 2
      3935311.79      10000027.5      3935313.94      9999874.72
#Sta/Elev= 23
  4922.6   58.54    4929    58.3    4939   58.74    4949   58.63    4959   56.56
    4969   53.19    4979   49.27 4980.6648.63147  4982.9   47.77    4989   45.43
    4993   42.49  4993.5   41.99  4998.8   41.99  4999.3   42.49  5001.1   42.81
    5009   42.57    5019   44.71    5029    47.1 5038.8348.63349    5039   48.66
    5049   51.85    5069   59.55  5075.4   60.62
#Mann= 4 ,-1 , 0
  4922.6    .125       0 4980.66     .03       0 5038.83     .08       0
    5039     .11       0
Bank Sta=4980.66,5038.83
XS Rating Curve= 0 ,0
Exp/Cntr=0.3,0.1

Type RM Length L Ch R = 1 ,478     ,348,348,348
BEGIN DESCRIPTION:
Mapping XS 7de6a6f5
END DESCRIPTION:
XS GIS Cut Line= 2
       3935769.7      9999984.13      3935724.51      9999855.01
#Sta/Elev= 24
  4932.5    56.4  4936.8    56.4  4946.3   55.94  4950.9   53.61  4952.4   52.85
  4957.7    52.1  4967.5   48.38  4978.1   42.95  4980.3    42.6  4980.8    42.1
  4986.1    42.1  4986.6    42.6  4988.8   43.21  4999.3   43.21  5009.2   43.49
  5014.5   43.05  5020.5   45.55 5028.9348.38919  5031.1   49.12  5040.2   53.03
  5045.5   54.27  5052.3    58.5  5062.9   60.82  5069.3   60.53
#Mann= 4 ,-1 , 0
  4932.5    .125       0  4950.9     .11       0  4967.5     .03       0
 5028.93     .11       0
Bank Sta=4967.5,5028.93
XS Rating Curve= 0 ,0
Exp/Cntr=0.3,0.1

Type RM Length L Ch R = 1 ,130     ,0,0,0
BEGIN DESCRIPTION:
G103-24-03 1.0
END DESCRIPTION:
XS GIS Cut Line= 3
      3936093.04      9999960.24      3936073.51      9999799.62
       3936023.6      9999710.67
#Sta/Elev= 30
  4835.5   57.03  4844.7   57.82  4864.9   56.75    4875   56.68  4887.1    56.3
  4895.1   56.12  4905.2   55.49  4925.3    55.9  4935.4   55.52  4945.5   52.48
  4965.6   46.93  4975.7   43.85  4985.8   42.86  4994.1   42.94  4996.8   42.75
  4997.3   42.25  5002.7   42.25  5003.2   42.75  5007.1   43.77 5016.29 46.8265
  5021.7   48.44    5030   51.83  5037.6   55.23  5043.4   57.18    5053   59.83
  5059.3   60.13  5075.3   60.23  5087.4   59.33  5096.2   60.51  5099.3   60.51
#Mann= 4 ,-1 , 0
  4835.5    .125       0  4887.1     .11       0  4965.6     .03       0
 5016.29     .11       0
Bank Sta=4965.6,5016.29
XS Rating Curve= 0 ,0
Exp/Cntr=0.3,0.1

Chan Stop Cuts=-1
Use User Specified Reach Order=0
Composite Channel Slope=5