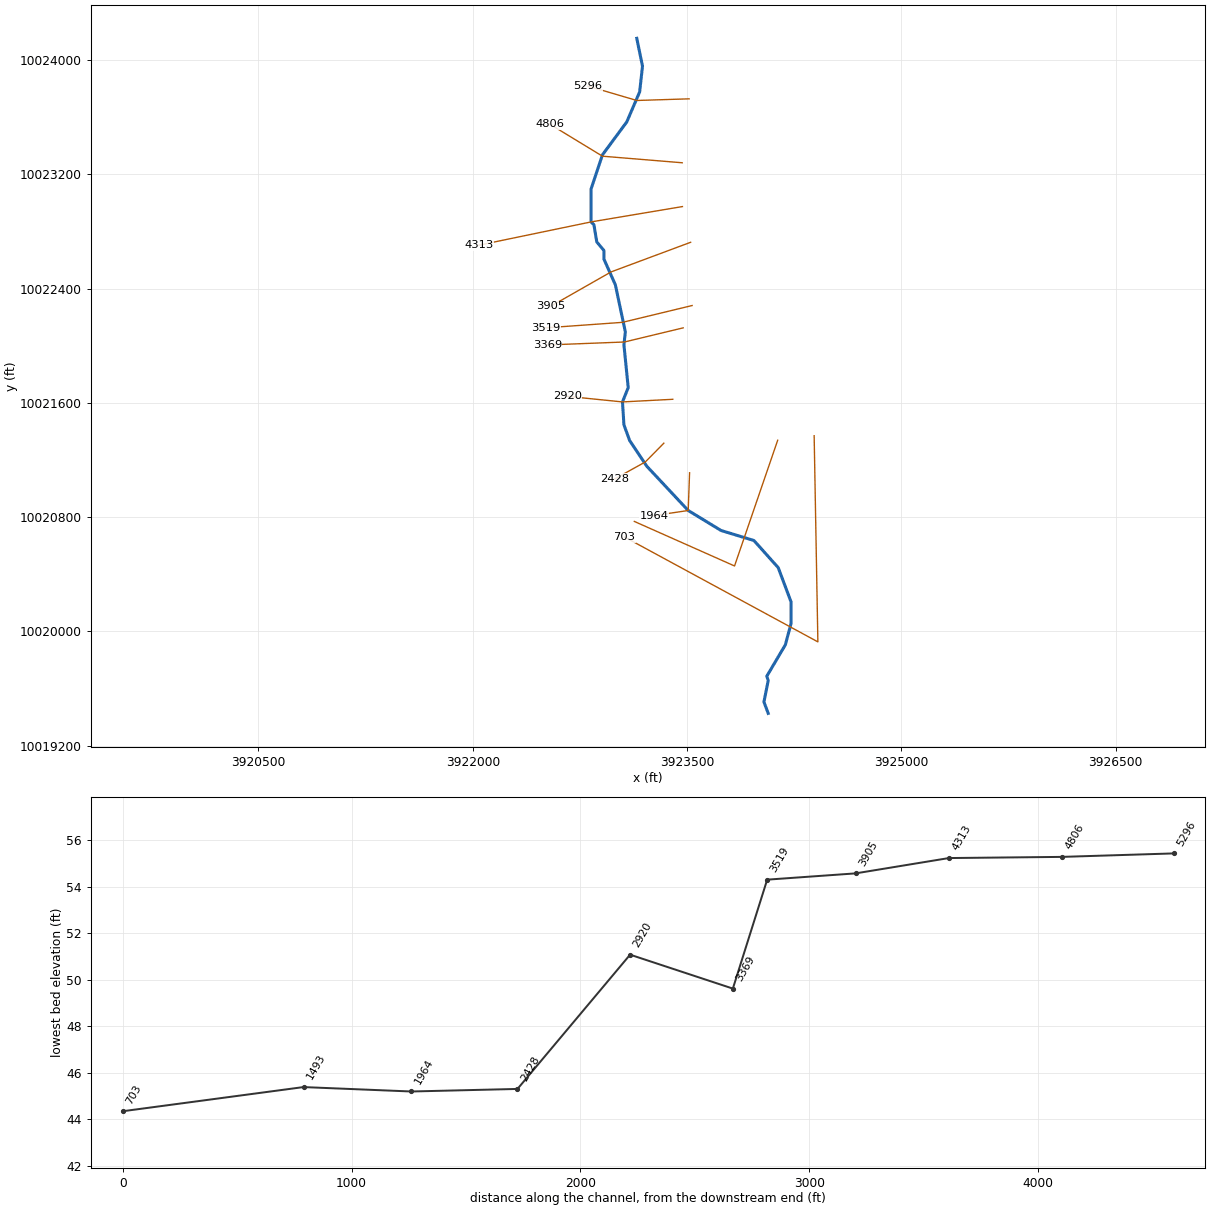
--- G103 33 01.prj (project) ---

Proj Title=G103 33 01 Base Level Engineering
Current Plan=p01
Default Exp/Contr=0.3,0.1
English Units
Geom File=g01
Flow File=f01
Flow File=f02
Plan File=p01
Y Axis Title=Elevation
X Axis Title(PF)=Main Channel Distance
X Axis Title(XS)=Station
BEGIN DESCRIPTION:
G103 33 01
END DESCRIPTION:
DSS Export Rating Curves= 0
DSS Export Rating Curve Sorted= 0
DSS Export Volume Flow Curves= 0
DXF OffsetX= 0
DXF OffsetY= 0
DXF ScaleX= 1
DXF ScaleY= 10

--- G103 33 01.p01 (plan) ---

Plan Title=Multiple Run
Short Identifier=Multiple
Geom File=g01
Flow File=f01
Subcritical Flow
K Sum by GR= 0
Std Step Tol= 0.01
Critical Tol= 0.01
Num of Std Step Trials= 20
Max Error Tol= 0.3
Flow Tol Ratio= 0.001
Split Flow NTrial= 30
Split Flow Tol= 0.02
Split Flow Ratio= 0.02
Log Output Level= 0
Friction Slope Method= 1
Unsteady Friction Slope Method= 2
Unsteady Bridges Friction Slope Method= 1
Parabolic Critical Depth
Global Vel Dist=  1 , 1 , 1
Global Log Level= 0
CheckData=True
Encroach Param= -1, 0, 0, 0
BEGIN DESCRIPTION:
Multiple Run
END DESCRIPTION:

--- G103 33 01.f01 (steady flow) ---

Flow Title=Multiple
Program Version=4.10
Number of Profiles= 7
Profile Names=10-year,25-year,50-year,1pct_min,100-year,1pct_plu,500-year
River Rch & RM=G103 33 01,Reach-1         ,5296
     739     983    1312     576    1738    5249    3151
River Rch & RM=G103 33 01,Reach-1         ,4313
     837    1119    1498     659    1990    6010    3627
Boundary for River Rch & Prof#=G103 33 01,Reach-1         , 1
Up Type= 0
Dn Type= 3
Dn Slope=0.005
Boundary for River Rch & Prof#=G103 33 01,Reach-1         , 2
Up Type= 0
Dn Type= 3
Dn Slope=0.005
Boundary for River Rch & Prof#=G103 33 01,Reach-1         , 3
Up Type= 0
Dn Type= 3
Dn Slope=0.005
Boundary for River Rch & Prof#=G103 33 01,Reach-1         , 4
Up Type= 0
Dn Type= 3
Dn Slope=0.005
Boundary for River Rch & Prof#=G103 33 01,Reach-1         , 5
Up Type= 0
Dn Type= 3
Dn Slope=0.005
Boundary for River Rch & Prof#=G103 33 01,Reach-1         , 6
Up Type= 0
Dn Type= 3
Dn Slope=0.005
Boundary for River Rch & Prof#=G103 33 01,Reach-1         , 7
Up Type= 0
Dn Type= 3
Dn Slope=0.005
DSS Import GetInterval= 0
DSS Import GetPeak= 0
DSS Import FillOption= 0

--- G103 33 01.f02 (steady flow) ---

Flow Title=Orgi_BLE_Flows
Program Version=4.10
Number of Profiles= 7
Profile Names=10-year,25-year,50-year,1pct_min,100-year,1pct_plu,500-year
River Rch & RM=G103 33 01,Reach-1         ,5296
     739     964    1141     443    1337    4039    1832
River Rch & RM=G103 33 01,Reach-1         ,4313
     837    1097    1303     507    1531    4624    2109
Boundary for River Rch & Prof#=G103 33 01,Reach-1         , 1
Up Type= 0
Dn Type= 3
Dn Slope=0.005
Boundary for River Rch & Prof#=G103 33 01,Reach-1         , 2
Up Type= 0
Dn Type= 3
Dn Slope=0.005
Boundary for River Rch & Prof#=G103 33 01,Reach-1         , 3
Up Type= 0
Dn Type= 3
Dn Slope=0.005
Boundary for River Rch & Prof#=G103 33 01,Reach-1         , 4
Up Type= 0
Dn Type= 3
Dn Slope=0.005
Boundary for River Rch & Prof#=G103 33 01,Reach-1         , 5
Up Type= 0
Dn Type= 3
Dn Slope=0.005
Boundary for River Rch & Prof#=G103 33 01,Reach-1         , 6
Up Type= 0
Dn Type= 3
Dn Slope=0.005
Boundary for River Rch & Prof#=G103 33 01,Reach-1         , 7
Up Type= 0
Dn Type= 3
Dn Slope=0.005
DSS Import GetInterval= 0
DSS Import GetPeak= 0
DSS Import FillOption= 0

--- G103 33 01.g01 (geometry) ---

Geom Title=Existing Conditions
Program Version=4.10

River Reach=G103 33 01      ,Reach-1
Reach XY= 30
      3923148.23     10024151.84      3923188.23     10023956.84
      3923168.23     10023776.84      3923078.23     10023566.84
      3922908.23     10023336.84      3922828.23     10023096.84
      3922828.23     10022866.84      3922848.23     10022846.84
      3922868.23     10022726.84      3922918.23     10022666.84
      3922918.23     10022606.84      3922998.23     10022426.84
      3923068.23     10022096.84      3923058.23     10022006.84
      3923088.23     10021706.84      3923048.23     10021606.84
      3923058.23     10021446.84      3923098.23     10021336.84
      3923218.23     10021156.84      3923508.23     10020846.84
      3923738.23     10020706.84      3923968.23     10020636.84
      3924138.23     10020446.84      3924228.23     10020206.84
      3924228.23     10020056.84      3924188.23     10019906.84
      3924058.23     10019686.84      3924068.23     10019656.84
      3924038.23     10019506.84      3924068.23     10019426.84

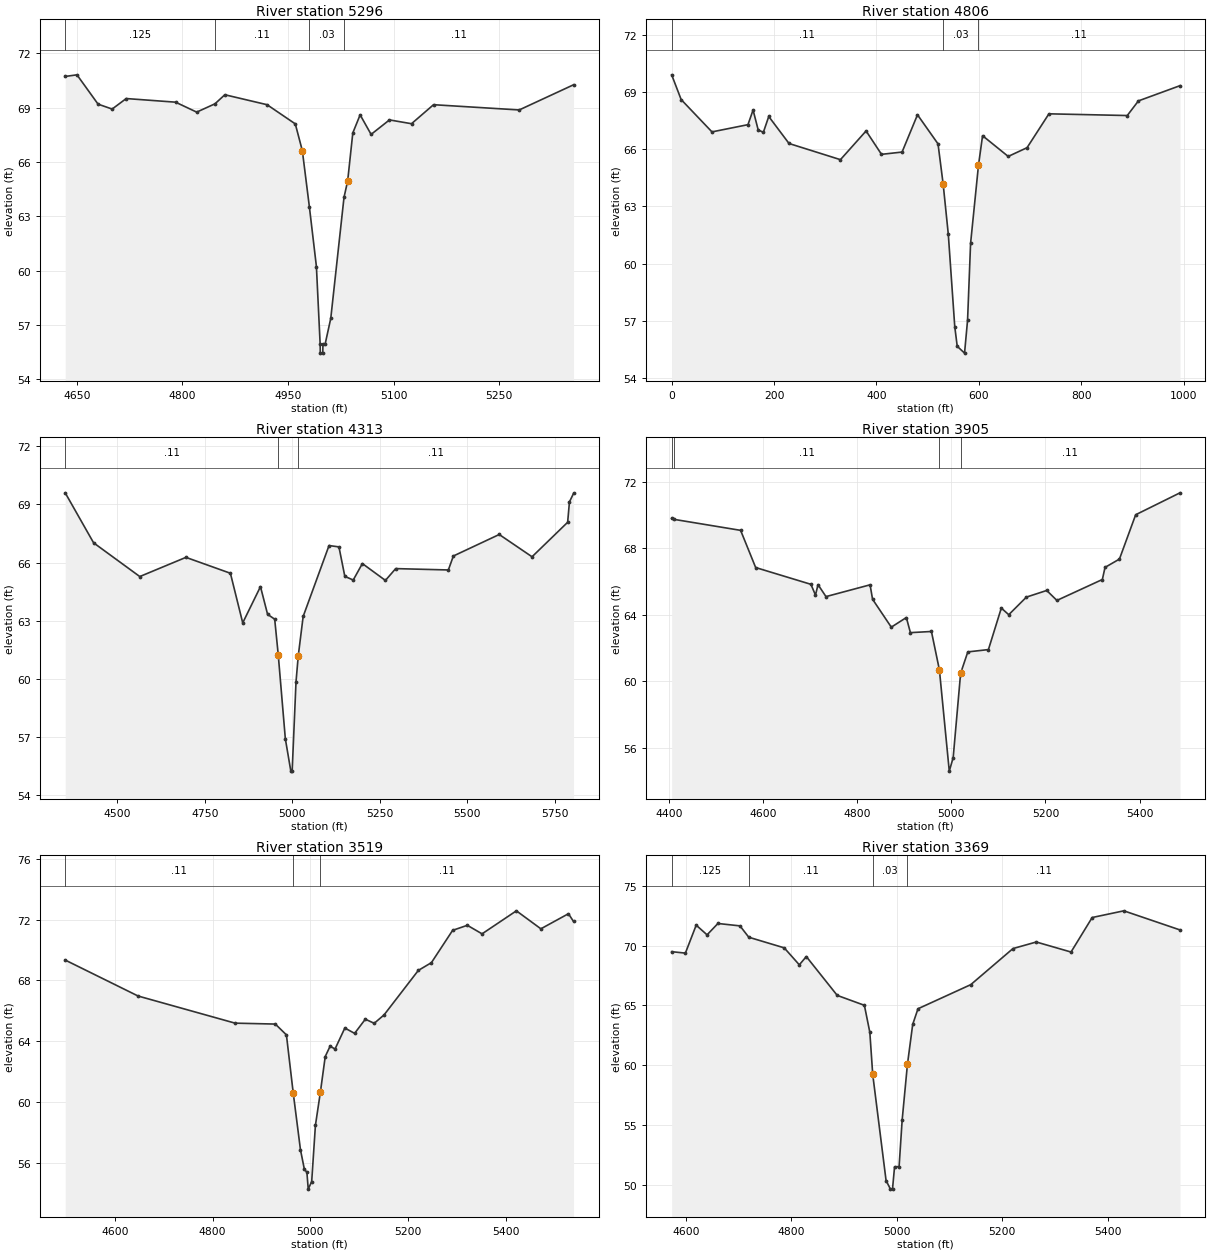
Type RM Length L Ch R = 1 ,5296    ,490,490,490
BEGIN DESCRIPTION:
G103-33-01 9.0
END DESCRIPTION:
XS GIS Cut Line= 3
      3923514.55     10023728.37      3923148.23     10023716.84
      3922807.02     10023817.35
#Sta/Elev= 30
  4633.5   70.72  4650.2   70.81  4680.2   69.19  4700.2   68.92  4720.2    69.5
  4790.3    69.3  4820.3   68.75  4846.3   69.21  4860.3   69.71  4920.3   69.16
  4960.4    68.1  4970.4   66.62  4980.4   63.52  4990.4   60.22  4995.7   55.94
  4995.9   55.44  4999.4   55.44  4999.7   55.94  5002.8   55.94  5010.8   57.36
  5029.6   64.04  5034.8   64.95  5042.1    67.6  5052.5    68.6  5068.1   67.52
  5094.2   68.32  5125.5   68.11  5156.8   69.16  5278.5   68.87  5355.7   70.26
#Mann= 4 ,-1 , 0
  4633.5    .125       0  4846.3     .11       0  4980.4     .03       0
  5029.6     .11       0
Bank Sta=4970.4,5034.8
XS Rating Curve= 0 ,0
Exp/Cntr=0.3,0.1

Type RM Length L Ch R = 1 ,4806    ,493,493,493
BEGIN DESCRIPTION:
G103-33-01 8.0
END DESCRIPTION:
XS GIS Cut Line= 3
      3923466.32     10023280.89      3922908.23     10023326.84
       3922538.5     10023551.78
#Sta/Elev= 30
       0   69.92    18.5   68.62    78.7   66.92     149    67.3     159   68.07
     169   67.02   179.1    66.9   189.6   67.73   229.2   66.31   329.6   65.46
   379.7   66.97   409.8   65.74     450   65.86   480.1   67.82   520.2   66.29
   530.3   64.16   540.3   61.53   552.9   56.68   557.7   55.65     572   55.29
   577.9   57.02   583.8   61.06   599.2   65.16   607.2   66.72   657.3   65.63
   694.1   66.09   736.8   67.87   889.8   67.78   911.6   68.55   992.8   69.35
#Mann= 3 , 0 , 0
       0     .11       0   530.3     .03       0   599.2     .11       0
Bank Sta=530.3,599.2
XS Rating Curve= 0 ,0
Exp/Cntr=0.3,0.1

Type RM Length L Ch R = 1 ,4313    ,408,408,408
BEGIN DESCRIPTION:
G103-33-01 7.0
END DESCRIPTION:
XS GIS Cut Line= 3
      3923467.87     10022974.26      3922828.23     10022866.84
      3922041.79     10022703.63
#Sta/Elev= 30
  4351.4    69.6  4432.5   67.02  4564.4   65.28  4696.2   66.27  4823.2   65.45
  4858.4   62.89  4909.1   64.76  4929.4   63.33  4949.7   63.08  4959.8   61.25
  4980.1   56.91  4995.8   55.24  4999.6   55.24  5010.6   59.85    501761.18649
    5031   63.22  5104.9   66.88  5133.2   66.81    5150   65.29    5174    65.1
  5200.1   65.95  5265.9   65.08  5295.3   65.69  5445.7   65.62    5460   66.34
    5591   67.45  5684.7    66.3  5786.4   68.08  5791.5   69.13  5803.2   69.57
#Mann= 3 , 0 , 0
  4351.4     .11       0  4959.8     .03       0    5017     .11       0
Bank Sta=4959.8,5017
XS Rating Curve= 0 ,0
Exp/Cntr=0.3,0.1

Type RM Length L Ch R = 1 ,3905    ,386,386,386
BEGIN DESCRIPTION:
G103-33-01 6.0
END DESCRIPTION:
XS GIS Cut Line= 3
      3923525.16     10022724.25      3922968.23     10022516.84
      3922546.02     10022276.35
#Sta/Elev= 30
  4405.7    69.8  4411.1   69.74  4552.2   69.08  4584.2   66.84  4701.6   65.83
  4711.3   65.18  4716.7   65.81  4733.6   65.09  4827.3    65.8  4832.6   64.93
  4872.4   63.25  4904.4   63.83    4913   62.92  4957.7   62.99 4974.6360.67809
  4995.6   54.58  5003.9   55.39  5019.7   60.47    5035   61.76  5078.8    61.9
  5106.2    64.4    5122      64  5159.5   65.06  5202.7   65.46  5224.3   64.86
  5320.9   66.12  5326.6   66.85  5357.2   67.35  5391.7   70.02  5485.9   71.34
#Mann= 4 ,-1 , 0
  4405.7     .15       0  4411.1     .11       0 4974.63     .03       0
  5019.7     .11       0
Bank Sta=4974.63,5019.7
XS Rating Curve= 0 ,0
Exp/Cntr=0.3,0.1

Type RM Length L Ch R = 1 ,3519    ,150,150,150
BEGIN DESCRIPTION:
Mapping XS da939df0
END DESCRIPTION:
XS GIS Cut Line= 3
      3923535.63     10022281.56      3923048.12     10022163.88
      3922511.21     10022125.42
#Sta/Elev= 30
  4498.6   69.34  4647.7   66.98  4846.1    65.2  4928.4   65.14  4951.1   64.43
 4964.9360.64323  4979.8    56.9  4987.9    55.6    4993   55.42  4995.7   54.31
  5002.8   54.81  5010.4   58.49  5020.560.65359  5030.5   63.01  5040.5   63.69
  5050.5    63.5  5070.6   64.88  5090.6   64.53  5112.5   65.46  5130.7   65.19
  5150.8   65.74  5220.9   68.66  5247.7   69.17  5291.1   71.29  5321.2   71.62
  5351.3   71.06  5421.5   72.57  5471.6   71.39    5528   72.38  5538.4   71.87
#Mann= 3 ,-1 , 0
  4498.6     .11       0 4964.93     .03       0  5020.5     .11       0
Bank Sta=4964.93,5020.5
XS Rating Curve= 0 ,0
Exp/Cntr=0.3,0.1

Type RM Length L Ch R = 1 ,3369    ,449,449,449
BEGIN DESCRIPTION:
G103-33-01 5.0
END DESCRIPTION:
XS GIS Cut Line= 3
       3923473.1      10022125.3      3923061.65     10022026.35
      3922521.43     10022005.57
#Sta/Elev= 30
  4573.4    69.5  4599.4   69.38  4619.9   71.72  4640.5   70.91  4661.1   71.86
  4702.9   71.66  4719.6   70.71  4786.8   69.82  4815.4    68.4  4828.7   69.09
  4887.3   65.84  4938.8   65.01  4949.1   62.75  4954.6   59.22  4979.9   50.34
  4988.2   49.62  4992.1   49.62    4996   51.49  5004.6    51.5  5010.4    55.4
  5020.4   60.06  5030.4   63.41  5040.4   64.72  5140.5   66.74  5220.5   69.76
  5264.7   70.31  5330.6   69.47  5370.7   72.36  5430.7   72.92  5537.2   71.32
#Mann= 4 ,-1 , 0
  4573.4    .125       0  4719.6     .11       0  4954.6     .03       0
  5020.4     .11       0
Bank Sta=4954.6,5020.4
XS Rating Curve= 0 ,0
Exp/Cntr=0.3,0.1

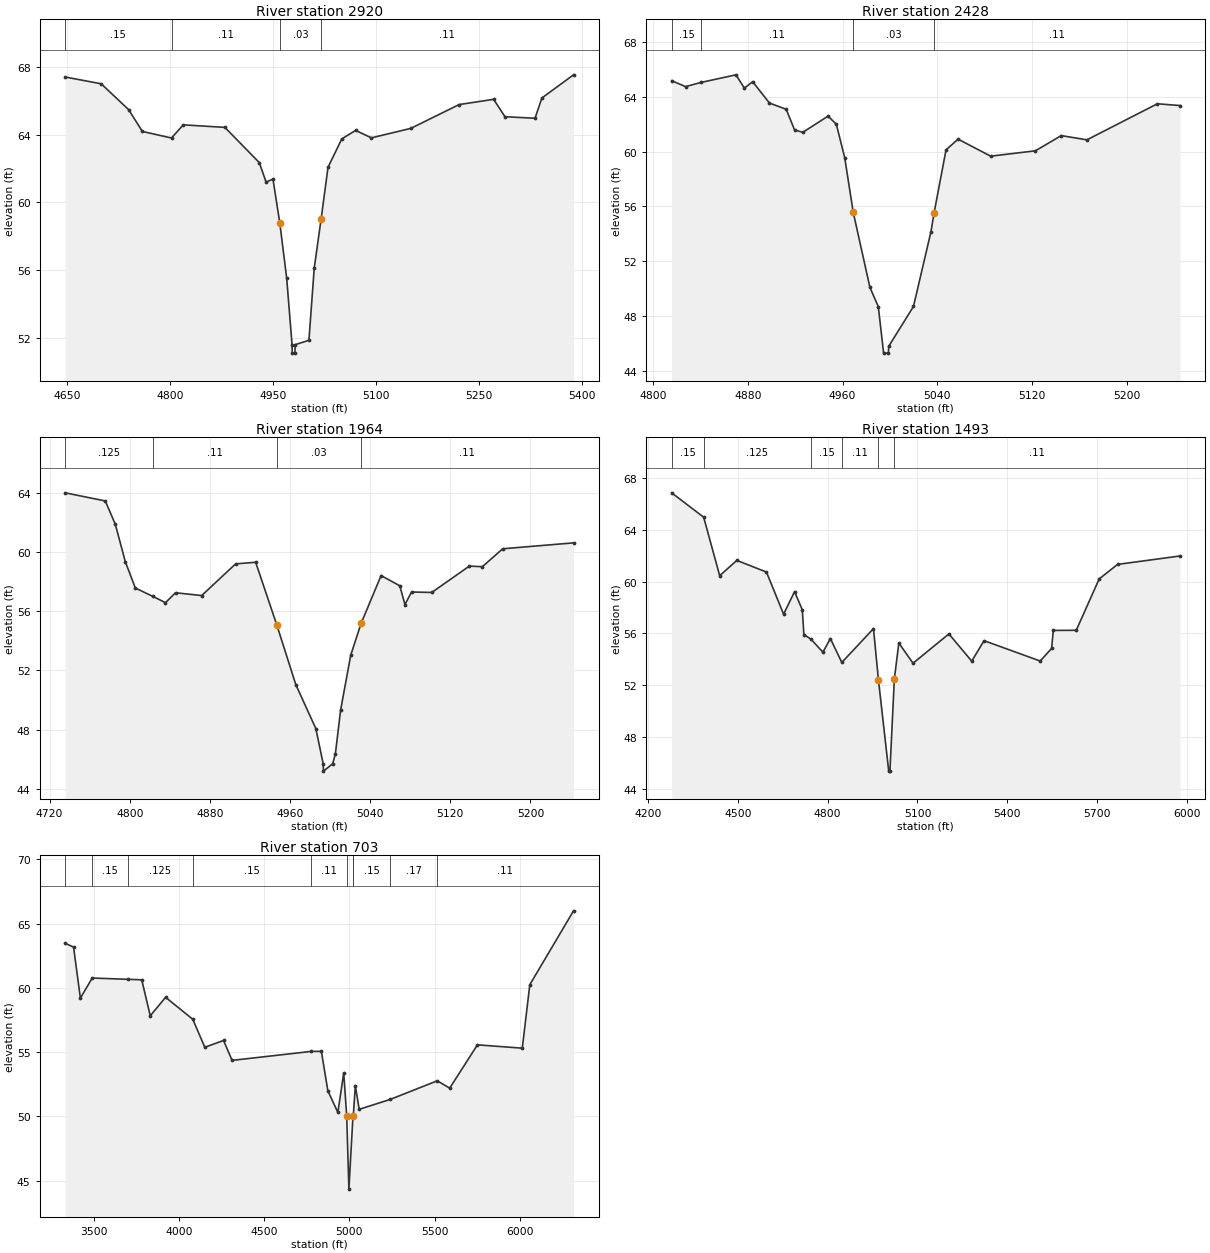
Type RM Length L Ch R = 1 ,2920    ,492,492,492
BEGIN DESCRIPTION:
G103-33-01 4.0
END DESCRIPTION:
XS GIS Cut Line= 3
      3923400.15      10021625.3      3923048.23     10021606.84
      3922662.01       10021646.
#Sta/Elev= 30
  4647.6   67.42    4700   67.02    4740   65.49    4760    64.2  4802.5   63.81
  4819.5   64.59  4880.2   64.44  4930.3   62.36  4940.3    61.2  4950.3   61.38
  4960.3   58.77  4970.3   55.51  4978.1   51.58  4978.4   51.08  4982.3   51.08
  4982.6   51.58  5002.7   51.84  5010.4    56.1  5020.5   59.03  5030.5   62.08
  5050.6   63.76  5070.7   64.26  5093.7   63.82  5151.1   64.38  5221.5   65.79
  5271.8    66.1  5288.3   65.07  5332.1   64.98  5342.1   66.18  5388.2   67.55
#Mann= 4 ,-1 , 0
  4647.6     .15       0  4802.5     .11       0  4960.3     .03       0
  5020.5     .11       0
Bank Sta=4960.3,5020.5
XS Rating Curve= 0 ,0
Exp/Cntr=0.3,0.1

Type RM Length L Ch R = 1 ,2428    ,464,464,464
BEGIN DESCRIPTION:
G103-33-01 3.0
END DESCRIPTION:
XS GIS Cut Line= 3
      3923337.69     10021318.01      3923208.23     10021186.84
      3922993.97     10021068.03
#Sta/Elev= 30
  4815.7   65.16  4827.5   64.73  4840.7   65.04    4870   65.59  4877.1   64.62
  4884.1   65.09  4898.3   63.53  4912.4   63.08  4919.5   61.57  4926.5    61.4
  4947.8   62.58  4954.8   61.98  4961.9   59.52    4969   55.58  4983.1    50.1
  4990.2   48.69  4994.7    45.3  4998.7    45.3    4999    45.8  5019.9    48.7
  5034.7   54.16 5037.2555.49035  5047.4   60.12  5057.6    60.9  5085.1   59.66
  5122.9   60.05  5144.7   61.16  5166.4   60.85  5225.9   63.48    5245   63.35
#Mann= 4 ,-1 , 0
  4815.7     .15       0  4840.7     .11       0    4969     .03       0
 5037.25     .11       0
Bank Sta=4969,5037.25
XS Rating Curve= 0 ,0
Exp/Cntr=0.3,0.1

Type RM Length L Ch R = 1 ,1964    ,471,471,471
BEGIN DESCRIPTION:
G103-33-01 2.0
END DESCRIPTION:
XS GIS Cut Line= 3
      3923517.85     10021111.07      3923508.23     10020846.84
      3923267.88     10020811.08
#Sta/Elev= 30
  4735.6   63.99  4775.6   63.44  4785.6   61.87  4795.6   59.34  4805.6   57.56
  4823.2   56.99  4835.7   56.57  4845.7   57.24  4871.8   57.05  4905.7   59.19
  4925.7    59.3 4946.8455.05789  4965.8   51.03  4985.8   48.06  4993.1   45.69
  4993.4   45.19  5002.6   45.69  5005.3   46.37  5010.5   49.31  5020.6   53.02
 5030.9255.16286  5050.9    58.4  5069.6   57.71  5074.7   56.44  5081.3   57.29
  5101.5   57.26    5139   59.04    5152      59  5172.3   60.21    5243   60.61
#Mann= 4 ,-1 , 0
  4735.6    .125       0  4823.2     .11       0 4946.84     .03       0
 5030.92     .11       0
Bank Sta=4946.84,5030.92
XS Rating Curve= 0 ,0
Exp/Cntr=0.3,0.1

Type RM Length L Ch R = 1 ,1493    ,790,790,790
BEGIN DESCRIPTION:
Mapping XS 73fe18bd
END DESCRIPTION:
XS GIS Cut Line= 3
      3924134.55      10021338.8      3923832.48     10020458.64
      3923131.09     10020770.37
#Sta/Elev= 30
    4279   66.84  4385.9   64.96  4439.4   60.45  4496.6   61.63  4595.7   60.73
  4652.9   57.48  4689.5   59.22  4715.4   57.82  4720.7   55.91  4744.7   55.55
  4784.1   54.55  4809.2    55.6  4847.4   53.76  4953.2   56.37 4969.7352.41198
  5004.1   45.38  5008.1   45.38  5022.8   52.47  5037.8   55.26  5085.3    53.7
  5205.1   55.96  5281.4   53.86  5322.5   55.44  5510.1   53.87  5548.2   54.84
  5553.9   56.23  5630.5   56.24  5707.1    60.2  5768.4   61.32  5977.1   61.97
#Mann= 6 ,-1 , 0
    4279     .15       0  4385.9    .125       0  4744.7     .15       0
  4847.4     .11       0 4969.73     .03       0  5022.8     .11       0
Bank Sta=4969.73,5022.8
XS Rating Curve= 0 ,0
Exp/Cntr=0.3,0.1

Type RM Length L Ch R = 1 ,703     ,0,0,0
BEGIN DESCRIPTION:
G103-33-01 1.0
END DESCRIPTION:
XS GIS Cut Line= 3
      3924389.78     10021370.08      3924415.82     10019927.39
      3923062.27     10020661.43
#Sta/Elev= 30
  3332.3   63.47  3381.3   63.18  3421.3   59.21    3491   60.77  3698.2   60.67
  3781.4   60.63  3831.4   57.83  3921.4   59.27  4080.9   57.56  4151.4   55.38
  4261.5   55.91  4311.5   54.36  4776.8   55.06  4835.4   55.06  4873.5   51.99
  4932.2   50.31  4966.6   53.39 4984.0950.01196  4996.9   44.34 5020.7850.01337
  5023.7   50.22  5034.6   52.39  5057.3   50.55  5240.9   51.33  5515.4   52.77
  5588.4    52.2  5751.2   55.57  6014.3   55.31  6058.4   60.25    6315      66
#Mann= 11 ,-1 , 0
  3332.3    .125       0    3491     .15       0  3698.2    .125       0
  4080.9     .15       0  4776.8     .11       0 4984.09     .03       0
 5020.78     .08       0  5023.7     .11       0  5023.7     .15       0
  5240.9     .17       0  5515.4     .11       0
Bank Sta=4984.09,5020.78
XS Rating Curve= 0 ,0
Exp/Cntr=0.3,0.1

Chan Stop Cuts=-1
Use User Specified Reach Order=0
Composite Channel Slope=5